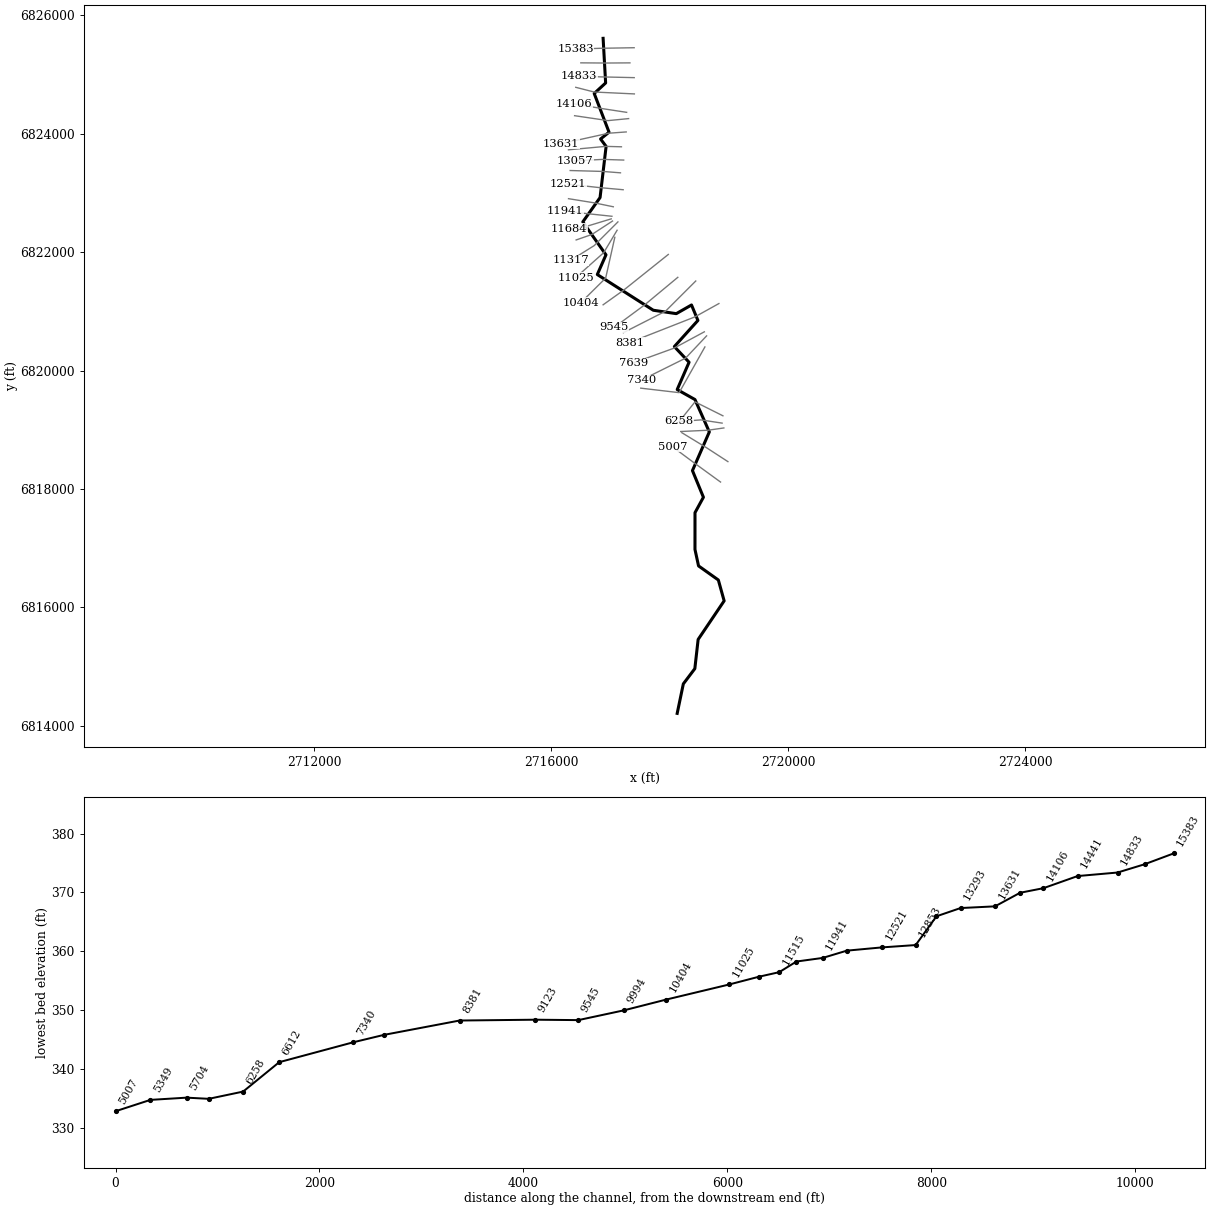
--- Little Dry Branch.prj (project) ---

Proj Title=Little Dry Branch Base Level Engineering
Current Plan=p01
Default Exp/Contr=0.3,0.1
English Units
Geom File=g01
Flow File=f01
Plan File=p01
Y Axis Title=Elevation
X Axis Title(PF)=Main Channel Distance
X Axis Title(XS)=Station
BEGIN DESCRIPTION:
Little Dry Branch
END DESCRIPTION:
DSS File=dss
DSS Export Rating Curves= 0
DSS Export Rating Curve Sorted= 0
DSS Export Volume Flow Curves= 0
DXF OffsetX= 0
DXF OffsetY= 0
DXF ScaleX= 1
DXF ScaleY= 10

--- Little Dry Branch.p01 (plan) ---

Plan Title=Multiple Run
Program Version=4.10
Short Identifier=Multiple Run
Geom File=g01
Flow File=f01
Subcritical Flow
K Sum by GR= 0
Std Step Tol= 0.01
Critical Tol= 0.01
Num of Std Step Trials= 20
Max Error Tol= 0.3
Flow Tol Ratio= 0.001
Split Flow NTrial= 30
Split Flow Tol= 0.02
Split Flow Ratio= 0.02
Log Output Level= 0
Friction Slope Method= 1
Unsteady Friction Slope Method= 2
Unsteady Bridges Friction Slope Method= 1
Parabolic Critical Depth
Global Vel Dist= 1 , 1 , 1
Global Log Level= 0
CheckData=True
Encroach Param=-1 ,0,0, 0
BEGIN DESCRIPTION:
Multiple Run
END DESCRIPTION:
Computation Interval=1HOUR
Output Interval=1HOUR
Run HTab= 0
Run UNet= 0
Run PostProcess= 0
Run WQNet= 0
UNET Theta= 1
UNET Theta Warmup= 1
UNET ZTol= 0.02
UNET ZSATol= 0.05
UNET MxIter= 20
UNET MaxInSteps= 0
UNET DtIC= 0
UNET DtMin= 0
UNET MaxCRTS= 20
UNET WFStab= 2
UNET SFStab= 1
UNET WFX= 1
UNET SFX= 1
UNET DSS MLevel= 4
UNET DZMax Abort= 100
UNET Convert EG Bridges= 0
UNET Use Existing IB Tables=-1
UNET Froude Reduction=False
UNET Froude Limit= 1
UNET Froude Power= 10
UNET Time Slicing=0,0, 5
UNET Junction Losses=0
Instantaneous Interval=1HOUR
DSS File=dss
Write IC File= 0
Write IC File at Sim End=0
Echo Input=False
Echo Parameters=False
Echo Output=False
Write Detailed= 0
WQ AD Non Conservative
WQ ULTIMATE=-1
WQ Max Comp Step=1HOUR
WQ Output Interval=15MIN
WQ Output Selected Increments= 0
WQ Output face flow=0
WQ Output face velocity=0
WQ Output face area=0
WQ Output face dispersion=0
WQ Output cell volume=0
WQ Output cell surface area=0
WQ Output cell continuity=0
WQ Output cumulative cell continuity=0
WQ Output face conc=0
WQ Output face dconc_dx=0
WQ Output face courant=0
WQ Output face peclet=0
WQ Output face adv mass=0
WQ Output face disp mass=0
WQ Output cell mass=0
WQ Output cell source sink temp=0
WQ Output cell source sink nsm=0
WQ Output MaxMinRange=-1
WQ Daily Max Min Mean=-1
WQ Daily Range=0
WQ Daily Time=0
WQ Create Restart=0
WQ Fixed Restart=0
WQ System Summary=0
WQ Use Fixed Temperature=0
Sorting and Armoring Iterations= 10
XS Update Threshold= 0.02
Hydraulics Update Threshold= 0.02
Energy Slope Method= 1
Volume Change Method= 0
XS Weighting Method= 0
Number of US Weighted Cross Sections= 1
Number of DS Weighted Cross Sections= 1
Upstream XS Weight=0.25
Main XS Weight=0.5
Downstream XS Weight=0.25
Number of DS XS's Weighted with US Boundary= 1
Upstream Boundary Weight= 1
Weight of XSs Associated with US Boundary= 0
Number of US XS's Weighted with DS Boundary= 1
Downstream Boundary Weight= 0.5
Weight of XSs Associated with DS Boundary= 0.5
Sediment Output Level= 4
Mass or Volume Output= 0
Output Increment Type= 1
Profile and TS Output Increment= 10
XS Output Flag= 0
XS Output Increment= 10
Disregard all LS=0
Disregard all Conn=0
Disregard all Breaches=0
Disregard all Pumps=0

--- Little Dry Branch.f01 (steady flow) ---

Flow Title=Multiple
Number of Profiles=7
Profile Names=10-year,25-year,50-year,1pct_min,100-year,1pct_plu,500-year
River Rch & RM= Little Dry Branc,Reach-1,15383
     652     875    1056     632    1261    2517    1798
River Rch & RM= Little Dry Branc,Reach-1,11317
     725     979    1186     712    1420    2834    2038
River Rch & RM= Little Dry Branc,Reach-1,9994
    1110    1528    1874    1138    2270    4529    3329
River Rch & RM= Little Dry Branc,Reach-1,6258
    1342    1859    2288    1392    2778    5542    4096
Boundary for River Rch & Prof#=Little Dry Branc,Reach-1,1
Up Type=0
Dn Type=3
Dn Slope=0.005
Boundary for River Rch & Prof#=Little Dry Branc,Reach-1,2
Up Type=0
Dn Type=3
Dn Slope=0.005
Boundary for River Rch & Prof#=Little Dry Branc,Reach-1,3
Up Type=0
Dn Type=3
Dn Slope=0.005
Boundary for River Rch & Prof#=Little Dry Branc,Reach-1,4
Up Type=0
Dn Type=3
Dn Slope=0.005
Boundary for River Rch & Prof#=Little Dry Branc,Reach-1,5
Up Type=0
Dn Type=3
Dn Slope=0.005
Boundary for River Rch & Prof#=Little Dry Branc,Reach-1,6
Up Type=0
Dn Type=3
Dn Slope=0.005
Boundary for River Rch & Prof#=Little Dry Branc,Reach-1,7
Up Type=0
Dn Type=3
Dn Slope=0.005

--- Little Dry Branch.g01 (geometry) ---

Geom Title=Existing Conditions
Program Version=4.10

River Reach=Little Dry Branc,Reach-1
Reach XY= 30
        2716876.        6825611.       2716918.5      6824857.42
      2716725.63      6824679.41      2716976.04      6824026.24
        2716833.      6823911.22      2716926.49      6823786.04
      2716824.58      6822922.34      2716533.31       6822510.9
      2716924.25      6821954.89      2716777.83      6821622.13
      2717722.68      6821019.04       2718110.8      6820961.48
      2718367.68      6821108.04      2718475.76       6820846.9
      2718077.97       6820405.1      2718326.47      6820140.84
      2718125.92      6819679.29        2718426.        6819511.
      2718668.38      6818964.33      2718383.56        6818311.
      2718568.68       6817861.1      2718426.61      6817600.38
      2718426.21      6816979.27      2718486.48       6816701.2
      2718820.55      6816463.47      2718918.47      6816111.01
      2718479.61       6815459.5      2718423.82      6814966.45
      2718229.75      6814709.45        2718126.        6814211.

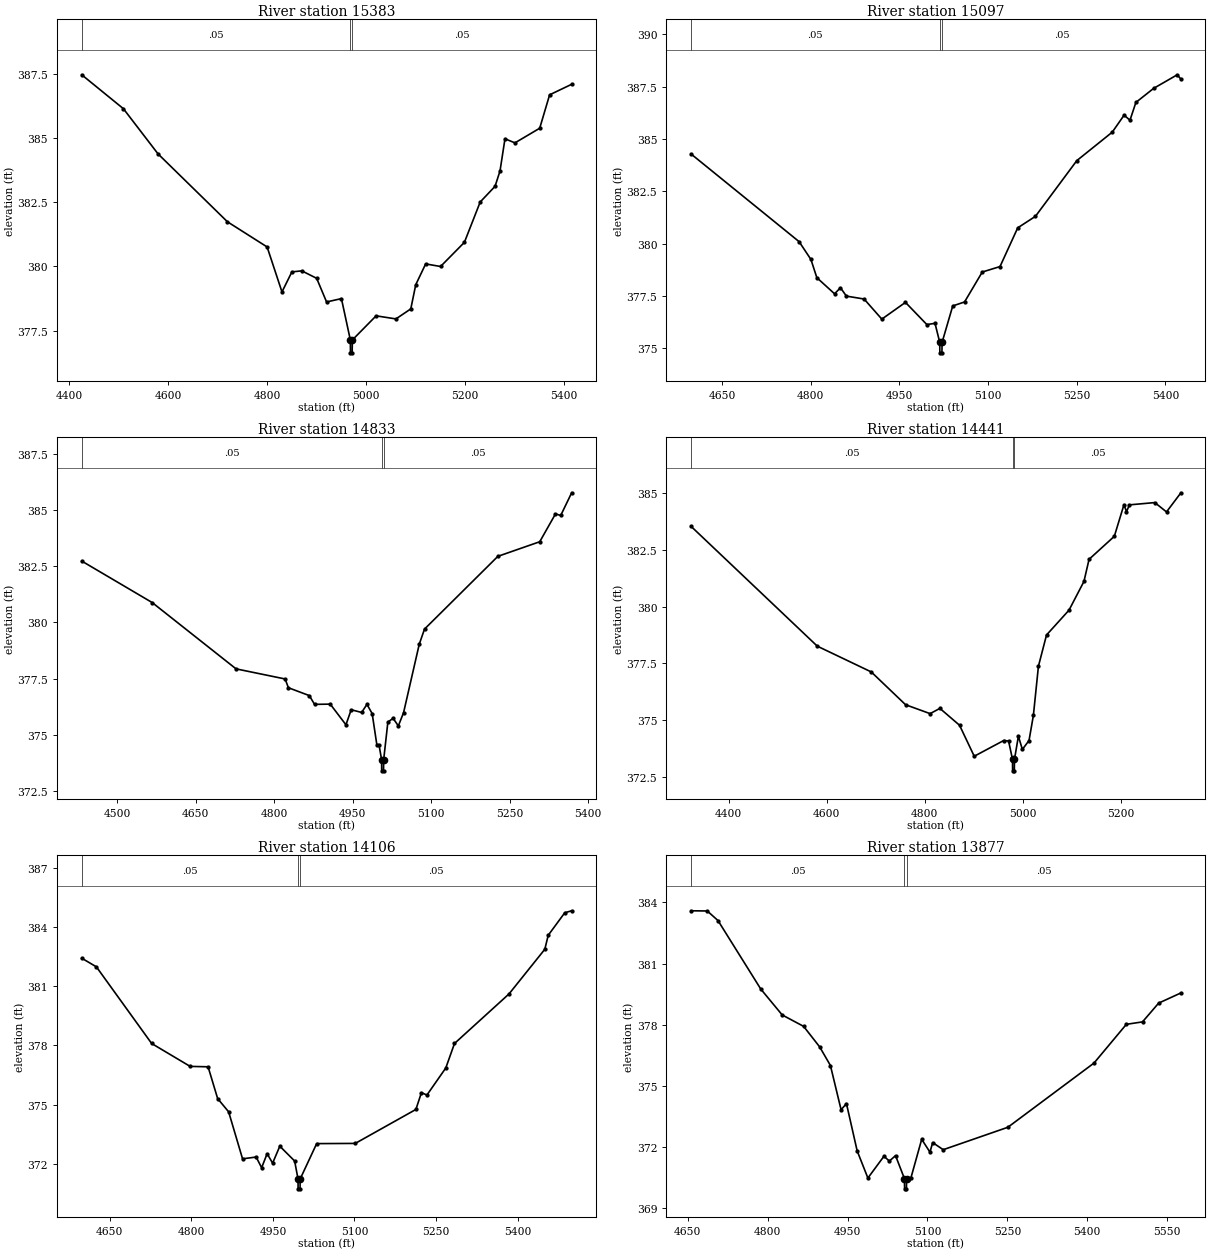
Type RM Length L Ch R = 1 ,15383   ,286,286,286
BEGIN DESCRIPTION:
Little Dry Branch15383.084
END DESCRIPTION:
XS GIS Cut Line= 3
       2717400.1      6825452.56      2716826.18      6825442.73
      2716411.51      6825428.88
#Sta/Elev= 30
    4426  387.46  4510.1  386.14  4580.1  384.38  4720.1  381.74  4800.2  380.76
  4830.2  379.01  4850.2  379.79  4870.2  379.83  4900.2  379.54  4920.2  378.62
  4950.2  378.75  4968.2  377.14  4968.4  376.64  4971.9  376.64  4972.2  377.14
  5020.2  378.08  5060.2  377.96  5090.2  378.35  5100.2  379.29  5120.2   380.1
  5150.3     380  5198.4  380.94  5230.3  382.51  5260.3  383.12  5270.3  383.72
  5280.3  384.97  5300.4  384.81  5350.4  385.38  5370.4  386.68  5414.9  387.09
#Mann= 3 ,-1 , 0
    4426     .05       0  4968.2     .05       0  4972.2     .05       0
Bank Sta=4968.2,4972.2
XS Rating Curve= 0 ,0
Exp/Cntr=0.3,0.1

Type RM Length L Ch R = 1 ,15097   ,264,264,264
BEGIN DESCRIPTION:
Little Dry Branch15096.82
END DESCRIPTION:
XS GIS Cut Line= 3
      2717328.97      6825196.67       2716928.5      6825193.92
      2716499.79      6825196.98
#Sta/Elev= 30
  4597.2  384.29  4780.2   380.1  4800.2  379.25  4810.2  378.38  4840.2  377.61
  4850.2   377.9  4860.2   377.5  4890.2  377.36  4920.2   376.4  4960.2   377.2
  4996.4  376.14  5010.2   376.2  5018.2  375.29  5018.4  374.79  5021.9  374.79
  5022.2  375.29  5040.2  377.03  5060.2  377.22  5090.2  378.65  5120.2  378.91
  5150.2  380.76  5180.2  381.31  5250.2  383.97  5310.2  385.33  5330.2  386.14
  5340.2   385.9  5350.2  386.75  5380.2  387.42  5420.2  388.07  5426.4  387.86
#Mann= 3 ,-1 , 0
  4597.2     .05       0  5018.2     .05       0  5022.2     .05       0
Bank Sta=5018.2,5022.2
XS Rating Curve= 0 ,0
Exp/Cntr=0.3,0.1

Type RM Length L Ch R = 1 ,14833   ,392,392,392
BEGIN DESCRIPTION:
Little Dry Branch14832.59
END DESCRIPTION:
XS GIS Cut Line= 3
      2717400.81      6824947.23      2716832.85      6824960.09
      2716465.08      6824975.42
#Sta/Elev= 30
  4432.5  382.73  4567.3  380.88  4727.4  377.93  4821.2  377.48  4827.4  377.09
  4867.4  376.74  4877.4  376.35  4907.4  376.36  4937.4  375.44  4947.4  376.11
  4967.4  375.99  4977.5  376.35  4987.5  375.94  4996.5  374.54  5000.6  374.54
  5005.5  373.89  5005.7  373.39  5009.2  373.39  5009.5  373.89  5017.5  375.56
  5027.5  375.73  5037.5  375.39  5047.5  375.98  5077.5  379.03  5087.5   379.7
  5227.7  382.94  5307.7  383.59  5337.8  384.83  5347.8  384.76  5368.7  385.77
#Mann= 3 ,-1 , 0
  4432.5     .05       0  5005.5     .05       0  5009.5     .05       0
Bank Sta=5005.5,5009.5
XS Rating Curve= 0 ,0
Exp/Cntr=0.3,0.1

Type RM Length L Ch R = 1 ,14441   ,335,335,335
BEGIN DESCRIPTION:
Little Dry Branch14441.41
END DESCRIPTION:
XS GIS Cut Line= 3
      2717403.47      6824672.37      2716724.84      6824704.33
      2716414.32      6824783.76
#Sta/Elev= 30
  4323.2  383.52    4581  378.26  4691.1  377.13  4761.2  375.69  4811.2   375.3
  4831.2  375.53  4871.3  374.79  4901.3  373.43  4961.4  374.12  4971.4   374.1
  4979.4  373.29  4979.6  372.79  4983.1  372.79  4983.4  373.29  4991.4  374.31
  4999.5  373.73  5013.1  374.12    5022  375.22  5032.3  377.38  5048.8  378.75
  5094.7  379.84  5125.2   381.1  5135.6  382.07  5187.2  383.08  5206.9  384.47
    5212  384.16  5218.1  384.46  5269.8  384.56  5293.7  384.15  5323.1  384.99
#Mann= 3 ,-1 , 0
  4323.2     .05       0  4979.4     .05       0  4983.4     .05       0
Bank Sta=4979.4,4983.4
XS Rating Curve= 0 ,0
Exp/Cntr=0.3,0.1

Type RM Length L Ch R = 1 ,14106   ,229,229,229
BEGIN DESCRIPTION:
Little Dry Branch14106.03
END DESCRIPTION:
XS GIS Cut Line= 3
       2717273.1       6824361.2      2716874.81      6824422.15
      2716383.46      6824504.34
#Sta/Elev= 30
  4598.4  382.41  4625.4  381.97    4727  378.09  4797.8  376.93  4830.8  376.91
  4848.4   375.3  4868.6  374.63  4894.2  372.25  4919.2  372.34  4929.3   371.8
  4939.4  372.51  4949.5  372.03  4962.7  372.89    4990  372.14  4996.2  371.23
  4996.4  370.73  4999.9  370.73  5000.2  371.23  5030.5  373.02  5101.5  373.03
    5213  374.75  5223.2   375.6  5233.3  375.48    5268  376.85    5284  378.09
  5384.3   380.6  5450.1  382.86  5456.4  383.57  5486.8  384.71  5499.5  384.81
#Mann= 3 ,-1 , 0
  4598.4     .05       0  4996.2     .05       0  5000.2     .05       0
Bank Sta=4996.2,5000.2
XS Rating Curve= 0 ,0
Exp/Cntr=0.3,0.1

Type RM Length L Ch R = 1 ,13877   ,246,246,246
BEGIN DESCRIPTION:
Little Dry Branch13877.24
END DESCRIPTION:
XS GIS Cut Line= 3
      2717306.41      6824255.48      2716958.81      6824221.48
      2716394.66      6824304.58
#Sta/Elev= 30
  4656.2  383.59  4686.8  383.58  4706.9  383.11  4787.2  379.75  4827.4  378.48
  4867.6  377.92  4897.8  376.91  4917.9     376  4937.9  373.83    4948  374.13
  4968.1  371.81  4988.2  370.48  5018.4  371.55  5028.5  371.31  5040.1  371.58
  5056.8  370.45  5057.1  369.95  5060.6  369.95  5060.8  370.45  5068.9  370.48
  5089.2  372.38  5104.7  371.75  5109.8  372.22  5129.6  371.87  5250.9  372.97
  5412.6  376.12  5473.3  378.02  5503.6  378.14  5533.9  379.06  5575.7  379.56
#Mann= 3 ,-1 , 0
  4656.2     .05       0  5056.8     .05       0  5060.8     .05       0
Bank Sta=5056.8,5060.8
XS Rating Curve= 0 ,0
Exp/Cntr=0.3,0.1

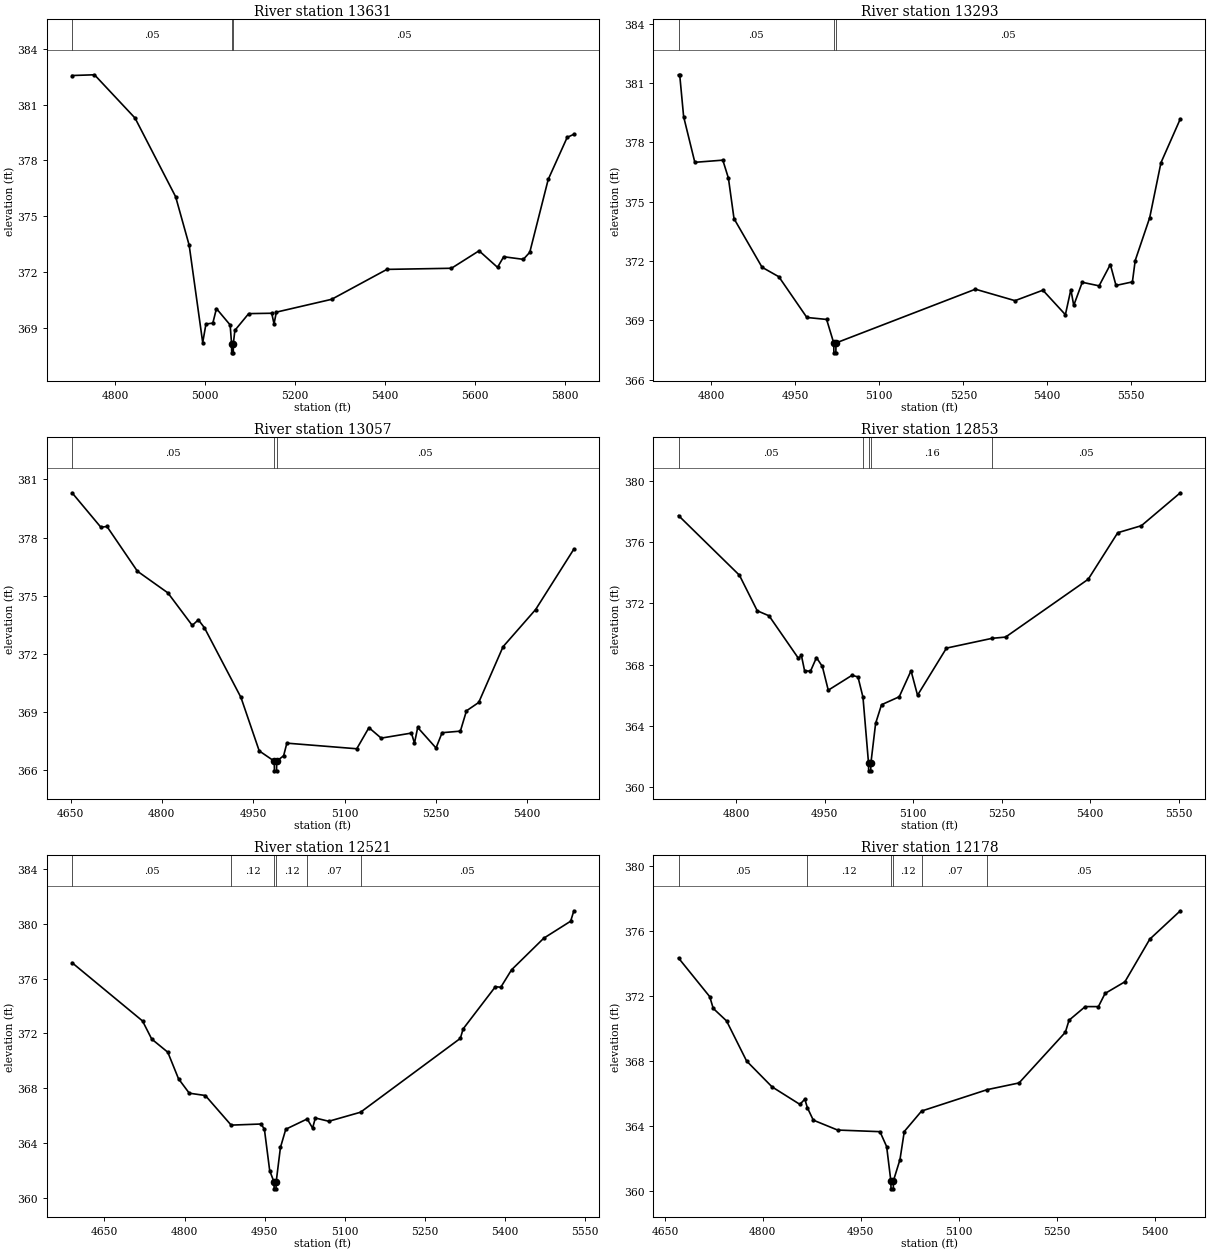
Type RM Length L Ch R = 1 ,13631   ,338,338,338
BEGIN DESCRIPTION:
Little Dry Branch13631.49
END DESCRIPTION:
XS GIS Cut Line= 3
      2717265.62      6824030.27      2716966.67      6824008.22
      2716170.31      6823831.94
#Sta/Elev= 30
  4704.6  382.56  4754.4   382.6  4844.6  380.27  4934.8  376.04  4964.9  373.43
    4995  368.19  5002.2  369.19  5017.5  369.24  5025.5  370.02    5056  369.14
  5059.1  368.14  5059.4  367.64  5062.9  367.64  5063.1  368.14  5066.5  368.85
  5097.2  369.75  5148.4  369.77  5153.5   369.2  5158.7  369.83  5281.6  370.52
  5404.5  372.13  5547.9  372.19  5609.3  373.13  5650.3  372.24    5664  372.81
  5707.7  372.67    5722  373.05    5763  376.97  5805.1  379.23    5820   379.4
#Mann= 3 ,-1 , 0
  4704.6     .05       0  5059.1     .05       0  5063.1     .05       0
Bank Sta=5059.1,5063.1
XS Rating Curve= 0 ,0
Exp/Cntr=0.3,0.1

Type RM Length L Ch R = 1 ,13293   ,236,236,236
BEGIN DESCRIPTION:
Little Dry Branch13292.85
END DESCRIPTION:
XS GIS Cut Line= 3
       2717185.1      6823779.47      2716920.35      6823786.35
      2716291.54      6823728.55
#Sta/Elev= 30
  4741.3  381.42  4743.4  381.42  4750.4   379.3  4770.4  376.99  4820.4   377.1
  4830.4  376.19  4840.4  374.14  4890.5  371.68  4920.5   371.2  4970.5  369.14
  5005.8  369.04  5018.5  367.85  5018.8  367.35  5022.3  367.35  5022.5  367.85
  5271.6  370.57  5342.3  369.99  5392.1  370.52  5432.3  369.28  5442.1  370.55
  5447.2  369.75  5462.4  370.92  5492.5  370.74  5512.6  371.82  5522.7  370.76
    5552  370.94    5557  372.02  5582.9  374.19    5603  376.97  5637.6  379.19
#Mann= 3 ,-1 , 0
  4741.3     .05       0  5018.5     .05       0  5022.5     .05       0
Bank Sta=5018.5,5022.5
XS Rating Curve= 0 ,0
Exp/Cntr=0.3,0.1

Type RM Length L Ch R = 1 ,13057   ,204,204,204
BEGIN DESCRIPTION:
Little Dry Branch13056.68
END DESCRIPTION:
XS GIS Cut Line= 3
      2717223.29      6823555.23      2716870.31      6823566.56
      2716399.87      6823542.75
#Sta/Elev= 30
  4652.5  380.31  4699.8  378.53  4709.8  378.57  4759.8  376.26  4809.9  375.14
  4849.9  373.46  4859.9  373.75  4869.9  373.34  4929.9  369.74  4959.9  366.98
  4984.6  366.45  4984.9  365.95  4988.4  365.95  4988.6  366.45    5000  366.73
  5005.3  367.38  5120.1  367.09  5140.1  368.18  5160.2  367.64  5209.9   367.9
  5214.9  367.38  5220.2  368.19  5250.3  367.13  5260.3  367.92  5290.3     368
  5300.3  369.05  5320.4  369.48  5360.4  372.36  5413.9  374.28  5476.7   377.4
#Mann= 3 ,-1 , 0
  4652.5     .05       0  4984.6     .05       0  4988.6     .05       0
Bank Sta=4984.6,4988.6
XS Rating Curve= 0 ,0
Exp/Cntr=0.3,0.1

Type RM Length L Ch R = 1 ,12853   ,332,332,332
BEGIN DESCRIPTION:
Little Dry Branch12852.9
END DESCRIPTION:
XS GIS Cut Line= 3
      2717168.84      6823339.74      2716870.71      6823363.16
      2716320.08      6823378.55
#Sta/Elev= 30
  4702.6  377.74  4805.8  373.84  4835.9  371.52  4855.9  371.19  4905.7  368.41
  4910.7   368.6  4916.1   367.6  4926.1  367.57  4936.2  368.46  4946.2  367.88
  4956.2  366.33  4996.3   367.3  5006.5   367.2    5015  365.87  5024.4  361.56
  5024.6  361.06  5028.1  361.06  5028.4  361.56  5036.4  364.16  5046.4  365.38
  5076.4   365.9  5096.4   367.6  5107.4     366  5156.4  369.08  5233.8  369.72
  5256.5   369.8  5396.5  373.58  5446.5  376.62  5486.6  377.08  5552.5  379.23
#Mann= 5 ,-1 , 0
  4702.6     .05       0    5015     .16       0  5024.4     .05       0
  5028.4     .16       0  5233.8     .05       0
Bank Sta=5024.4,5028.4
XS Rating Curve= 0 ,0
Exp/Cntr=0.3,0.1

Type RM Length L Ch R = 1 ,12521   ,343,343,343
BEGIN DESCRIPTION:
Little Dry Branch12521.24
END DESCRIPTION:
XS GIS Cut Line= 3
      2717214.51      6823054.33      2716794.74      6823092.26
        2716280.      6823149.52
#Sta/Elev= 30
  4589.5  377.16  4721.4  372.91  4738.6  371.59  4768.7  370.63  4788.8  368.69
  4808.9  367.64    4839  367.47  4887.3  365.31  4942.9  365.39  4949.5  365.03
  4959.5  361.98  4967.6  361.16  4967.8  360.66  4971.3  360.66  4971.6  361.16
  4979.6  363.68  4989.6  365.01  5029.7  365.76  5039.8  365.09  5044.9  365.83
  5070.1  365.59  5129.5  366.25  5316.4  371.64  5321.6  372.33    5382  375.41
  5392.1  375.37  5412.2  376.64  5472.6  378.95  5522.9  380.19  5528.9  380.95
#Mann= 6 ,-1 , 0
  4589.5     .05       0  4887.3     .12       0  4967.6     .07       0
  4971.6     .12       0  5029.7     .07       0  5129.5     .05       0
Bank Sta=4967.6,4971.6
XS Rating Curve= 0 ,0
Exp/Cntr=0.3,0.1

Type RM Length L Ch R = 1 ,12178   ,237,237,237
BEGIN DESCRIPTION:
Little Dry Branch12178.43
END DESCRIPTION:
XS GIS Cut Line= 3
      2717047.99      6822766.32      2716724.53      6822833.33
      2716292.24      6822903.02
#Sta/Elev= 30
  4670.9  374.32  4718.7  371.94    4724  371.22  4744.4  370.45  4775.1  367.98
    4814  366.39  4856.7  365.31  4864.2  365.63  4868.2   365.1  4877.2  364.34
  4914.4  363.73  4979.3  363.63  4989.5  362.71  4995.9  360.61  4996.2  360.11
  4999.7  360.11  4999.9  360.61  5009.9  361.91  5016.5  363.64    5043   364.9
  5143.7  366.22  5192.2  366.63  5263.1  369.75  5268.7  370.49  5293.5  371.33
  5313.7  371.33  5323.9  372.14  5354.3  372.86  5392.3  375.48  5439.1  377.23
#Mann= 6 ,-1 , 0
  4670.9     .05       0  4868.2     .12       0  4995.9     .07       0
  4999.9     .12       0    5043     .07       0  5143.7     .05       0
Bank Sta=4995.9,4999.9
XS Rating Curve= 0 ,0
Exp/Cntr=0.3,0.1

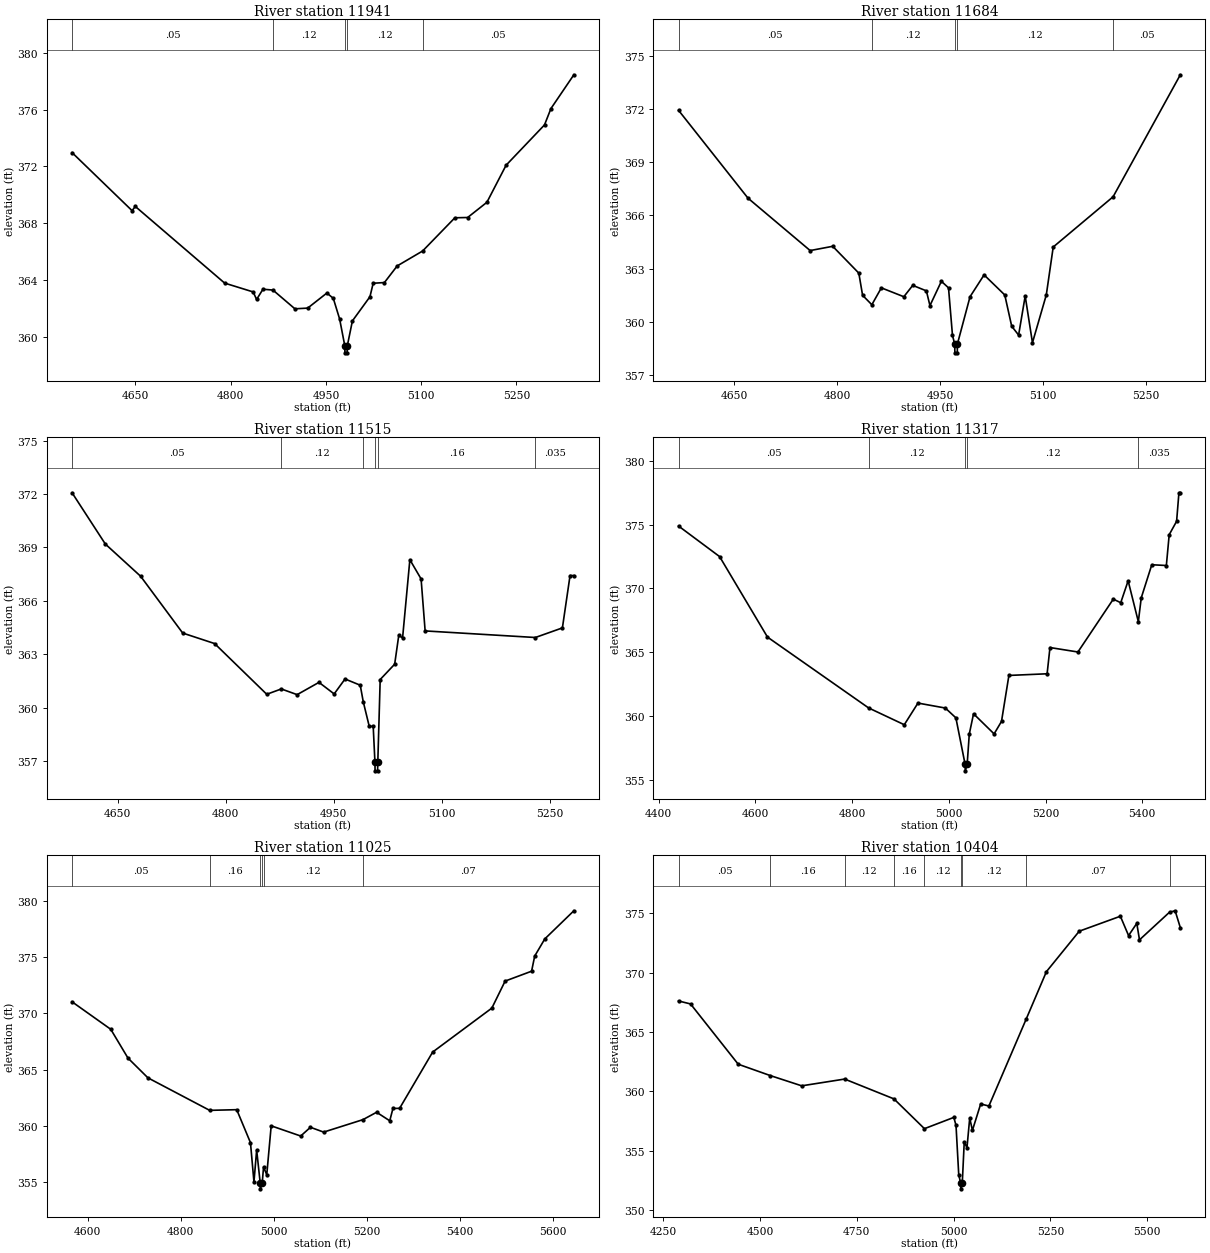
Type RM Length L Ch R = 1 ,11941   ,257,257,257
BEGIN DESCRIPTION:
Little Dry Branch11941.3
END DESCRIPTION:
XS GIS Cut Line= 3
      2717024.87      6822606.03      2716571.76      6822654.03
      2716240.14      6822695.89
#Sta/Elev= 30
  4550.4  372.97  4644.9  368.88  4649.9  369.18  4790.6  363.78  4835.4  363.16
  4840.9  362.63  4850.9  363.35  4866.6  363.29  4901.2  361.97  4921.3  362.02
  4951.5  363.08  4961.6  362.71  4971.6  361.25  4979.7  359.37  4979.9  358.87
  4983.4  358.87  4983.7  359.37  4991.7  361.12  5019.3  362.82  5024.4  363.77
  5042.1  363.82  5062.2  364.99  5102.2  366.04    5153  368.38  5173.1   368.4
  5203.4  369.47  5233.6  372.08  5294.1  374.92  5304.2  376.07  5340.3  378.45
#Mann= 5 ,-1 , 0
  4550.4     .05       0  4866.6     .12       0  4979.7     .07       0
  4983.7     .12       0  5102.2     .05       0
Bank Sta=4979.7,4983.7
XS Rating Curve= 0 ,0
Exp/Cntr=0.3,0.1

Type RM Length L Ch R = 1 ,11684   ,169,169,169
BEGIN DESCRIPTION:
Little Dry Branch11683.96
END DESCRIPTION:
XS GIS Cut Line= 3
      2717012.97      6822562.46        2716597.      6822435.98
      2716302.08       6822396.7
#Sta/Elev= 30
  4568.4  371.92  4669.8  366.97  4760.5  364.02  4793.4  364.26  4831.5  362.75
    4837   361.5  4850.5  360.97  4864.4  361.92  4897.2  361.42  4910.2  362.06
  4930.1  361.75  4935.3  360.92    4952  362.29  4962.4  361.92  4968.2  359.24
  4971.4  358.76  4971.7  358.26  4975.2  358.26  4975.4  358.76  4993.8  361.42
  5014.3  362.65  5044.5  361.52  5054.6  359.76  5064.7  359.26  5074.3  361.46
  5084.9  358.83  5105.1  361.52  5115.2  364.22  5202.6  367.05  5300.7  373.92
#Mann= 5 ,-1 , 0
  4568.4     .05       0  4850.5     .12       0  4971.4     .07       0
  4975.4     .12       0  5202.6     .05       0
Bank Sta=4971.4,4975.4
XS Rating Curve= 0 ,0
Exp/Cntr=0.3,0.1

Type RM Length L Ch R = 1 ,11515   ,198,198,198
BEGIN DESCRIPTION:
Little Dry Branch11514.76
END DESCRIPTION:
XS GIS Cut Line= 3
      2717034.66      6822525.49      2716687.16      6822298.87
      2716421.03      6822206.13
#Sta/Elev= 30
  4586.8  372.07    4633  369.19    4682  367.38  4740.4  364.19  4784.7   363.6
  4857.1  360.75  4877.3  361.05  4899.3  360.73  4929.6  361.42  4950.7  360.77
  4965.8  361.61  4986.9  361.26  4991.1  360.33  4999.4  358.95  5004.9  358.95
  5007.3  356.95  5007.5  356.45    5011  356.45  5011.3  356.95  5014.6  361.58
  5034.7  362.44  5040.4  364.06  5045.7  363.92  5055.8  368.31  5071.4  367.23
    5077  364.31    5230  363.94  5267.6  364.48  5278.2  367.42  5283.5  367.42
#Mann= 6 ,-1 , 0
  4586.8     .05       0  4877.3     .12       0  4991.1     .16       0
  5007.3     .07       0  5011.3     .16       0    5230    .035       0
Bank Sta=5007.3,5011.3
XS Rating Curve= 0 ,0
Exp/Cntr=0.3,0.1

Type RM Length L Ch R = 1 ,11317   ,292,292,292
BEGIN DESCRIPTION:
Little Dry Branch11317.006
END DESCRIPTION:
XS GIS Cut Line= 3
      2717126.01      6822511.01        2716726.        6822111.
        2716326.        6821861.
#Sta/Elev= 30
  4441.3   374.9  4526.2   372.5  4625.2  366.18  4834.2  360.62    4908   359.3
  4936.3     361  4992.9  360.61  5014.7  359.84  5033.8  356.18  5034.1  355.68
    5038  356.18  5042.4  358.57  5051.2  360.16  5093.7  358.58    5109  359.56
  5124.3  363.17  5203.3   363.3  5209.2  365.36    5267  365.01  5340.1  369.16
  5355.5  368.88  5370.8   370.6  5391.9  367.39  5397.9  369.26  5419.7  371.86
  5449.8   371.8  5455.7  374.22    5471  375.27  5475.8  377.51  5478.7  377.51
#Mann= 5 ,-1 , 0
  4441.3     .05       0  4834.2     .12       0  5033.8     .07       0
    5038     .12       0  5391.9    .035       0
Bank Sta=5033.8,5038
XS Rating Curve= 0 ,0
Exp/Cntr=0.3,0.1

Type RM Length L Ch R = 1 ,11025   ,621,621,621
BEGIN DESCRIPTION:
Little Dry Branch11024.65
END DESCRIPTION:
XS GIS Cut Line= 3
      2717112.04      6822369.96      2716885.61      6821990.67
      2716410.68      6821567.87
#Sta/Elev= 30
  4566.6  371.04  4649.7  368.59  4686.7  366.02  4729.5  364.26  4862.1  361.36
  4920.2  361.42  4949.7  358.48  4957.2  354.98    4963  357.82  4970.7  354.86
    4971  354.36  4974.9  354.86  4977.8   356.3  4984.7  355.62  4994.2  359.98
  5057.6  359.07  5078.5  359.85  5106.9  359.42  5191.2  360.53  5220.6  361.19
  5248.8  360.43  5255.7  361.53    5270  361.54    5341  366.56  5468.1  370.48
  5496.6  372.89  5553.4  373.77  5560.1  375.12  5581.8  376.65  5644.2  379.16
#Mann= 6 ,-1 , 0
  4566.6     .05       0  4862.1     .16       0  4970.7     .07       0
  4974.9     .16       0  4977.8     .12       0  5191.2     .07       0
Bank Sta=4970.7,4974.9
XS Rating Curve= 0 ,0
Exp/Cntr=0.3,0.1

Type RM Length L Ch R = 1 ,10404   ,410,410,410
BEGIN DESCRIPTION:
Little Dry Branch10403.88
END DESCRIPTION:
XS GIS Cut Line= 3
      2717073.61      6822251.26      2716919.02      6821561.96
       2716500.2      6821147.86
#Sta/Elev= 30
  4289.9  367.61  4320.9  367.36    4444  362.28  4527.1  361.32  4607.9  360.46
  4718.7  361.03    4846  359.36  4924.7  356.85  5000.6   357.8  5006.2  357.13
  5013.3  352.95  5018.2  352.28  5018.5  351.78  5022.4  352.28  5027.5  355.74
  5034.5  355.24  5041.6  357.74  5048.6  356.71  5069.9  358.93  5091.1  358.76
  5187.2  366.07  5239.6  370.08  5324.4  373.49  5430.5  374.75  5451.7  373.12
  5472.9  374.15  5479.9  372.76  5557.4  375.09  5571.9  375.21  5585.3  373.79
#Mann= 9 ,-1 , 0
  4289.9     .05       0  4527.1     .16       0  4718.7     .12       0
    4846     .16       0  4924.7     .12       0  5018.2     .07       0
  5022.4     .12       0  5187.2     .07       0  5557.4     .05       0
Bank Sta=5018.2,5022.4
XS Rating Curve= 0 ,0
Exp/Cntr=0.3,0.1

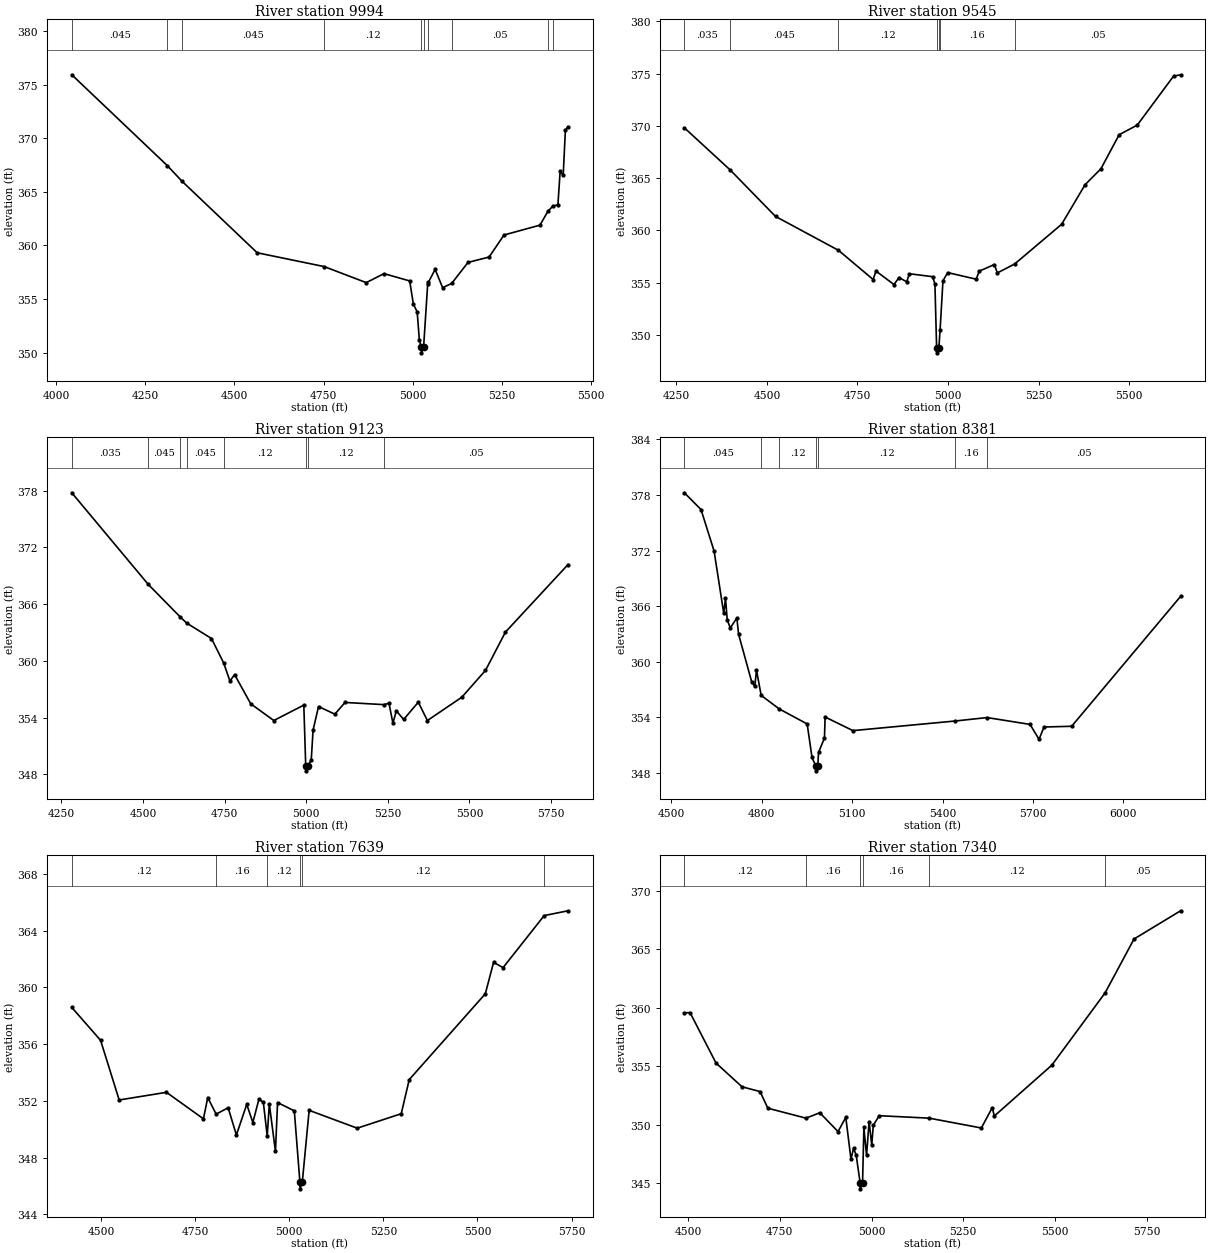
Type RM Length L Ch R = 1 ,9994    ,449,449,449
BEGIN DESCRIPTION:
Little Dry Branch9994.11
END DESCRIPTION:
XS GIS Cut Line= 3
      2717976.01      6821961.01        2717226.        6821361.
        2716876.        6821111.
#Sta/Elev= 30
  4044.1  375.95  4312.2  367.45  4352.8  366.01  4563.6  359.32  4751.3  358.03
  4869.3  356.53  4918.9  357.37    4991  356.69  5001.4  354.51    5012   353.8
  5018.1  351.15  5023.6  350.47  5024.1  349.97  5029.9  350.47  5041.4  356.37
  5043.4  356.55  5062.3  357.77  5083.2  356.06  5108.5  356.45  5154.5  358.42
  5213.5  358.92  5255.3  360.98    5356   361.9  5378.5   363.2    5392  363.67
  5406.4  363.81  5412.6  366.92  5421.2  366.55  5427.3  370.77  5434.7  371.08
#Mann= 10 ,-1 , 0
  4044.1    .045       0  4312.2     .07       0  4352.8    .045       0
  4751.3     .12       0  5023.6     .07       0  5029.9     .12       0
  5043.4     .16       0  5108.5     .05       0  5378.5     .12       0
    5392     .16       0
Bank Sta=5023.6,5029.9
XS Rating Curve= 0 ,0
Exp/Cntr=0.3,0.1

Type RM Length L Ch R = 1 ,9545    ,422,422,422
BEGIN DESCRIPTION:
Little Dry Branch9544.54
END DESCRIPTION:
XS GIS Cut Line= 3
      2718136.54      6821575.07      2717574.07      6821107.48
      2717061.02      6820727.64
#Sta/Elev= 30
  4272.2  369.81  4398.7  365.78  4523.8  361.34  4697.6   358.1  4793.3  355.31
  4801.1  356.12  4850.6  354.83  4864.9   355.5  4885.7  355.09  4893.5  355.86
  4957.3  355.58  4963.8  354.89  4968.5   348.8    4969   348.3  4974.8   348.8
  4978.1  350.51    4986  355.19  4999.1  355.97  5077.7  355.34  5086.1  356.11
  5127.8  356.74  5136.2  355.94  5183.8  356.79  5313.6  360.59  5378.3  364.37
  5422.2   365.9  5472.3  369.15  5522.4  370.07  5622.5  374.75    5642  374.88
#Mann= 7 ,-1 , 0
  4272.2    .035       0  4398.7    .045       0  4697.6     .12       0
  4968.5     .07       0  4974.8     .12       0  4978.1     .16       0
  5183.8     .05       0
Bank Sta=4968.5,4974.8
XS Rating Curve= 0 ,0
Exp/Cntr=0.3,0.1

Type RM Length L Ch R = 1 ,9123    ,742,742,742
BEGIN DESCRIPTION:
Little Dry Branch9123.22
END DESCRIPTION:
XS GIS Cut Line= 3
       2718439.3       6821512.8      2717929.27      6821003.13
      2717217.42      6820640.35
#Sta/Elev= 30
  4282.1  377.77  4516.4  368.08  4613.1  364.68  4633.7     364    4710  362.36
  4747.4  359.77  4766.5  357.86  4780.7  358.55  4830.2  355.46  4900.9  353.69
  4992.8  355.32  4998.7  348.87  4999.2  348.37  5005.1  348.87  5015.6  349.53
  5021.2  352.68  5037.9  355.17  5087.9  354.36    5119   355.6  5238.6  355.37
  5253.7  355.52  5265.8   353.4  5276.2  354.72  5298.6   353.8  5343.5  355.63
  5371.4  353.69    5477  356.16  5549.3  358.99  5610.4  363.04  5802.1  370.18
#Mann= 8 ,-1 , 0
  4282.1    .035       0  4516.4    .045       0  4613.1    .035       0
  4633.7    .045       0  4747.4     .12       0  4998.7     .07       0
  5005.1     .12       0  5238.6     .05       0
Bank Sta=4998.7,5005.1
XS Rating Curve= 0 ,0
Exp/Cntr=0.3,0.1

Type RM Length L Ch R = 1 ,8381    ,742,742,742
BEGIN DESCRIPTION:
Little Dry Branch8380.51
END DESCRIPTION:
XS GIS Cut Line= 3
      2718830.31      6821132.21      2718423.93      6820906.32
      2717324.11      6820473.95
#Sta/Elev= 30
  4543.2  378.24  4598.4  376.43  4641.8  371.95  4673.9  365.22  4679.6  366.86
  4685.4  364.53  4695.6  363.65  4717.3  364.73  4723.1  362.97  4766.5  357.84
  4776.8  357.34  4782.5  359.08  4798.1  356.37  4858.1  354.91  4950.7  353.29
  4966.7  349.68  4979.5  348.73    4980  348.23  4985.9  348.73  4988.4  350.22
  5008.1  351.78  5010.2  354.04  5102.6  352.57  5442.2  353.61  5547.6  353.98
  5690.3  353.24  5720.1  351.63  5736.6  352.96  5828.4  353.04  6189.9  367.06
#Mann= 7 ,-1 , 0
  4543.2    .045       0  4798.1     .16       0  4858.1     .12       0
  4979.5     .07       0  4985.9     .12       0  5442.2     .16       0
  5547.6     .05       0
Bank Sta=4979.5,4985.9
XS Rating Curve= 0 ,0
Exp/Cntr=0.3,0.1

Type RM Length L Ch R = 1 ,7639    ,299,299,299
BEGIN DESCRIPTION:
Little Dry Branch7638.91
END DESCRIPTION:
XS GIS Cut Line= 5
      2718584.07      6820654.58      2718072.32      6820378.67
      2717398.12      6820133.63      2717390.97      6820124.81
      2717383.74      6820120.32
#Sta/Elev= 30
    4422  358.59  4498.5  356.27  4547.9  352.06  4673.6   352.6  4771.8  350.73
  4783.3  352.23  4805.6  351.06  4837.5  351.51  4859.4  349.59  4886.9  351.75
  4903.1  350.47  4919.4  352.13    4931  351.89  4941.3  349.53  4946.9  351.77
  4963.2  348.43  4968.8  351.88  5013.3  351.29  5028.1  346.29  5028.6  345.79
  5034.6  346.29  5052.7  351.33  5180.4  350.07  5297.4  351.09  5318.7   353.5
  5520.8  359.55  5542.8  361.77  5568.1   361.4  5677.2  365.07  5740.6  365.41
#Mann= 6 ,-1 , 0
    4422     .12       0  4805.6     .16       0  4941.3     .12       0
  5028.1     .07       0  5034.6     .12       0  5677.2     .05       0
Bank Sta=5028.1,5034.6
XS Rating Curve= 0 ,0
Exp/Cntr=0.3,0.1

Type RM Length L Ch R = 1 ,7340    ,728,728,728
BEGIN DESCRIPTION:
Little Dry Branch7339.83
END DESCRIPTION:
XS GIS Cut Line= 3
      2718622.45      6820586.23      2718267.31        6820210.
      2717519.94      6819838.22
#Sta/Elev= 30
    4490  359.58  4505.4   359.6  4576.2  355.29    4647  353.26  4696.3  352.85
  4717.4  351.43  4821.3  350.58    4859  351.04  4908.7  349.43  4929.8  350.65
  4943.9  347.08    4951  347.99  4958.1  347.44  4968.9  345.04  4969.4  344.54
  4975.5  345.04  4979.1  349.79  4986.4  347.39  4993.3  350.29  5000.6  348.27
  5004.7  349.97    5021  350.79    5157  350.58  5299.2  349.74  5328.9  351.48
  5334.5  350.76  5491.3  355.11  5636.3  361.28  5715.2  365.89  5842.1   368.3
#Mann= 6 ,-1 , 0
    4490     .12       0  4821.3     .16       0  4968.9     .07       0
  4975.5     .16       0    5157     .12       0  5636.3     .05       0
Bank Sta=4968.9,4975.5
XS Rating Curve= 0 ,0
Exp/Cntr=0.3,0.1

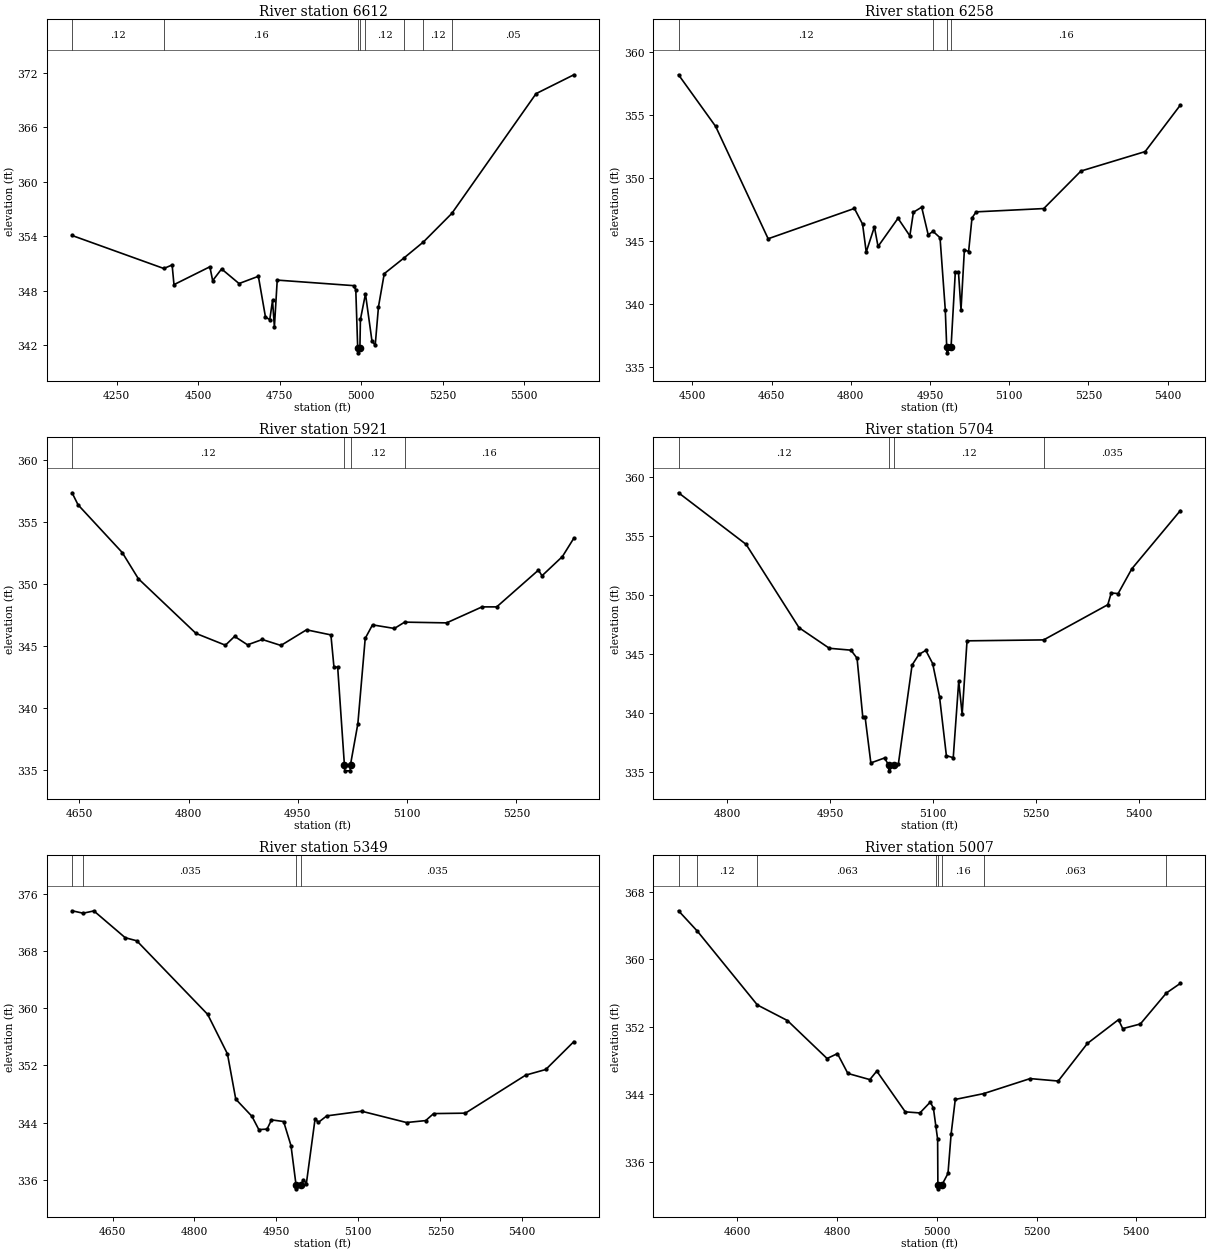
Type RM Length L Ch R = 1 ,6612    ,354,354,354
BEGIN DESCRIPTION:
Little Dry Branch6612.17
END DESCRIPTION:
XS GIS Cut Line= 3
      2718593.66      6820399.35      2718159.51      6819627.36
      2717510.93       6819703.3
#Sta/Elev= 30
  4113.7  354.09    4395  350.45  4420.5  350.84  4426.2  348.67  4536.3  350.64
  4544.8  349.11  4572.2   350.4  4625.7  348.79    4685  349.59  4706.7  345.11
  4719.9   344.8  4728.4  346.93  4734.1  343.99  4742.8  349.17    4977  348.56
  4983.7   348.1  4989.6  341.65  4990.1  341.15  4996.3  341.65  4997.9  344.83
  5013.4  347.65  5033.1  342.51  5043.2  341.97  5053.3  346.24    5071  349.88
  5132.1  351.63  5191.2  353.38  5278.1  356.52  5536.5  369.73  5652.4  371.81
#Mann= 8 ,-1 , 0
  4113.7     .12       0    4395     .16       0  4989.6     .07       0
  4996.3     .16       0  5013.4     .12       0  5132.1     .16       0
  5191.2     .12       0  5278.1     .05       0
Bank Sta=4989.6,4996.3
XS Rating Curve= 0 ,0
Exp/Cntr=0.3,0.1

Type RM Length L Ch R = 1 ,6258    ,337,337,337
BEGIN DESCRIPTION:
Little Dry Branch6257.832
END DESCRIPTION:
XS GIS Cut Line= 3
      2718897.75       6819236.5      2718427.01      6819471.86
      2718161.33      6819141.56
#Sta/Elev= 30
  4473.7  358.16    4544  354.07  4643.4  345.18  4806.7  347.58  4822.2  346.34
  4829.1  344.13  4844.6  346.12  4851.5  344.57  4889.3   346.8  4911.7  345.41
  4918.5  347.28  4934.1  347.68  4946.5  345.49  4955.6  345.77  4968.9  345.26
  4978.8  339.57  4981.5  336.65    4982  336.15  4989.8  336.65  4997.8  342.53
  5003.8  342.53  5008.6  339.56    5015  344.31    5023  344.17  5029.4  346.83
  5037.3  347.31  5165.3  347.57  5235.7  350.54  5357.3  352.08  5423.9  355.76
#Mann= 4 ,-1 , 0
  4473.7     .12       0  4955.6     .16       0  4981.5     .07       0
  4989.8     .16       0
Bank Sta=4981.5,4989.8
XS Rating Curve= 0 ,0
Exp/Cntr=0.3,0.1

Type RM Length L Ch R = 1 ,5921    ,217,217,217
BEGIN DESCRIPTION:
Little Dry Branch5920.6
END DESCRIPTION:
XS GIS Cut Line= 3
      2718884.12      6819112.78      2718526.37      6819167.28
      2718200.39      6819142.45
#Sta/Elev= 30
  4640.1  357.34  4648.3  356.37    4709  352.52  4731.1  350.41  4810.2     346
  4850.6  345.05  4863.2  345.76    4881  345.08  4901.2  345.51  4926.8  345.03
  4961.9  346.29  4995.4  345.88  4999.6  343.28  5004.7  343.28  5013.9  335.42
  5014.4  334.92  5021.8  334.92  5022.3  335.42  5032.4  338.72  5042.5   345.6
  5052.5  346.69  5082.6   346.4  5096.6  346.91  5154.2  346.85  5202.9  348.14
    5223  348.14  5280.2   351.1  5285.2  350.65  5313.2   352.2  5328.9  353.68
#Mann= 4 ,-1 , 0
  4640.1     .12       0  5013.9     .07       0  5022.3     .12       0
  5096.6     .16       0
Bank Sta=5013.9,5022.3
XS Rating Curve= 0 ,0
Exp/Cntr=0.3,0.1

Type RM Length L Ch R = 1 ,5704    ,355,355,355
BEGIN DESCRIPTION:
Little Dry Branch5704.13
END DESCRIPTION:
XS GIS Cut Line= 3
      2718913.54       6819031.2      2718644.34       6818992.5
      2718185.41      6818971.07
#Sta/Elev= 30
  4728.9  358.67  4827.4   354.3  4904.6  347.24  4948.7   345.5  4980.2  345.34
  4989.1  344.66  4997.5  339.65  5000.9  339.65  5009.2  335.79  5029.2  336.21
    5035  335.62  5035.5  335.12  5043.4  335.62  5049.3  335.69  5069.3  344.08
  5079.3  344.98  5089.3  345.32  5099.3  344.21  5109.3   341.4  5119.3  336.41
  5129.3  336.23  5137.3  342.71  5142.3  339.91  5149.4  346.13  5261.1  346.21
  5354.6  349.19  5359.6  350.19  5369.6  350.13  5389.6  352.23  5460.3  357.16
#Mann= 4 ,-1 , 0
  4728.9     .12       0    5035     .07       0  5043.4     .12       0
  5261.1    .035       0
Bank Sta=5035,5043.4
XS Rating Curve= 0 ,0
Exp/Cntr=0.3,0.1

Type RM Length L Ch R = 1 ,5349    ,342,342,342
BEGIN DESCRIPTION:
Little Dry Branch5348.98
END DESCRIPTION:
XS GIS Cut Line= 3
      2718981.97      6818462.58      2718621.93      6818696.68
      2718204.41      6818951.14
#Sta/Elev= 30
    4576  373.65  4596.2  373.31  4615.9  373.63  4673.3  369.88  4694.4  369.45
  4824.2  359.15  4860.4  353.62  4875.6  347.29  4905.2  344.89  4917.8  343.03
  4932.9   343.1    4941  344.39  4963.2  344.16  4976.7  340.78    4986  335.24
  4986.5  334.74  4994.4  335.24  4999.4  336.03  5004.8  335.47  5020.8  344.55
  5026.7  344.03  5042.1  344.95  5106.1   345.6  5188.1  344.02  5223.2  344.29
  5237.7  345.27  5295.8  345.33  5406.2  350.65    5443  351.44  5494.4  355.34
#Mann= 4 ,-1 , 0
    4576     .12       0  4596.2    .035       0    4986    .035       0
  4994.4    .035       0
Bank Sta=4986,4994.4
XS Rating Curve= 0 ,0
Exp/Cntr=0.3,0.1

Type RM Length L Ch R = 1 ,5007    ,335,335,335
BEGIN DESCRIPTION:
Little Dry Branch5007.3
END DESCRIPTION:
XS GIS Cut Line= 3
      2718857.69      6818117.64      2718433.41      6818426.06
      2718046.41      6818713.66
#Sta/Elev= 30
  4481.8  365.75  4519.8  363.32    4640  354.59  4700.2  352.75  4779.8  348.25
  4800.6  348.83  4821.5  346.48  4865.6  345.75  4879.5  346.76  4936.7  341.93
    4966   341.8  4986.9  343.09  4993.1  342.38    4998  340.25  5001.6  338.68
  5002.1  333.31  5002.6  332.81  5010.5  333.31  5022.4  334.64  5028.6  339.27
    5037   343.4  5093.9  344.09  5187.2  345.87  5243.5  345.58    5302  350.03
  5364.5  352.85  5372.9  351.79  5408.3  352.34  5460.5  356.01  5488.5  357.15
#Mann= 8 ,-1 , 0
  4481.8    .063       0  4519.8     .12       0    4640    .063       0
    4998     .16       0  5002.1     .07       0  5010.5     .16       0
  5093.9    .063       0  5460.5     .16       0
Bank Sta=5002.1,5010.5
XS Rating Curve= 0 ,0
Exp/Cntr=0.3,0.1