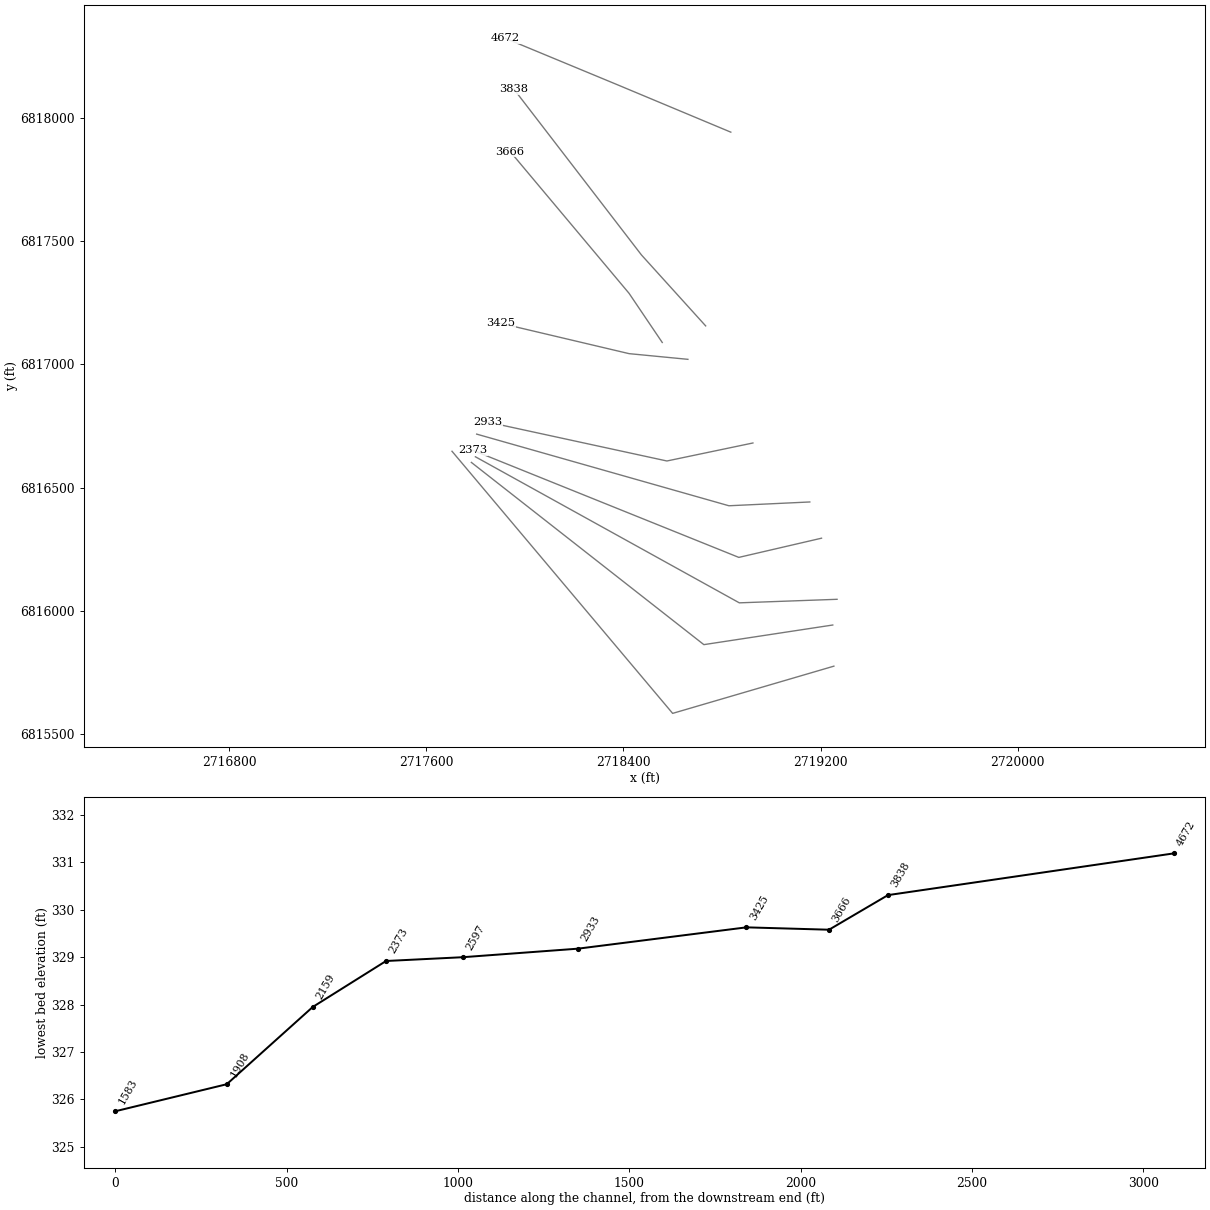
HEC-RAS study Little Dry Branch.prj: Little Dry Branch Base Level Engineering

--- Little Dry Branch.g01 (geometry) --- (continued)

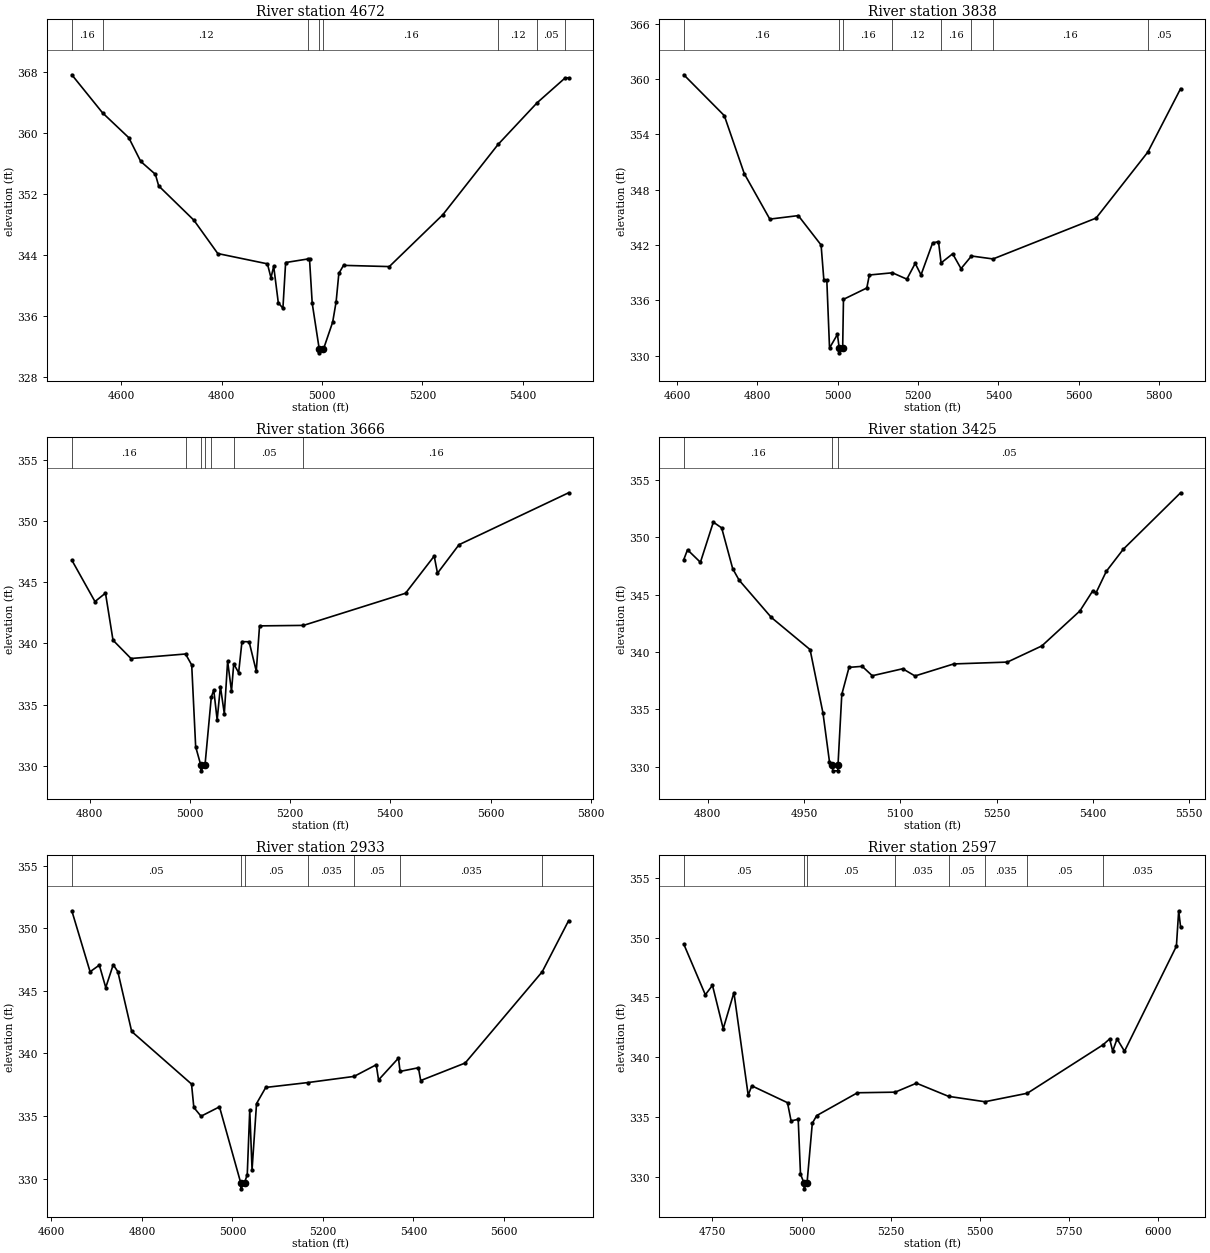
Type RM Length L Ch R = 1 ,4672    ,834,834,834
BEGIN DESCRIPTION:
Little Dry Branch4672.11
END DESCRIPTION:
XS GIS Cut Line= 3
      2718835.83       6817942.2      2718372.65      6818135.85
       2717921.4      6818322.86
#Sta/Elev= 30
  4501.1  367.65  4562.5  362.65  4614.7   359.4  4638.5  356.29  4667.7   354.6
  4674.3  353.08  4744.5  348.58  4792.1  344.21  4891.1  342.86  4898.2  341.03
  4903.6  342.54  4912.8  337.75    4922  337.04  4927.4  343.03  4972.9  343.51
    4975  343.51  4980.4  337.69  4994.4  331.69  4994.9  331.19  5002.9  331.69
  5021.2  335.22  5028.1   337.9  5033.5   341.6  5042.8  342.66  5134.1   342.5
  5240.8   349.3  5350.9  358.51  5428.8  363.98  5484.9  367.25  5491.6  367.25
#Mann= 8 ,-1 , 0
  4501.1     .16       0  4562.5     .12       0  4972.9     .16       0
  4994.4     .07       0  5002.9     .16       0  5350.9     .12       0
  5428.8     .05       0  5484.9     .16       0
Bank Sta=4994.4,5002.9
XS Rating Curve= 0 ,0
Exp/Cntr=0.3,0.1

Type RM Length L Ch R = 1 ,3838    ,172,172,172
BEGIN DESCRIPTION:
Little Dry Branch3837.82
END DESCRIPTION:
XS GIS Cut Line= 3
      2718733.79      6817156.19      2718473.52      6817443.74
      2717955.76      6818116.78
#Sta/Elev= 30
  4616.7  360.46  4717.6  356.03  4767.3  349.74  4830.9  344.81  4901.8  345.19
  4958.6     342  4965.4  338.24  4972.8  338.22  4979.6  330.83  4999.3  332.31
  5003.7  330.81  5004.2  330.31  5012.3  330.81  5014.3  336.11  5072.4  337.34
  5078.7  338.75  5136.2  338.99  5172.1   338.3  5192.9  340.01  5207.4  338.76
  5236.4  342.24  5250.9  342.36  5257.4  340.06  5286.2  341.05    5307  339.44
    5333  340.81  5386.7  340.49  5643.3  344.92  5772.2  352.08  5853.7  358.95
#Mann= 8 ,-1 , 0
  4616.7     .16       0  5003.7     .07       0  5012.3     .16       0
  5136.2     .12       0  5257.4     .16       0    5333     .12       0
  5386.7     .16       0  5772.2     .05       0
Bank Sta=5003.7,5012.3
XS Rating Curve= 0 ,0
Exp/Cntr=0.3,0.1

Type RM Length L Ch R = 1 ,3666    ,241,241,241
BEGIN DESCRIPTION:
Little Dry Branch3665.5
END DESCRIPTION:
XS GIS Cut Line= 3
      2718557.67      6817088.91      2718422.93      6817288.44
      2717940.45      6817863.73
#Sta/Elev= 30
  4764.3  346.82  4810.5  343.43  4831.5  344.12  4846.5  340.27  4882.4  338.77
  4991.3  339.14  5003.6  338.24  5011.5  331.55  5021.5  330.08    5022  329.58
  5030.2  330.08  5042.7  335.61  5047.6   336.2  5054.4  333.75  5060.9  336.48
  5068.7  334.25  5075.3  338.56    5083   336.1  5087.5  338.33  5097.3  337.61
  5103.9  340.15  5118.2  340.14  5132.5  337.74    5139  341.44  5226.7  341.48
  5430.4  344.11  5487.6  347.15  5494.2  345.75  5537.1  348.08  5755.9  352.33
#Mann= 7 ,-1 , 0
  4764.3     .16       0  4991.3     .12       0  5021.5     .07       0
  5030.2     .12       0  5042.7     .16       0  5087.5     .05       0
  5226.7     .16       0
Bank Sta=5021.5,5030.2
XS Rating Curve= 0 ,0
Exp/Cntr=0.3,0.1

Type RM Length L Ch R = 1 ,3425    ,492,492,492
BEGIN DESCRIPTION:
Little Dry Branch3424.58
END DESCRIPTION:
XS GIS Cut Line= 3
       2718661.8      6817020.53      2718423.16      6817043.58
      2717903.41       6817166.3
#Sta/Elev= 30
  4762.9  348.05  4768.7   348.9  4788.8  347.81  4808.9  351.31  4821.9  350.81
  4839.1  347.25  4849.1  346.25  4899.3     343  4959.6   340.2  4979.7  334.67
  4989.8  330.43  4994.4  330.13  4994.9  329.63  5002.6  329.63  5003.1  330.13
    5009  336.29  5020.3  338.65  5040.8  338.74  5056.5  337.92  5103.9  338.53
    5123   337.9  5183.4  338.95  5266.9  339.11  5320.6  340.52  5379.9  343.57
  5400.1  345.34  5405.2  345.17    5421  347.02  5447.5  348.95  5536.7  353.87
#Mann= 3 ,-1 , 0
  4762.9     .16       0  4994.4     .07       0  5003.1     .05       0
Bank Sta=4994.4,5003.1
XS Rating Curve= 0 ,0
Exp/Cntr=0.3,0.1

Type RM Length L Ch R = 1 ,2933    ,336,336,336
BEGIN DESCRIPTION:
Little Dry Branch2933.45
END DESCRIPTION:
XS GIS Cut Line= 3
      2718925.53      6816681.14      2718576.56      6816608.12
      2717851.86      6816765.41
#Sta/Elev= 30
  4645.1  351.39  4685.5  346.52  4705.9  347.05  4720.1  345.26  4736.6  347.08
  4746.8  346.53  4777.4  341.75  4909.7  337.55  4914.8  335.68  4930.7  334.98
  4971.5  335.73  5018.3  329.68  5018.8  329.18    5027  329.68  5032.9  330.32
  5038.4  335.48  5043.5   330.7  5053.4  335.99  5073.8  337.28  5167.1  337.67
    5269  338.16    5318  339.09  5323.1  337.88  5367.1  339.62  5370.7  338.56
  5411.2  338.85  5416.3  337.83  5514.6  339.23  5684.9  346.52  5743.2   350.6
#Mann= 7 ,-1 , 0
  4645.1     .05       0  5018.3     .05       0    5027     .05       0
  5167.1    .035       0    5269     .05       0  5370.7    .035       0
  5684.9     .05       0
Bank Sta=5018.3,5027
XS Rating Curve= 0 ,0
Exp/Cntr=0.3,0.1

Type RM Length L Ch R = 1 ,2597    ,224,224,224
BEGIN DESCRIPTION:
Mapping XS 1213b8db
END DESCRIPTION:
XS GIS Cut Line= 3
      2719156.34      6816441.83      2718828.14      6816426.45
      2717804.78      6816717.12
#Sta/Elev= 30
  4669.7  349.45  4730.1  345.22  4750.1  346.01  4780.2  342.38  4810.2   345.4
  4850.2  336.83  4860.3  337.61  4960.4   336.2  4970.4  334.68  4990.4  334.81
  4996.8  330.23  5006.5   329.5    5007     329  5015.2   329.5  5029.9  334.48
  5042.1  335.12  5156.4  337.03  5262.1  337.08  5321.8  337.83  5411.7  336.73
  5513.8  336.28  5632.6  336.99  5844.4  341.03  5863.3  341.53  5871.8  340.51
  5884.1  341.53  5904.9   340.5  6050.4  349.28  6056.8  352.24  6062.1   350.9
#Mann= 8 ,-1 , 0
  4669.7     .05       0  5006.5     .05       0  5015.2     .05       0
  5262.1    .035       0  5411.7     .05       0  5513.8    .035       0
  5632.6     .05       0  5844.4    .035       0
Bank Sta=5006.5,5015.2
XS Rating Curve= 0 ,0
Exp/Cntr=0.3,0.1

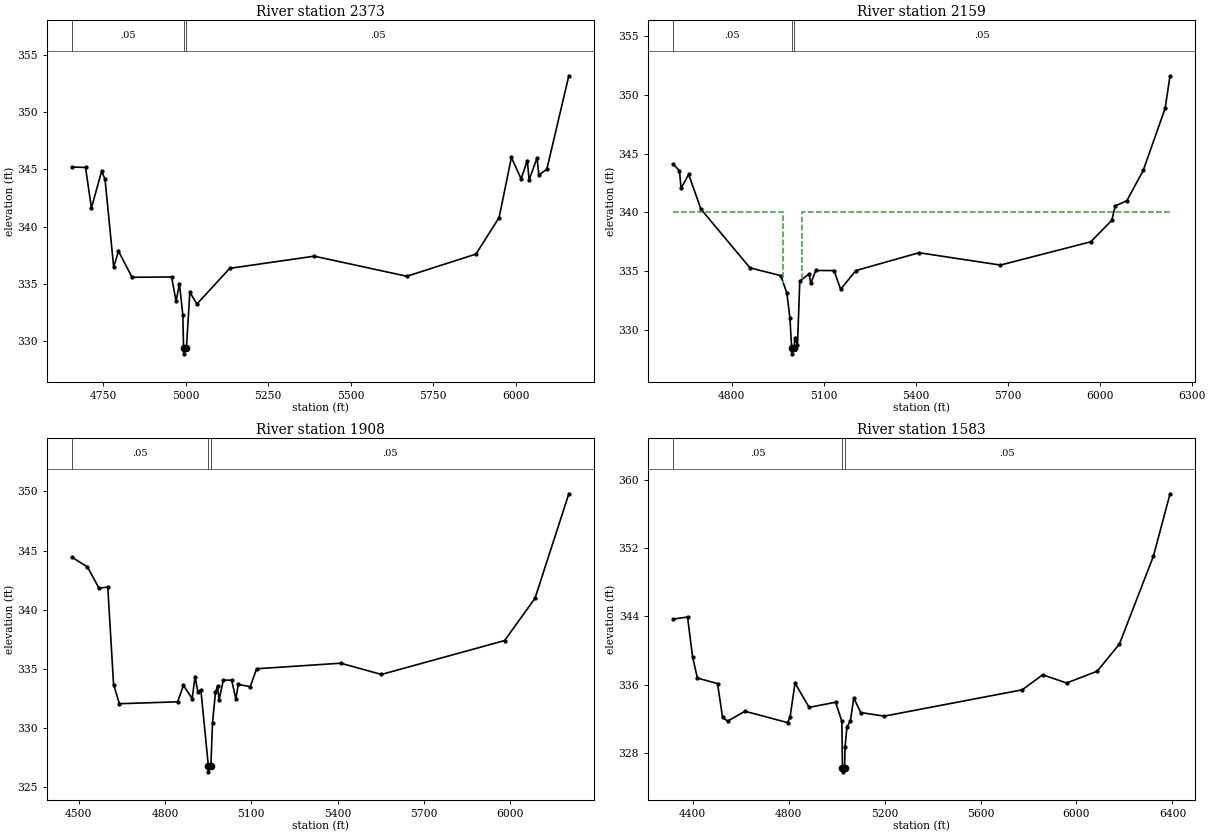
Type RM Length L Ch R = 1 ,2373    ,214,214,214
BEGIN DESCRIPTION:
Mapping XS 5516553b
END DESCRIPTION:
XS GIS Cut Line= 3
      2719203.88      6816294.87      2718868.27      6816216.96
      2717789.89      6816651.31
#Sta/Elev= 30
  4654.3   345.2  4695.9  345.16  4713.7  341.63  4744.5  344.82  4754.8  344.17
  4781.2  336.48  4795.8  337.87  4836.9  335.59  4956.9  335.62  4970.4  333.49
  4980.6  335.04  4990.9  332.29  4993.1  329.42  4993.6  328.92  5001.8  329.42
  5012.1  334.29  5033.6  333.26  5133.1  336.37  5389.4  337.43  5670.2  335.68
  5879.7  337.61    5950   340.8  5987.2  346.03  6016.7  344.17  6035.5  345.76
  6040.9  344.07    6065     346  6070.4  344.51  6094.6     345  6161.4  353.15
#Mann= 3 ,-1 , 0
  4654.3     .05       0  4993.1     .05       0  5001.8     .05       0
Bank Sta=4993.1,5001.8
XS Rating Curve= 0 ,0
Exp/Cntr=0.3,0.1

Type RM Length L Ch R = 1 ,2159    ,251,251,251
BEGIN DESCRIPTION:
Mapping XS 0b976527
END DESCRIPTION:
XS GIS Cut Line= 3
      2719266.96      6816046.95      2718870.33      6816032.58
      2717799.59      6816625.21
#Sta/Elev= 30
  4608.8  344.11  4629.8  343.55  4634.9  342.05  4659.8  343.23  4699.8  340.27
  4859.9  335.27    4960  334.61    4980  333.12    4990  330.98  4995.6  328.45
  4996.1  327.95  5004.4  328.45  5005.4  329.32  5014.6  328.68  5022.1  334.14
  5052.4  334.76  5058.1  333.95  5074.1  335.05  5133.7  335.04  5155.4  333.45
  5204.9  335.04  5410.8  336.56  5676.4  335.51  5970.7  337.49  6039.3  339.31
  6050.9  340.55  6088.7  340.99  6142.2  343.58  6213.5  348.86  6229.5  351.63
#Mann= 3 ,-1 , 0
  4608.8     .05       0  4995.6     .05       0  5004.4     .05       0
#XS Ineff= 2 , 0
       0    4968     340    5030       0     340
Permanent Ineff=
       F       F
Bank Sta=4995.6,5004.4
XS Rating Curve= 0 ,0
Exp/Cntr=0.3,0.1

Type RM Length L Ch R = 1 ,1908    ,325,325,325
BEGIN DESCRIPTION:
Mapping XS 8a2de872
END DESCRIPTION:
XS GIS Cut Line= 3
      2719249.47      6815942.64       2718726.5        6815863.
       2717783.2      6816602.32
#Sta/Elev= 30
  4476.5  344.44  4530.6  343.62    4571  341.82  4601.4  341.92  4621.6  333.69
  4641.8  332.07  4844.2  332.23  4864.4  333.61  4894.7  332.51  4904.8  334.34
  4914.5   333.1  4925.1  333.23    4951  326.82  4951.5  326.32  4959.8  326.82
  4965.5  330.48  4975.7  333.02  4983.1  333.57  4988.2  332.39  5003.2  334.07
  5032.2  334.05  5046.7  332.47  5054.8   333.7  5096.4  333.51    5119  335.02
    5411  335.49  5552.5  334.54  5980.6   337.4  6086.4  340.97    6204  349.79
#Mann= 3 ,-1 , 0
  4476.5     .05       0    4951     .05       0  4959.8     .05       0
Bank Sta=4951,4959.8
XS Rating Curve= 0 ,0
Exp/Cntr=0.3,0.1

Type RM Length L Ch R = 1 ,1583    ,0,0,0
BEGIN DESCRIPTION:
Little Dry Branch2511.766
END DESCRIPTION:
XS GIS Cut Line= 3
      2719254.04      6815775.72      2718599.82      6815584.13
      2717704.68      6816647.54
#Sta/Elev= 30
  4318.3  343.68  4378.8  343.92  4399.6  339.27  4419.7  336.76  4503.8  336.11
  4524.7  332.16  4545.5   331.7  4618.4  332.86  4795.6  331.53    4806  332.15
  4826.8  336.17  4885.4  333.32  4996.1  333.92    5022  331.67  5024.5  326.25
    5025  325.75  5033.3  326.25  5035.4  328.67  5043.2  331.02  5057.5  331.73
  5071.8  334.43  5100.4  332.71  5199.3  332.29  5774.1  335.38  5858.7  337.14
  5958.8  336.18  6086.2  337.56  6178.6  340.73  6320.4  351.04    6390  358.39
#Mann= 3 ,-1 , 0
  4318.3     .05       0  5024.5     .05       0  5033.3     .05       0
Bank Sta=5024.5,5033.3
XS Rating Curve= 0 ,0
Exp/Cntr=0.3,0.1

Chan Stop Cuts=-1
Use User Specified Reach Order=0
Composite Channel Slope=5