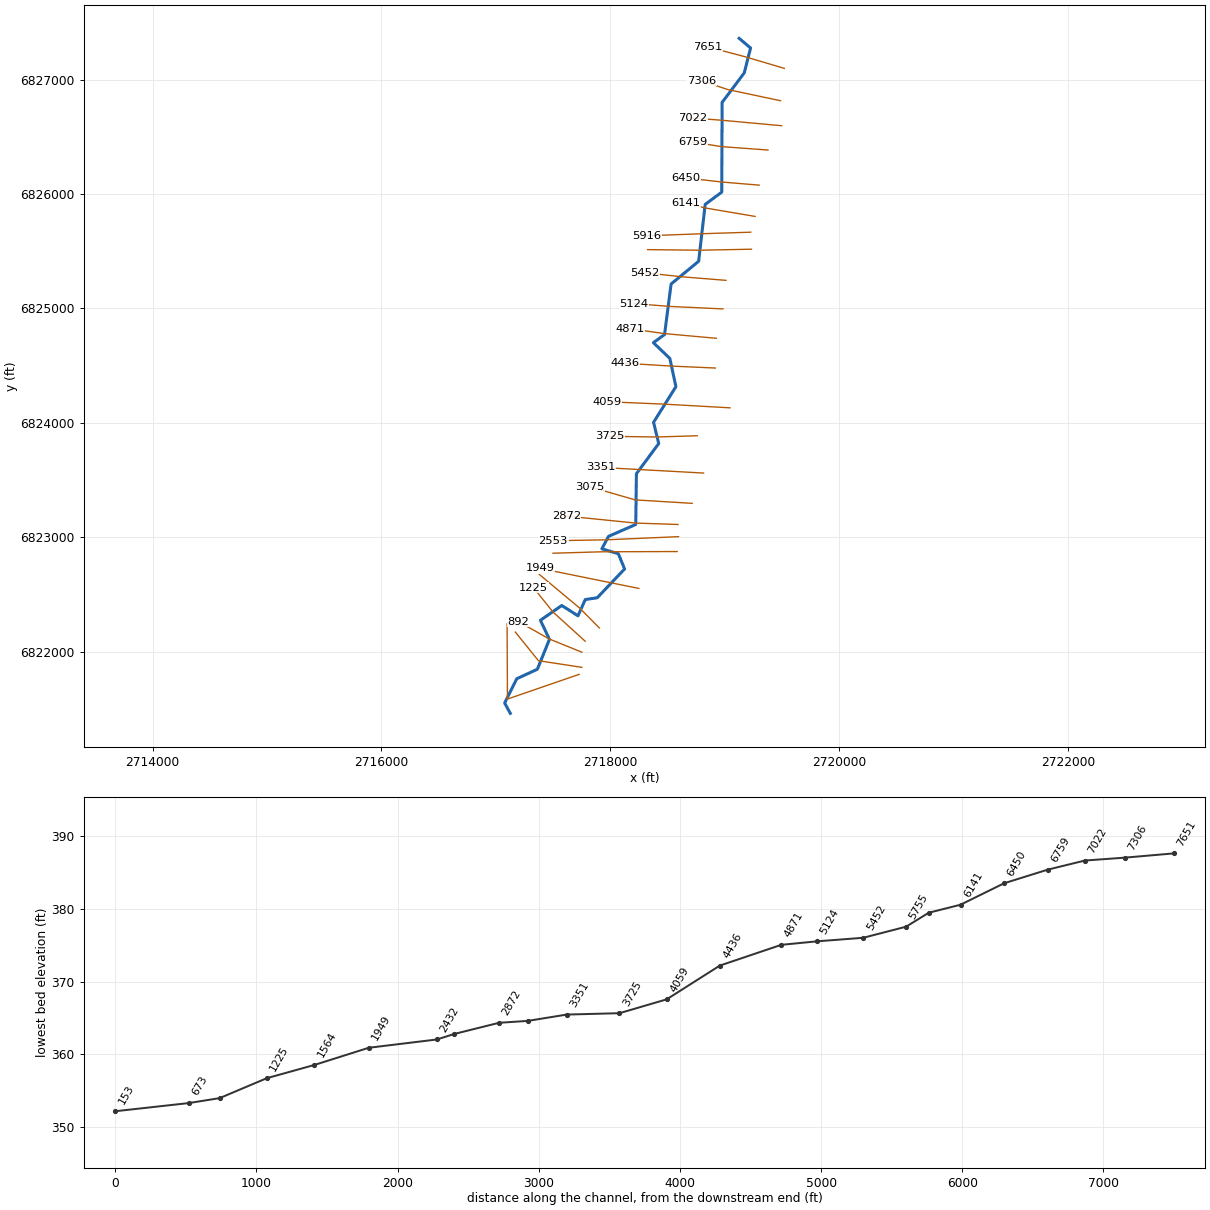
--- Little Dry Branch Trib A.prj (project) ---

Proj Title=Little Dry Branch Trib A Base Level Engineering
Current Plan=p01
Default Exp/Contr=0.3,0.1
English Units
Geom File=g01
Flow File=f01
Plan File=p01
BEGIN DESCRIPTION:
Little Dry Branch Trib A
END DESCRIPTION:

--- Little Dry Branch Trib A.p01 (plan) ---

Plan Title=Multiple Run
Short Identifier=Multiple
Geom File=g01
Flow File=f01
Subcritical Flow
K Sum by GR= 0
Std Step Tol= 0.01
Critical Tol= 0.01
Num of Std Step Trials= 20
Max Error Tol= 0.3
Flow Tol Ratio= 0.001
Split Flow NTrial= 30
Split Flow Tol= 0.02
Split Flow Ratio= 0.02
Log Output Level= 0
Friction Slope Method= 1
Unsteady Friction Slope Method= 2
Unsteady Bridges Friction Slope Method= 1
Parabolic Critical Depth
Global Vel Dist=  1 , 1 , 1
Global Log Level= 0
CheckData=True
Encroach Param= -1, 0, 0, 0
BEGIN DESCRIPTION:
Multiple Run
END DESCRIPTION:

--- Little Dry Branch Trib A.f01 (steady flow) ---

Flow Title=Multiple
Number of Profiles=7
Profile Names=10-year,25-year,50-year,1pct_min,100-year,1pct_plu,500-year
River Rch & RM= Little Dry Branc,Reach-1,7651
     446     585     695     410     819    1634    1134
River Rch & RM= Little Dry Branc,Reach-1,5452
     607     811     974     580    1158    2310    1635
Boundary for River Rch & Prof#=Little Dry Branc,Reach-1,1
Up Type=0
Dn Type=3
Dn Slope=0.005
Boundary for River Rch & Prof#=Little Dry Branc,Reach-1,2
Up Type=0
Dn Type=3
Dn Slope=0.005
Boundary for River Rch & Prof#=Little Dry Branc,Reach-1,3
Up Type=0
Dn Type=3
Dn Slope=0.005
Boundary for River Rch & Prof#=Little Dry Branc,Reach-1,4
Up Type=0
Dn Type=3
Dn Slope=0.005
Boundary for River Rch & Prof#=Little Dry Branc,Reach-1,5
Up Type=0
Dn Type=3
Dn Slope=0.005
Boundary for River Rch & Prof#=Little Dry Branc,Reach-1,6
Up Type=0
Dn Type=3
Dn Slope=0.005
Boundary for River Rch & Prof#=Little Dry Branc,Reach-1,7
Up Type=0
Dn Type=3
Dn Slope=0.005

--- Little Dry Branch Trib A.g01 (geometry) ---

Geom Title=Existing Conditions

River Reach=Little Dry Branc,Reach-1
Reach XY= 30
      2719126.00      6827361.00      2719226.01      6827276.45
      2719170.53      6827058.55      2718977.36      6826801.35
      2718974.02      6826016.67      2718829.45      6825909.75
      2718772.19      6825412.56      2718531.36      6825213.70
      2718474.13      6824772.15      2718376.60      6824701.00
      2718520.24      6824563.54      2718573.66      6824316.52
      2718378.14      6824005.03      2718423.18      6823819.20
      2718228.18      6823555.55      2718222.55      6823112.25
      2717984.31      6823007.84      2717926.48      6822899.82
      2718070.58      6822855.82      2718124.81      6822723.03
      2717885.75      6822471.53      2717781.44      6822455.75
      2717717.52      6822313.59      2717576.00      6822403.90
      2717389.37      6822274.73      2717467.98      6822107.69
      2717362.60      6821846.91      2717181.83      6821763.33
      2717076.83      6821551.22      2717126.00      6821461.00

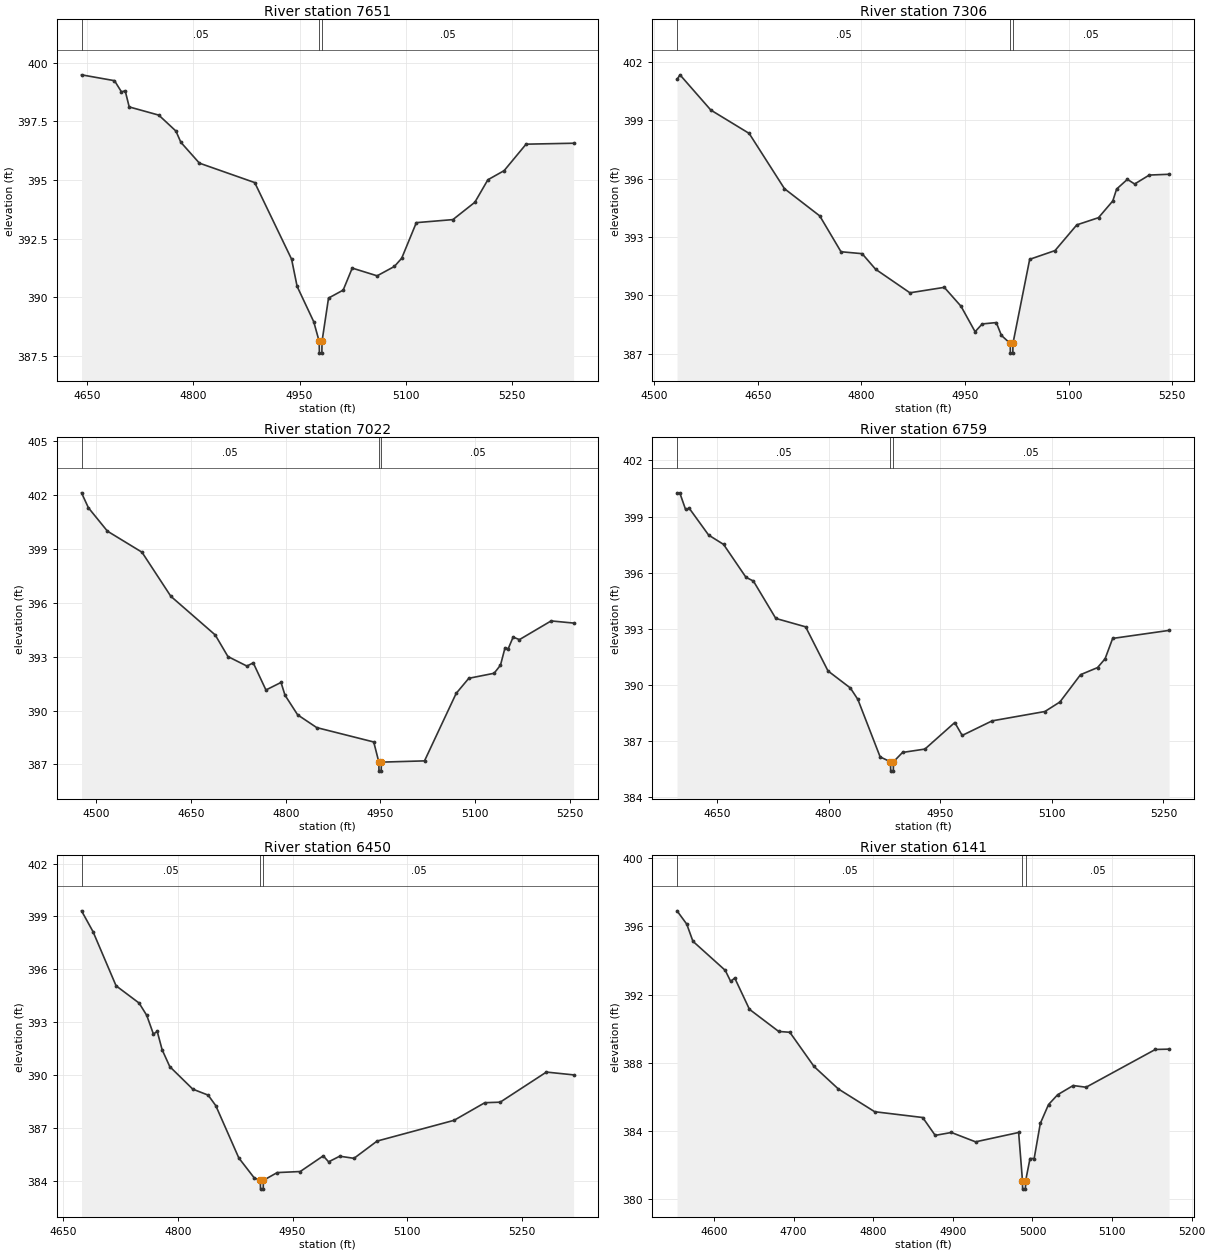
Type RM Length L Ch R = 1,7651,345,345,345
BEGIN DESCRIPTION:
Little Dry Branch Trib A7651.393
END DESCRIPTION:
XS GIS Cut Line= 3
      2719520.64      6827098.57      2719177.25      6827200.50
      2718850.97      6827286.01
#Sta/Elev= 30
  4641.8  399.49  4688.4  399.24  4698.3  398.76  4703.5  398.81  4709.2  398.12
  4751.0  397.77  4775.2  397.09  4782.2  396.61  4808.4  395.72  4886.6  394.89
  4938.7  391.62  4946.5  390.46  4970.0  388.95  4977.7  388.11  4978.0  387.61
  4981.5  387.61  4981.7  388.11  4990.9  389.96  5011.6  390.30  5024.4  391.24
  5059.6  390.91  5084.0  391.31  5094.3  391.66  5115.0  393.18  5166.7  393.31
  5197.7  394.05  5216.1  395.01  5239.1  395.40  5270.1  396.53  5337.3  396.57
#Mann=3,-1,0
  4641.8    0.05       0  4977.7    0.05       0  4981.7    0.05       0
Bank Sta=4977.7,4981.7
Exp/Cntr=0.3,0.1

Type RM Length L Ch R = 1,7306,284,284,284
BEGIN DESCRIPTION:
Little Dry Branch Trib A7306.16
END DESCRIPTION:
XS GIS Cut Line= 3
      2719488.15      6826815.73      2719026.58      6826913.29
      2718798.81      6826990.29
#Sta/Elev= 30
  4533.1  401.09  4537.4  401.33  4582.0  399.52  4637.5  398.32  4688.6  395.48
  4739.7  394.08  4770.4  392.24  4801.0  392.14  4820.5  391.34  4870.2  390.13
  4919.9  390.41  4944.1  389.44  4964.5  388.13  4974.8  388.53  4995.2  388.60
  5002.6  387.94  5015.3  387.53  5015.6  387.03  5019.1  387.03  5019.3  387.53
  5043.5  391.85  5080.2  392.30  5111.7  393.62  5143.1  393.99  5163.8  394.85
  5169.3  395.46  5184.9  395.96  5195.4  395.72  5216.6  396.18  5245.3  396.22
#Mann=3,-1,0
  4533.1    0.05       0  5015.3    0.05       0  5019.3    0.05       0
Bank Sta=5015.3,5019.3
Exp/Cntr=0.3,0.1

Type RM Length L Ch R = 1,7022,263,263,263
BEGIN DESCRIPTION:
Little Dry Branch Trib A7022.32
END DESCRIPTION:
XS GIS Cut Line= 3
      2719496.81      6826597.31      2718968.47      6826645.69
      2718720.48      6826663.72
#Sta/Elev= 30
  4476.6  402.10  4487.5  401.27  4517.6  399.97  4572.3  398.80  4618.0  396.35
  4688.3  394.20  4708.4  393.00  4738.5  392.47  4748.5  392.65  4768.6  391.14
  4792.5  391.56  4798.8  390.85  4818.8  389.76  4849.0  389.05  4939.3  388.25
  4947.4  387.13  4947.6  386.63  4951.1  386.63  4951.4  387.13  5019.7  387.20
  5069.8  390.95  5089.8  391.79  5129.9  392.07  5140.0  392.52  5147.2  393.49
  5152.2  393.43  5160.0  394.08  5170.0  393.94  5220.2  394.98  5255.8  394.86
#Mann=3,-1,0
  4476.6    0.05       0  4947.4    0.05       0  4951.4    0.05       0
Bank Sta=4947.4,4951.4
Exp/Cntr=0.3,0.1

Type RM Length L Ch R = 1,6759,309,309,309
BEGIN DESCRIPTION:
Little Dry Branch Trib A6758.92
END DESCRIPTION:
XS GIS Cut Line= 3
      2719378.42      6826384.87      2718973.59      6826414.46
      2718720.99      6826454.07
#Sta/Elev= 30
  4596.1  400.27  4599.8  400.27  4607.6  399.38  4612.6  399.44  4638.6  398.01
  4658.7  397.51  4688.8  395.75  4698.8  395.55  4728.9  393.55  4769.0  393.10
  4799.1  390.74  4829.1  389.83  4839.2  389.22  4869.2  386.14  4883.1  385.88
  4883.4  385.38  4886.9  385.38  4887.1  385.88  4899.3  386.38  4929.4  386.56
  4969.5  387.98  4979.5  387.29  5019.8  388.07  5090.7  388.57  5110.9  389.08
  5138.6  390.54  5161.5  390.92  5171.6  391.39  5181.8  392.48  5257.7  392.91
#Mann=3,-1,0
  4596.1    0.05       0  4883.1    0.05       0  4887.1    0.05       0
Bank Sta=4883.1,4887.1
Exp/Cntr=0.3,0.1

Type RM Length L Ch R = 1,6450,309,309,309
BEGIN DESCRIPTION:
Little Dry Branch Trib A6449.7
END DESCRIPTION:
XS GIS Cut Line= 3
      2719300.99      6826077.85      2718977.08      6826104.99
      2718660.66      6826140.90
#Sta/Elev= 30
  4674.0  399.32  4689.0  398.14  4719.2  395.06  4749.3  394.08  4759.3  393.38
  4768.0  392.32  4773.0  392.47  4779.4  391.43  4789.4  390.47  4819.5  389.19
  4839.6  388.85  4849.6  388.25  4879.7  385.28  4899.8  384.15  4907.8  384.01
  4908.1  383.51  4911.6  383.51  4911.8  384.01  4929.9  384.45  4960.0  384.51
  4990.1  385.40  4997.1  385.06  5011.6  385.38  5030.3  385.26  5060.5  386.24
  5161.2  387.42  5201.4  388.42  5221.5  388.45  5281.9  390.16  5317.5  390.00
#Mann=3,-1,0
  4674.0    0.05       0  4907.8    0.05       0  4911.8    0.05       0
Bank Sta=4907.8,4911.8
Exp/Cntr=0.3,0.1

Type RM Length L Ch R = 1,6141,225,225,225
BEGIN DESCRIPTION:
Little Dry Branch Trib A6140.78
END DESCRIPTION:
XS GIS Cut Line= 3
      2719265.70      6825804.42      2718826.04      6825879.09
      2718659.21      6825921.51
#Sta/Elev= 30
  4553.5  396.92  4565.7  396.14  4573.5  395.13  4614.1  393.42  4620.9  392.77
  4626.0  392.97  4644.5  391.13  4681.2  389.83  4695.2  389.78  4725.6  387.77
  4756.1  386.45  4801.8  385.11  4862.1  384.77  4877.8  383.72  4898.1  383.89
  4928.5  383.34  4982.6  383.89  4987.4  381.06  4987.6  380.56  4991.1  380.56
  4991.4  381.06  4996.9  382.36  5002.1  382.36  5009.8  384.42  5020.1  385.53
  5031.6  386.11  5051.1  386.65  5067.3  386.55  5154.3  388.77  5171.6  388.79
#Mann=3,-1,0
  4553.5    0.05       0  4987.4    0.05       0  4991.4    0.05       0
Bank Sta=4987.4,4991.4
Exp/Cntr=0.3,0.1

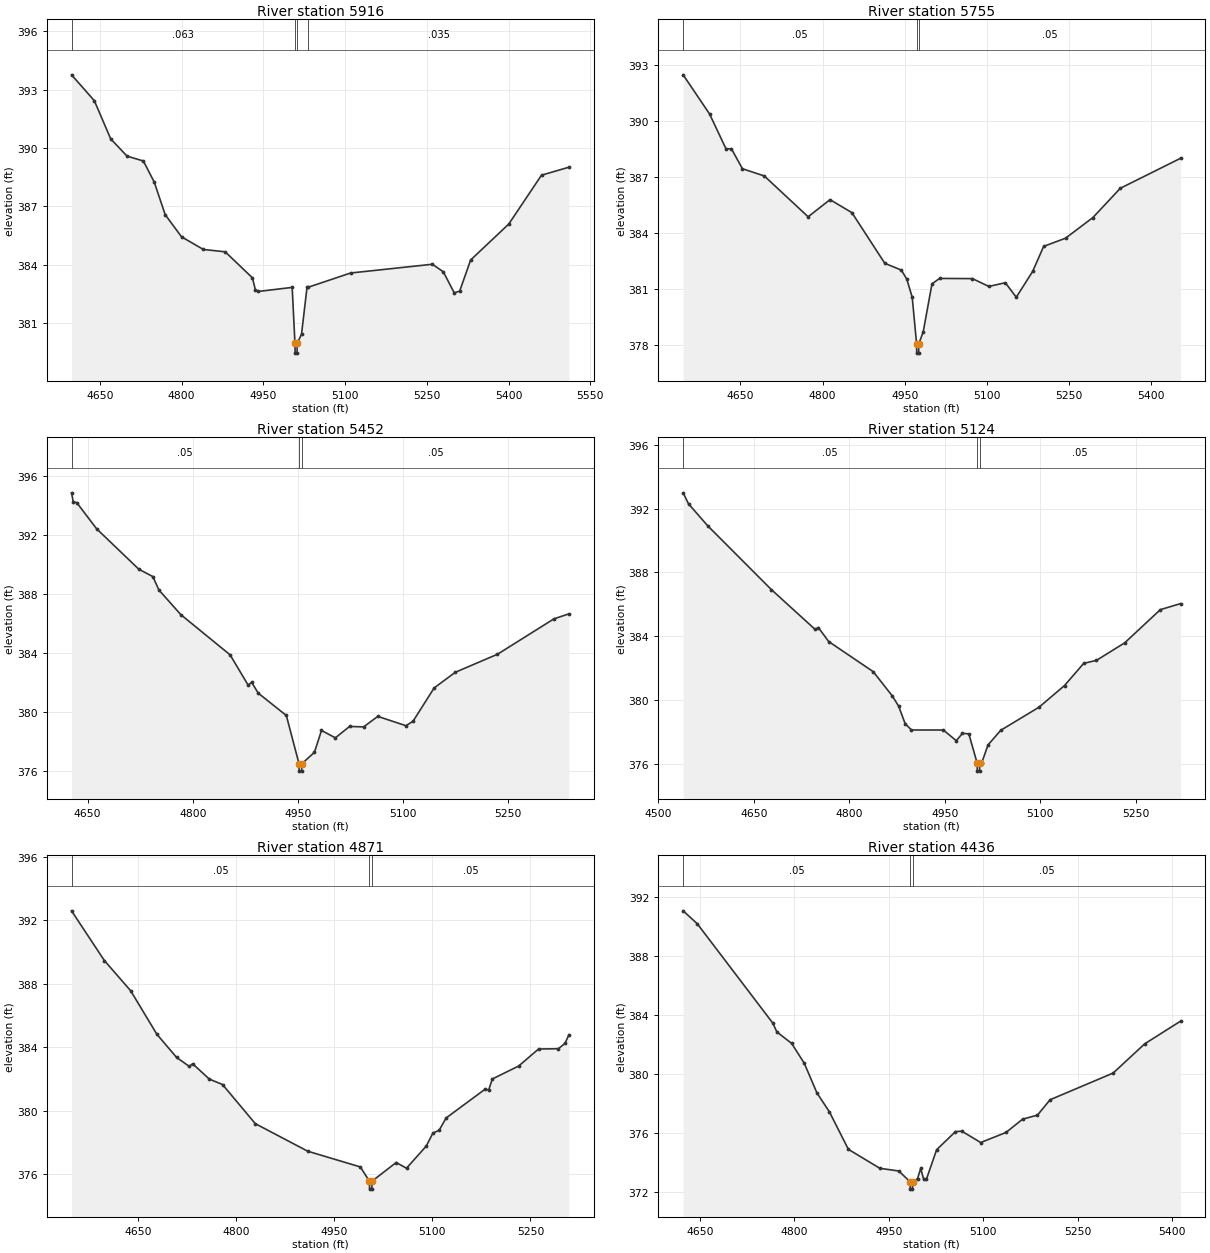
Type RM Length L Ch R = 1,5916,161,161,161
BEGIN DESCRIPTION:
Little Dry Branch Trib A5915.52
END DESCRIPTION:
XS GIS Cut Line= 3
      2719227.73      6825666.72      2718825.37      6825653.94
      2718315.78      6825635.23
#Sta/Elev= 30
  4598.2  393.77  4640.0  392.44  4670.0  390.48  4700.0  389.59  4730.0  389.34
  4750.0  388.25  4770.0  386.58  4800.0  385.44  4840.1  384.79  4880.1  384.67
  4930.1  383.33  4935.5  382.71  4940.5  382.63  5003.0  382.84  5008.1  379.96
  5008.4  379.46  5011.9  379.46  5012.1  379.96  5020.1  380.43  5030.2  382.84
  5032.6  382.85  5110.2  383.58  5260.3  384.03  5280.3  383.64  5300.3  382.56
  5310.3  382.65  5330.4  384.25  5400.4  386.10  5460.4  388.61  5510.7  389.02
#Mann=4,-1,0
  4598.2   0.063       0  5008.1   0.063       0  5012.1   0.063       0
  5032.6   0.035       0
Bank Sta=5008.1,5012.1
Exp/Cntr=0.3,0.1

Type RM Length L Ch R = 1,5755,303,303,303
BEGIN DESCRIPTION:
Little Dry Branch Trib A5755.06
END DESCRIPTION:
XS GIS Cut Line= 3
      2719234.18      6825517.94      2718778.75      6825509.13
      2718326.00      6825514.24
#Sta/Elev= 30
  4545.5  392.48  4593.7  390.38  4623.7  388.51  4633.7  388.51  4653.7  387.44
  4693.7  387.05  4773.7  384.86  4813.7  385.78  4853.7  385.08  4913.8  382.36
  4943.8  382.00  4953.8  381.52  4963.8  380.54  4971.8  378.04  4972.0  377.54
  4975.5  377.54  4975.8  378.04  4983.8  378.67  4999.9  381.26  5013.8  381.55
  5073.8  381.54  5103.8  381.12  5133.8  381.32  5153.8  380.54  5183.8  381.93
  5203.8  383.27  5243.8  383.71  5293.8  384.82  5343.8  386.39  5453.8  388.00
#Mann=3,-1,0
  4545.5    0.05       0  4971.8    0.05       0  4975.8    0.05       0
Bank Sta=4971.8,4975.8
Exp/Cntr=0.3,0.1

Type RM Length L Ch R = 1,5452,328,328,328
BEGIN DESCRIPTION:
Little Dry Branch Trib A5451.94
END DESCRIPTION:
XS GIS Cut Line= 3
      2719011.70      6825245.67      2718636.18      6825275.95
      2718304.63      6825311.58
#Sta/Elev= 30
  4627.0  394.83  4629.4  394.23  4634.4  394.17  4662.8  392.40  4723.0  389.67
  4743.1  389.17  4751.8  388.26  4783.2  386.59  4853.4  383.88  4879.2  381.83
  4884.2  382.02  4893.6  381.29  4933.7  379.78  4951.8  376.52  4952.0  376.02
  4955.5  376.02  4955.8  376.52  4973.8  377.29  4983.9  378.77  5003.7  378.27
  5024.0  379.04  5044.1  379.01  5064.3  379.72  5104.5  379.09  5114.6  379.39
  5144.7  381.64  5174.9  382.70  5235.2  383.92  5315.7  386.31  5337.2  386.65
#Mann=3,-1,0
  4627.0    0.05       0  4951.8    0.05       0  4955.8    0.05       0
Bank Sta=4951.8,4955.8
Exp/Cntr=0.3,0.1

Type RM Length L Ch R = 1,5124,253,253,253
BEGIN DESCRIPTION:
Little Dry Branch Trib A5124.29
END DESCRIPTION:
XS GIS Cut Line= 3
      2718984.40      6824996.10      2718520.90      6825017.85
      2718204.31      6825043.00
#Sta/Elev= 30
  4539.0  392.99  4547.4  392.30  4577.4  390.93  4677.6  386.92  4746.4  384.42
  4751.4  384.54  4767.7  383.66  4837.7  381.77  4867.8  380.24  4877.8  379.59
  4887.8  378.51  4897.8  378.11  4947.8  378.11  4968.2  377.44  4977.9  377.90
  4987.9  377.87  5001.0  376.03  5001.2  375.53  5004.7  375.53  5005.0  376.03
  5008.0  376.03  5018.0  377.17  5038.0  378.09  5098.2  379.54  5138.3  380.90
  5168.4  382.29  5188.5  382.48  5232.9  383.58  5288.8  385.66  5320.6  386.04
#Mann=3,-1,0
  4539.0    0.05       0  5001.0    0.05       0  5005.0    0.05       0
Bank Sta=5001,5005
Exp/Cntr=0.3,0.1

Type RM Length L Ch R = 1,4871,435,435,435
BEGIN DESCRIPTION:
Little Dry Branch Trib A4870.72
END DESCRIPTION:
XS GIS Cut Line= 3
      2718926.06      6824739.31      2718469.43      6824780.71
      2718169.96      6824823.41
#Sta/Elev= 30
  4547.9  392.61  4598.2  389.47  4638.3  387.57  4678.5  384.82  4708.6  383.36
  4728.2  382.79  4733.2  382.96  4758.8  381.99  4778.9  381.65  4829.1  379.18
  4909.4  377.44  4989.8  376.45  5003.6  375.55  5003.9  375.05  5007.4  375.05
  5007.6  375.55  5044.6  376.73  5060.4  376.37  5090.7  377.77  5100.8  378.59
  5110.3  378.76  5121.0  379.54  5181.1  381.37  5186.1  381.30  5191.7  382.00
  5232.1  382.82  5262.4  383.89  5292.7  383.91  5302.8  384.24  5308.9  384.79
#Mann=3,-1,0
  4547.9    0.05       0  5003.6    0.05       0  5007.6    0.05       0
Bank Sta=5003.6,5007.6
Exp/Cntr=0.3,0.1

Type RM Length L Ch R = 1,4436,377,377,377
BEGIN DESCRIPTION:
Little Dry Branch Trib A4435.94
END DESCRIPTION:
XS GIS Cut Line= 3
      2718918.26      6824479.37      2718532.04      6824496.41
      2718129.13      6824521.57
#Sta/Elev= 30
  4623.2  391.07  4645.5  390.20  4765.6  383.46  4772.1  382.86  4795.6  382.08
  4815.7  380.73  4835.7  378.73  4855.7  377.43  4885.7  374.90  4935.8  373.61
  4965.8  373.43  4983.8  372.70  4984.1  372.20  4987.6  372.20  4987.8  372.70
  4995.6  372.91  5000.6  373.60  5005.3  372.88  5009.8  372.88  5025.9  374.87
  5055.9  376.10  5065.9  376.13  5096.0  375.36  5136.1  376.04  5162.4  376.94
  5186.2  377.22  5206.2  378.26  5306.4  380.07  5356.5  382.05  5413.5  383.59
#Mann=3,-1,0
  4623.2    0.05       0  4983.8    0.05       0  4987.8    0.05       0
Bank Sta=4983.8,4987.8
Exp/Cntr=0.3,0.1

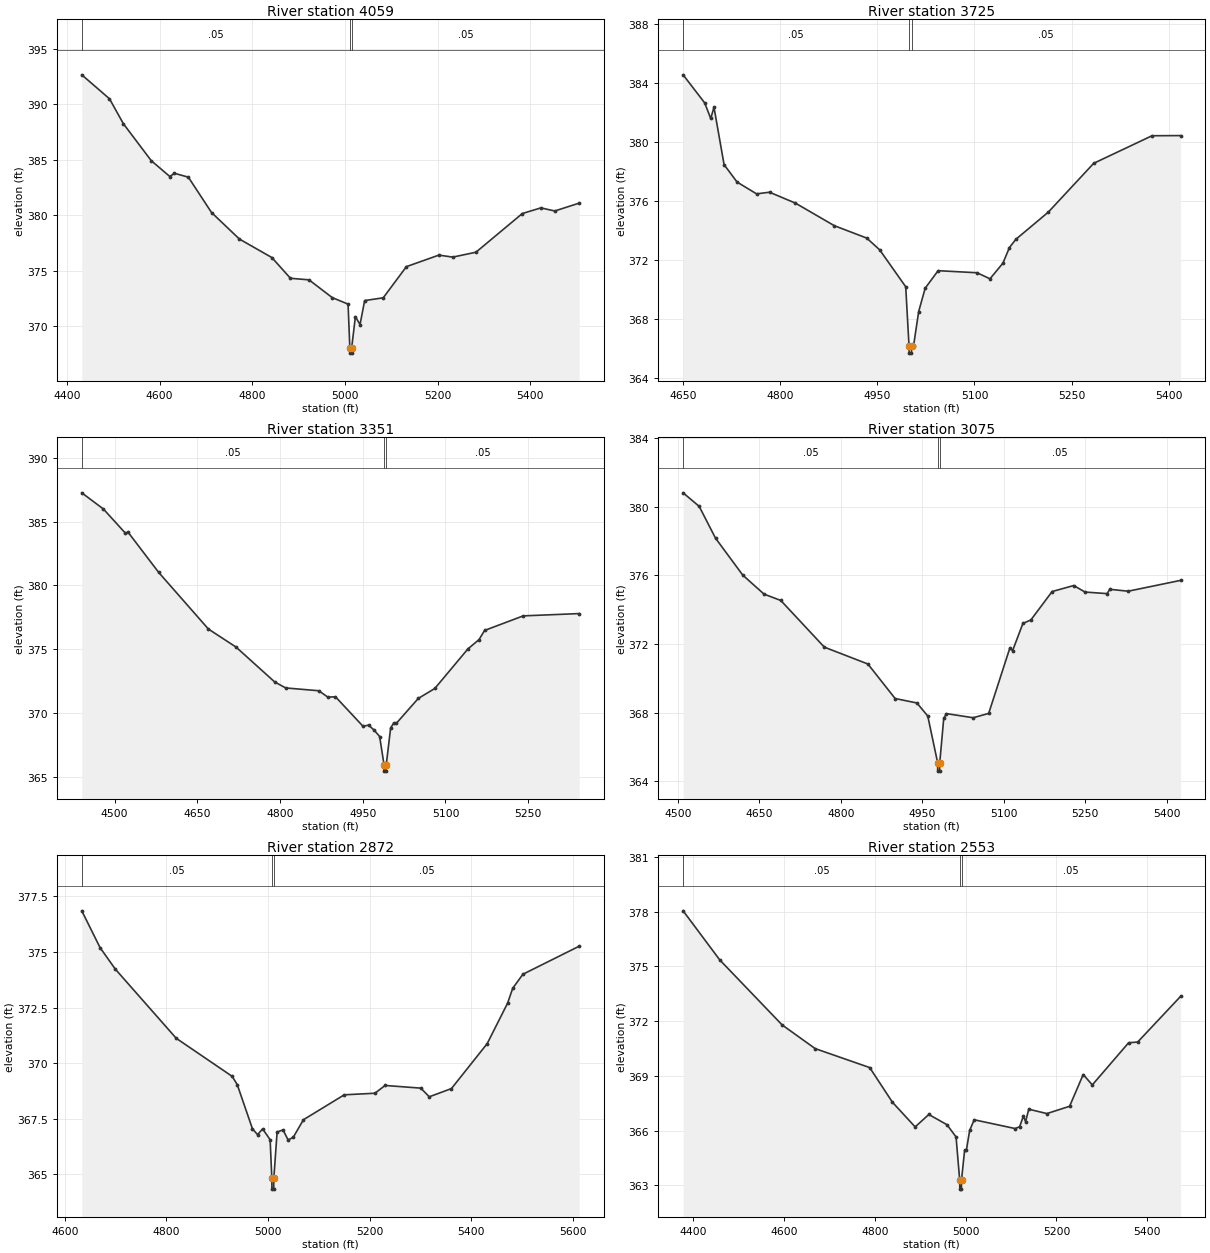
Type RM Length L Ch R = 1,4059,334,334,334
BEGIN DESCRIPTION:
Little Dry Branch Trib A4058.58
END DESCRIPTION:
XS GIS Cut Line= 3
      2719045.69      6824131.64      2718471.75      6824163.82
      2717973.33      6824184.77
#Sta/Elev= 30
  4431.9  392.66  4491.7  390.50  4521.7  388.25  4581.8  384.92  4621.9  383.49
  4631.9  383.78  4661.9  383.43  4712.0  380.24  4772.1  377.85  4842.2  376.18
  4882.3  374.31  4922.4  374.17  4972.4  372.57  5006.7  371.98  5010.5  368.06
  5010.7  367.56  5014.2  367.56  5014.5  368.06  5022.5  370.85  5032.5  370.14
  5042.5  372.30  5082.6  372.55  5132.6  375.36  5202.7  376.40  5232.7  376.22
  5282.7  376.66  5382.8  380.15  5422.9  380.66  5452.9  380.38  5505.6  381.09
#Mann=3,-1,0
  4431.9    0.05       0  5010.5    0.05       0  5014.5    0.05       0
Bank Sta=5010.5,5014.5
Exp/Cntr=0.3,0.1

Type RM Length L Ch R = 1,3725,374,374,374
BEGIN DESCRIPTION:
Little Dry Branch Trib A3724.97
END DESCRIPTION:
XS GIS Cut Line= 3
      2718759.20      6823887.43      2718406.68      6823876.68
      2717992.01      6823882.68
#Sta/Elev= 30
  4650.5  384.53  4683.7  382.63  4693.1  381.57  4698.1  382.33  4713.7  378.44
  4733.7  377.26  4763.8  376.46  4783.8  376.57  4823.8  375.83  4883.8  374.30
  4933.8  373.46  4953.8  372.66  4993.9  370.16  4999.0  366.16  4999.3  365.66
  5002.8  365.66  5003.0  366.16  5006.0  366.16  5013.9  368.48  5023.9  370.06
  5043.9  371.25  5103.9  371.11  5123.9  370.70  5143.9  371.76  5153.9  372.82
  5163.9  373.38  5213.9  375.22  5283.9  378.53  5373.9  380.40  5417.9  380.41
#Mann=3,-1,0
  4650.5    0.05       0  4999.0    0.05       0  5003.0    0.05       0
Bank Sta=4999,5003
Exp/Cntr=0.3,0.1

Type RM Length L Ch R = 1,3351,276,276,276
BEGIN DESCRIPTION:
Little Dry Branch Trib A3350.78
END DESCRIPTION:
XS GIS Cut Line= 3
      2718815.26      6823561.42      2718250.10      6823592.51
      2717914.61      6823610.73
#Sta/Elev= 30
  4440.5  387.25  4479.8  385.98  4519.4  384.10  4524.4  384.17  4580.0  381.02
  4670.1  376.59  4720.2  375.18  4790.3  372.45  4810.3  371.98  4870.4  371.76
  4886.7  371.26  4900.5  371.29  4950.5  368.98  4960.5  369.07  4970.6  368.68
  4980.6  368.18  4988.6  365.97  4988.8  365.47  4992.3  365.47  4992.6  365.97
  5000.6  368.86  5006.1  369.22  5011.1  369.22  5050.7  371.16  5080.7  371.94
  5140.8  375.04  5160.8  375.76  5170.9  376.48  5241.0  377.62  5342.5  377.80
#Mann=3,-1,0
  4440.5    0.05       0  4988.6    0.05       0  4992.6    0.05       0
Bank Sta=4988.6,4992.6
Exp/Cntr=0.3,0.1

Type RM Length L Ch R = 1,3075,203,203,203
BEGIN DESCRIPTION:
Little Dry Branch Trib A3074.59
END DESCRIPTION:
XS GIS Cut Line= 3
      2718715.50      6823296.76      2718218.76      6823326.83
      2717817.05      6823442.23
#Sta/Elev= 30
  4509.6  380.81  4539.2  380.02  4569.2  378.17  4619.3  376.02  4658.5  374.91
  4689.4  374.54  4769.6  371.82  4849.7  370.84  4899.8  368.83  4939.9  368.57
  4959.9  367.81  4978.0  365.10  4978.2  364.60  4981.7  364.60  4982.0  365.10
  4989.3  367.67  4994.3  367.95  5043.5  367.71  5072.0  367.96  5110.9  371.76
  5116.1  371.62  5135.0  373.20  5149.8  373.41  5188.8  375.06  5228.6  375.41
  5249.4  375.03  5289.9  374.94  5295.1  375.19  5328.8  375.08  5425.2  375.71
#Mann=3,-1,0
  4509.6    0.05       0  4978.0    0.05       0  4982.0    0.05       0
Bank Sta=4978,4982
Exp/Cntr=0.3,0.1

Type RM Length L Ch R = 1,2872,319,319,319
BEGIN DESCRIPTION:
Little Dry Branch Trib A2872.29
END DESCRIPTION:
XS GIS Cut Line= 3
      2718591.93      6823112.06      2718221.24      6823124.27
      2717615.73      6823185.61
#Sta/Elev= 30
  4633.3  376.85  4669.2  375.20  4699.3  374.23  4819.3  371.12  4929.4  369.41
  4939.4  369.04  4969.4  367.05  4979.4  366.79  4989.4  367.05  5004.2  366.56
  5007.5  364.84  5007.7  364.34  5011.2  364.34  5011.5  364.84  5017.9  366.91
  5029.6  367.00  5039.6  366.55  5049.7  366.67  5069.8  367.46  5150.2  368.58
  5210.5  368.65  5230.6  369.00  5300.9  368.88  5317.5  368.49  5361.2  368.86
  5431.6  370.88  5471.8  372.70  5481.9  373.37  5502.0  374.00  5612.8  375.26
#Mann=3,-1,0
  4633.3    0.05       0  5007.5    0.05       0  5011.5    0.05       0
Bank Sta=5007.5,5011.5
Exp/Cntr=0.3,0.1

Type RM Length L Ch R = 1,2553,121,121,121
BEGIN DESCRIPTION:
Little Dry Branch Trib A2552.64
END DESCRIPTION:
XS GIS Cut Line= 3
      2718596.63      6823005.66      2717973.27      6822978.26
      2717501.61      6822969.96
#Sta/Elev= 30
  4377.7  378.05  4458.4  375.36  4595.7  371.80  4668.6  370.50  4788.7  369.46
  4838.8  367.56  4888.8  366.21  4918.9  366.89  4958.9  366.33  4978.9  365.66
  4986.9  363.30  4987.2  362.80  4990.7  362.80  4990.9  363.30  4997.8  364.94
  5001.7  364.94  5008.9  366.02  5018.9  366.60  5109.0  366.12  5119.0  366.22
  5127.1  366.80  5132.1  366.50  5139.0  367.18  5179.0  366.94  5229.0  367.34
  5259.0  369.08  5279.0  368.51  5359.0  370.82  5379.0  370.86  5473.4  373.36
#Mann=3,-1,0
  4377.7    0.05       0  4986.9    0.05       0  4990.9    0.05       0
Bank Sta=4986.9,4990.9
Exp/Cntr=0.3,0.1

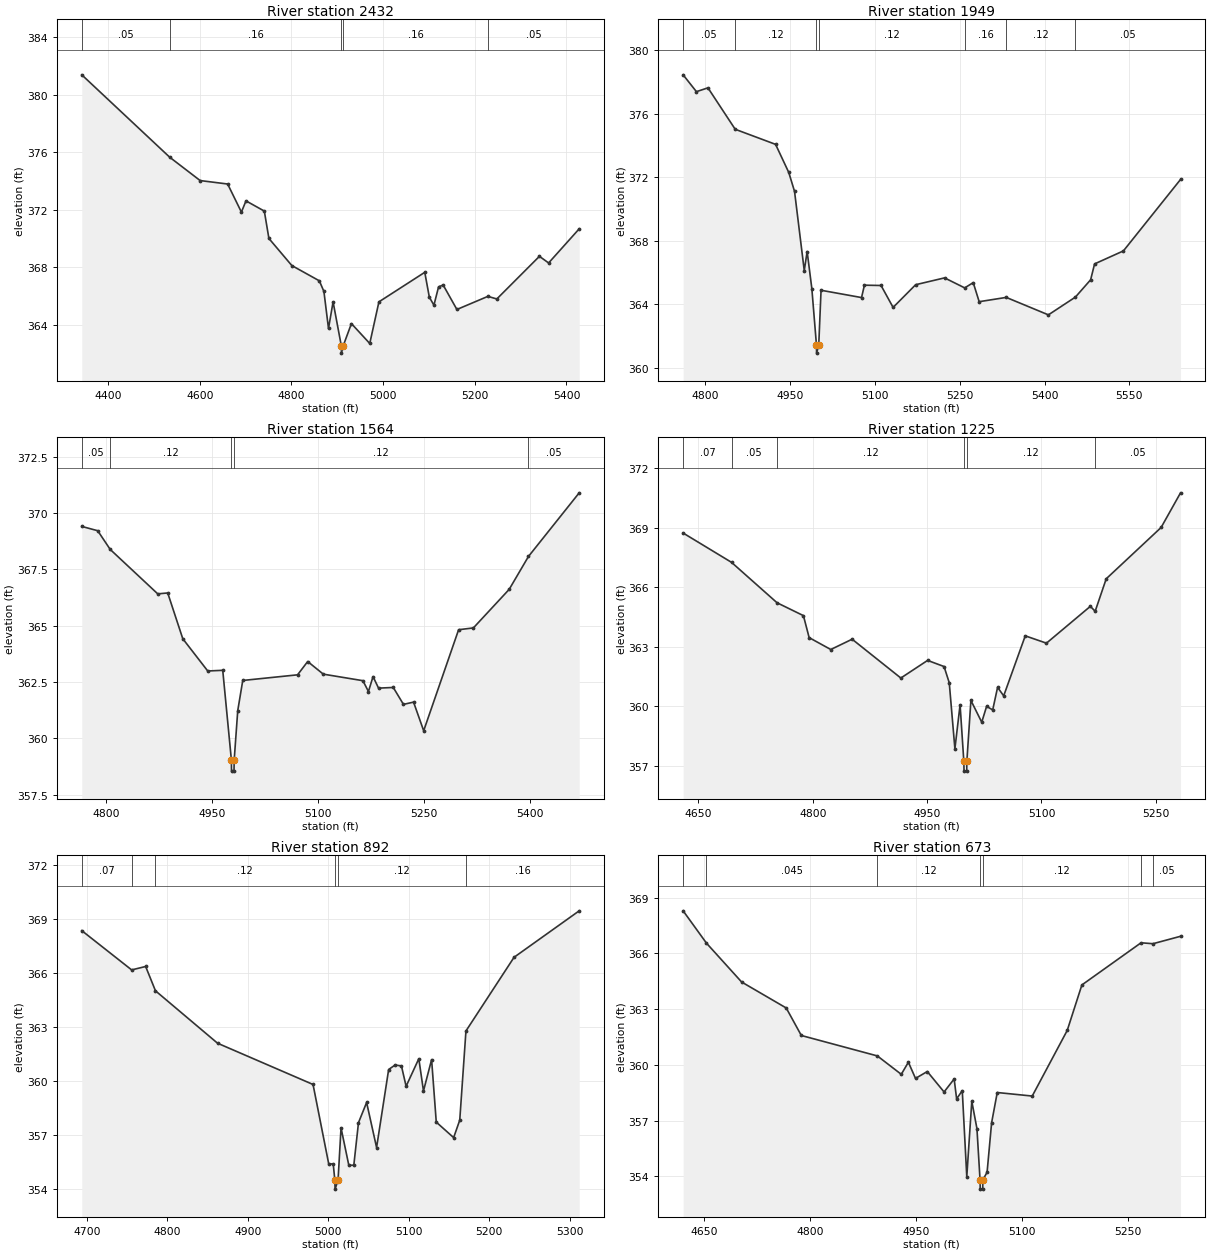
Type RM Length L Ch R = 1,2432,483,483,483
BEGIN DESCRIPTION:
Little Dry Branch Trib A2431.58
END DESCRIPTION:
XS GIS Cut Line= 3
      2718584.20      6822875.49      2717924.99      6822873.24
      2717499.28      6822860.82
#Sta/Elev= 30
  4342.7  381.37  4534.5  375.65  4600.9  374.03  4660.9  373.79  4690.9  371.84
  4700.9  372.62  4740.9  371.91  4750.9  370.01  4800.9  368.13  4860.9  367.07
  4870.9  366.33  4880.9  363.76  4890.9  365.61  4908.9  362.55  4909.2  362.05
  4912.9  362.55  4930.9  364.10  4970.9  362.72  4990.9  365.61  5090.9  367.66
  5100.9  365.93  5110.9  365.38  5121.0  366.65  5131.0  366.78  5161.0  365.08
  5228.6  365.99  5248.1  365.81  5341.0  368.77  5361.1  368.31  5427.8  370.68
#Mann=5,-1,0
  4342.7    0.05       0  4534.5    0.16       0  4908.9    0.07       0
  4912.9    0.16       0  5228.6    0.05       0
Bank Sta=4908.9,4912.9
Exp/Cntr=0.3,0.1

Type RM Length L Ch R = 1,1949,385,385,385
BEGIN DESCRIPTION:
Little Dry Branch Trib A1948.67
END DESCRIPTION:
XS GIS Cut Line= 3
      2718249.05      6822553.12      2718009.06      6822601.70
      2717387.01      6822728.02
#Sta/Elev= 30
  4760.8  378.44  4784.3  377.38  4804.7  377.62  4852.9  375.01  4924.3  374.06
  4947.6  372.29  4957.8  371.10  4975.0  366.11  4980.1  367.31  4988.4  364.98
  4996.6  361.41  4996.8  360.91  5000.6  361.41  5004.7  364.87  5076.3  364.41
  5081.4  365.19  5110.8  365.17  5132.1  363.79  5172.0  365.22  5223.1  365.65
  5258.7  365.02  5273.8  365.35  5284.3  364.15  5332.2  364.42  5406.7  363.32
  5454.5  364.44  5481.4  365.53  5488.4  366.53  5539.4  367.35  5640.4  371.85
#Mann=7,-1,0
  4760.8    0.05       0  4852.9    0.12       0  4996.6    0.07       0
  5000.6    0.12       0  5258.7    0.16       0  5332.2    0.12       0
  5454.5    0.05       0
Bank Sta=4996.6,5000.6
Exp/Cntr=0.3,0.1

Type RM Length L Ch R = 1,1564,339,339,339
BEGIN DESCRIPTION:
Little Dry Branch Trib A1563.52
END DESCRIPTION:
XS GIS Cut Line= 3
      2717904.28      6822207.43      2717734.93      6822378.89
      2717379.96      6822675.07
#Sta/Elev= 30
  4766.2  369.40  4788.7  369.21  4806.4  368.38  4873.6  366.41  4887.7  366.45
  4909.0  364.42  4944.3  362.99  4965.5  363.02  4977.7  359.05  4977.9  358.55
  4981.4  358.55  4981.7  359.05  4986.7  361.23  4993.8  362.57  5071.3  362.82
  5085.6  363.41  5107.7  362.85  5163.7  362.56  5171.5  362.08  5178.0  362.74
  5185.8  362.23  5206.6  362.26  5221.0  361.51  5235.3  361.61  5249.6  360.34
  5299.0  364.82  5319.9  364.90  5370.5  366.61  5397.8  368.07  5469.5  370.89
#Mann=5,-1,0
  4766.2    0.05       0  4806.4    0.12       0  4977.7    0.07       0
  4981.7    0.12       0  5397.8    0.05       0
Bank Sta=4977.7,4981.7
Exp/Cntr=0.3,0.1

Type RM Length L Ch R = 1,1225,333,333,333
BEGIN DESCRIPTION:
Little Dry Branch Trib A1224.51
END DESCRIPTION:
XS GIS Cut Line= 3
      2717780.16      6822092.01      2717498.64      6822347.46
      2717328.36      6822560.02
#Sta/Elev= 30
  4629.9  368.74  4693.4  367.26  4753.1  365.22  4787.7  364.57  4795.2  363.46
  4823.6  362.86  4851.6  363.38  4915.5  361.42  4950.6  362.31  4972.2  362.00
  4979.0  361.18  4986.4  357.85  4993.2  360.07  4998.1  357.22  4998.4  356.72
  5001.9  356.72  5002.1  357.22  5007.4  360.29  5021.6  359.19  5028.0  359.99
  5036.0  359.81  5042.4  360.95  5050.4  360.52  5078.7  363.55  5106.5  363.18
  5164.1  365.04  5170.4  364.79  5184.9  366.43  5256.9  369.02  5282.4  370.77
#Mann=6,-1,0
  4629.9    0.07       0  4693.4    0.05       0  4753.1    0.12       0
  4998.1    0.07       0  5002.1    0.12       0  5170.4    0.05       0
Bank Sta=4998.1,5002.1
Exp/Cntr=0.3,0.1

Type RM Length L Ch R = 1,892,219,219,219
BEGIN DESCRIPTION:
Little Dry Branch Trib A891.83
END DESCRIPTION:
XS GIS Cut Line= 3
      2717752.41      6821995.26      2717464.88      6822112.02
      2717196.82      6822263.84
#Sta/Elev= 30
  4693.5  368.34  4755.5  366.16  4772.9  366.35  4785.1  365.00  4862.3  362.09
  4981.0  359.80  5000.5  355.39  5006.1  355.39  5008.1  354.49  5008.4  353.99
  5012.1  354.49  5015.8  357.39  5025.5  355.31  5031.7  355.32  5037.5  357.68
  5047.6  358.80  5060.0  356.30  5075.0  360.63  5083.0  360.88  5090.9  360.83
  5096.7  359.70  5112.5  361.23  5118.3  359.44  5128.4  361.18  5134.2  357.71
  5155.8  356.85  5163.4  357.82  5171.1  362.77  5230.9  366.86  5311.9  369.44
#Mann=6,-1,0
  4693.5    0.07       0  4755.5   0.045       0  4785.1    0.12       0
  5008.1    0.07       0  5012.1    0.12       0  5171.1    0.16       0
Bank Sta=5008.1,5012.1
Exp/Cntr=0.3,0.1

Type RM Length L Ch R = 1,673,520,520,520
BEGIN DESCRIPTION:
Little Dry Branch Trib A672.58
END DESCRIPTION:
XS GIS Cut Line= 3
      2717751.71      6821863.22      2717371.90      6821921.54
      2717170.27      6822171.37
#Sta/Elev= 30
  4619.8  368.29  4652.9  366.55  4702.7  364.46  4766.0  363.06  4787.4  361.58
  4895.2  360.48  4929.1  359.49  4939.2  360.14  4949.3  359.27  4966.0  359.64
  4989.8  358.54  5004.1  359.24  5007.6  358.17  5015.6  358.61  5022.0  353.98
  5029.1  358.04  5036.4  356.57  5040.8  353.81  5041.1  353.31  5044.6  353.31
  5044.8  353.81  5050.8  354.22  5057.2  356.88  5065.2  358.51  5114.8  358.32
  5164.4  361.85  5185.2  364.30  5269.1  366.57  5286.0  366.52  5325.1  366.92
#Mann=7,-1,0
  4619.8    0.07       0  4652.9   0.045       0  4895.2    0.12       0
  5040.8    0.07       0  5044.8    0.12       0  5269.1    0.16       0
  5286.0    0.05       0
Bank Sta=5040.8,5044.8
Exp/Cntr=0.3,0.1

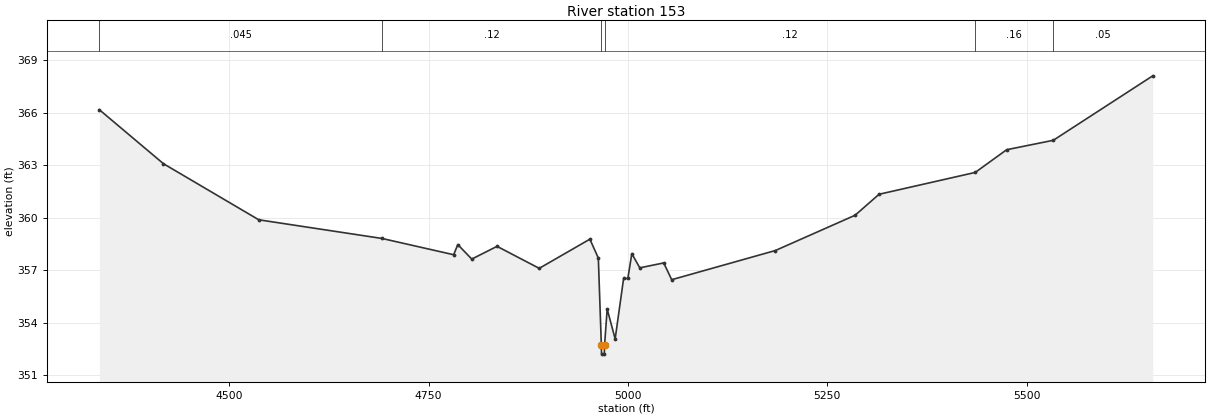
Type RM Length L Ch R = 1,153,0,0,0
BEGIN DESCRIPTION:
Little Dry Branch Trib A152.683
END DESCRIPTION:
XS GIS Cut Line= 3
      2717727.47      6821802.05      2717101.00      6821586.00
      2717098.03      6822244.21
#Sta/Elev= 30
  4337.1  366.18  4417.5  363.09  4537.0  359.88  4691.6  358.81  4781.4  357.88
  4786.6  358.46  4804.1  357.63  4835.8  358.36  4888.7  357.10  4952.2  358.77
  4962.8  357.69  4966.6  352.69  4966.8  352.19  4970.3  352.19  4970.6  352.69
  4973.9  354.77  4983.9  353.06  4994.5  356.52  4999.8  356.52  5004.8  357.94
  5014.8  357.13  5044.8  357.41  5054.8  356.45  5184.8  358.12  5284.8  360.14
  5314.8  361.34  5435.4  362.59  5474.8  363.89  5533.3  364.43  5658.0  368.12
#Mann=6,-1,0
  4337.1   0.045       0  4691.6    0.12       0  4966.6    0.07       0
  4970.6    0.12       0  5435.4    0.16       0  5533.3    0.05       0
Bank Sta=4966.6,4970.6
Exp/Cntr=0.3,0.1

Chan Stop Cuts=-1