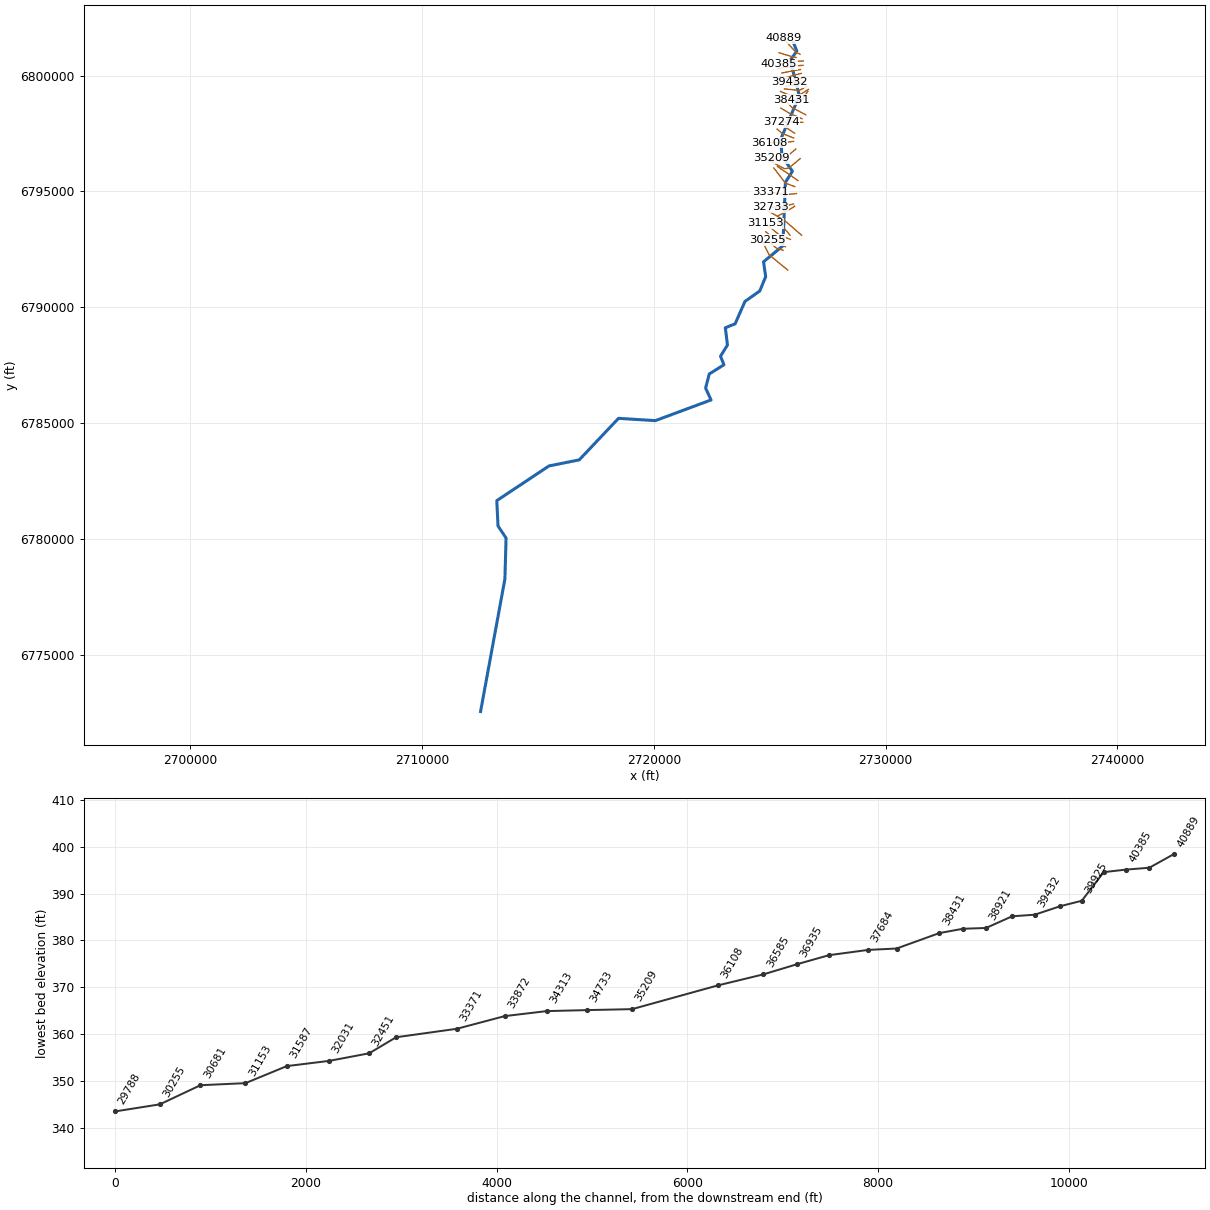
--- Lynn Creek.prj (project) ---

Proj Title=Lynn Creek Base Level Engineering
Current Plan=p01
Default Exp/Contr=0.3,0.1
English Units
Geom File=g01
Flow File=f01
Plan File=p01
Y Axis Title=Elevation
X Axis Title(PF)=Main Channel Distance
X Axis Title(XS)=Station
BEGIN DESCRIPTION:
Lynn Creek
END DESCRIPTION:
DSS Export Rating Curves= 0
DSS Export Rating Curve Sorted= 0
DSS Export Volume Flow Curves= 0
DXF OffsetX= 0
DXF OffsetY= 0
DXF ScaleX= 1
DXF ScaleY= 10

--- Lynn Creek.p01 (plan) ---

Plan Title=Multiple Run
Program Version=4.10
Short Identifier=Multiple
Geom File=g01
Flow File=f01
Subcritical Flow
K Sum by GR= 0
Std Step Tol= 0.01
Critical Tol= 0.01
Num of Std Step Trials= 20
Max Error Tol= 0.3
Flow Tol Ratio= 0.001
Split Flow NTrial= 30
Split Flow Tol= 0.02
Split Flow Ratio= 0.02
Log Output Level= 0
Friction Slope Method= 1
Unsteady Friction Slope Method= 2
Unsteady Bridges Friction Slope Method= 1
Parabolic Critical Depth
Global Vel Dist= 1 , 1 , 1
Global Log Level= 0
CheckData=True
Encroach Param=-1 ,0,0, 0
BEGIN DESCRIPTION:
Multiple Run
END DESCRIPTION:
Computation Interval=1HOUR
Output Interval=1HOUR
Run HTab= 0
Run UNet= 0
Run PostProcess= 0
Run WQNet= 0
UNET Theta= 1
UNET Theta Warmup= 1
UNET ZTol= 0.02
UNET ZSATol= 0.05
UNET MxIter= 20
UNET MaxInSteps= 0
UNET DtIC= 0
UNET DtMin= 0
UNET MaxCRTS= 20
UNET WFStab= 2
UNET SFStab= 1
UNET WFX= 1
UNET SFX= 1
UNET DSS MLevel= 4
UNET DZMax Abort= 100
UNET Convert EG Bridges= 0
UNET Use Existing IB Tables=-1
UNET Froude Reduction=False
UNET Froude Limit= 1
UNET Froude Power= 10
UNET Time Slicing=0,0, 5
UNET Junction Losses=0
Instantaneous Interval=1HOUR
Write IC File= 0
Write IC File at Sim End=0
Echo Input=False
Echo Parameters=False
Echo Output=False
Write Detailed= 0
WQ AD Non Conservative
WQ ULTIMATE=-1
WQ Max Comp Step=1HOUR
WQ Output Interval=15MIN
WQ Output Selected Increments= 0
WQ Output face flow=0
WQ Output face velocity=0
WQ Output face area=0
WQ Output face dispersion=0
WQ Output cell volume=0
WQ Output cell surface area=0
WQ Output cell continuity=0
WQ Output cumulative cell continuity=0
WQ Output face conc=0
WQ Output face dconc_dx=0
WQ Output face courant=0
WQ Output face peclet=0
WQ Output face adv mass=0
WQ Output face disp mass=0
WQ Output cell mass=0
WQ Output cell source sink temp=0
WQ Output cell source sink nsm=0
WQ Output MaxMinRange=-1
WQ Daily Max Min Mean=-1
WQ Daily Range=0
WQ Daily Time=0
WQ Create Restart=0
WQ Fixed Restart=0
WQ System Summary=0
WQ Use Fixed Temperature=0
Sorting and Armoring Iterations= 10
XS Update Threshold= 0.02
Hydraulics Update Threshold= 0.02
Energy Slope Method= 1
Volume Change Method= 0
XS Weighting Method= 0
Number of US Weighted Cross Sections= 1
Number of DS Weighted Cross Sections= 1
Upstream XS Weight=0.25
Main XS Weight=0.5
Downstream XS Weight=0.25
Number of DS XS's Weighted with US Boundary= 1
Upstream Boundary Weight= 1
Weight of XSs Associated with US Boundary= 0
Number of US XS's Weighted with DS Boundary= 1
Downstream Boundary Weight= 0.5
Weight of XSs Associated with DS Boundary= 0.5
Sediment Output Level= 4
Mass or Volume Output= 0
Output Increment Type= 1
Profile and TS Output Increment= 10
XS Output Flag= 0
XS Output Increment= 10
Disregard all LS=0
Disregard all Conn=0
Disregard all Breaches=0
Disregard all Pumps=0

--- Lynn Creek.f01 (steady flow) ---

Flow Title=Multiple
Number of Profiles=7
Profile Names=10-year,25-year,50-year,1pct_min,100-year,1pct_plu,500-year
River Rch & RM= Lynn Creek,Reach-1,40889
     299     383     448     261     520    1038     699
River Rch & RM= Lynn Creek,Reach-1,37983
     643     865    1044     626    1249    2491    1784
River Rch & RM= Lynn Creek,Reach-1,36108
     806    1098    1338     808    1611    3215    2338
River Rch & RM= Lynn Creek,Reach-1,34733
     871    1188    1448     875    1745    3482    2534
River Rch & RM= Lynn Creek,Reach-1,33371
     948    1297    1583     957    1909    3809    2777
River Rch & RM= Lynn Creek,Reach-1,32031
    1113    1534    1883    1144    2282    4554    3354
River Rch & RM= Lynn Creek,Reach-1,30255
    1132    1564    1921    1168    2331    4651    3432
River Rch & RM= Lynn Creek,Reach-1,29788
    1198    1659    2042    1244    2481    4951    3666
River Rch & RM= Lynn Creek,Reach-1,28418
    1405    1957    2418    1476    2946    5878    4377
River Rch & RM= Lynn Creek,Reach-1,25272
    1472    2054    2540    1553    3099    6184    4615
River Rch & RM= Lynn Creek,Reach-1,23982
    1745    2452    3047    1871    3732    7447    5605
River Rch & RM= Lynn Creek,Reach-1,22658
    1801    2529    3143    1929    3849    7680    5776
River Rch & RM= Lynn Creek,Reach-1,19462
    1785    2499    3098    1896    3783    7549    5647
River Rch & RM= Lynn Creek,Reach-1,18104
    1835    2568    3182    1947    3884    7751    5793
River Rch & RM= Lynn Creek,Reach-1,16685
    1824    2550    3159    1931    3853    7688    5738
River Rch & RM= Lynn Creek,Reach-1,16193
    2351    3315    4128    2535    5059   10094    7604
River Rch & RM= Lynn Creek,Reach-1,13354
    2444    3446    4291    2635    5258   10492    7902
River Rch & RM= Lynn Creek,Reach-1,12442
    2426    3411    4240    2598    5183   10342    7754
River Rch & RM= Lynn Creek,Reach-1,9700
    2515    3517    4355    2657    5301   10577    7861
Boundary for River Rch & Prof#=Lynn Creek,Reach-1,1
Up Type=0
Dn Type=3
Dn Slope=0.001
Boundary for River Rch & Prof#=Lynn Creek,Reach-1,2
Up Type=0
Dn Type=3
Dn Slope=0.001
Boundary for River Rch & Prof#=Lynn Creek,Reach-1,3
Up Type=0
Dn Type=3
Dn Slope=0.001
Boundary for River Rch & Prof#=Lynn Creek,Reach-1,4
Up Type=0
Dn Type=3
Dn Slope=0.001
Boundary for River Rch & Prof#=Lynn Creek,Reach-1,5
Up Type=0
Dn Type=3
Dn Slope=0.001
Boundary for River Rch & Prof#=Lynn Creek,Reach-1,6
Up Type=0
Dn Type=3
Dn Slope=0.001
Boundary for River Rch & Prof#=Lynn Creek,Reach-1,7
Up Type=0
Dn Type=3
Dn Slope=0.001

--- Lynn Creek.g01 (geometry) ---

Geom Title=Existing Conditions

River Reach=Lynn Creek,Reach-1
Reach XY= 30
      2726026.00      6801411.00      2726168.39      6801057.67
      2725883.30      6800661.08      2726276.39      6799131.13
      2725476.00      6797261.00      2725527.19      6796523.02
      2725977.00      6795871.45      2725676.34      6795395.96
      2725568.24      6792657.57      2724731.35      6791963.70
      2724825.41      6791322.83      2724568.14      6790704.83
      2723931.04      6790255.92      2723506.39      6789289.91
      2723084.75      6789117.79      2723175.00      6788371.41
      2722875.36      6787890.43      2723024.48      6787522.88
      2722389.53      6787124.44      2722233.76      6786514.42
      2722467.05      6786004.31      2720065.72      6785111.99
      2718476.00      6785211.00      2716782.19      6783418.81
      2715477.58      6783157.17      2713226.00      6781661.00
      2713278.24      6780566.93      2713625.61      6780045.84
      2713575.93      6778281.03      2712526.00      6772561.00

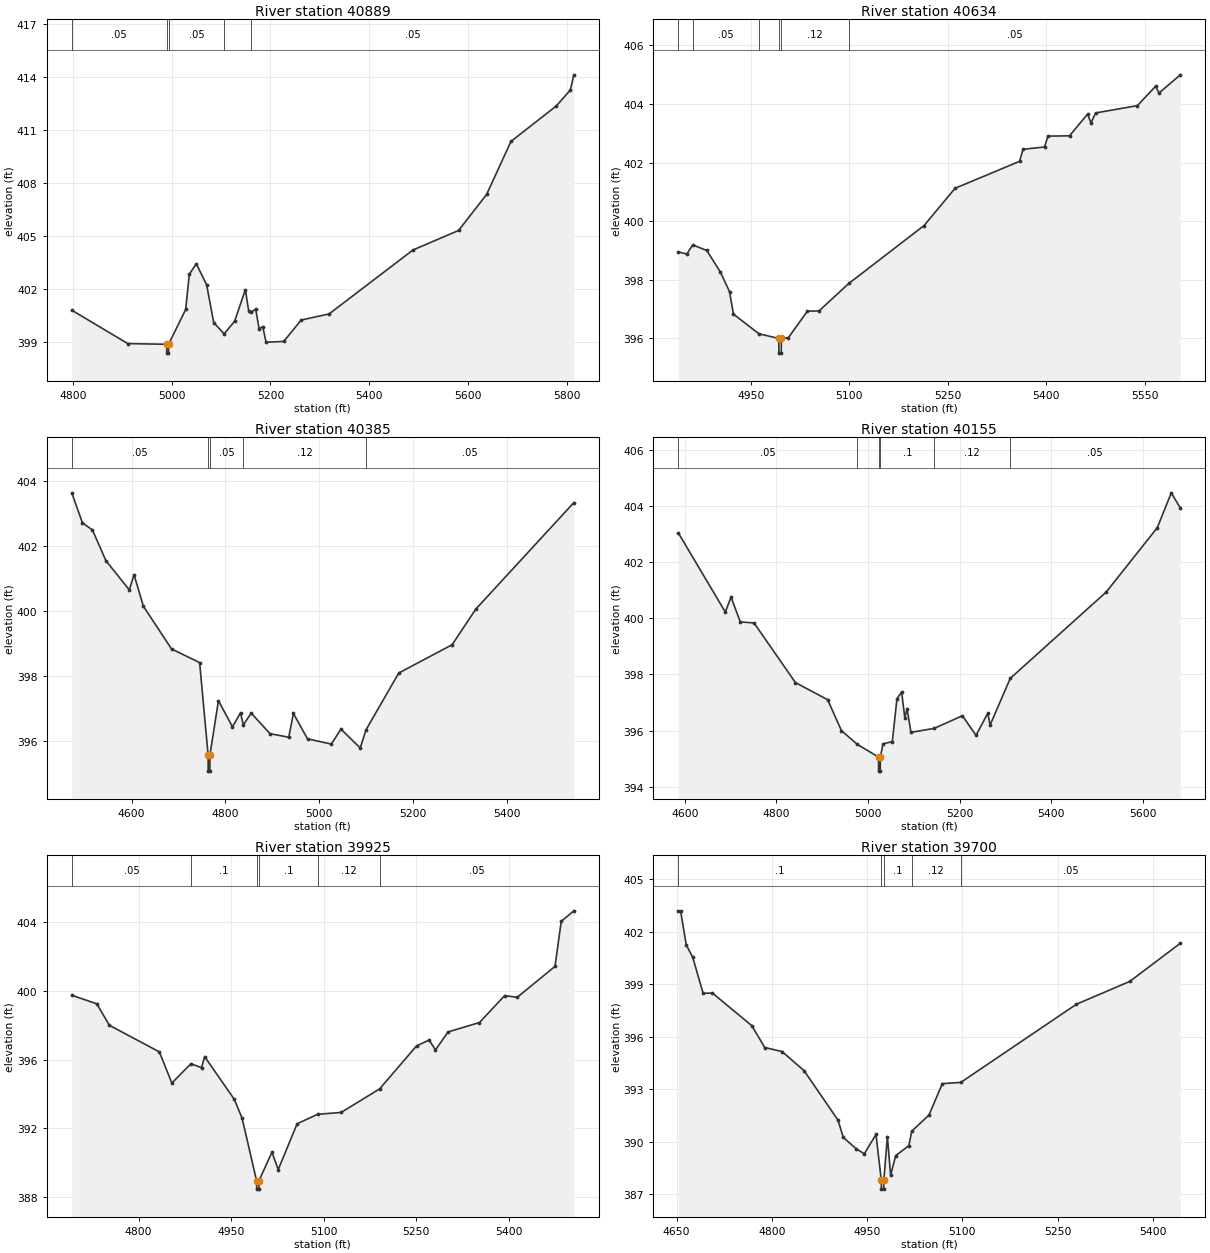
Type RM Length L Ch R = 1,40889,255,255,255
BEGIN DESCRIPTION:
Lynn Creek 85.0
END DESCRIPTION:
XS GIS Cut Line= 3
      2726307.81      6800921.84      2726126.00      6801011.00
      2725576.03      6801610.97
#Sta/Elev= 30
  4797.9  400.81  4911.3  398.92  4989.9  398.88  4990.2  398.38  4993.7  398.38
  4993.9  398.88  5028.5  400.85  5035.9  402.85  5050.0  403.44  5071.0  402.24
  5085.2  400.11  5106.4  399.47  5127.7  400.19  5149.3  401.97  5156.1  400.76
  5161.6  400.71  5170.3  400.87  5177.1  399.76  5184.5  399.88  5191.2  399.00
  5227.0  399.04  5262.2  400.25  5318.9  400.60  5488.8  404.22  5580.9  405.32
  5637.7  407.36  5687.0  410.36  5778.9  412.37  5807.2  413.27  5814.3  414.13
#Mann=5,-1,0
  4797.9    0.05       0  4989.9    0.04       0  4993.9    0.05       0
  5106.4    0.12       0  5161.6    0.05       0
Bank Sta=4989.9,4993.9
Exp/Cntr=0.3,0.1

Type RM Length L Ch R = 1,40634,249,249,249
BEGIN DESCRIPTION:
Lynn Creek 84.0
END DESCRIPTION:
XS GIS Cut Line= 3
      2726138.90      6800782.88      2725976.00      6800811.00
      2725402.61      6800986.31
#Sta/Elev= 30
  4839.4  398.95  4852.5  398.88  4861.5  399.19  4882.9  399.00  4903.2  398.28
  4917.5  397.60  4923.5  396.83  4962.3  396.16  4992.6  396.00  4992.8  395.50
  4996.3  395.50  4996.6  396.00  5007.3  396.03  5036.1  396.93  5053.9  396.94
  5099.5  397.88  5213.9  399.85  5261.1  401.12  5359.4  402.04  5364.7  402.45
  5397.4  402.53  5402.7  402.90  5435.5  402.91  5463.0  403.65  5468.2  403.35
  5475.3  403.69  5539.0  403.94  5566.6  404.60  5571.8  404.37  5604.3  404.99
#Mann=6,-1,0
  4839.4    0.12       0  4861.5    0.05       0  4962.3    0.12       0
  4992.6    0.07       0  4996.6    0.12       0  5099.5    0.05       0
Bank Sta=4992.6,4996.6
Exp/Cntr=0.3,0.1

Type RM Length L Ch R = 1,40385,230,230,230
BEGIN DESCRIPTION:
Lynn Creek 83.0
END DESCRIPTION:
XS GIS Cut Line= 3
      2726448.72      6800627.26      2725926.00      6800611.00
      2725392.27      6800485.73
#Sta/Elev= 30
  4472.2  403.63  4494.9  402.71  4516.3  402.49  4545.0  401.55  4595.0  400.65
  4605.0  401.12  4625.0  400.15  4685.0  398.84  4745.0  398.42  4763.1  395.59
  4763.3  395.09  4766.8  395.09  4767.1  395.59  4785.1  397.25  4815.1  396.45
  4832.2  396.88  4838.2  396.51  4855.1  396.87  4895.1  396.24  4935.1  396.13
  4945.1  396.86  4975.2  396.08  5026.0  395.92  5046.5  396.38  5087.6  395.80
  5100.1  396.36  5169.8  398.10  5283.8  398.97  5334.1  400.06  5543.4  403.33
#Mann=5,-1,0
  4472.2    0.05       0  4763.1    0.07       0  4767.1    0.05       0
  4838.2    0.12       0  5100.1    0.05       0
Bank Sta=4763.1,4767.1
Exp/Cntr=0.3,0.1

Type RM Length L Ch R = 1,40155,230,230,230
BEGIN DESCRIPTION:
Lynn Creek 82.0
END DESCRIPTION:
XS GIS Cut Line= 3
      2726430.84      6800444.74      2726026.00      6800411.00
      2725346.53      6800295.89
#Sta/Elev= 30
  4585.9  403.04  4688.6  400.22  4701.1  400.75  4721.2  399.87  4751.3  399.83
  4841.6  397.71  4911.9  397.10  4942.0  396.00  4976.8  395.51  5022.9  395.06
  5023.1  394.56  5026.6  394.56  5026.9  395.06  5032.7  395.53  5053.0  395.61
  5063.1  397.14  5073.3  397.37  5080.2  396.46  5085.2  396.78  5093.6  395.94
  5144.2  396.08  5205.9  396.53  5235.6  395.83  5261.2  396.62  5266.3  396.20
  5310.3  397.86  5519.6  400.93  5631.1  403.22  5661.6  404.46  5681.3  403.92
#Mann=6,-1,0
  4585.9    0.05       0  4976.8     0.1       0  5022.9    0.07       0
  5026.9     0.1       0  5144.2    0.12       0  5310.3    0.05       0
Bank Sta=5022.9,5026.9
Exp/Cntr=0.3,0.1

Type RM Length L Ch R = 1,39925,225,225,225
BEGIN DESCRIPTION:
Lynn Creek 81.0
END DESCRIPTION:
XS GIS Cut Line= 3
      2726326.05      6800261.01      2726026.00      6800211.00
      2725525.99      6800111.00
#Sta/Elev= 30
  4691.5  399.75  4732.1  399.25  4752.4  398.00  4833.5  396.45  4853.8  394.63
  4884.7  395.76  4901.9  395.53  4907.0  396.17  4955.1  393.68  4967.8  392.57
  4991.1  388.95  4991.4  388.45  4994.9  388.45  4995.1  388.95  5016.1  390.60
  5026.3  389.59  5056.9  392.26  5090.1  392.81  5128.3  392.92  5190.6  394.29
  5250.6  396.80  5271.0  397.14  5281.2  396.56  5301.6  397.61  5352.6  398.16
  5393.4  399.73  5413.8  399.63  5475.0  401.43  5485.2  404.06  5505.6  404.67
#Mann=6,-1,0
  4691.5    0.05       0  4884.7     0.1       0  4991.1    0.07       0
  4995.1     0.1       0  5090.1    0.12       0  5190.6    0.05       0
Bank Sta=4991.1,4995.1
Exp/Cntr=0.3,0.1

Type RM Length L Ch R = 1,39700,268,268,268
BEGIN DESCRIPTION:
Lynn Creek 80.0
END DESCRIPTION:
XS GIS Cut Line= 3
      2726368.27      6800095.57      2726026.00      6800011.00
      2725610.45      6799872.78
#Sta/Elev= 30
  4652.7  403.18  4656.4  403.18  4665.3  401.24  4675.6  400.52  4691.9  398.47
  4706.5  398.49  4768.4  396.63  4789.0  395.38  4816.2  395.15  4850.8  394.06
  4904.2  391.24  4912.6  390.25  4933.2  389.59  4945.7  389.32  4964.1  390.42
  4972.4  387.80  4972.6  387.30  4976.1  387.30  4976.4  387.80  4982.0  390.30
  4987.1  388.08  4995.0  389.21  5015.8  389.78  5020.4  390.61  5047.4  391.52
  5068.5  393.32  5097.6  393.39  5279.6  397.85  5363.6  399.15  5443.2  401.33
#Mann=5,-1,0
  4652.7     0.1       0  4972.4    0.07       0  4976.4     0.1       0
  5020.4    0.12       0  5097.6    0.05       0
Bank Sta=4972.4,4976.4
Exp/Cntr=0.3,0.1

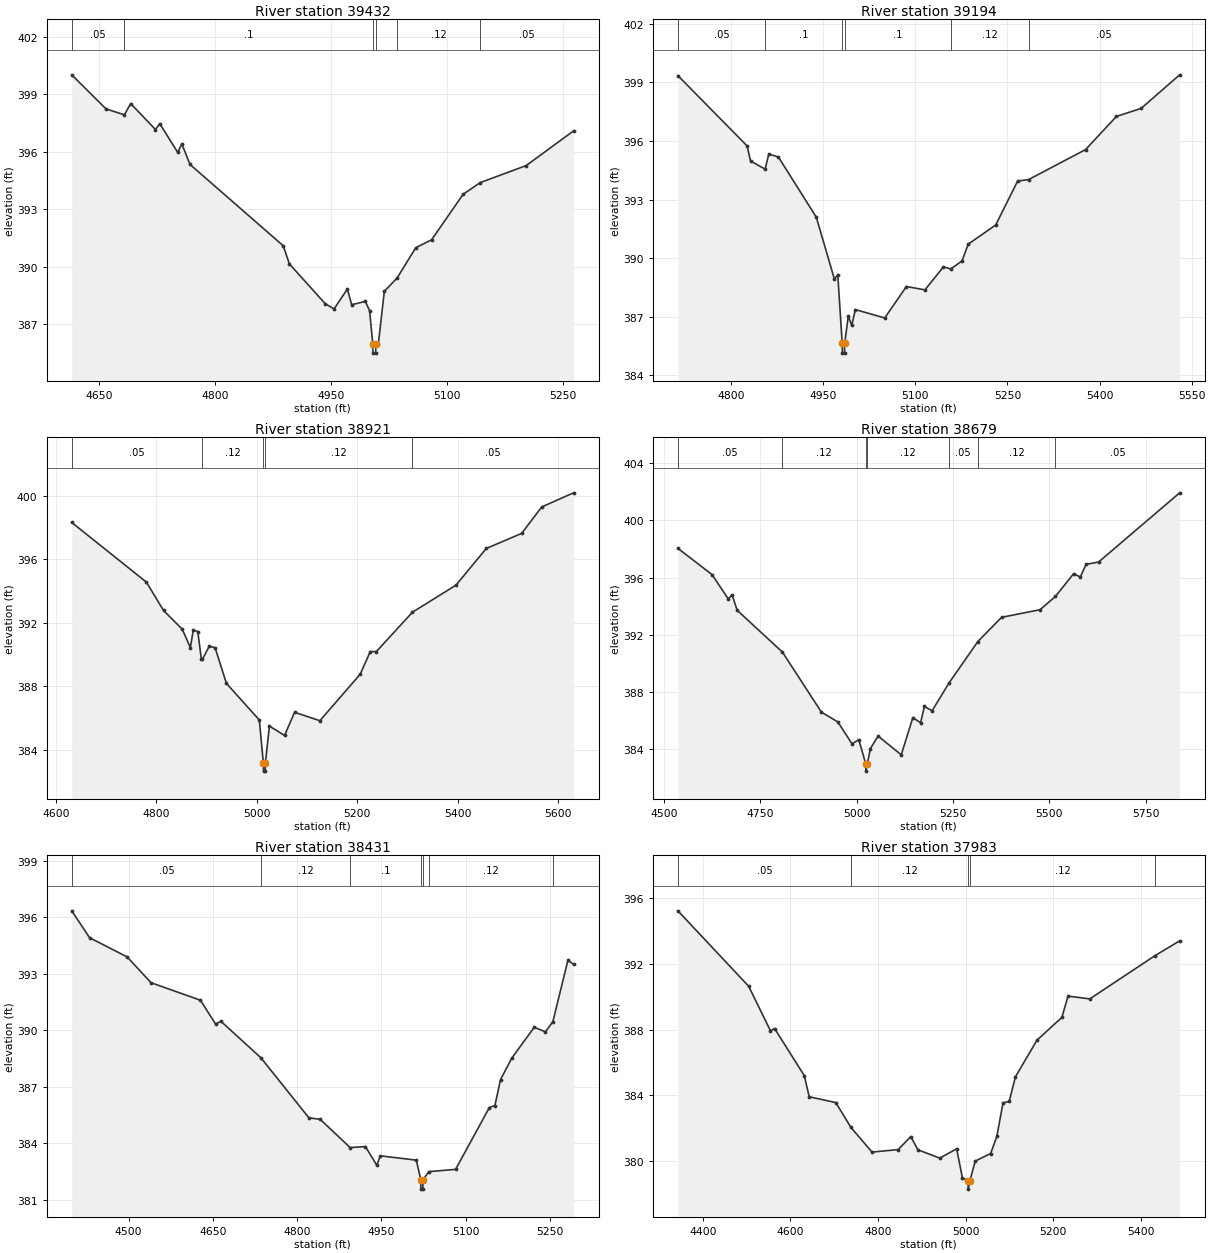
Type RM Length L Ch R = 1,39432,238,238,238
BEGIN DESCRIPTION:
Lynn Creek 79.0
END DESCRIPTION:
XS GIS Cut Line= 3
      2726435.56      6799922.23      2726076.00      6799761.00
      2725826.00      6799711.00
#Sta/Elev= 30
  4615.0  400.02  4659.3  398.24  4683.1  397.93  4691.2  398.52  4723.3  397.16
  4728.8  397.47  4752.0  395.97  4757.4  396.41  4767.9  395.34  4888.5  391.09
  4896.5  390.14  4942.9  388.06  4954.3  387.79  4971.5  388.83  4977.0  388.01
  4994.7  388.18  5000.2  387.70  5004.3  385.98  5004.6  385.48  5008.1  385.48
  5008.3  385.98  5011.6  385.98  5019.3  388.71  5035.9  389.41  5060.0  390.99
  5080.4  391.40  5121.2  393.78  5143.4  394.39  5202.8  395.28  5264.0  397.09
#Mann=6,-1,0
  4615.0    0.05       0  4683.1     0.1       0  5004.3    0.07       0
  5008.3     0.1       0  5035.9    0.12       0  5143.4    0.05       0
Bank Sta=5004.3,5008.3
Exp/Cntr=0.3,0.1

Type RM Length L Ch R = 1,39194,273,273,273
BEGIN DESCRIPTION:
Lynn Creek 78.0
END DESCRIPTION:
XS GIS Cut Line= 3
      2726489.92      6799735.60      2726226.00      6799611.00
      2725703.59      6799552.73
#Sta/Elev= 30
  4713.0  399.35  4825.8  395.75  4831.3  394.98  4855.2  394.56  4861.1  395.34
  4876.8  395.18  4938.5  392.10  4967.9  388.94  4973.5  389.15  4980.7  385.64
  4981.0  385.14  4984.5  385.14  4984.7  385.64  4990.7  387.04  4996.2  386.56
  5002.1  387.37  5050.0  386.94  5085.3  388.55  5115.5  388.38  5145.7  389.56
  5157.6  389.45  5175.9  389.86  5186.0  390.72  5230.8  391.70  5266.5  393.95
  5284.6  394.03  5377.1  395.56  5427.5  397.26  5467.7  397.67  5530.5  399.39
#Mann=6,-1,0
  4713.0    0.05       0  4855.2     0.1       0  4980.7    0.07       0
  4984.7     0.1       0  5157.6    0.12       0  5284.6    0.05       0
Bank Sta=4980.7,4984.7
Exp/Cntr=0.3,0.1

Type RM Length L Ch R = 1,38921,242,242,242
BEGIN DESCRIPTION:
Lynn Creek 77.0
END DESCRIPTION:
XS GIS Cut Line= 3
      2726586.65      6799530.04      2726276.00      6799361.00
      2725633.00      6799425.53
#Sta/Elev= 30
  4631.2  398.33  4779.9  394.57  4814.1  392.78  4851.4  391.60  4867.6  390.44
  4873.3  391.55  4882.4  391.45  4889.4  389.72  4891.6  389.70  4905.2  390.53
  4916.9  390.43  4939.3  388.19  5005.0  385.87  5013.0  383.15  5013.3  382.65
  5016.8  382.65  5017.0  383.15  5025.1  385.49  5055.2  384.90  5075.3  386.36
  5125.6  385.83  5206.0  388.76  5226.1  390.19  5238.2  390.19  5310.1  392.67
  5396.9  394.38  5457.2  396.69  5527.6  397.64  5567.8  399.31  5631.1  400.20
#Mann=5,-1,0
  4631.2    0.05       0  4891.6    0.12       0  5013.0    0.07       0
  5017.0    0.12       0  5310.1    0.05       0
Bank Sta=5013,5017
Exp/Cntr=0.3,0.1

Type RM Length L Ch R = 1,38679,248,248,248
BEGIN DESCRIPTION:
Lynn Creek 76.0
END DESCRIPTION:
XS GIS Cut Line= 4
      2726666.85      6799402.02      2726276.00      6799161.00
      2725796.46      6799175.73      2725461.35      6799313.28
#Sta/Elev= 30
  4536.5  398.05  4624.9  396.22  4667.4  394.51  4677.0  394.81  4690.2  393.72
  4807.6  390.80  4908.8  386.60  4951.3  385.92  4988.0  384.39  5005.7  384.68
  5023.7  382.98  5024.0  382.48  5027.7  382.98  5035.7  384.06  5055.7  384.93
  5115.7  383.62  5145.8  386.22  5165.8  385.86  5175.8  387.00  5195.8  386.70
  5239.1  388.62  5314.1  391.53  5375.9  393.23  5475.5  393.76  5515.6  394.69
  5562.4  396.27  5580.1  396.05  5594.9  396.93  5627.3  397.09  5837.7  401.93
#Mann=7,-1,0
  4536.5    0.05       0  4807.6    0.12       0  5023.7    0.07       0
  5027.7    0.12       0  5239.1    0.05       0  5314.1    0.12       0
  5515.6    0.05       0
Bank Sta=5023.7,5027.7
Exp/Cntr=0.3,0.1

Type RM Length L Ch R = 1,38431,448,448,448
BEGIN DESCRIPTION:
Lynn Creek 75.0
END DESCRIPTION:
XS GIS Cut Line= 4
      2726636.52      6799315.27      2726426.55      6798984.81
      2726226.00      6798961.00      2725925.98      6798961.00
#Sta/Elev= 30
  4398.7  396.35  4430.5  394.92  4497.4  393.90  4539.8  392.53  4627.8  391.60
  4654.9  390.33  4664.3  390.48  4735.5  388.54  4821.0  385.35  4841.1  385.27
  4894.4  383.77  4921.7  383.82  4941.8  382.83  4948.3  383.33  5012.2  383.10
  5020.2  382.06  5020.4  381.56  5023.9  381.56  5024.2  382.06  5034.6  382.49
  5082.2  382.61  5142.2  385.89  5152.2  386.00  5162.2  387.38  5182.2  388.52
  5222.2  390.16  5242.2  389.92  5255.4  390.46  5282.2  393.72  5292.2  393.51
#Mann=7,-1,0
  4398.7    0.05       0  4735.5    0.12       0  4894.4     0.1       0
  5020.2    0.07       0  5024.2     0.1       0  5034.6    0.12       0
  5255.4    0.05       0
Bank Sta=5020.2,5024.2
Exp/Cntr=0.3,0.1

Type RM Length L Ch R = 1,37983,299,299,299
BEGIN DESCRIPTION:
Lynn Creek 74.0
END DESCRIPTION:
XS GIS Cut Line= 3
      2726551.86      6798310.06      2725969.39      6798613.79
      2725631.35      6798966.43
#Sta/Elev= 30
  4343.1  395.24  4504.7  390.64  4554.5  387.92  4564.0  388.06  4631.6  385.19
  4642.9  383.90  4703.5  383.55  4738.2  382.03  4786.2  380.53  4845.9  380.68
  4874.6  381.47  4891.0  380.67  4940.9  380.16  4979.4  380.73  4992.6  378.96
  5005.6  378.77  5005.8  378.27  5009.6  378.77  5021.8  379.98  5057.0  380.44
  5071.1  381.48  5085.3  383.53  5099.4  383.62  5113.6  385.12  5163.0  387.36
  5219.6  388.74  5233.7  390.04  5283.4  389.87  5432.4  392.51  5488.5  393.41
#Mann=5,-1,0
  4343.1    0.05       0  4738.2    0.12       0  5005.6    0.07       0
  5009.6    0.12       0  5432.4    0.05       0
Bank Sta=5005.6,5009.6
Exp/Cntr=0.3,0.1

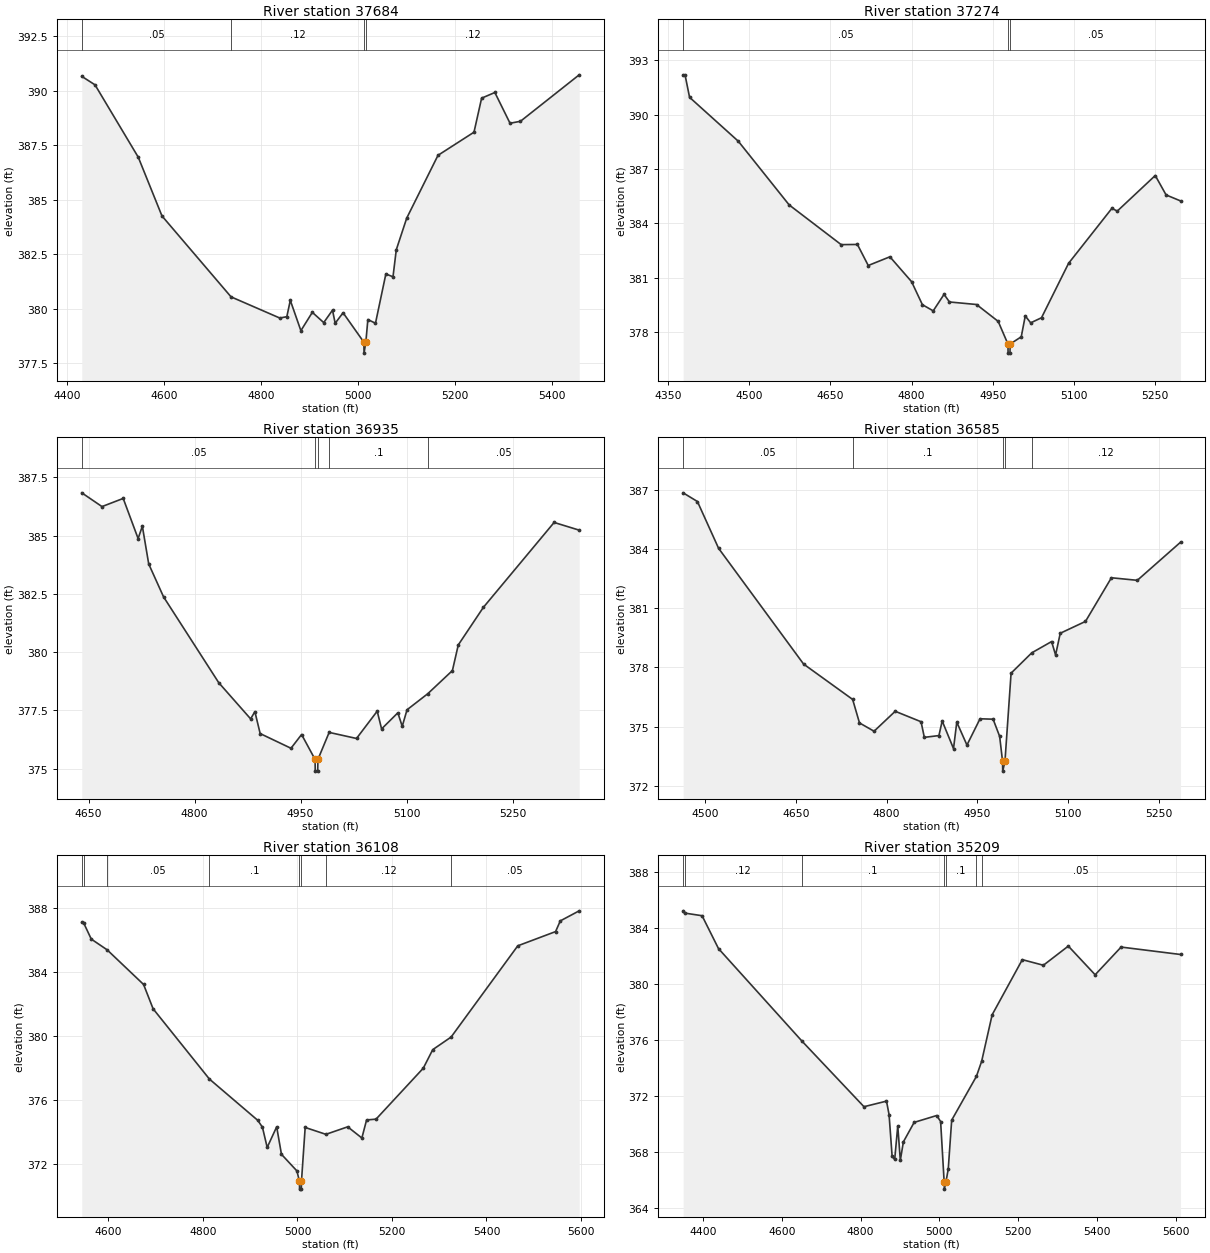
Type RM Length L Ch R = 1,37684,410,410,410
BEGIN DESCRIPTION:
Lynn Creek 73.0
END DESCRIPTION:
XS GIS Cut Line= 3
      2726391.07      6798140.06      2725876.00      6798361.00
      2725474.88      6798596.30
#Sta/Elev= 30
  4430.9  390.66  4458.2  390.27  4547.4  386.95  4596.2  384.26  4738.6  380.55
  4839.0  379.58  4853.6  379.64  4860.8  380.39  4882.6  379.00  4906.2  379.84
  4929.7  379.37  4947.8  379.94  4953.3  379.34  4969.6  379.82  5012.5  378.47
  5012.8  377.97  5016.5  378.47  5020.7  379.51  5036.4  379.34  5057.8  381.60
  5072.5  381.47  5079.3  382.71  5100.8  384.16  5165.3  387.04  5239.5  388.10
  5255.2  389.66  5282.5  389.92  5313.8  388.51  5335.3  388.60  5456.4  390.73
#Mann=4,-1,0
  4430.9    0.05       0  4738.6    0.12       0  5012.5    0.07       0
  5016.5    0.12       0
Bank Sta=5012.5,5016.5
Exp/Cntr=0.3,0.1

Type RM Length L Ch R = 1,37274,339,339,339
BEGIN DESCRIPTION:
Lynn Creek 72.0
END DESCRIPTION:
XS GIS Cut Line= 3
      2726427.88      6797983.71      2725805.92      6797991.03
      2725509.26      6797995.97
#Sta/Elev= 30
  4378.0  392.19  4381.5  392.19  4389.9  390.95  4479.9  388.53  4573.8  385.02
  4669.9  382.83  4699.9  382.84  4719.9  381.68  4759.9  382.16  4799.9  380.79
  4819.9  379.52  4839.9  379.18  4859.9  380.09  4869.9  379.67  4919.9  379.53
  4959.9  378.60  4977.9  377.35  4978.2  376.85  4981.7  376.85  4981.9  377.35
  5002.5  377.75  5009.9  378.90  5019.9  378.52  5039.9  378.80  5089.9  381.80
  5169.9  384.83  5179.9  384.68  5250.0  386.64  5270.0  385.57  5296.7  385.24
#Mann=3,-1,0
  4378.0    0.05       0  4977.9    0.03       0  4981.9    0.05       0
Bank Sta=4977.9,4981.9
Exp/Cntr=0.3,0.1

Type RM Length L Ch R = 1,36935,350,350,350
BEGIN DESCRIPTION:
Lynn Creek 71.0
END DESCRIPTION:
XS GIS Cut Line= 3
      2726076.03      6797510.98      2725776.00      6797711.00
      2725500.42      6797915.56
#Sta/Elev= 30
  4640.4  386.83  4669.0  386.24  4699.0  386.59  4720.1  384.87  4726.1  385.40
  4735.1  383.78  4756.1  382.37  4834.2  378.69  4879.3  377.14  4885.3  377.45
  4892.8  376.51  4936.4  375.88  4951.4  376.47  4970.5  375.40  4970.7  374.90
  4974.2  374.90  4974.5  375.40  4990.4  376.56  5029.1  376.30  5058.4  377.47
  5064.6  376.71  5087.6  377.40  5093.8  376.82  5100.6  377.53  5130.0  378.22
  5164.8  379.21  5173.1  380.31  5208.6  381.92  5308.7  385.56  5344.2  385.23
#Mann=5,-1,0
  4640.4    0.05       0  4970.5    0.07       0  4974.5    0.05       0
  4990.4     0.1       0  5130.0    0.05       0
Bank Sta=4970.5,4974.5
Exp/Cntr=0.3,0.1

Type RM Length L Ch R = 1,36585,477,477,477
BEGIN DESCRIPTION:
Lynn Creek 70.0
END DESCRIPTION:
XS GIS Cut Line= 3
      2726030.33      6797306.12      2725526.00      6797511.00
      2725315.30      6797691.18
#Sta/Elev= 30
  4464.0  386.84  4487.6  386.40  4522.6  384.03  4663.0  378.17  4744.0  376.38
  4755.3  375.19  4779.4  374.77  4814.3  375.78  4857.0  375.25  4862.4  374.46
  4886.5  374.55  4891.9  375.29  4910.6  373.89  4916.0  375.23  4932.8  374.07
  4954.4  375.40  4976.0  375.38  4986.8  374.51  4991.6  373.25  4991.9  372.75
  4995.6  373.25  5005.7  377.71  5039.9  378.74  5072.6  379.31  5079.2  378.63
  5086.9  379.73  5128.6  380.33  5171.4  382.54  5214.2  382.41  5285.6  384.34
#Mann=5,-1,0
  4464.0    0.05       0  4744.0     0.1       0  4991.6    0.07       0
  4995.6     0.1       0  5039.9    0.12       0
Bank Sta=4991.6,4995.6
Exp/Cntr=0.3,0.1

Type RM Length L Ch R = 1,36108,899,899,899
BEGIN DESCRIPTION:
Lynn Creek 69.0
END DESCRIPTION:
XS GIS Cut Line= 3
      2726025.98      6797161.00      2725576.00      6797111.00
      2724975.95      6797111.00
#Sta/Elev= 30
  4543.5  387.09  4547.8  387.04  4563.6  386.05  4597.1  385.38  4674.3  383.21
  4694.4  381.69  4813.6  377.29  4915.8  374.71  4925.8  374.28  4935.9  373.01
  4956.0  374.30  4966.1  372.58  4998.8  371.54  5004.1  370.90  5004.5  370.40
  5008.1  370.40  5008.5  370.90  5016.3  374.26  5060.2  373.83  5106.3  374.30
  5136.3  373.60  5146.3  374.73  5166.3  374.78  5266.3  377.97  5286.3  379.13
  5325.2  379.92  5466.3  385.63  5546.3  386.52  5556.3  387.19  5596.3  387.82
#Mann=8,-1,0
  4543.5    0.05       0  4547.8     0.1       0  4597.1    0.05       0
  4813.6     0.1       0  5004.1    0.07       0  5008.5     0.1       0
  5060.2    0.12       0  5325.2    0.05       0
Bank Sta=5004.1,5008.5
Exp/Cntr=0.3,0.1

Type RM Length L Ch R = 1,35209,476,476,476
BEGIN DESCRIPTION:
Lynn Creek 68.0
END DESCRIPTION:
XS GIS Cut Line= 4
      2726123.80      6796830.32      2725626.00      6796411.00
      2725433.34      6796316.65      2725050.78      6796424.25
#Sta/Elev= 30
  4349.6  385.23  4353.3  385.07  4397.7  384.88  4439.4  382.53  4650.6  375.94
  4808.7  371.23  4865.9  371.63  4872.4  370.67  4880.2  367.68  4886.7  367.46
  4894.5  369.86  4901.0  367.40  4908.8  368.72  4936.1  370.11  4993.3  370.60
  5003.3  370.17  5012.3  365.84  5012.7  365.34  5016.8  365.84  5022.7  366.79
  5031.4  370.27  5094.2  373.40  5107.5  374.48  5134.1  377.80  5210.7  381.74
  5264.2  381.34  5327.5  382.71  5395.6  380.66  5461.5  382.64  5612.4  382.11
#Mann=7,-1,0
  4349.6     0.1       0  4353.3    0.12       0  4650.6     0.1       0
  5012.3    0.07       0  5016.8     0.1       0  5094.2    0.12       0
  5107.5    0.05       0
Bank Sta=5012.3,5016.8
Exp/Cntr=0.3,0.1

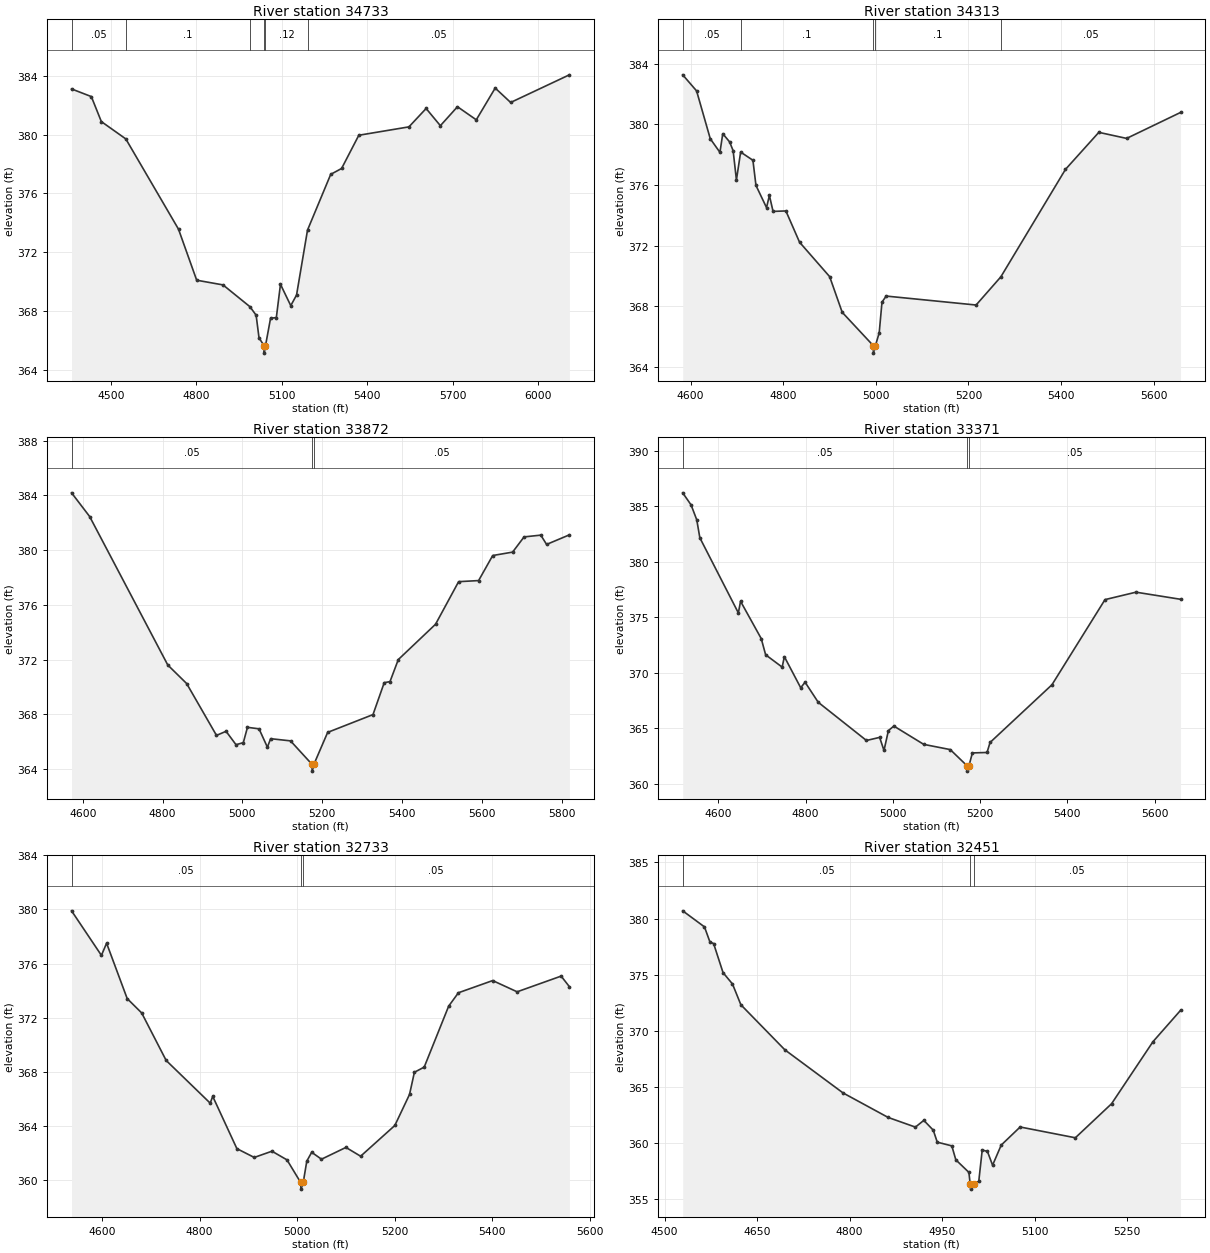
Type RM Length L Ch R = 1,34733,420,420,420
BEGIN DESCRIPTION:
Lynn Creek 67.0
END DESCRIPTION:
XS GIS Cut Line= 4
      2726315.79      6796419.16      2725826.00      6796011.00
      2725637.59      6795980.80      2724826.03      6796410.98
#Sta/Elev= 30
  4362.4  383.10  4431.8  382.58  4466.9  380.88  4552.8  379.70  4737.7  373.56
  4801.5  370.09  4893.9  369.77  4988.2  368.29  5010.1  367.71  5020.2  366.17
  5038.1  365.63  5038.6  365.13  5042.9  365.63  5060.7  367.50  5081.0  367.55
  5095.5  369.81  5131.6  368.36  5151.9  369.08  5190.4  373.50  5271.8  377.29
  5310.0  377.69  5370.4  379.95  5546.3  380.52  5606.6  381.77  5656.6  380.60
  5716.6  381.89  5782.6  381.00  5849.0  383.16  5903.2  382.18  6109.3  384.06
#Mann=6,-1,0
  4362.4    0.05       0  4552.8     0.1       0  4988.2    0.12       0
  5038.1    0.07       0  5042.9    0.12       0  5190.4    0.05       0
Bank Sta=5038.1,5042.9
Exp/Cntr=0.3,0.1

Type RM Length L Ch R = 1,34313,441,441,441
BEGIN DESCRIPTION:
Lynn Creek 66.0
END DESCRIPTION:
XS GIS Cut Line= 3
      2726214.47      6795467.80      2725876.00      6795711.00
      2725329.38      6796077.50
#Sta/Elev= 30
  4583.0  383.26  4613.0  382.20  4642.5  379.05  4663.4  378.15  4669.5  379.38
  4684.3  378.84  4691.9  378.26  4699.0  376.33  4708.1  378.17  4734.6  377.63
  4741.2  375.97  4764.0  374.51  4770.2  375.31  4778.1  374.26  4805.8  374.29
  4835.3  372.23  4900.3  369.96  4927.4  367.61  4994.3  365.42  4994.9  364.92
  4999.2  365.42  5007.3  366.26  5013.3  368.28  5022.3  368.68  5216.5  368.09
  5270.0  369.95  5409.5  377.03  5481.5  379.47  5541.5  379.07  5657.9  380.78
#Mann=5,-1,0
  4583.0    0.05       0  4708.1     0.1       0  4994.3    0.07       0
  4999.2     0.1       0  5270.0    0.05       0
Bank Sta=4994.3,4999.2
Exp/Cntr=0.3,0.1

Type RM Length L Ch R = 1,33872,501,501,501
BEGIN DESCRIPTION:
Lynn Creek 65.0
END DESCRIPTION:
XS GIS Cut Line= 3
      2726075.96      6795211.01      2725676.00      6795361.00
      2725176.01      6796010.98
#Sta/Elev= 30
  4572.1  384.18  4617.4  382.45  4813.2  371.60  4860.4  370.25  4935.2  366.46
  4959.2  366.76  4984.1  365.78  5002.4  365.93  5012.8  367.05  5041.8  366.94
  5062.7  365.60  5070.9  366.22  5120.7  366.06  5174.4  364.35  5175.0  363.85
  5179.3  364.35  5213.7  366.68  5327.3  367.98  5355.4  370.31  5369.9  370.39
  5390.7  372.00  5484.0  374.58  5541.8  377.69  5591.9  377.77  5627.2  379.60
  5677.1  379.85  5705.8  380.96  5747.7  381.09  5762.2  380.41  5819.3  381.11
#Mann=3,-1,0
  4572.1    0.05       0  5174.4    0.05       0  5179.3    0.05       0
Bank Sta=5174.4,5179.3
Exp/Cntr=0.3,0.1

Type RM Length L Ch R = 1,33371,638,638,638
BEGIN DESCRIPTION:
Lynn Creek 64.0
END DESCRIPTION:
XS GIS Cut Line= 3
      2726155.11      6794909.01      2725676.00      6794861.00
      2725025.27      6794968.79
#Sta/Elev= 30
  4518.4  386.22  4537.6  385.13  4550.6  383.79  4557.7  382.17  4646.0  375.40
  4651.0  376.45  4698.4  373.09  4708.5  371.63  4746.4  370.52  4751.4  371.46
  4788.9  368.66  4798.9  369.16  4829.1  367.35  4939.6  363.91  4969.8  364.19
  4979.8  363.01  4989.9  364.80  5002.4  365.21  5070.9  363.56  5131.7  363.09
  5169.7  361.65  5170.4  361.15  5174.7  361.65  5182.4  362.79  5216.0  362.83
  5222.9  363.73  5364.8  368.93  5486.4  376.60  5557.4  377.27  5659.5  376.63
#Mann=3,-1,0
  4518.4    0.05       0  5169.7    0.04       0  5174.7    0.05       0
Bank Sta=5169.7,5174.7
Exp/Cntr=0.3,0.1

Type RM Length L Ch R = 1,32733,282,282,282
BEGIN DESCRIPTION:
Lynn Creek 63.0
END DESCRIPTION:
XS GIS Cut Line= 3
      2726025.96      6794460.99      2725575.86      6794355.94
      2725019.16      6794317.81
#Sta/Elev= 30
  4537.8  379.89  4599.0  376.60  4609.6  377.50  4651.8  373.41  4681.5  372.35
  4731.7  368.84  4821.9  365.69  4827.1  366.19  4876.6  362.33  4912.2  361.68
  4948.5  362.14  4979.3  361.50  5007.2  359.84  5008.0  359.34  5012.6  359.84
  5019.9  361.41  5029.9  362.06  5050.0  361.55  5100.1  362.42  5130.2  361.77
  5200.3  364.04  5230.4  366.33  5240.4  367.97  5260.5  368.35  5310.6  372.85
  5330.6  373.84  5400.8  374.74  5450.9  373.91  5541.1  375.07  5558.0  374.29
#Mann=3,-1,0
  4537.8    0.05       0  5007.2    0.04       0  5012.6    0.05       0
Bank Sta=5007.2,5012.6
Exp/Cntr=0.3,0.1

Type RM Length L Ch R = 1,32451,420,420,420
BEGIN DESCRIPTION:
Lynn Creek 62.0
END DESCRIPTION:
XS GIS Cut Line= 3
      2726075.97      6794360.98      2725676.00      6794111.00
      2725375.97      6793960.99
#Sta/Elev= 30
  4529.3  380.69  4564.6  379.26  4573.5  377.91  4579.4  377.78  4594.7  375.19
  4610.0  374.18  4623.6  372.33  4694.9  368.32  4789.3  364.48  4862.4  362.30
  4906.6  361.44  4920.2  362.04  4935.5  361.17  4942.0  360.10  4965.6  359.77
  4972.1  358.53  4993.3  357.41  4995.3  356.42  4996.1  355.92  5000.8  356.42
  5009.3  356.61  5014.9  359.40  5023.3  359.28  5031.7  358.05  5045.7  359.84
  5076.4  361.45  5165.9  360.49  5224.6  363.52  5291.7  369.04  5336.4  371.83
#Mann=3,-1,0
  4529.3    0.05       0  4995.3    0.05       0  5000.8    0.05       0
Bank Sta=4995.3,5000.8
Exp/Cntr=0.3,0.1

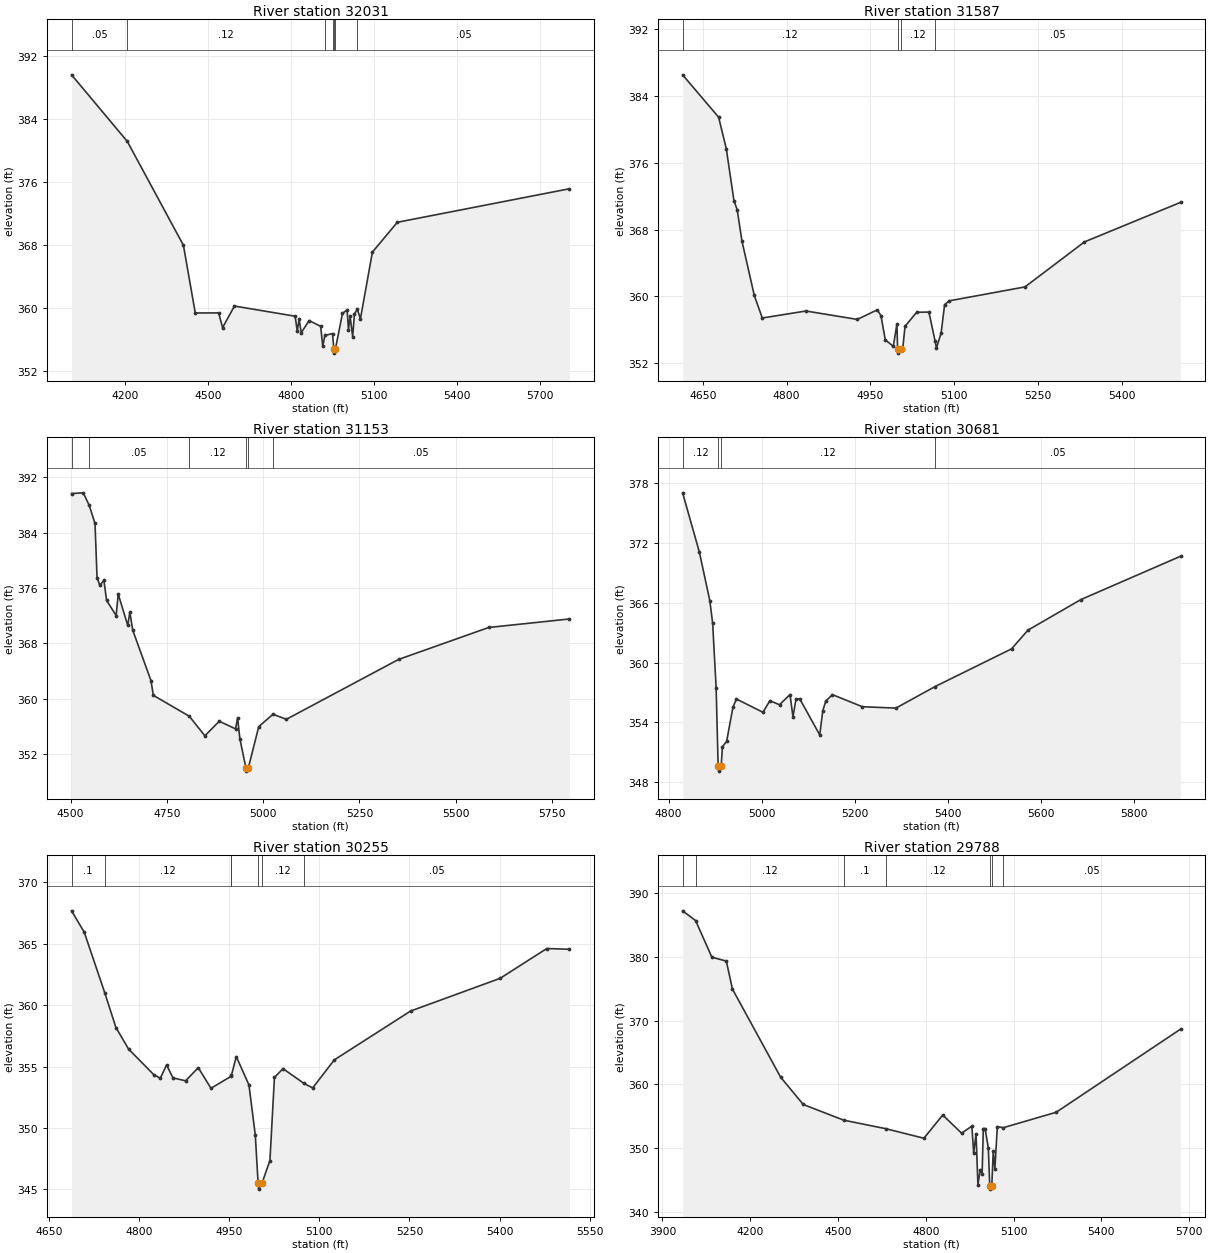
Type RM Length L Ch R = 1,32031,444,444,444
BEGIN DESCRIPTION:
Lynn Creek 61.0
END DESCRIPTION:
XS GIS Cut Line= 3
      2726376.01      6793110.99      2725626.00      6793761.00
      2724926.01      6794160.99
#Sta/Elev= 30
  4007.0  389.65  4208.4  381.19  4411.1  368.00  4453.9  359.40  4538.4  359.41
  4552.6  357.54  4595.4  360.28  4814.7  358.99  4822.4  357.07  4829.0  358.66
  4836.6  356.88  4865.1  358.44  4906.9  357.70  4914.5  355.16  4922.0  356.54
  4949.7  356.79  4954.5  354.80  4955.3  354.30  4960.0  354.80  4985.7  359.34
  5002.4  359.78  5007.4  357.27  5013.2  358.99  5022.5  356.40  5029.0  359.28
  5039.2  359.87  5050.6  358.67  5093.8  367.13  5183.8  370.92  5805.7  375.18
#Mann=7,-1,0
  4007.0    0.05       0  4208.4    0.12       0  4922.0    0.05       0
  4949.7    0.12       0  4954.5    0.07       0  4960.0    0.12       0
  5039.2    0.05       0
Bank Sta=4954.5,4960
Exp/Cntr=0.3,0.1

Type RM Length L Ch R = 1,31587,434,434,434
BEGIN DESCRIPTION:
Lynn Creek 60.0
END DESCRIPTION:
XS GIS Cut Line= 3
      2725875.99      6793111.01      2725626.00      6793411.00
      2725326.00      6793811.00
#Sta/Elev= 30
  4614.0  386.55  4678.4  381.47  4692.1  377.70  4705.8  371.47  4711.6  370.38
  4720.1  366.63  4742.2  360.10  4756.5  357.40  4834.6  358.24  4926.4  357.23
  4962.2  358.38  4968.7  357.69  4976.5  354.78  4990.8  354.00  4997.3  356.70
  4998.5  353.69  4999.3  353.19  5004.0  353.69  5007.6  353.69  5011.8  356.40
  5032.6  358.09  5054.5  358.11  5065.4  354.68  5068.0  353.79  5076.4  355.63
  5082.6  359.01  5091.0  359.46  5226.4  361.13  5332.6  366.52  5504.5  371.26
#Mann=4,-1,0
  4614.0    0.12       0  4998.5    0.07       0  5004.0    0.12       0
  5065.4    0.05       0
Bank Sta=4998.5,5004
Exp/Cntr=0.3,0.1

Type RM Length L Ch R = 1,31153,472,472,472
BEGIN DESCRIPTION:
Lynn Creek 59.0
END DESCRIPTION:
XS GIS Cut Line= 3
      2725894.55      6792933.10      2725426.00      6793111.00
      2724820.11      6793620.77
#Sta/Elev= 30
  4502.4  389.67  4532.9  389.77  4548.4  387.94  4563.3  385.34  4568.6  377.53
  4575.7  376.40  4586.4  377.12  4593.4  374.22  4618.2  372.03  4623.6  375.14
  4648.3  370.61  4653.7  372.53  4661.3  369.91  4708.6  362.64  4714.8  360.50
  4808.0  357.49  4848.6  354.66  4885.9  356.76  4928.3  355.66  4933.6  357.27
  4939.4  354.25  4955.1  350.05  4956.2  349.55  4961.6  350.05  4988.5  355.98
  5025.5  357.77  5060.2  357.04  5351.5  365.69  5585.6  370.31  5795.4  371.54
#Mann=6,-1,0
  4502.4    0.12       0  4548.4    0.05       0  4808.0    0.12       0
  4955.1    0.07       0  4961.6    0.12       0  5025.5    0.05       0
Bank Sta=4955.1,4961.6
Exp/Cntr=0.3,0.1

Type RM Length L Ch R = 1,30681,426,426,426
BEGIN DESCRIPTION:
Lynn Creek 58.0
END DESCRIPTION:
XS GIS Cut Line= 3
      2725676.01      6792610.99      2725526.00      6792711.00
      2724826.02      6793260.99
#Sta/Elev= 30
  4830.0  377.06  4866.1  371.09  4888.6  366.20  4894.6  363.95  4902.1  357.42
  4906.4  349.61  4907.4  349.11  4912.9  349.61  4915.6  351.56  4924.7  352.11
  4938.2  355.54  4945.7  356.35  5002.8  355.02  5017.5  356.18  5038.3  355.78
  5060.9  356.80  5067.2  354.58  5073.9  356.34  5081.7  356.38  5124.8  352.75
  5131.4  355.18  5137.8  356.15  5152.2  356.79  5216.4  355.58  5288.6  355.44
  5372.6  357.60  5537.2  361.39  5572.5  363.27  5686.3  366.34  5900.5  370.69
#Mann=4,-1,0
  4830.0    0.12       0  4906.4    0.07       0  4912.9    0.12       0
  5372.6    0.05       0
Bank Sta=4906.4,4912.9
Exp/Cntr=0.3,0.1

Type RM Length L Ch R = 1,30255,467,467,467
BEGIN DESCRIPTION:
Lynn Creek 57.0
END DESCRIPTION:
XS GIS Cut Line= 3
      2725576.00      6792461.00      2725276.00      6792561.00
      2724894.78      6792902.89
#Sta/Elev= 30
  4687.9  367.69  4709.0  365.95  4743.1  361.02  4761.7  358.19  4782.8  356.43
  4824.9  354.34  4835.5  354.06  4846.0  355.14  4856.6  354.09  4877.6  353.85
  4898.7  354.92  4919.8  353.24  4953.4  354.22  4953.8  354.29  4962.0  355.82
  4983.0  353.51  4993.6  349.41  4998.2  345.53  4999.2  345.03  5004.8  345.53
  5017.9  347.36  5025.4  354.12  5039.6  354.84  5074.5  353.64  5089.0  353.27
  5124.9  355.55  5251.9  359.53  5400.7  362.19  5478.5  364.62  5516.2  364.56
#Mann=7,-1,0
  4687.9     0.1       0  4743.1    0.12       0  4953.4     0.1       0
  4953.8    0.12       0  4998.2    0.07       0  5004.8    0.12       0
  5074.5    0.05       0
Bank Sta=4998.2,5004.8
Exp/Cntr=0.3,0.1

Type RM Length L Ch R = 1,29788,442,442,442
BEGIN DESCRIPTION:
Lynn Creek 56.0
END DESCRIPTION:
XS GIS Cut Line= 3
      2725776.00      6791611.00      2724976.00      6792261.00
      2724676.00      6792861.00
#Sta/Elev= 30
  3968.9  387.23  4013.3  385.70  4068.8  379.95  4118.3  379.34  4139.1  374.95
  4303.7  361.12  4381.2  356.82  4519.3  354.36  4663.4  353.02  4793.5  351.52
  4857.9  355.17  4922.1  352.32  4957.3  353.41  4963.7  349.19  4971.7  352.25
  4978.1  344.22  4986.0  346.59  4992.5  345.96  4996.5  353.03  5002.5  353.03
  5013.7  350.01  5018.5  344.03  5019.6  343.53  5025.5  344.03  5030.4  349.46
  5036.0  346.67  5044.4  353.35  5064.9  353.18  5245.6  355.60  5670.5  368.65
#Mann=7,-1,0
  3968.9    0.05       0  4013.3    0.12       0  4519.3     0.1       0
  4663.4    0.12       0  5018.5    0.07       0  5025.5    0.12       0
  5064.9    0.05       0
Bank Sta=5018.5,5025.5
Exp/Cntr=0.3,0.1