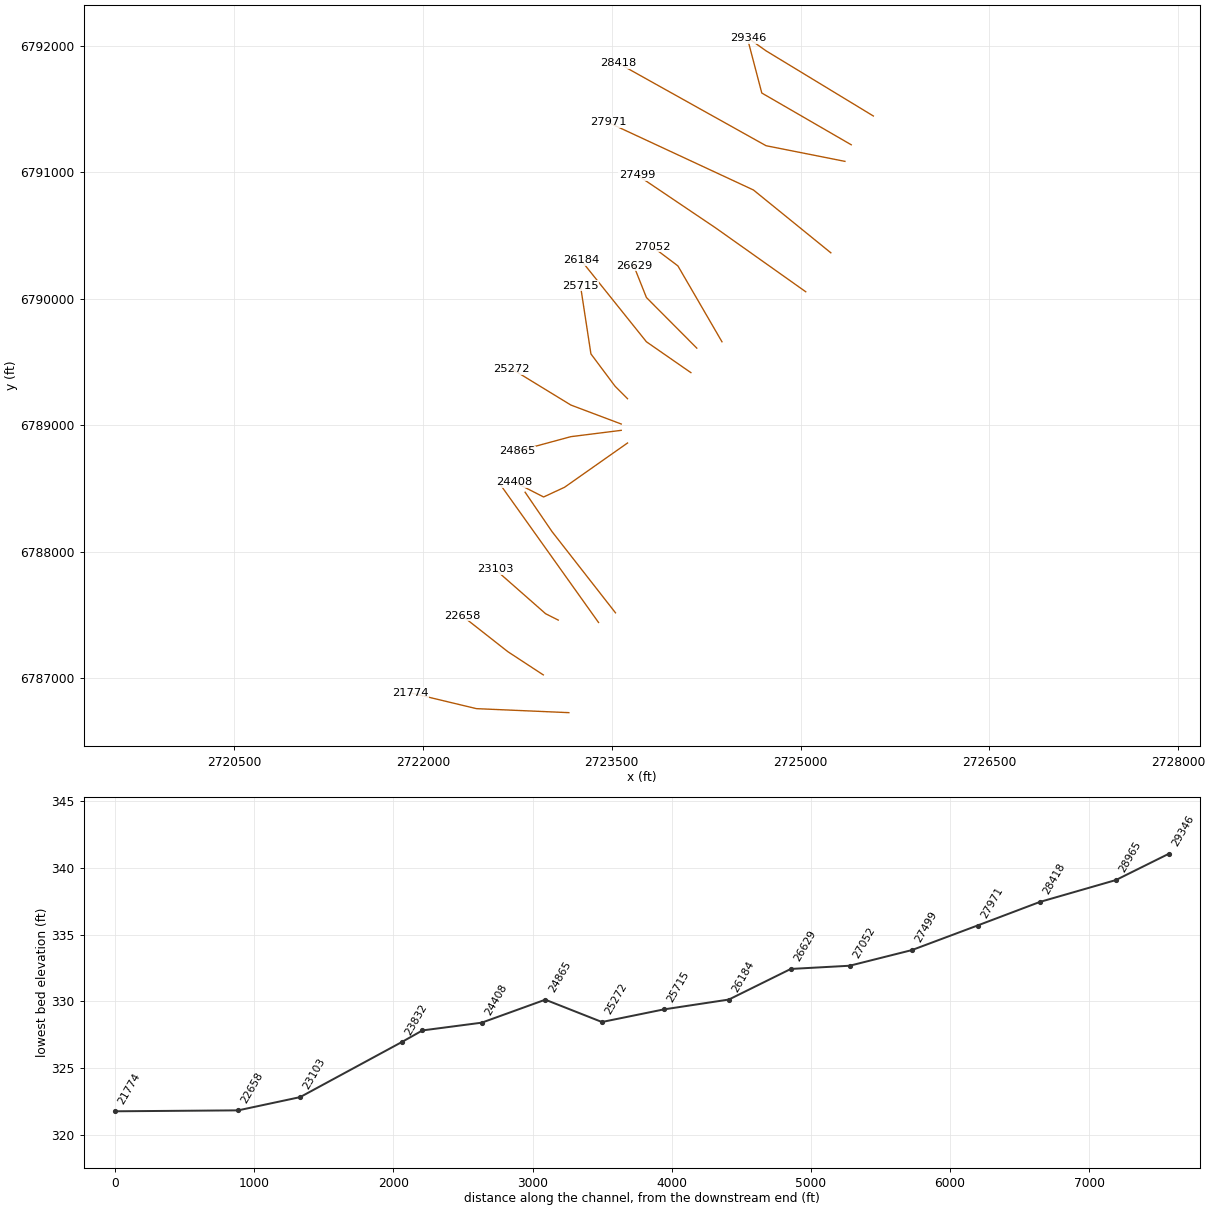
HEC-RAS study Lynn Creek.prj: Lynn Creek Base Level Engineering

--- Lynn Creek.g01 (geometry) --- (continued)

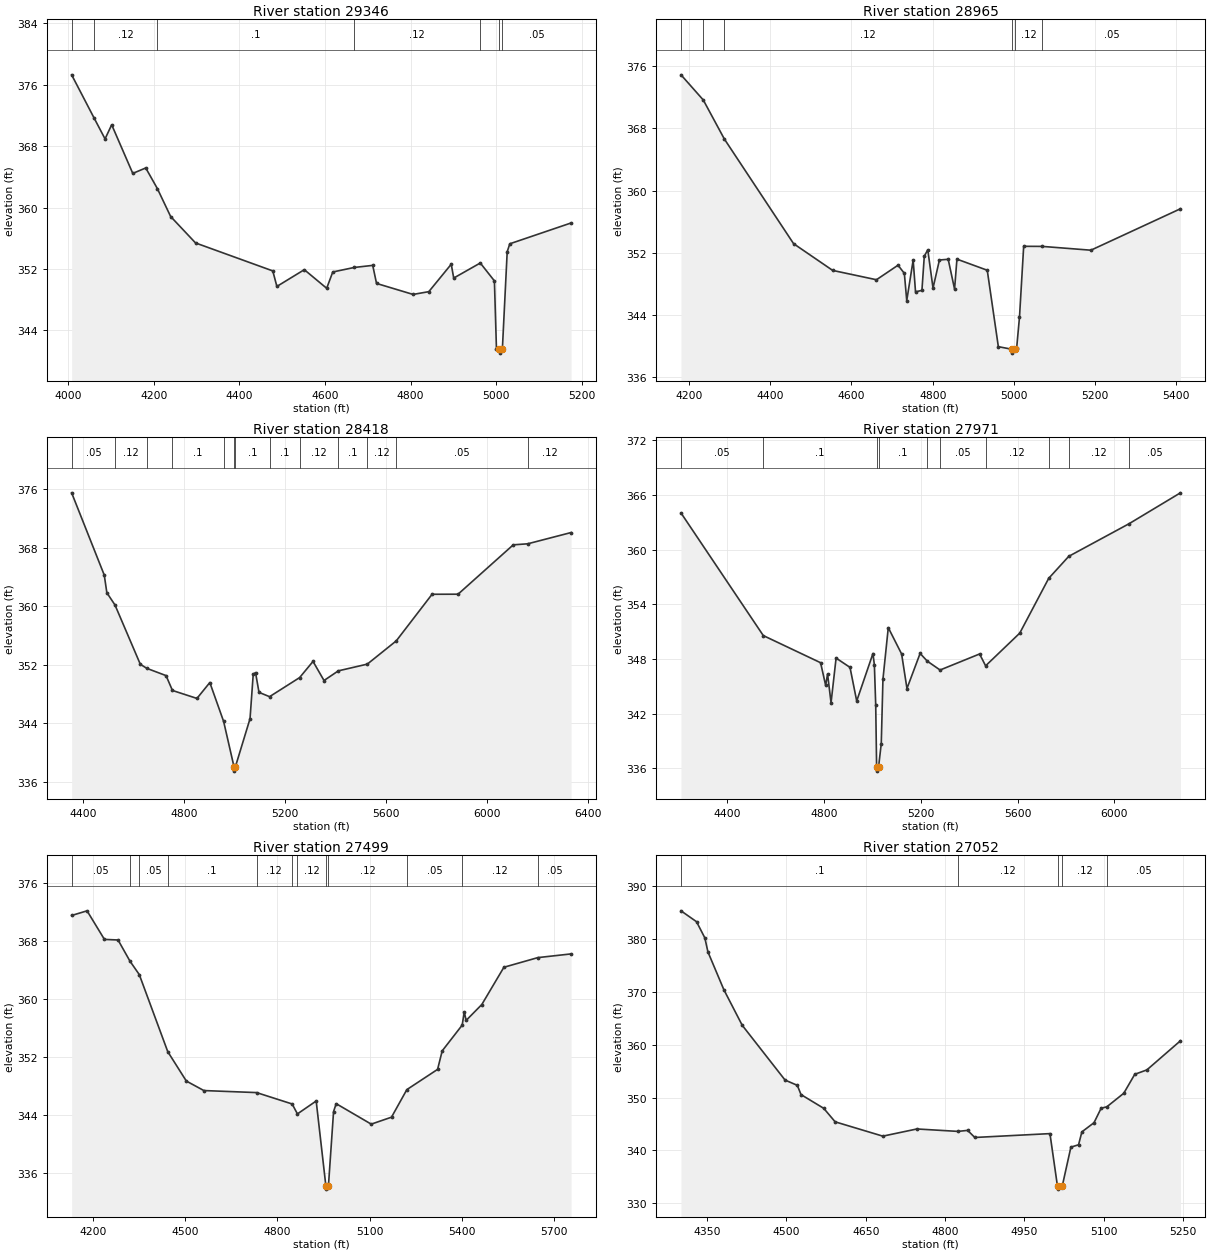
Type RM Length L Ch R = 1,29346,381,381,381
BEGIN DESCRIPTION:
Lynn Creek 55.0
END DESCRIPTION:
XS GIS Cut Line= 3
      2725578.26      6791445.86      2724726.00      6791961.00
      2724586.07      6792060.06
#Sta/Elev= 30
  4007.9  377.27  4059.9  371.70  4086.0  368.93  4101.5  370.77  4150.8  364.44
  4181.1  365.15  4208.3  362.46  4239.3  358.83  4297.5  355.39  4478.0  351.75
  4487.6  349.73  4551.7  351.91  4604.0  349.49  4618.2  351.61  4668.5  352.20
  4711.6  352.47  4720.5  350.12  4805.9  348.69  4842.7  349.05  4895.1  352.62
  4900.9  350.82  4963.0  352.78  4996.0  350.45  5000.8  341.59  5007.6  341.55
  5008.7  341.05  5014.6  341.55  5025.9  354.25  5032.0  355.28  5175.2  357.99
#Mann=7,-1,0
  4007.9     0.1       0  4059.9    0.12       0  4208.3     0.1       0
  4668.5    0.12       0  4963.0    0.05       0  5007.6    0.05       0
  5014.6    0.05       0
Bank Sta=5007.6,5014.6
Exp/Cntr=0.3,0.1

Type RM Length L Ch R = 1,28965,547,547,547
BEGIN DESCRIPTION:
Lynn Creek 54.0
END DESCRIPTION:
XS GIS Cut Line= 3
      2725402.66      6791218.33      2724692.24      6791627.65
      2724587.66      6792024.29
#Sta/Elev= 30
  4180.1  374.88  4235.0  371.64  4286.8  366.63  4457.4  353.16  4553.7  349.72
  4661.5  348.52  4714.6  350.39  4730.2  349.34  4736.1  345.84  4751.9  351.05
  4757.7  346.97  4773.5  347.15  4779.3  351.55  4787.9  352.37  4800.8  347.45
  4816.6  351.06  4838.2  351.15  4853.9  347.31  4859.7  351.17  4934.4  349.74
  4961.7  339.91  4994.8  339.58  4995.9  339.08  5001.8  339.58  5006.8  339.74
  5013.8  343.72  5024.1  352.82  5069.8  352.81  5189.6  352.32  5410.2  357.65
#Mann=6,-1,0
  4180.1    0.12       0  4235.0    0.05       0  4286.8    0.12       0
  4994.8    0.07       0  5001.8    0.12       0  5069.8    0.05       0
Bank Sta=4994.8,5001.8
Exp/Cntr=0.3,0.1

Type RM Length L Ch R = 1,28418,447,447,447
BEGIN DESCRIPTION:
Lynn Creek 53.0
END DESCRIPTION:
XS GIS Cut Line= 3
      2725352.73      6791087.29      2724726.00      6791211.00
      2723555.91      6791861.13
#Sta/Elev= 30
  4355.3  375.49  4484.5  364.24  4494.7  361.83  4527.0  360.15  4627.2  352.05
  4653.1  351.49  4729.1  350.50  4754.4  348.47  4851.4  347.38  4902.4  349.55
  4957.1  344.23  4998.8  337.94  4999.6  337.44  5002.8  337.94  5061.6  344.61
  5074.2  350.67  5083.4  350.91  5097.1  348.21  5138.9  347.62  5258.0  350.23
  5311.0  352.44  5354.5  349.83  5411.2  351.15  5525.9  352.07  5640.6  355.25
  5782.3  361.62  5885.2  361.63  6103.8  368.38  6160.9  368.52  6332.7  370.06
#Mann=13,-1,0
  4355.3    0.05       0  4527.0    0.12       0  4653.1    0.05       0
  4754.4     0.1       0  4957.1    0.12       0  4998.8    0.07       0
  5002.8     0.1       0  5138.9     0.1       0  5258.0    0.12       0
  5411.2     0.1       0  5525.9    0.12       0  5640.6    0.05       0
  6160.9    0.12       0
Bank Sta=4998.8,5002.8
Exp/Cntr=0.3,0.1

Type RM Length L Ch R = 1,27971,472,472,472
BEGIN DESCRIPTION:
Lynn Creek 52.0
END DESCRIPTION:
XS GIS Cut Line= 3
      2725240.62      6790364.34      2724626.00      6790861.00
      2723470.71      6791395.84
#Sta/Elev= 30
  4209.8  364.02  4549.8  350.56  4786.5  347.58  4807.4  345.09  4815.3  346.34
  4829.7  343.19  4850.5  348.09  4908.0  347.07  4935.7  343.38  5002.8  348.59
  5008.7  347.34  5014.2  342.95  5017.9  336.18  5019.2  335.68  5026.2  336.18
  5037.1  338.69  5044.1  345.77  5066.1  351.43  5121.2  348.54  5143.3  344.75
  5197.6  348.60  5227.4  347.75  5280.1  346.78  5443.3  348.54  5468.2  347.24
  5609.3  350.83  5728.8  356.84  5811.8  359.26  6060.3  362.83  6273.1  366.23
#Mann=10,-1,0
  4209.8    0.05       0  4549.8     0.1       0  5017.9    0.07       0
  5026.2     0.1       0  5227.4    0.12       0  5280.1    0.05       0
  5468.2    0.12       0  5728.8    0.05       0  5811.8    0.12       0
  6060.3    0.05       0
Bank Sta=5017.9,5026.2
Exp/Cntr=0.3,0.1

Type RM Length L Ch R = 1,27499,447,447,447
BEGIN DESCRIPTION:
Lynn Creek 51.0
END DESCRIPTION:
XS GIS Cut Line= 3
      2725041.28      6790056.56      2724326.00      6790561.00
      2723702.00      6790979.67
#Sta/Elev= 30
  4129.6  371.57  4179.8  372.21  4236.4  368.27  4280.8  368.19  4319.6  365.27
  4349.9  363.42  4442.7  352.79  4503.2  348.74  4560.3  347.43  4732.0  347.15
  4847.8  345.58  4865.0  344.21  4926.1  345.99  4957.5  334.34  4958.8  333.84
  4966.1  334.34  4982.7  344.54  4991.3  345.62  5105.4  342.80  5171.4  343.76
  5221.4  347.56  5321.5  350.35  5336.5  352.90  5401.6  356.45  5408.5  358.26
  5414.5  357.10  5465.5  359.29  5537.5  364.43  5648.1  365.76  5756.3  366.27
#Mann=12,-1,0
  4129.6    0.05       0  4319.6    0.12       0  4349.9    0.05       0
  4442.7     0.1       0  4732.0    0.12       0  4847.8     0.1       0
  4865.0    0.12       0  4957.5    0.07       0  4966.1    0.12       0
  5221.4    0.05       0  5401.6    0.12       0  5648.1    0.05       0
Bank Sta=4957.5,4966.1
Exp/Cntr=0.3,0.1

Type RM Length L Ch R = 1,27052,423,423,423
BEGIN DESCRIPTION:
Lynn Creek 50.0
END DESCRIPTION:
XS GIS Cut Line= 3
      2724376.01      6789660.98      2724026.00      6790261.00
      2723826.04      6790410.97
#Sta/Elev= 30
  4300.7  385.31  4330.1  383.25  4345.8  380.19  4351.6  377.55  4381.8  370.38
  4416.5  363.66  4497.5  353.30  4520.7  352.30  4527.7  350.55  4570.7  347.95
  4592.2  345.40  4682.4  342.69  4746.9  344.05  4824.4  343.59  4842.8  343.78
  4856.4  342.44  4998.5  343.17  5012.8  333.17  5014.1  332.67  5021.6  333.17
  5038.1  340.61  5052.6  341.06  5058.9  343.50  5081.8  345.23  5095.3  347.97
  5106.1  348.24  5138.1  350.80  5158.9  354.39  5181.8  355.22  5245.3  360.73
#Mann=5,-1,0
  4300.7     0.1       0  4824.4    0.12       0  5012.8    0.07       0
  5021.6    0.12       0  5106.1    0.05       0
Bank Sta=5012.8,5021.6
Exp/Cntr=0.3,0.1

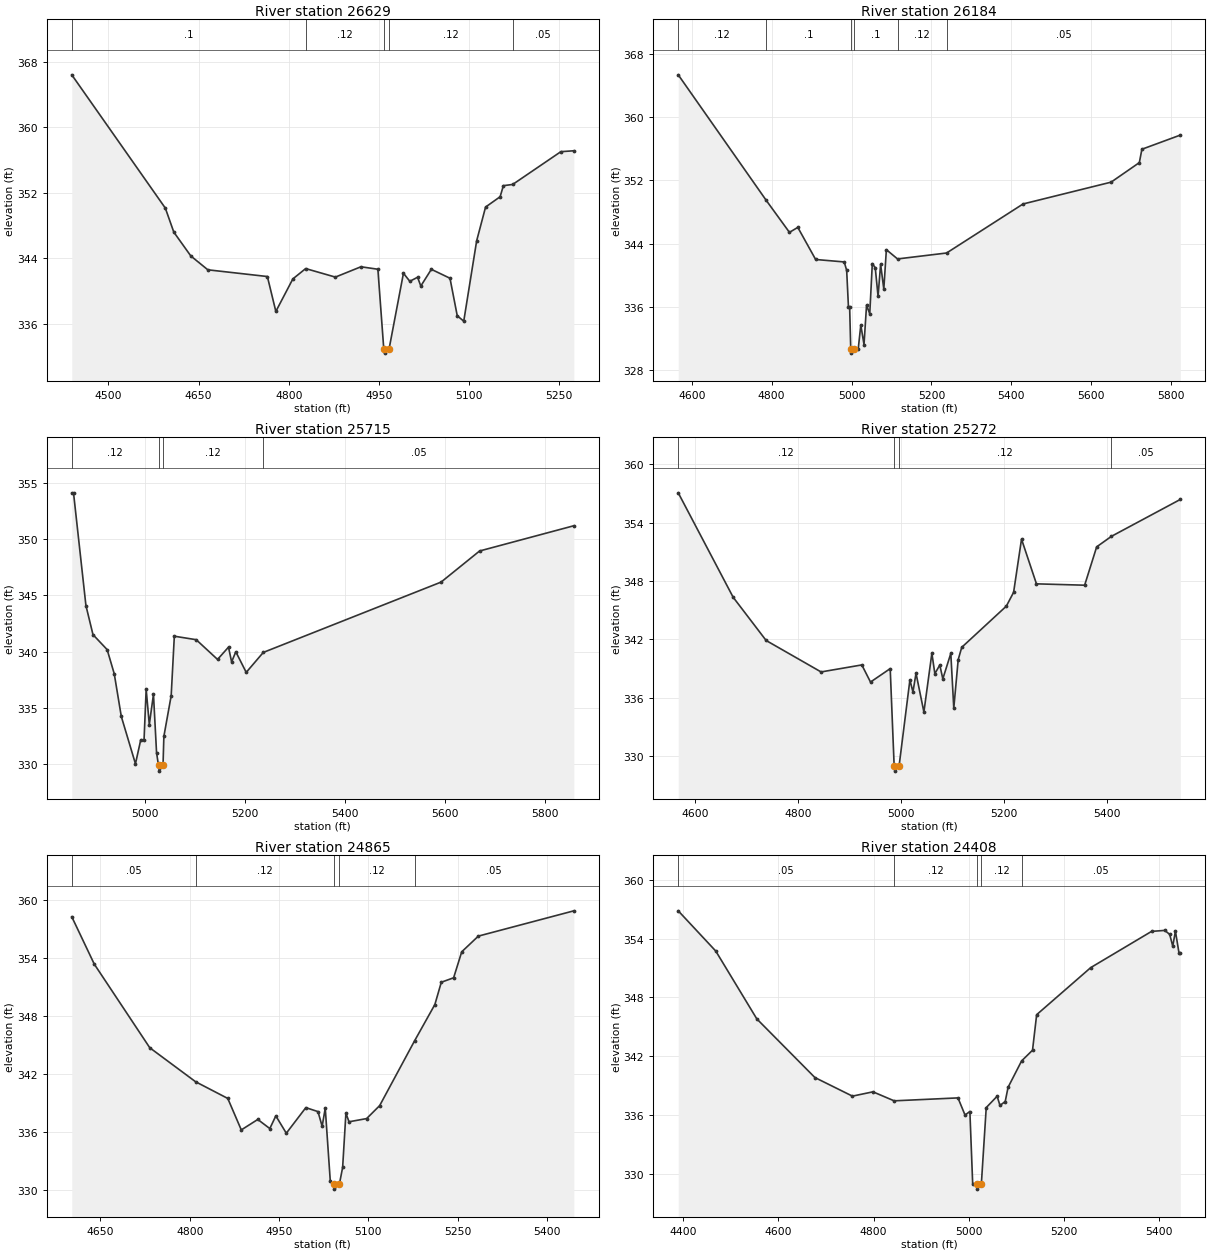
Type RM Length L Ch R = 1,26629,445,445,445
BEGIN DESCRIPTION:
Lynn Creek 49.0
END DESCRIPTION:
XS GIS Cut Line= 3
      2724176.01      6789610.99      2723776.00      6790011.00
      2723675.99      6790261.04
#Sta/Elev= 30
  4439.1  366.40  4594.7  350.13  4608.8  347.20  4637.1  344.29  4665.4  342.60
  4764.4  341.78  4778.5  337.52  4806.8  341.49  4828.1  342.75  4877.5  341.71
  4920.0  342.97  4948.2  342.67  4958.0  332.93  4959.2  332.43  4966.8  332.93
  4990.7  342.18  5001.3  341.20  5014.2  341.69  5019.6  340.62  5037.1  342.66
  5068.1  341.57  5080.2  336.99  5091.0  336.33  5112.5  346.15  5127.3  350.26
  5151.5  351.52  5156.9  352.87  5172.4  353.02  5252.5  357.02  5274.1  357.13
#Mann=5,-1,0
  4439.1     0.1       0  4828.1    0.12       0  4958.0    0.07       0
  4966.8    0.12       0  5172.4    0.05       0
Bank Sta=4958,4966.8
Exp/Cntr=0.3,0.1

Type RM Length L Ch R = 1,26184,469,469,469
BEGIN DESCRIPTION:
Lynn Creek 48.0
END DESCRIPTION:
XS GIS Cut Line= 3
      2724129.19      6789417.09      2723776.00      6789661.00
      2723256.63      6790305.95
#Sta/Elev= 30
  4566.0  365.33  4786.3  349.46  4844.5  345.41  4865.4  346.04  4910.1  341.98
  4981.7  341.67  4987.8  340.60  4992.2  336.03  4995.2  336.03  4998.0  330.64
  4999.2  330.14  5006.9  330.64  5016.8  330.70  5023.2  333.69  5031.2  331.23
  5037.6  336.21  5045.6  335.11  5052.0  341.46  5059.4  340.93  5066.4  337.32
  5072.8  341.37  5080.8  338.24  5087.2  343.22  5115.2  342.05  5238.0  342.80
  5429.5  349.00  5650.0  351.76  5720.7  354.23  5727.1  355.92  5823.3  357.71
#Mann=6,-1,0
  4566.0    0.12       0  4786.3     0.1       0  4998.0    0.07       0
  5006.9     0.1       0  5115.2    0.12       0  5238.0    0.05       0
Bank Sta=4998,5006.9
Exp/Cntr=0.3,0.1

Type RM Length L Ch R = 1,25715,443,443,443
BEGIN DESCRIPTION:
Lynn Creek 47.0
END DESCRIPTION:
XS GIS Cut Line= 4
      2723626.00      6789211.00      2723526.00      6789311.00
      2723335.28      6789565.29      2723252.51      6790103.28
#Sta/Elev= 30
  4854.0  354.09  4857.5  354.09  4882.3  344.09  4896.4  341.51  4924.7  340.18
  4938.9  338.04  4953.0  334.25  4981.3  330.05  4991.9  332.18  4998.5  332.18
  5002.7  336.66  5009.0  333.53  5017.3  336.21  5023.5  331.03  5027.4  329.90
  5028.7  329.40  5036.4  329.90  5038.1  332.48  5052.7  336.09  5059.0  341.37
  5102.7  341.06  5145.4  339.31  5167.3  340.40  5173.5  339.09  5181.9  339.99
  5202.7  338.16  5236.8  339.93  5592.2  346.17  5669.2  348.93  5857.6  351.17
#Mann=4,-1,0
  4854.0    0.12       0  5027.4    0.07       0  5036.4    0.12       0
  5236.8    0.05       0
Bank Sta=5027.4,5036.4
Exp/Cntr=0.3,0.1

Type RM Length L Ch R = 1,25272,407,407,407
BEGIN DESCRIPTION:
Lynn Creek 46.0
END DESCRIPTION:
XS GIS Cut Line= 3
      2723576.02      6789010.99      2723176.00      6789161.00
      2722707.08      6789446.29
#Sta/Elev= 30
  4567.1  357.05  4673.9  346.32  4738.0  341.88  4844.8  338.65  4924.0  339.37
  4940.9  337.61  4979.2  338.99  4986.9  328.96  4988.2  328.46  4996.4  328.96
  5017.5  337.83  5023.4  336.59  5029.4  338.51  5044.7  334.53  5060.2  340.57
  5066.0  338.47  5075.6  339.36  5081.5  337.94  5097.0  340.55  5102.8  334.93
  5111.4  339.92  5118.3  341.18  5205.0  345.41  5219.1  346.83  5234.5  352.29
  5263.5  347.70  5357.2  347.56  5380.6  351.50  5409.3  352.58  5543.2  356.37
#Mann=4,-1,0
  4567.1    0.12       0  4986.9    0.07       0  4996.4    0.12       0
  5409.3    0.05       0
Bank Sta=4986.9,4996.4
Exp/Cntr=0.3,0.1

Type RM Length L Ch R = 1,24865,457,457,457
BEGIN DESCRIPTION:
Lynn Creek 45.0
END DESCRIPTION:
XS GIS Cut Line= 3
      2723576.02      6788961.00      2723176.00      6788911.00
      2722751.11      6788796.46
#Sta/Elev= 30
  4601.9  358.24  4639.7  353.35  4732.9  344.72  4809.9  341.21  4863.9  339.49
  4886.6  336.24  4914.3  337.32  4934.5  336.38  4944.6  337.69  4962.2  335.90
  4995.0  338.54  5015.4  338.13  5022.4  336.61  5027.6  338.49  5036.1  330.92
  5041.7  330.63  5043.1  330.13  5051.3  330.63  5056.8  332.37  5062.3  337.97
  5067.5  337.08  5097.1  337.41  5119.0  338.75  5177.5  345.42  5211.7  349.18
  5222.5  351.48  5243.2  351.94  5256.8  354.62  5284.7  356.24  5445.1  358.85
#Mann=5,-1,0
  4601.9    0.05       0  4809.9    0.12       0  5041.7    0.07       0
  5051.3    0.12       0  5177.5    0.05       0
Bank Sta=5041.7,5051.3
Exp/Cntr=0.3,0.1

Type RM Length L Ch R = 1,24408,426,426,426
BEGIN DESCRIPTION:
Lynn Creek 44.0
END DESCRIPTION:
XS GIS Cut Line= 4
      2723626.00      6788861.00      2723126.00      6788511.00
      2722959.67      6788434.17      2722726.15      6788552.87
#Sta/Elev= 30
  4389.3  356.84  4468.2  352.73  4554.5  345.80  4676.6  339.81  4755.5  337.91
  4798.7  338.35  4843.2  337.43  4977.4  337.73  4992.2  335.98  5002.4  336.34
  5008.3  328.97  5016.9  328.91  5018.2  328.41  5026.5  328.91  5036.8  336.74
  5059.7  337.90  5065.7  336.96  5076.7  337.36  5082.7  338.81  5111.2  341.51
  5134.1  342.60  5142.8  346.23  5256.5  351.04  5384.4  354.74  5412.2  354.84
  5422.5  354.43  5428.9  353.23  5434.5  354.76  5442.1  352.52  5444.8  352.52
#Mann=5,-1,0
  4389.3    0.05       0  4843.2    0.12       0  5016.9    0.07       0
  5026.5    0.12       0  5111.2    0.05       0
Bank Sta=5016.9,5026.5
Exp/Cntr=0.3,0.1

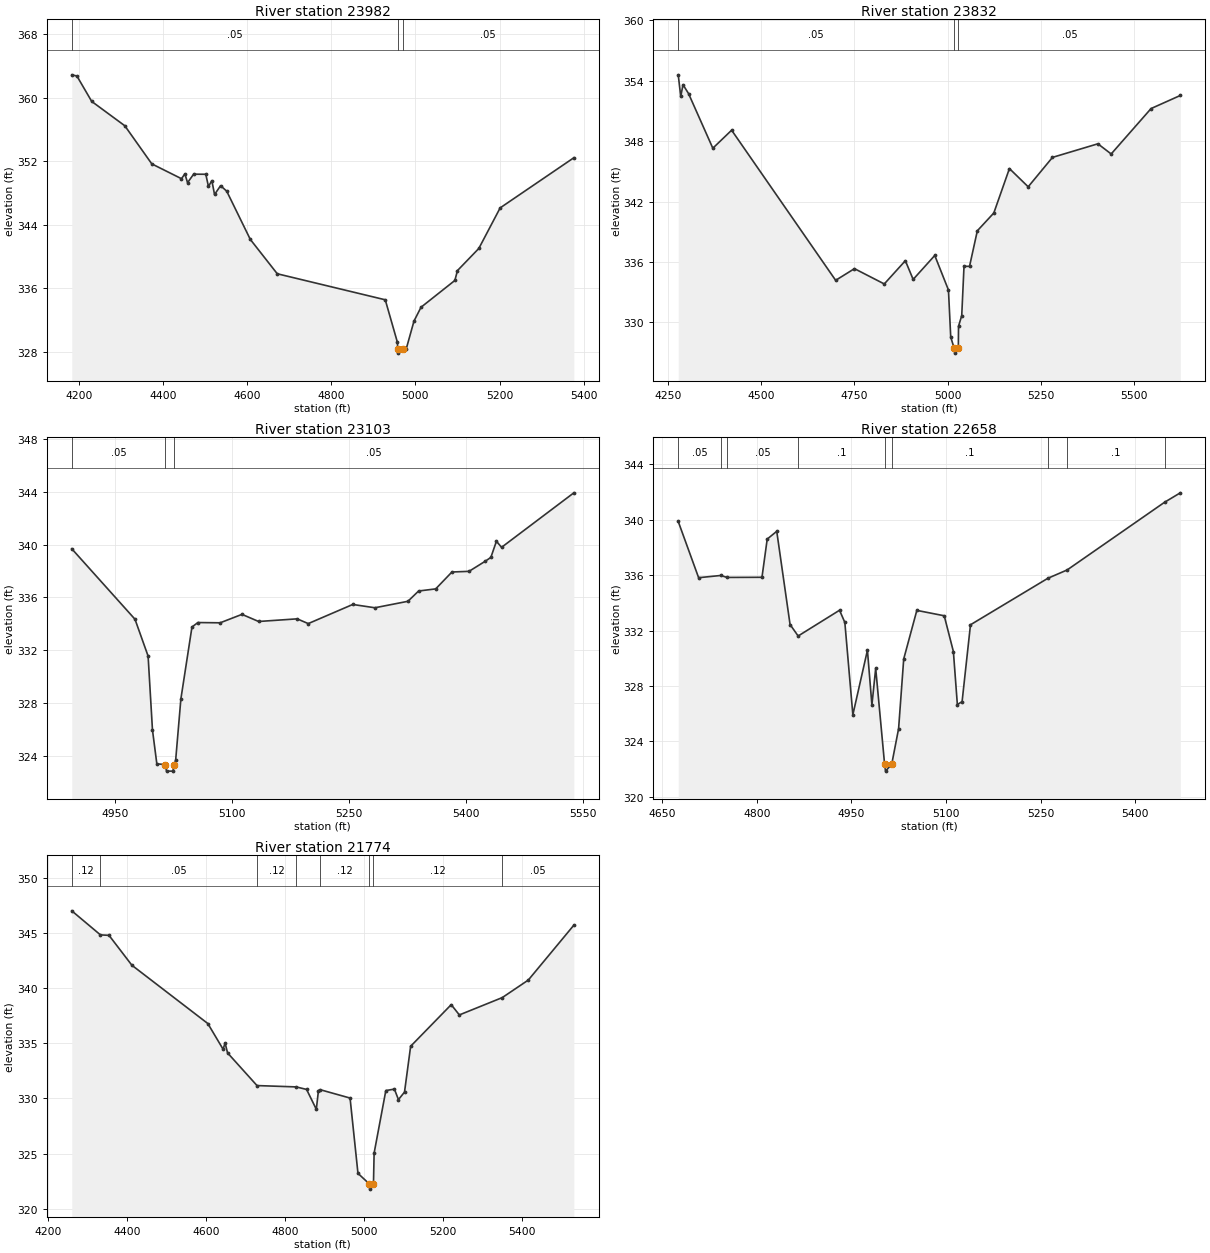
Type RM Length L Ch R = 1,23982,150,150,150
BEGIN DESCRIPTION:
Lynn Creek 43.0
END DESCRIPTION:
XS GIS Cut Line= 3
      2723530.22      6787518.62      2723026.00      6788161.00
      2722812.80      6788471.76
#Sta/Elev= 30
  4183.1  362.90  4195.3  362.75  4230.5  359.55  4309.2  356.48  4373.3  351.68
  4443.9  349.81  4452.0  350.42  4458.3  349.31  4472.8  350.38  4501.7  350.37
  4508.0  348.83  4516.1  349.56  4522.5  347.82  4536.9  348.93  4551.4  348.24
  4607.5  342.16  4671.6  337.83  4928.3  334.55  4957.2  329.19  4958.0  328.33
  4959.5  327.83  4969.3  328.33  4978.1  328.35  4996.6  331.87  5013.3  333.61
  5093.8  336.99  5099.9  338.23  5150.7  341.02  5201.4  346.13  5376.6  352.45
#Mann=3,-1,0
  4183.1    0.05       0  4958.0    0.05       0  4969.3    0.05       0
Bank Sta=4958,4969.3
Exp/Cntr=0.3,0.1

Type RM Length L Ch R = 1,23832,729,729,729
BEGIN DESCRIPTION:
Mapping XS 92a7de28
END DESCRIPTION:
XS GIS Cut Line= 2
      2723395.87      6787441.92      2722612.79      6788536.19
#Sta/Elev= 30
  4278.0  354.59  4284.7  352.44  4290.8  353.61  4305.6  352.73  4370.7  347.30
  4421.1  349.09  4699.9  334.18  4750.3  335.34  4830.2  333.82  4886.7  336.13
  4907.6  334.27  4965.5  336.65  5002.2  333.22  5008.3  328.54  5017.4  327.45
  5018.9  326.95  5028.7  327.45  5029.2  329.62  5037.8  330.68  5043.9  335.57
  5058.7  335.57  5079.6  339.10  5123.8  340.87  5165.6  345.28  5215.9  343.47
  5281.0  346.39  5402.7  347.74  5438.3  346.73  5545.2  351.24  5623.6  352.54
#Mann=3,-1,0
  4278.0    0.05       0  5017.4    0.03       0  5028.7    0.05       0
Bank Sta=5017.4,5028.7
Exp/Cntr=0.3,0.1

Type RM Length L Ch R = 1,23103,445,445,445
BEGIN DESCRIPTION:
Lynn Creek 42.0
END DESCRIPTION:
XS GIS Cut Line= 3
      2723075.97      6787461.02      2722976.00      6787511.00
      2722575.98      6787861.02
#Sta/Elev= 30
  4894.8  339.69  4975.8  334.35  4992.6  331.56  4998.2  325.96  5003.8  323.39
  5014.7  323.34  5016.2  322.84  5024.4  322.84  5026.0  323.34  5027.9  323.66
  5034.6  328.31  5048.8  333.76  5056.4  334.10  5084.9  334.08  5112.9  334.72
  5134.2  334.18  5183.6  334.38  5197.8  334.02  5254.8  335.47  5283.2  335.22
  5325.5  335.71  5339.2  336.49  5361.1  336.65  5381.9  337.93  5403.8  337.98
  5424.7  338.75  5431.8  339.04  5438.9  340.26  5445.5  339.80  5538.1  343.93
#Mann=3,-1,0
  4894.8    0.05       0  5014.7    0.04       0  5026.0    0.05       0
Bank Sta=5014.7,5026
Exp/Cntr=0.3,0.1

Type RM Length L Ch R = 1,22658,884,884,884
BEGIN DESCRIPTION:
Lynn Creek 41.0
END DESCRIPTION:
XS GIS Cut Line= 3
      2722957.12      6787027.72      2722676.00      6787211.00
      2722313.52      6787494.23
#Sta/Elev= 30
  4675.6  339.88  4707.9  335.82  4742.8  335.98  4753.1  335.84  4808.3  335.85
  4816.6  338.61  4831.7  339.17  4852.8  332.44  4865.6  331.61  4931.2  333.47
  4939.6  332.59  4952.3  325.92  4975.4  330.58  4982.5  326.63  4988.5  329.27
  5002.6  322.35  5004.1  321.85  5013.9  322.35  5024.8  324.92  5032.9  329.95
  5053.7  333.46  5097.1  333.07  5111.6  330.49  5117.9  326.66  5125.4  326.87
  5138.7  332.42  5261.4  335.78  5291.9  336.38  5446.3  341.27  5471.2  341.95
#Mann=9,-1,0
  4675.6    0.05       0  4742.8     0.1       0  4753.1    0.05       0
  4865.6     0.1       0  5002.6    0.07       0  5013.9     0.1       0
  5261.4    0.05       0  5291.9     0.1       0  5446.3    0.05       0
Bank Sta=5002.6,5013.9
Exp/Cntr=0.3,0.1

Type RM Length L Ch R = 1,21774,288,288,288
BEGIN DESCRIPTION:
Lynn Creek 40.0
END DESCRIPTION:
XS GIS Cut Line= 3
      2723160.24      6786729.31      2722426.00      6786761.00
      2721903.86      6786885.52
#Sta/Elev= 30
  4259.8  346.99  4332.4  344.81  4354.1  344.77  4412.1  342.06  4604.4  336.78
  4643.1  334.45  4648.1  335.02  4654.4  334.12  4729.0  331.16  4828.2  331.04
  4854.6  330.81  4879.2  329.01  4884.6  330.70  4888.7  330.79  4964.7  330.03
  4984.7  323.21  5012.6  322.28  5014.2  321.78  5024.0  322.28  5025.6  325.04
  5055.3  330.71  5077.0  330.84  5087.2  329.89  5102.6  330.57  5118.1  334.72
  5220.9  338.49  5241.5  337.56  5350.2  339.13  5416.2  340.72  5531.5  345.69
#Mann=8,-1,0
  4259.8    0.12       0  4332.4    0.05       0  4729.0    0.12       0
  4828.2     0.1       0  4888.7    0.12       0  5012.6    0.07       0
  5024.0    0.12       0  5350.2    0.05       0
Bank Sta=5012.6,5024
Exp/Cntr=0.3,0.1