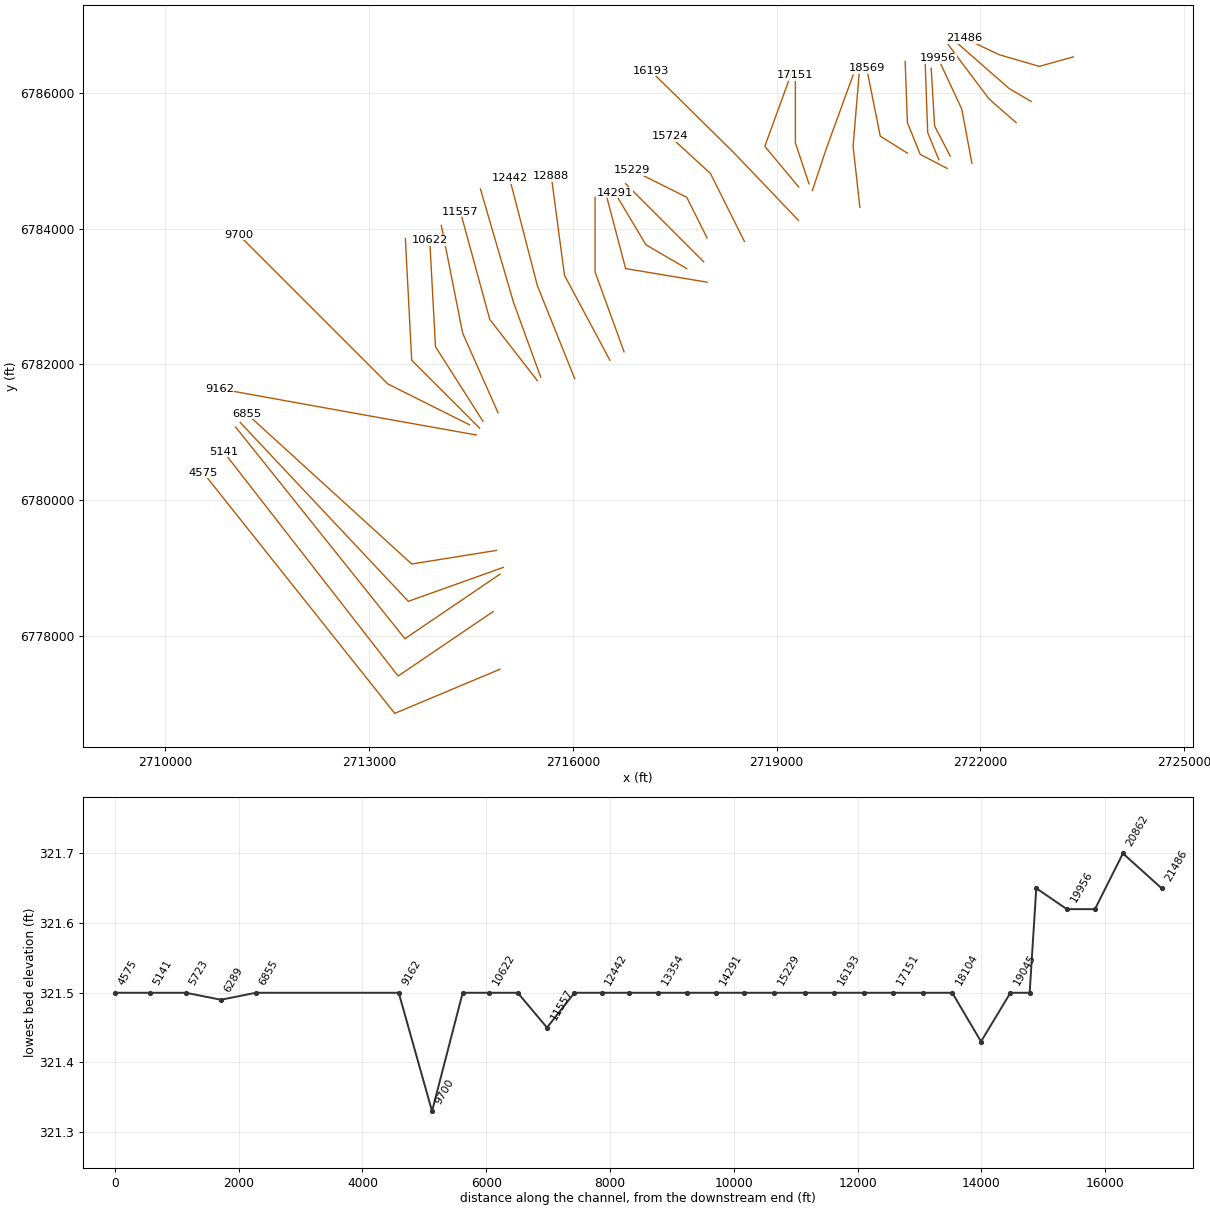
HEC-RAS study Lynn Creek.prj: Lynn Creek Base Level Engineering

--- Lynn Creek.g01 (geometry) --- (continued)

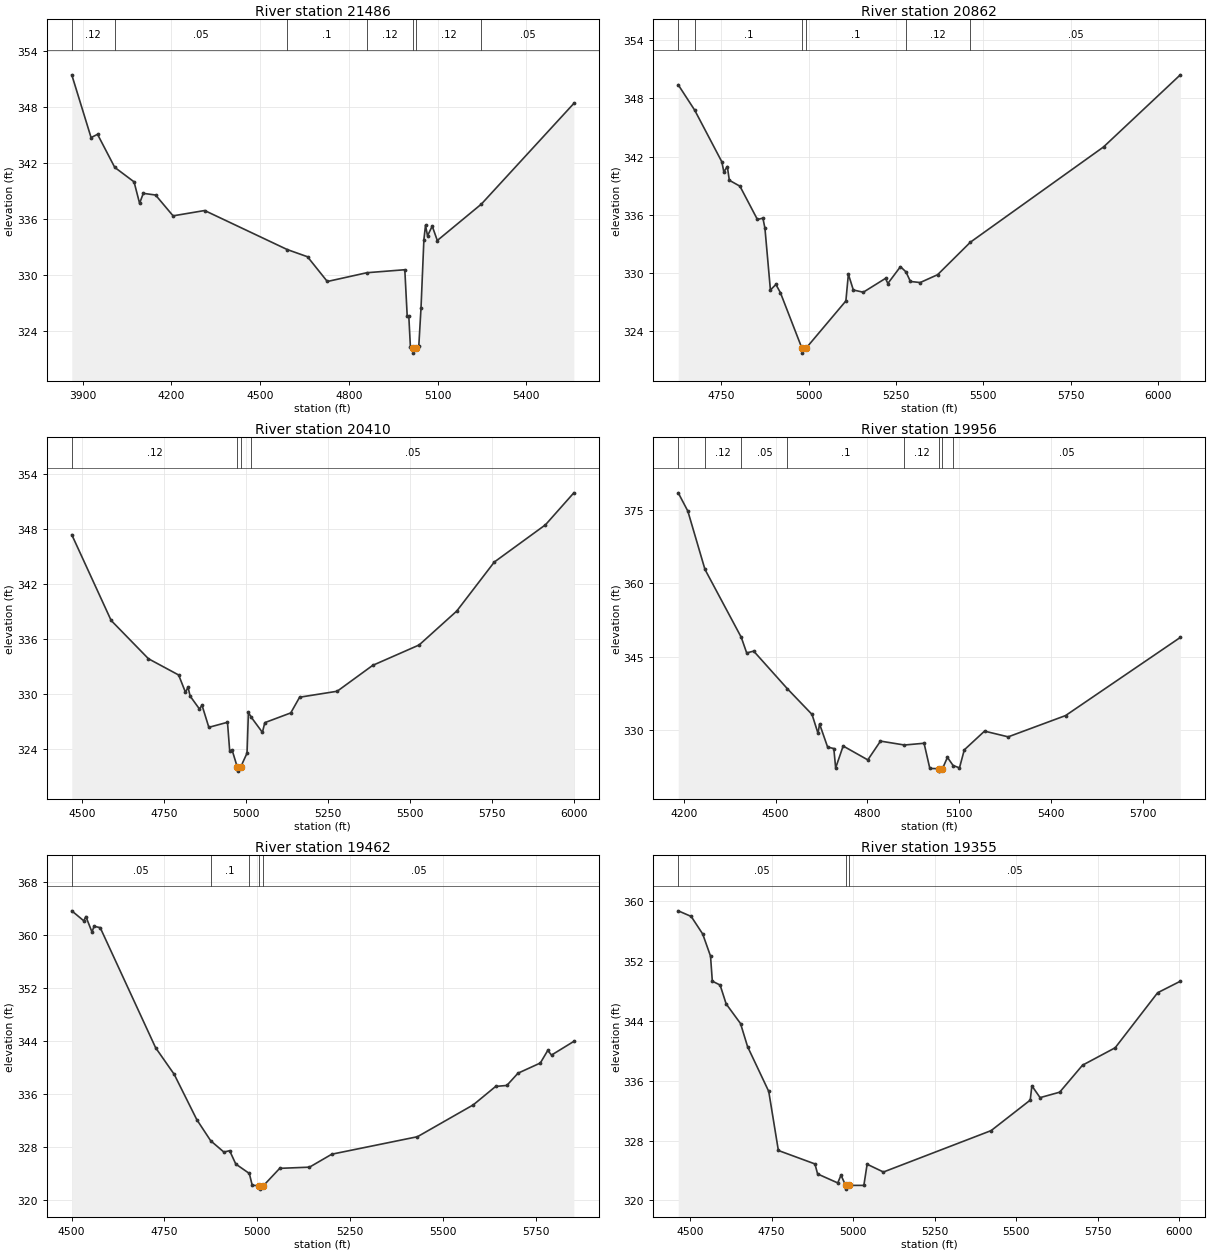
Type RM Length L Ch R = 1,21486,624,624,624
BEGIN DESCRIPTION:
Lynn Creek 39.0
END DESCRIPTION:
XS GIS Cut Line= 4
      2723368.95      6786528.16      2722867.52      6786389.02
      2722275.43      6786561.22      2721769.22      6786801.86
#Sta/Elev= 30
  3863.0  351.45  3928.3  344.73  3950.1  345.08  4008.3  341.54  4073.6  339.99
  4092.3  337.69  4104.8  338.76  4146.3  338.58  4205.5  336.35  4312.3  336.92
  4591.5  332.74  4660.0  331.97  4727.0  329.32  4860.8  330.26  4989.0  330.58
  4997.1  325.61  5002.5  325.61  5008.0  322.28  5015.8  322.15  5017.4  321.65
  5027.2  322.15  5036.3  322.42  5043.7  326.43  5053.5  333.79  5059.0  335.34
  5065.8  334.21  5081.7  335.25  5098.9  333.71  5247.9  337.61  5560.5  348.39
#Mann=7,-1,0
  3863.0    0.12       0  4008.3    0.05       0  4591.5     0.1       0
  4860.8    0.12       0  5015.8    0.07       0  5027.2    0.12       0
  5247.9    0.05       0
Bank Sta=5015.8,5027.2
Exp/Cntr=0.3,0.1

Type RM Length L Ch R = 1,20862,452,452,452
BEGIN DESCRIPTION:
Lynn Creek 38.0
END DESCRIPTION:
XS GIS Cut Line= 3
      2722748.46      6785873.01      2722426.00      6786061.00
      2721625.98      6786761.02
#Sta/Elev= 30
  4627.1  349.41  4674.2  346.79  4751.8  341.46  4757.6  340.41  4767.5  340.97
  4773.3  339.55  4803.6  338.94  4853.6  335.50  4869.3  335.64  4875.1  334.61
  4890.8  328.22  4906.5  328.79  4919.3  327.95  4981.0  322.20  4982.5  321.70
  4992.5  322.20  5106.7  327.09  5113.8  329.85  5128.0  328.22  5156.5  327.99
  5220.1  329.42  5226.7  328.89  5262.8  330.63  5278.6  330.09  5291.3  329.10
  5319.3  328.99  5369.1  329.80  5463.0  333.16  5843.7  342.99  6063.4  350.44
#Mann=6,-1,0
  4627.1    0.12       0  4674.2     0.1       0  4981.0    0.07       0
  4992.5     0.1       0  5278.6    0.12       0  5463.0    0.05       0
Bank Sta=4981,4992.5
Exp/Cntr=0.3,0.1

Type RM Length L Ch R = 1,20410,454,454,454
BEGIN DESCRIPTION:
Lynn Creek 37.0
END DESCRIPTION:
XS GIS Cut Line= 3
      2722525.99      6785561.01      2722126.00      6785911.00
      2721526.00      6786711.00
#Sta/Elev= 30
  4468.5  347.37  4588.6  338.03  4702.4  333.86  4794.5  332.09  4815.4  330.20
  4823.0  330.77  4829.6  329.79  4858.1  328.38  4865.7  328.81  4886.6  326.39
  4943.5  326.94  4950.2  323.83  4957.8  323.89  4972.9  322.12  4974.4  321.62
  4984.4  322.12  5003.1  323.58  5007.3  328.01  5016.2  327.48  5050.0  325.84
  5057.3  326.90  5136.5  327.96  5163.5  329.67  5278.1  330.32  5386.5  333.14
  5528.1  335.36  5642.7  339.05  5757.3  344.39  5913.5  348.45  6000.0  351.93
#Mann=4,-1,0
  4468.5    0.12       0  4972.9    0.07       0  4984.4    0.12       0
  5016.2    0.05       0
Bank Sta=4972.9,4984.4
Exp/Cntr=0.3,0.1

Type RM Length L Ch R = 1,19956,494,494,494
BEGIN DESCRIPTION:
Lynn Creek 36.0
END DESCRIPTION:
XS GIS Cut Line= 3
      2721876.00      6784961.00      2721726.00      6785761.00
      2721376.00      6786511.01
#Sta/Elev= 30
  4181.9  378.53  4213.3  374.79  4269.3  362.87  4388.0  348.98  4405.7  345.79
  4428.6  346.16  4538.8  338.46  4619.4  333.21  4638.9  329.35  4644.0  331.27
  4670.3  326.54  4690.6  326.24  4696.6  322.27  4721.1  326.76  4801.7  323.92
  4843.2  327.76  4921.4  326.96  4985.7  327.32  5004.5  322.17  5034.2  322.12
  5035.8  321.62  5045.8  322.12  5062.1  324.43  5080.6  322.77  5101.5  322.29
  5117.2  325.97  5183.4  329.80  5260.7  328.63  5448.3  332.98  5823.5  348.96
#Mann=8,-1,0
  4181.9     0.1       0  4269.3    0.12       0  4388.0    0.05       0
  4538.8     0.1       0  4921.4    0.12       0  5034.2    0.07       0
  5045.8    0.12       0  5080.6    0.05       0
Bank Sta=5034.2,5045.8
Exp/Cntr=0.3,0.1

Type RM Length L Ch R = 1,19462,107,107,107
BEGIN DESCRIPTION:
Lynn Creek 35.0
END DESCRIPTION:
XS GIS Cut Line= 3
      2721556.09      6785067.76      2721326.00      6785511.00
      2721276.00      6786361.03
#Sta/Elev= 30
  4500.6  363.71  4532.9  362.20  4538.5  362.85  4555.0  360.51  4560.6  361.37
  4577.1  361.17  4726.3  343.01  4776.2  339.00  4836.9  332.16  4874.4  328.96
  4909.9  327.25  4925.4  327.46  4941.9  325.44  4978.3  324.02  4986.1  322.24
  5004.2  322.15  5005.8  321.65  5015.9  322.15  5060.1  324.79  5140.2  324.97
  5200.3  326.93  5430.7  329.57  5581.0  334.39  5641.1  337.17  5671.2  337.32
  5701.2  339.17  5761.3  340.71  5781.3  342.61  5791.4  341.91  5851.5  343.98
#Mann=5,-1,0
  4500.6    0.05       0  4874.4     0.1       0  4978.3    0.05       0
  5004.2    0.05       0  5015.9    0.05       0
Bank Sta=5004.2,5015.9
Exp/Cntr=0.3,0.1

Type RM Length L Ch R = 1,19355,310,310,310
BEGIN DESCRIPTION:
Mapping XS 03fe8f2d
END DESCRIPTION:
XS GIS Cut Line= 3
      2721388.56      6785014.32      2721224.79      6785413.16
      2721184.41      6786520.57
#Sta/Elev= 30
  4463.5  358.73  4503.2  357.98  4538.5  355.63  4562.5  352.67  4568.0  349.32
  4591.9  348.80  4610.4  346.28  4654.5  343.65  4676.1  340.56  4741.0  334.57
  4770.5  326.67  4882.6  324.87  4890.8  323.53  4952.5  322.33  4962.5  323.37
  4976.7  322.00  4978.3  321.50  4988.4  322.00  5032.6  322.00  5042.6  324.83
  5092.6  323.79  5422.8  329.33  5542.7  333.41  5547.7  335.32  5572.9  333.74
  5633.0  334.47  5703.0  338.08  5803.1  340.41  5933.2  347.77  6002.8  349.31
#Mann=3,-1,0
  4463.5    0.05       0  4976.7    0.05       0  4988.4    0.05       0
Bank Sta=4976.7,4988.4
Exp/Cntr=0.3,0.1

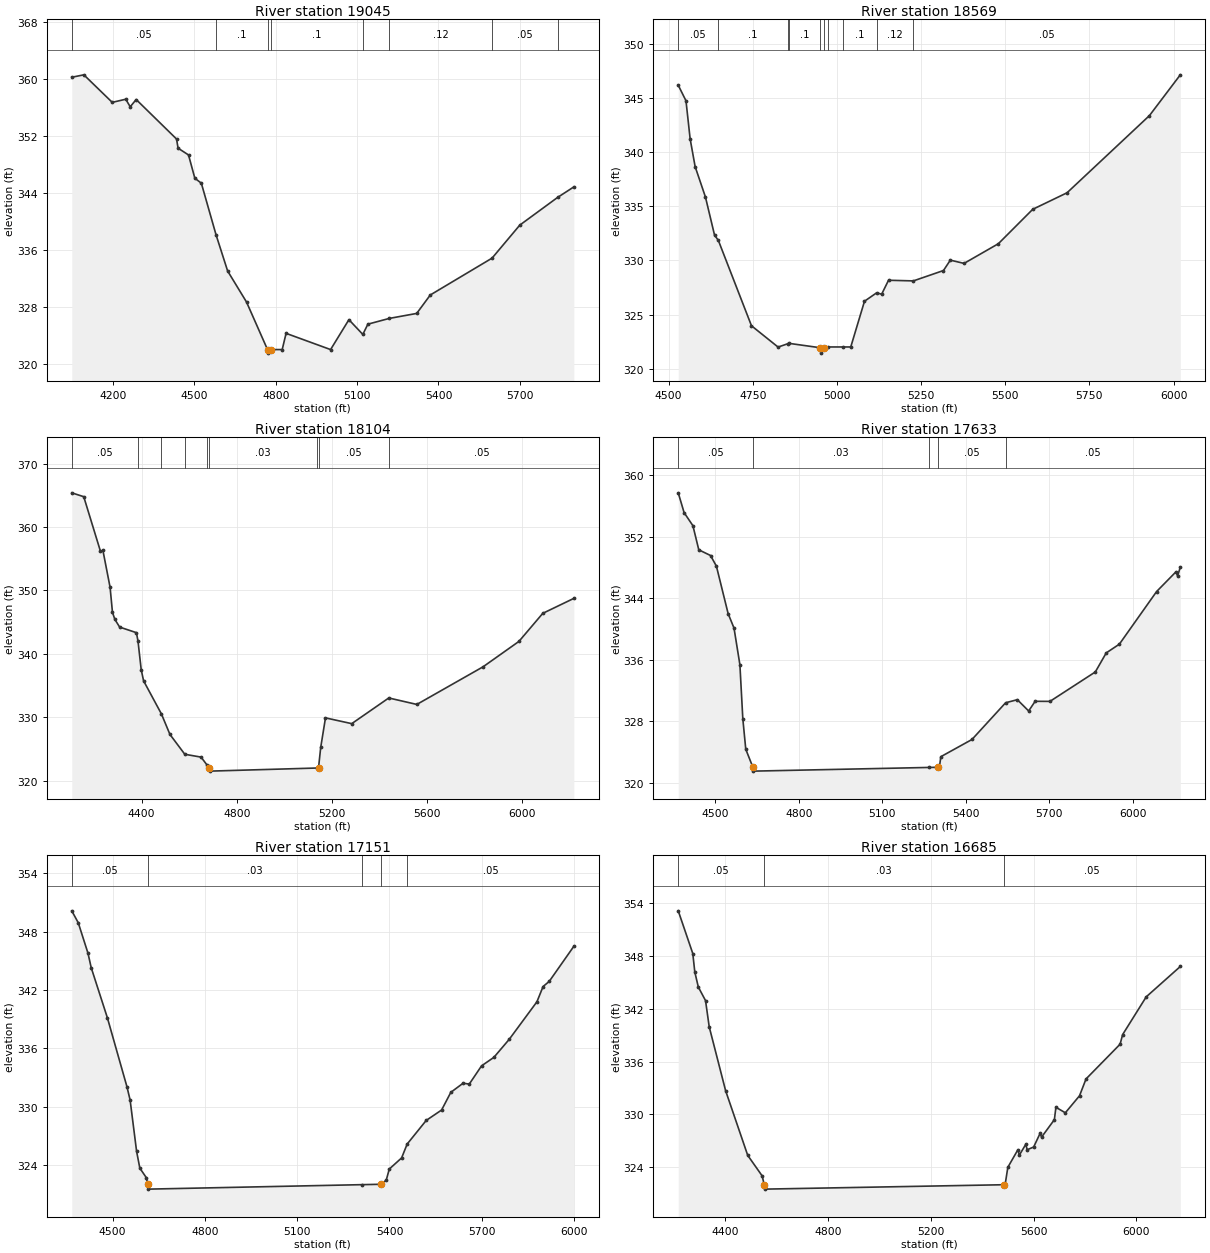
Type RM Length L Ch R = 1,19045,476,476,476
BEGIN DESCRIPTION:
Lynn Creek 34.0
END DESCRIPTION:
XS GIS Cut Line= 4
      2721511.73      6784885.99      2721114.03      6785093.85
      2720926.00      6785561.00      2720892.53      6786460.26
#Sta/Elev= 30
  4047.3  360.27  4091.9  360.61  4196.6  356.74  4246.4  357.18  4262.9  356.12
  4284.9  357.14  4433.8  351.59  4439.5  350.30  4478.0  349.35  4501.3  346.08
  4525.3  345.38  4579.6  338.12  4622.3  333.04  4692.0  328.68  4769.4  322.00
  4771.1  321.50  4781.2  322.00  4823.6  322.00  4837.9  324.28  5002.1  322.00
  5069.7  326.20  5121.0  324.13  5139.7  325.57  5218.9  326.38  5319.8  327.08
  5369.9  329.67  5597.8  334.85  5700.1  339.49  5839.5  343.38  5899.5  344.86
#Mann=8,-1,0
  4047.3    0.05       0  4579.6     0.1       0  4769.4    0.07       0
  4781.2     0.1       0  5121.0    0.05       0  5218.9    0.12       0
  5597.8    0.05       0  5839.5     0.1       0
Bank Sta=4769.4,4781.2
Exp/Cntr=0.3,0.1

Type RM Length L Ch R = 1,18569,465,465,465
BEGIN DESCRIPTION:
Lynn Creek 33.0
END DESCRIPTION:
XS GIS Cut Line= 3
      2720926.03      6785110.98      2720526.00      6785361.00
      2720326.01      6786360.96
#Sta/Elev= 30
  4528.5  346.21  4551.5  344.77  4563.9  341.24  4578.7  338.68  4609.3  335.87
  4636.4  332.34  4647.6  331.86  4746.1  323.96  4825.1  321.99  4855.0  322.31
  4856.1  322.34  4950.1  321.93  4951.8  321.43  4961.9  321.93  4974.6  322.00
  5018.6  322.00  5041.0  322.00  5081.8  326.23  5118.0  327.01  5132.8  326.88
  5153.2  328.17  5227.0  328.11  5316.4  329.07  5336.8  330.03  5377.6  329.73
  5479.5  331.55  5581.5  334.73  5683.5  336.26  5928.3  343.40  6020.0  347.17
#Mann=10,-1,0
  4528.5    0.05       0  4647.6     0.1       0  4855.0    0.12       0
  4856.1     0.1       0  4950.1    0.07       0  4961.9     0.1       0
  4974.6    0.12       0  5018.6     0.1       0  5118.0    0.12       0
  5227.0    0.05       0
Bank Sta=4950.1,4961.9
Exp/Cntr=0.3,0.1

Type RM Length L Ch R = 1,18104,471,471,471
BEGIN DESCRIPTION:
Lynn Creek 32.0
END DESCRIPTION:
XS GIS Cut Line= 3
      2720226.00      6784311.03      2720126.00      6785211.00
      2720226.00      6786411.03
#Sta/Elev= 30
  4106.4  365.40  4156.7  364.79  4227.1  356.16  4237.2  356.33  4267.4  350.50
  4277.4  346.55  4287.5  345.43  4307.6  344.22  4378.0  343.34  4384.7  342.01
  4398.2  337.49  4408.2  335.74  4483.0  330.53  4518.9  327.29  4581.3  324.16
  4649.7  323.71  4675.8  322.41  4683.9  322.00  4685.6  321.50  5136.3  321.99
  5143.2  322.00  5152.4  325.23  5172.5  329.90  5282.8  328.99  5438.5  333.04
  5556.3  332.02  5834.8  337.96  5985.3  341.96  6085.6  346.39  6216.1  348.75
#Mann=9,-1,0
  4106.4    0.05       0  4384.7    0.12       0  4483.0     0.1       0
  4581.3    0.12       0  4675.8    0.05       0  4683.9    0.03       0
  5136.3    0.12       0  5143.2    0.05       0  5438.5    0.05       0
Bank Sta=4683.9,5143.2
Exp/Cntr=0.3,0.1

Type RM Length L Ch R = 1,17633,482,482,482
BEGIN DESCRIPTION:
Lynn Creek 31.0
END DESCRIPTION:
XS GIS Cut Line= 3
      2719525.99      6784560.98      2719726.00      6785161.00
      2720125.98      6786260.96
#Sta/Elev= 30
  4367.1  357.73  4388.2  355.15  4419.8  353.45  4440.9  350.31  4483.1  349.57
  4504.2  348.18  4546.3  342.00  4567.4  340.12  4588.5  335.36  4599.0  328.32
  4609.6  324.35  4635.2  322.00  4636.8  321.50  5267.8  321.98  5299.3  322.00
  5304.8  322.00  5310.1  323.38  5421.9  325.62  5542.7  330.40  5584.8  330.80
  5625.4  329.33  5648.7  330.59  5701.9  330.58  5864.8  334.41  5904.0  336.89
  5951.2  338.03  6084.9  344.88  6154.7  347.46  6160.1  346.91  6170.0  348.04
#Mann=5,-1,0
  4367.1    0.05       0  4635.2    0.03       0  5267.8    0.12       0
  5299.3    0.05       0  5542.7    0.05       0
Bank Sta=4635.2,5299.3
Exp/Cntr=0.3,0.1

Type RM Length L Ch R = 1,17151,466,466,466
BEGIN DESCRIPTION:
Lynn Creek 30.0
END DESCRIPTION:
XS GIS Cut Line= 3
      2719475.99      6784661.03      2719276.00      6785261.00
      2719276.00      6786260.97
#Sta/Elev= 30
  4367.1  350.14  4388.2  348.91  4419.8  345.78  4430.3  344.29  4483.0  339.12
  4546.3  332.06  4556.8  330.67  4577.9  325.38  4588.4  323.66  4609.5  322.68
  4614.0  322.00  4615.7  321.50  5311.5  321.96  5372.9  322.00  5389.5  322.42
  5399.5  323.57  5439.5  324.71  5457.6  326.14  5519.5  328.57  5569.5  329.64
  5599.5  331.46  5639.5  332.40  5659.5  332.31  5699.5  334.19  5739.5  335.06
  5789.5  336.92  5879.5  340.78  5899.5  342.35  5919.5  342.88  5999.5  346.49
#Mann=5,-1,0
  4367.1    0.05       0  4614.0    0.03       0  5311.5    0.12       0
  5372.9    0.05       0  5457.6    0.05       0
Bank Sta=4614,5372.9
Exp/Cntr=0.3,0.1

Type RM Length L Ch R = 1,16685,492,492,492
BEGIN DESCRIPTION:
Lynn Creek 29.0
END DESCRIPTION:
XS GIS Cut Line= 3
      2719325.99      6784611.01      2718826.00      6785211.00
      2719226.01      6786311.02
#Sta/Elev= 30
  4219.0  353.15  4275.6  348.29  4283.4  346.19  4297.1  344.48  4325.1  342.94
  4339.4  339.96  4403.2  332.69  4489.1  325.34  4545.1  323.01  4553.3  322.00
  4555.0  321.50  5484.7  322.00  5489.5  322.00  5500.1  323.98  5539.4  325.99
  5544.7  325.36  5570.0  326.60  5575.3  325.98  5600.5  326.29  5625.8  327.86
  5631.1  327.41  5681.0  329.40  5687.0  330.81  5723.6  330.18  5778.8  332.12
  5804.0  334.03  5936.4  337.98  5946.4  339.08  6038.1  343.37  6170.5  346.82
#Mann=3,-1,0
  4219.0    0.05       0  4553.3    0.03       0  5484.7    0.05       0
Bank Sta=4553.3,5484.7
Exp/Cntr=0.3,0.1

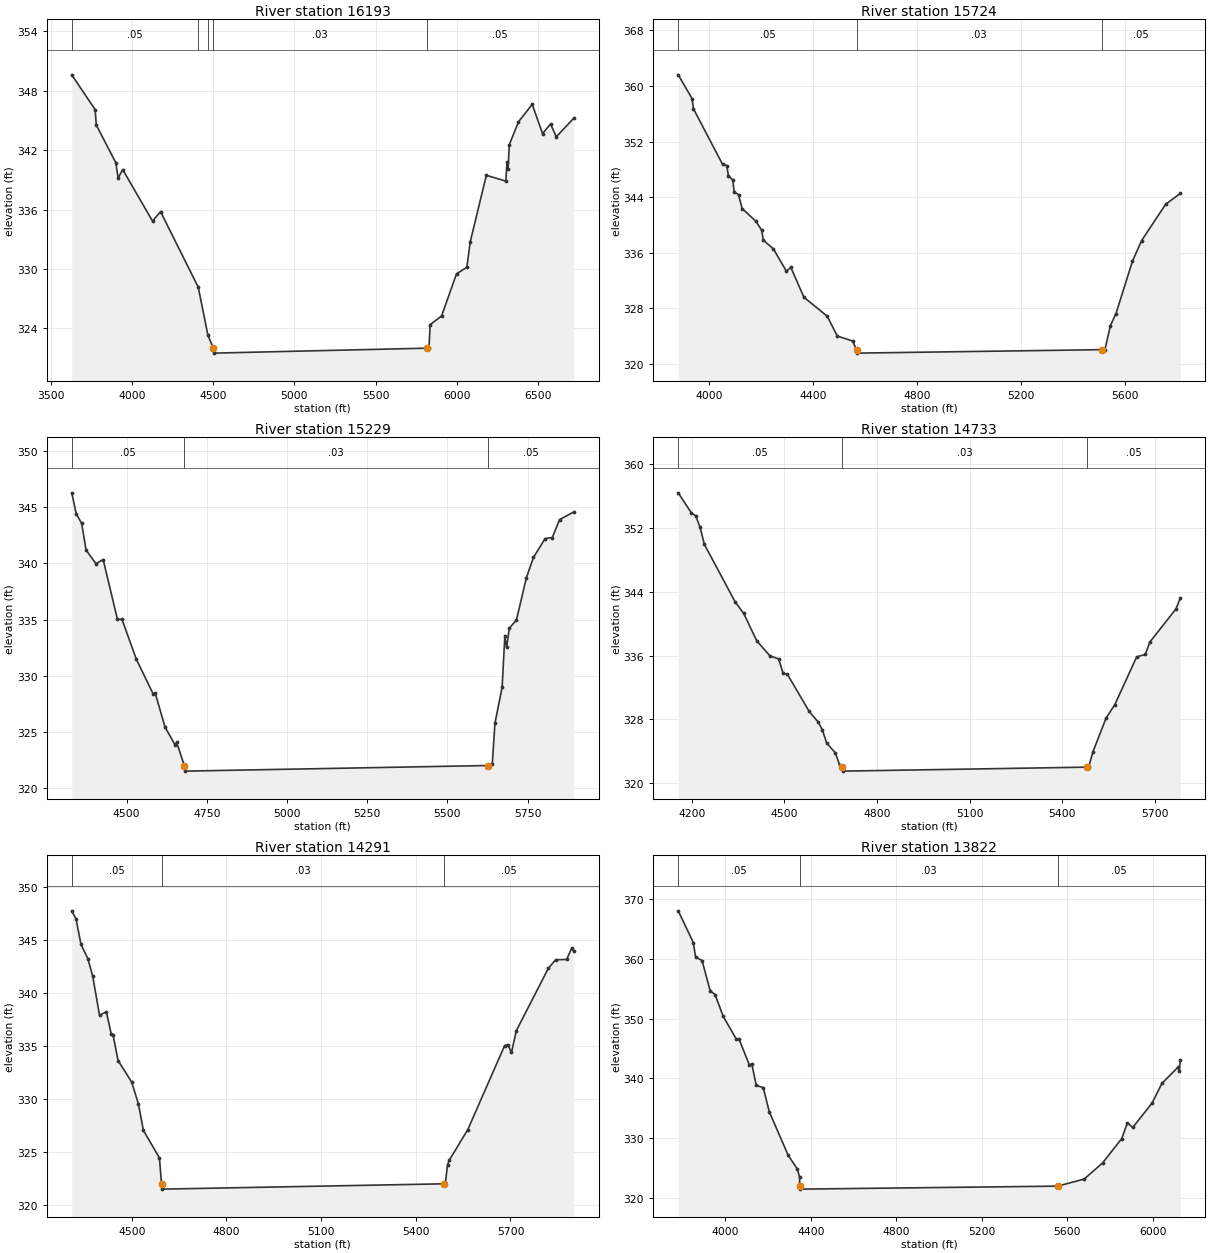
Type RM Length L Ch R = 1,16193,469,469,469
BEGIN DESCRIPTION:
Lynn Creek 28.0
END DESCRIPTION:
XS GIS Cut Line= 4
      2719320.91      6784122.05      2718376.00      6785111.00
      2717669.12      6785808.75      2717145.15      6786323.13
#Sta/Elev= 30
  3627.4  349.61  3771.6  346.09  3778.5  344.54  3899.0  340.73  3913.1  339.18
  3941.4  340.04  4125.1  334.84  4174.8  335.79  4407.2  328.16  4466.7  323.31
  4500.2  322.00  4502.2  321.50  5814.8  322.00  5829.6  322.00  5836.7  324.37
  5907.4  325.26  5999.3  329.51  6062.9  330.17  6084.2  332.76  6183.2  339.46
  6303.3  338.88  6310.5  340.78  6317.5  340.12  6324.6  342.54  6381.2  344.86
  6466.1  346.63  6529.6  343.68  6579.2  344.64  6614.5  343.35  6722.7  345.24
#Mann=5,-1,0
  3627.4    0.05       0  4407.2   0.075       0  4466.7    0.05       0
  4500.2    0.03       0  5814.8    0.05       0
Bank Sta=4500.2,5814.8
Exp/Cntr=0.3,0.1

Type RM Length L Ch R = 1,15724,495,495,495
BEGIN DESCRIPTION:
Lynn Creek 27.0
END DESCRIPTION:
XS GIS Cut Line= 3
      2718525.98      6783811.03      2718026.00      6784811.00
      2717426.03      6785360.97
#Sta/Elev= 30
  3882.0  361.61  3935.1  358.19  3940.7  356.71  4052.5  348.71  4069.2  348.54
  4074.8  347.08  4091.6  346.46  4097.2  344.79  4114.0  344.32  4127.9  342.34
  4181.0  340.50  4203.4  339.19  4209.0  337.79  4248.1  336.53  4298.4  333.29
  4315.2  333.86  4365.5  329.56  4455.0  326.83  4494.1  323.96  4552.8  323.25
  4568.1  322.00  4570.1  321.50  5511.2  322.00  5523.8  322.00  5544.8  325.45
  5566.4  327.21  5629.9  334.76  5665.0  337.72  5757.5  342.96  5813.9  344.51
#Mann=3,-1,0
  3882.0    0.05       0  4568.1    0.03       0  5511.2    0.05       0
Bank Sta=4568.1,5511.2
Exp/Cntr=0.3,0.1

Type RM Length L Ch R = 1,15229,496,496,496
BEGIN DESCRIPTION:
Lynn Creek 26.0
END DESCRIPTION:
XS GIS Cut Line= 3
      2717975.99      6783861.02      2717676.00      6784461.00
      2716876.02      6784860.99
#Sta/Elev= 30
  4329.2  346.29  4343.2  344.41  4359.9  343.58  4373.9  341.19  4404.6  339.97
  4427.0  340.35  4471.7  335.01  4485.7  335.02  4530.4  331.47  4583.5  328.34
  4589.1  328.47  4619.9  325.43  4650.6  323.86  4656.2  324.06  4679.9  322.00
  4681.9  321.50  5627.8  322.00  5640.1  322.14  5648.5  325.78  5670.8  328.96
  5679.2  333.50  5684.8  332.53  5693.2  334.23  5715.5  334.97  5746.3  338.71
  5768.6  340.54  5805.0  342.22  5827.3  342.31  5849.7  343.90  5894.4  344.59
#Mann=3,-1,0
  4329.2    0.05       0  4679.9    0.03       0  5627.8    0.05       0
Bank Sta=4679.9,5627.8
Exp/Cntr=0.3,0.1

Type RM Length L Ch R = 1,14733,442,442,442
BEGIN DESCRIPTION:
Lynn Creek 25.0
END DESCRIPTION:
XS GIS Cut Line= 3
      2717925.99      6783511.01      2717326.00      6784111.00
      2716776.02      6784660.98
#Sta/Elev= 30
  4156.3  356.43  4198.7  353.92  4212.8  353.54  4227.0  352.12  4241.1  349.95
  4340.1  342.78  4368.4  341.29  4410.8  337.84  4453.3  335.97  4481.6  335.58
  4495.7  333.81  4509.8  333.66  4580.5  328.99  4608.8  327.70  4623.0  326.70
  4637.1  325.02  4665.4  323.79  4679.5  322.21  4686.6  322.00  4688.6  321.50
  5480.6  322.00  5485.6  322.00  5499.8  323.95  5542.2  328.16  5570.5  329.85
  5641.2  335.84  5669.5  336.15  5683.6  337.68  5768.5  341.86  5782.6  343.21
#Mann=3,-1,0
  4156.3    0.05       0  4686.6    0.03       0  5480.6    0.05       0
Bank Sta=4686.6,5480.6
Exp/Cntr=0.3,0.1

Type RM Length L Ch R = 1,14291,469,469,469
BEGIN DESCRIPTION:
Lynn Creek 24.0
END DESCRIPTION:
XS GIS Cut Line= 3
      2717675.97      6783411.02      2717076.00      6783761.00
      2716616.38      6784530.61
#Sta/Elev= 30
  4309.8  347.71  4323.4  346.94  4339.1  344.54  4360.6  343.22  4376.3  341.54
  4397.8  337.86  4419.3  338.21  4435.0  336.09  4440.8  335.99  4456.5  333.61
  4499.5  331.59  4521.0  329.53  4536.8  327.03  4587.6  324.44  4594.2  322.00
  4596.2  321.50  5488.5  322.00  5493.6  322.04  5500.6  323.79  5506.4  324.24
  5564.8  327.11  5681.5  335.02  5691.3  335.11  5703.2  334.37  5718.5  336.42
  5819.7  342.28  5843.0  343.10  5878.0  343.13  5893.6  344.17  5900.8  343.93
#Mann=3,-1,0
  4309.8    0.05       0  4594.2    0.03       0  5488.5    0.05       0
Bank Sta=4594.2,5488.5
Exp/Cntr=0.3,0.1

Type RM Length L Ch R = 1,13822,468,468,468
BEGIN DESCRIPTION:
Lynn Creek 23.0
END DESCRIPTION:
XS GIS Cut Line= 3
      2717975.95      6783211.01      2716776.00      6783411.00
      2716488.19      6784506.00
#Sta/Elev= 30
  3779.6  367.99  3850.5  362.66  3860.7  360.28  3891.1  359.69  3929.1  354.62
  3951.9  354.00  3989.9  350.36  4050.7  346.60  4063.4  346.62  4111.6  342.31
  4124.2  342.34  4144.5  338.83  4177.5  338.45  4205.3  334.44  4294.1  327.14
  4337.1  324.84  4347.3  323.52  4347.8  322.00  4349.8  321.50  5554.6  322.00
  5678.5  323.18  5764.8  325.88  5854.3  329.95  5880.7  332.56  5906.0  331.81
  5996.6  335.90  6042.1  339.16  6117.6  341.87  6123.1  341.23  6128.3  343.00
#Mann=3,-1,0
  3779.6    0.05       0  4347.8    0.03       0  5554.6    0.05       0
Bank Sta=4347.8,5554.6
Exp/Cntr=0.3,0.1

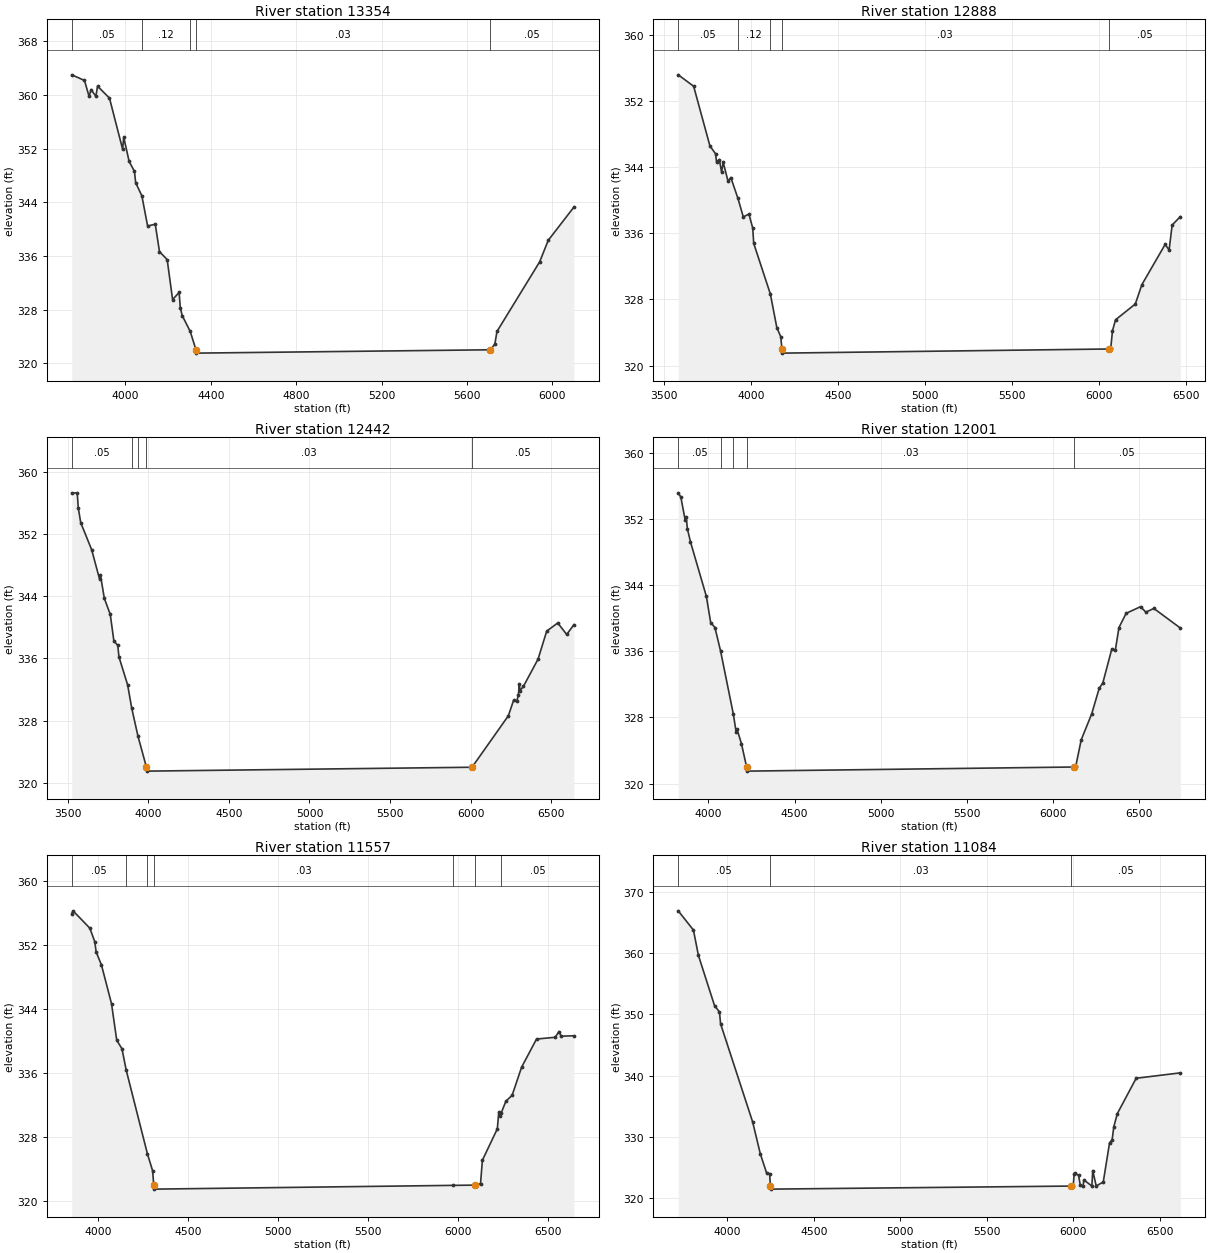
Type RM Length L Ch R = 1,13354,466,466,466
BEGIN DESCRIPTION:
Lynn Creek 22.0
END DESCRIPTION:
XS GIS Cut Line= 3
      2716753.23      6782185.01      2716326.00      6783361.00
      2716326.00      6784461.01
#Sta/Elev= 30
  3748.8  363.01  3808.4  362.17  3829.7  359.80  3839.1  360.81  3861.6  359.81
  3869.7  361.32  3925.4  359.53  3986.8  351.93  3992.1  353.69  4017.4  350.10
  4042.4  348.61  4048.0  346.92  4077.0  344.97  4103.9  340.47  4139.8  340.72
  4159.5  336.65  4195.7  335.44  4220.9  329.49  4251.6  330.55  4256.9  328.30
  4265.9  327.11  4303.6  324.73  4330.4  322.00  4332.4  321.50  5709.2  322.00
  5730.0  322.84  5740.0  324.73  5940.0  335.12  5980.0  338.32  6100.0  343.27
#Mann=5,-1,0
  3748.8    0.05       0  4077.0    0.12       0  4303.6    0.05       0
  4330.4    0.03       0  5709.2    0.05       0
Bank Sta=4330.4,5709.2
Exp/Cntr=0.3,0.1

Type RM Length L Ch R = 1,12888,446,446,446
BEGIN DESCRIPTION:
Lynn Creek 21.0
END DESCRIPTION:
XS GIS Cut Line= 3
      2716544.52      6782061.16      2715876.00      6783311.00
      2715682.16      6784767.46
#Sta/Elev= 30
  3582.6  355.15  3671.2  353.77  3764.6  346.57  3797.1  345.60  3802.8  344.62
  3819.1  344.90  3831.9  343.37  3841.0  344.59  3868.6  342.30  3884.9  342.73
  3925.8  340.22  3956.7  337.97  3989.0  338.31  4010.9  336.62  4016.6  334.77
  4112.4  328.64  4149.4  324.59  4172.1  323.48  4178.8  322.00  4180.8  321.50
  6056.5  322.00  6069.3  322.08  6079.4  324.20  6096.8  325.53  6210.6  327.44
  6248.3  329.78  6382.1  334.64  6404.8  333.97  6422.4  336.99  6469.3  338.00
#Mann=5,-1,0
  3582.6    0.05       0  3925.8    0.12       0  4112.4    0.05       0
  4178.8    0.03       0  6056.5    0.05       0
Bank Sta=4178.8,6056.5
Exp/Cntr=0.3,0.1

Type RM Length L Ch R = 1,12442,441,441,441
BEGIN DESCRIPTION:
Lynn Creek 20.0
END DESCRIPTION:
XS GIS Cut Line= 3
      2716026.47      6781789.50      2715476.00      6783161.00
      2715066.32      6784743.90
#Sta/Elev= 30
  3526.3  357.26  3560.2  357.24  3566.7  355.32  3581.8  353.43  3650.1  349.92
  3698.5  346.18  3703.9  346.72  3728.1  343.71  3765.0  341.63  3787.3  338.24
  3811.5  337.65  3818.9  336.17  3872.7  332.58  3897.8  329.61  3937.1  325.96
  3989.3  322.00  3991.3  321.50  6007.9  322.00  6233.4  328.62  6265.4  330.59
  6285.0  330.47  6295.3  331.24  6300.9  332.74  6306.0  331.86  6326.3  332.38
  6417.5  335.90  6470.9  339.49  6539.4  340.54  6594.9  339.06  6639.2  340.31
#Mann=5,-1,0
  3526.3    0.05       0  3897.8    0.12       0  3937.1    0.05       0
  3989.3    0.03       0  6007.9    0.05       0
Bank Sta=3989.3,6007.9
Exp/Cntr=0.3,0.1

Type RM Length L Ch R = 1,12001,444,444,444
BEGIN DESCRIPTION:
Lynn Creek 19.0
END DESCRIPTION:
XS GIS Cut Line= 3
      2715525.99      6781811.02      2715126.00      6782911.00
      2714637.76      6784582.51
#Sta/Elev= 30
  3825.2  355.20  3840.5  354.67  3865.7  351.88  3871.1  352.31  3878.4  350.84
  3896.3  349.25  3988.1  342.68  4013.4  339.49  4038.0  338.89  4070.4  336.08
  4144.9  328.39  4161.0  326.22  4166.3  326.57  4191.6  324.84  4221.8  322.00
  4223.8  321.50  6121.6  322.00  6131.2  322.16  6162.4  325.30  6222.9  328.42
  6266.8  331.54  6287.5  332.17  6339.6  336.28  6360.4  336.18  6381.2  338.89
  6422.9  340.61  6506.2  341.41  6537.5  340.75  6583.6  341.20  6737.0  338.83
#Mann=5,-1,0
  3825.2    0.05       0  4070.4    0.12       0  4144.9    0.05       0
  4221.8    0.03       0  6121.6    0.05       0
Bank Sta=4221.8,6121.6
Exp/Cntr=0.3,0.1

Type RM Length L Ch R = 1,11557,473,473,473
BEGIN DESCRIPTION:
Lynn Creek 18.0
END DESCRIPTION:
XS GIS Cut Line= 3
      2715475.97      6781761.03      2714776.00      6782661.00
      2714341.87      6784250.96
#Sta/Elev= 30
  3855.5  355.88  3862.7  356.22  3955.9  354.05  3983.0  352.38  3991.2  351.06
  4020.2  349.47  4076.3  344.61  4105.2  340.05  4134.2  338.99  4157.9  336.31
  4275.5  325.87  4304.3  323.76  4310.9  321.95  4312.9  321.45  5972.3  321.92
  6092.6  321.95  6125.5  322.12  6135.9  325.06  6218.8  328.98  6226.8  331.05
  6231.9  330.54  6241.4  331.02  6266.5  332.44  6301.0  333.17  6353.6  336.68
  6436.5  340.20  6540.2  340.42  6560.9  341.13  6573.8  340.56  6643.8  340.61
#Mann=7,-1,0
  3855.5    0.05       0  4157.9    0.12       0  4275.5    0.05       0
  4310.9    0.03       0  5972.3   0.075       0  6092.6    0.05       0
  6241.4    0.05       0
Bank Sta=4310.9,6092.6
Exp/Cntr=0.3,0.1

Type RM Length L Ch R = 1,11084,462,462,462
BEGIN DESCRIPTION:
Lynn Creek 17.0
END DESCRIPTION:
XS GIS Cut Line= 3
      2714897.44      6781287.30      2714376.00      6782461.00
      2714061.73      6784047.86
#Sta/Elev= 30
  3715.7  366.86  3803.6  363.72  3832.4  359.59  3925.4  351.42  3954.1  350.37
  3960.5  348.44  4145.7  332.46  4190.3  327.24  4226.4  324.13  4244.2  324.01
  4248.0  322.00  4250.0  321.50  5984.6  322.00  5998.9  322.01  6004.0  324.02
  6009.2  324.08  6029.6  323.74  6039.8  322.11  6055.2  322.00  6060.3  323.01
  6106.4  322.00  6111.5  324.53  6131.6  322.01  6172.4  322.67  6208.9  329.08
  6223.3  329.48  6233.5  331.69  6253.9  333.82  6362.5  339.57  6617.7  340.45
#Mann=3,-1,0
  3715.7    0.05       0  4248.0    0.03       0  5984.6    0.05       0
Bank Sta=4248,5984.6
Exp/Cntr=0.3,0.1

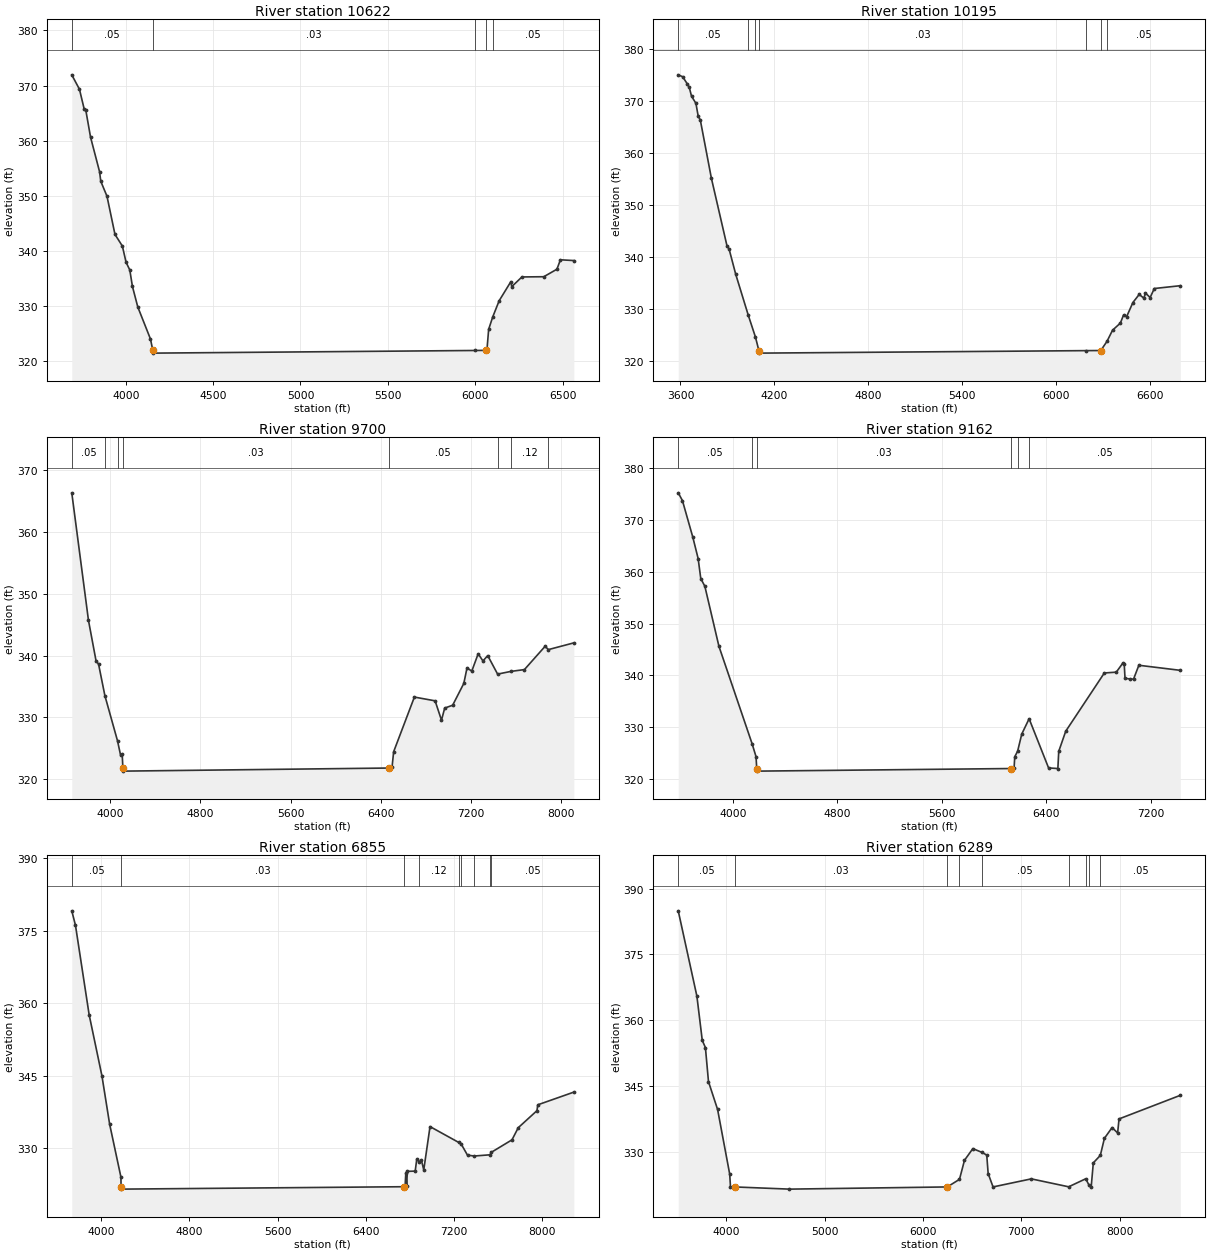
Type RM Length L Ch R = 1,10622,427,427,427
BEGIN DESCRIPTION:
Lynn Creek 16.0
END DESCRIPTION:
XS GIS Cut Line= 3
      2714675.99      6781161.02      2713976.00      6782261.00
      2713891.76      6783827.72
#Sta/Elev= 30
  3691.3  371.95  3735.3  369.33  3762.4  365.74  3771.7  365.52  3798.8  360.64
  3850.4  354.38  3857.2  352.66  3892.8  349.94  3938.5  343.02  3980.8  340.91
  4002.0  337.97  4023.2  336.58  4038.4  333.59  4068.9  329.88  4141.7  324.05
  4155.0  322.00  4157.0  321.50  5998.2  321.98  6060.0  322.00  6066.7  322.01
  6076.7  325.82  6100.1  328.07  6136.8  331.00  6203.8  334.46  6208.8  333.55
  6267.0  335.31  6392.1  335.35  6467.2  336.71  6487.3  338.42  6564.1  338.28
#Mann=5,-1,0
  3691.3    0.05       0  4155.0    0.03       0  5998.2   0.075       0
  6060.0    0.05       0  6100.1    0.05       0
Bank Sta=4155,6060
Exp/Cntr=0.3,0.1

Type RM Length L Ch R = 1,10195,495,495,495
BEGIN DESCRIPTION:
Lynn Creek 15.0
END DESCRIPTION:
XS GIS Cut Line= 3
      2714625.98      6781061.02      2713626.00      6782061.00
      2713532.41      6783853.58
#Sta/Elev= 30
  3585.8  374.95  3614.1  374.58  3642.3  373.27  3656.5  372.52  3670.6  370.86
  3698.9  369.47  3713.0  367.07  3727.2  366.23  3797.9  355.06  3896.9  342.17
  3911.0  341.47  3953.5  336.62  4034.0  328.73  4079.6  324.56  4101.1  322.00
  4103.1  321.50  6194.6  321.98  6286.7  322.00  6326.1  323.75  6361.8  325.90
  6411.9  327.27  6431.9  328.80  6452.0  328.51  6492.0  331.22  6532.1  332.77
  6562.1  332.06  6572.1  333.04  6602.2  332.18  6628.7  333.91  6795.0  334.45
#Mann=7,-1,0
  3585.8    0.05       0  4034.0    0.12       0  4079.6    0.05       0
  4101.1    0.03       0  6194.6   0.075       0  6286.7    0.05       0
  6326.1    0.05       0
Bank Sta=4101.1,6286.7
Exp/Cntr=0.3,0.1

Type RM Length L Ch R = 1,9700,538,538,538
BEGIN DESCRIPTION:
Lynn Creek 14.0
END DESCRIPTION:
XS GIS Cut Line= 3
      2714475.96      6781111.02      2713276.00      6781711.00
      2711075.98      6783911.02
#Sta/Elev= 30
  3658.4  366.31  3806.5  345.70  3873.6  339.16  3895.9  338.63  3952.1  333.53
  4064.0  326.23  4091.6  323.89  4105.6  324.14  4111.6  321.83  4113.6  321.33
  6470.5  321.83  6499.1  322.00  6513.2  324.47  6697.1  333.30  6880.9  332.69
  6937.5  329.56  6965.8  331.52  7036.5  331.98  7135.5  335.51  7163.7  338.00
  7206.2  337.50  7262.7  340.29  7305.2  339.14  7347.6  340.00  7435.2  337.01
  7553.6  337.45  7672.9  337.74  7856.7  341.51  7885.4  340.97  8111.3  342.06
#Mann=8,-1,0
  3658.4    0.05       0  3952.1    0.12       0  4064.0    0.05       0
  4111.6    0.03       0  6470.5    0.05       0  7435.2     0.1       0
  7553.6    0.12       0  7885.4    0.05       0
Bank Sta=4111.6,6470.5
Exp/Cntr=0.3,0.1

Type RM Length L Ch R = 1,9162,2307,2307,2307
BEGIN DESCRIPTION:
Lynn Creek 13.0
END DESCRIPTION:
XS GIS Cut Line= 3
      2714575.96      6780961.01      2713176.00      6781211.00
      2710793.70      6781641.02
#Sta/Elev= 30
  3583.0  375.26  3615.0  373.77  3694.7  366.68  3735.3  362.57  3755.6  358.69
  3786.6  357.22  3894.3  345.63  4148.0  326.82  4178.5  324.29  4183.8  322.00
  4185.8  321.50  6128.0  322.00  6153.4  322.02  6158.8  324.28  6180.6  325.35
  6212.4  328.66  6268.6  331.62  6417.6  322.12  6488.7  322.00  6495.4  325.32
  6548.9  329.21  6844.4  340.46  6935.8  340.62  6986.6  342.39  6996.8  342.10
  7002.7  339.44  7037.4  339.31  7067.9  339.27  7108.6  341.95  7425.9  340.97
#Mann=6,-1,0
  3583.0    0.05       0  4148.0    0.12       0  4183.8    0.03       0
  6128.0    0.12       0  6180.6    0.12       0  6268.6    0.05       0
Bank Sta=4183.8,6128
Exp/Cntr=0.3,0.1

Type RM Length L Ch R = 1,6855,566,566,566
BEGIN DESCRIPTION:
Lynn Creek 12.0
END DESCRIPTION:
XS GIS Cut Line= 3
      2714875.99      6779261.00      2713626.00      6779061.00
      2711196.75      6781273.83
#Sta/Elev= 30
  3734.2  379.13  3767.7  376.14  3891.8  357.60  4007.6  344.96  4077.9  334.90
  4179.8  324.00  4181.2  322.00  4183.2  321.50  6748.8  322.00  6755.8  322.00
  6762.6  324.78  6770.0  322.25  6776.8  325.18  6847.7  325.23  6861.9  327.67
  6885.9  327.17  6904.4  327.46  6925.4  325.48  6982.2  334.45  7243.1  331.16
  7263.2  330.90  7322.0  328.53  7384.8  328.36  7526.6  328.61  7536.9  329.11
  7725.4  331.71  7782.1  334.22  7951.7  337.75  7959.2  338.96  8286.1  341.59
#Mann=9,-1,0
  3734.2    0.05       0  4181.2    0.03       0  6748.8    0.05       0
  6885.9    0.12       0  7243.1    0.05       0  7263.2    0.12       0
  7384.8    0.05       0  7526.6    0.12       0  7536.9    0.05       0
Bank Sta=4181.2,6748.8
Exp/Cntr=0.3,0.1

Type RM Length L Ch R = 1,6289,566,566,566
BEGIN DESCRIPTION:
Lynn Creek 11.0
END DESCRIPTION:
XS GIS Cut Line= 3
      2714976.01      6779011.00      2713576.00      6778511.00
      2711100.17      6781145.08
#Sta/Elev= 30
  3513.4  384.95  3703.0  365.49  3757.6  355.40  3789.5  353.78  3820.8  346.00
  3913.2  339.66  4036.4  324.91  4044.3  322.00  4086.1  321.99  4643.8  321.49
  6247.2  321.99  6371.1  323.72  6422.0  328.07  6507.0  330.73  6599.3  329.87
  6648.2  329.26  6662.4  325.05  6712.2  321.99  7101.0  323.83  7480.5  322.02
  7654.0  323.85  7685.8  322.46  7709.5  322.01  7731.0  327.48  7802.2  329.18
  7843.8  333.08  7921.9  335.53  7978.2  334.30  7992.3  337.50  8615.0  342.88
#Mann=9,-1,0
  3513.4    0.05       0  4086.1    0.03       0  6247.2    0.05       0
  6371.1    0.12       0  6599.3    0.05       0  7480.5    0.12       0
  7654.0    0.05       0  7685.8    0.12       0  7802.2    0.05       0
Bank Sta=4086.1,6247.2
Exp/Cntr=0.3,0.1

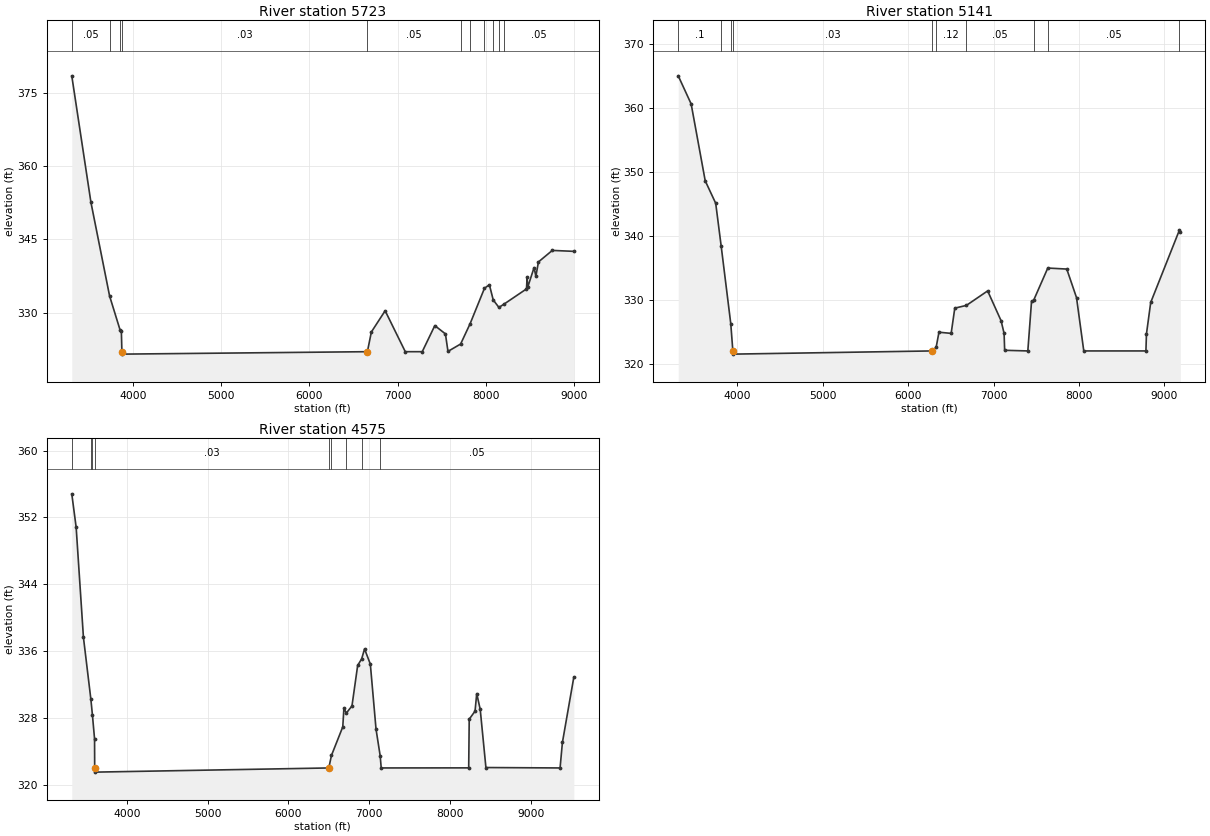
Type RM Length L Ch R = 1,5723,582,582,582
BEGIN DESCRIPTION:
Lynn Creek 10.0
END DESCRIPTION:
XS GIS Cut Line= 3
      2714925.98      6778910.98      2713526.00      6777961.00
      2711030.95      6781079.70
#Sta/Elev= 30
  3308.6  378.47  3525.6  352.57  3736.8  333.41  3854.5  326.51  3870.0  326.32
  3876.2  322.00  3878.2  321.50  6656.5  322.00  6701.3  326.03  6857.4  330.38
  7085.5  322.00  7277.6  322.00  7420.0  327.34  7540.1  325.64  7568.9  322.06
  7712.2  323.57  7819.2  327.71  7982.5  334.99  8037.9  335.69  8081.5  332.59
  8145.8  331.06  8204.6  331.75  8458.2  334.85  8465.3  337.32  8471.7  335.18
  8543.8  339.21  8564.6  337.44  8593.4  340.37  8750.3  342.73  8994.4  342.54
#Mann=11,-1,0
  3308.6    0.05       0  3736.8     0.1       0  3854.5    0.05       0
  3876.2    0.03       0  6656.5    0.05       0  7712.2    0.12       0
  7819.2    0.05       0  7982.5    0.12       0  8081.5    0.05       0
  8145.8    0.12       0  8204.6    0.05       0
Bank Sta=3876.2,6656.5
Exp/Cntr=0.3,0.1

Type RM Length L Ch R = 1,5141,566,566,566
BEGIN DESCRIPTION:
Lynn Creek 9.0
END DESCRIPTION:
XS GIS Cut Line= 3
      2714825.96      6778360.97      2713426.00      6777411.00
      2710854.32      6780714.71
#Sta/Elev= 30
  3308.1  365.08  3459.3  360.68  3624.0  348.64  3746.8  345.12  3811.4  338.36
  3923.1  326.28  3947.5  322.00  3949.5  321.50  6277.5  322.00  6327.8  322.56
  6360.8  324.93  6503.7  324.75  6546.0  328.70  6681.8  329.13  6930.8  331.40
  7088.2  326.73  7123.5  324.74  7129.9  322.10  7401.3  322.00  7444.7  329.77
  7468.6  329.91  7634.9  334.98  7857.3  334.82  7971.3  330.35  8056.4  322.00
  8783.9  322.00  8790.2  324.66  8840.0  329.59  9174.9  340.88  9186.6  340.69
#Mann=10,-1,0
  3308.1     0.1       0  3811.4    0.12       0  3923.1    0.05       0
  3947.5    0.03       0  6277.5    0.05       0  6327.8    0.12       0
  6681.8    0.05       0  7468.6    0.12       0  7634.9    0.05       0
  9174.9   0.075       0
Bank Sta=3947.5,6277.5
Exp/Cntr=0.3,0.1

Type RM Length L Ch R = 1,4575,0,0,0
BEGIN DESCRIPTION:
Lynn Creek 8.0
END DESCRIPTION:
XS GIS Cut Line= 3
      2714926.02      6777511.01      2713376.00      6776861.00
      2710553.47      6780407.52
#Sta/Elev= 30
  3319.3  354.82  3373.5  350.82  3463.6  337.64  3555.6  330.23  3574.8  328.35
  3601.3  325.48  3602.9  322.00  3604.9  321.50  6500.3  322.00  6533.1  323.50
  6673.1  326.92  6687.1  329.15  6717.2  328.57  6786.8  329.42  6857.3  334.27
  6906.7  335.06  6942.7  336.25  7014.2  334.43  7084.7  326.64  7135.9  323.46
  7148.8  322.00  8231.5  322.01  8237.9  327.84  8310.0  328.80  8330.8  330.90
  8374.1  329.01  8444.5  322.05  9362.3  322.00  9391.2  325.05  9532.7  332.89
#Mann=9,-1,0
  3319.3    0.05       0  3555.6    0.12       0  3574.8    0.05       0
  3602.9    0.03       0  6500.3    0.05       0  6533.1    0.12       0
  6717.2    0.05       0  6906.7    0.12       0  7135.9    0.05       0
Bank Sta=3602.9,6500.3
Exp/Cntr=0.3,0.1

Chan Stop Cuts=-1