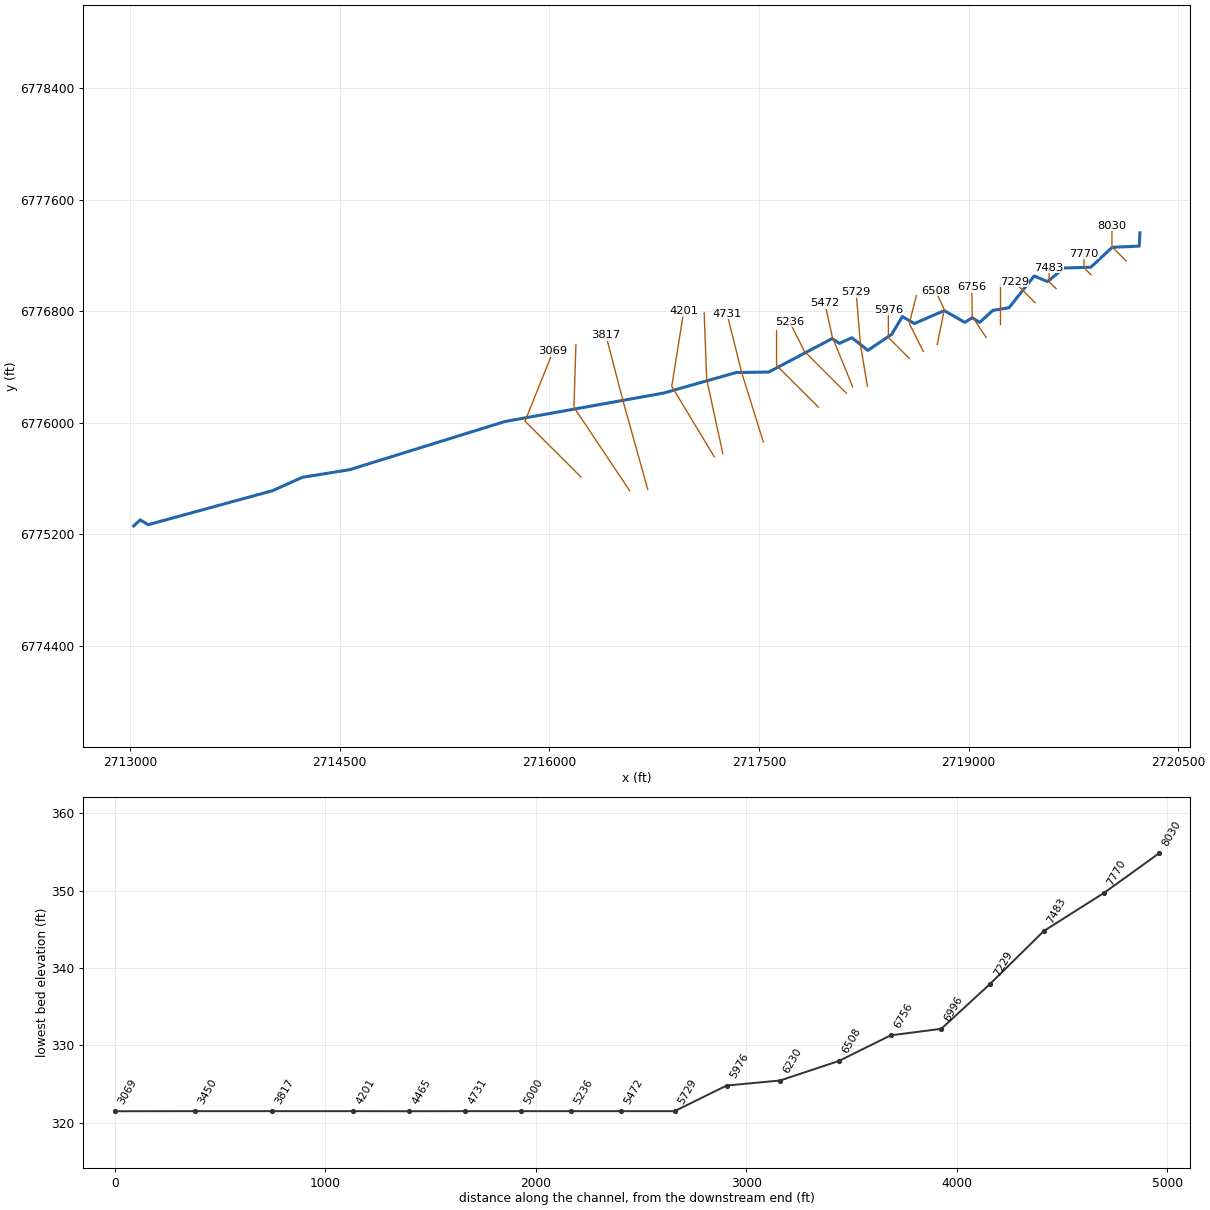
--- Lynn Creek T1.prj (project) ---

Proj Title=Lynn Creek T1 Base Level Engineering
Current Plan=p01
Default Exp/Contr=0.3,0.1
English Units
Geom File=g01
Flow File=f01
Plan File=p01
BEGIN DESCRIPTION:
Lynn Creek T1
END DESCRIPTION:

--- Lynn Creek T1.p01 (plan) ---

Plan Title=Multiple Run
Short Identifier=Multiple
Geom File=g01
Flow File=f01
Subcritical Flow
K Sum by GR= 0
Std Step Tol= 0.01
Critical Tol= 0.01
Num of Std Step Trials= 20
Max Error Tol= 0.3
Flow Tol Ratio= 0.001
Split Flow NTrial= 30
Split Flow Tol= 0.02
Split Flow Ratio= 0.02
Log Output Level= 0
Friction Slope Method= 1
Unsteady Friction Slope Method= 2
Unsteady Bridges Friction Slope Method= 1
Parabolic Critical Depth
Global Vel Dist=  1 , 1 , 1
Global Log Level= 0
CheckData=True
Encroach Param= -1, 0, 0, 0
BEGIN DESCRIPTION:
Multiple Run
END DESCRIPTION:

--- Lynn Creek T1.f01 (steady flow) ---

Flow Title=Multiple
Number of Profiles=7
Profile Names=10-year,25-year,50-year,1pct_min,100-year,1pct_plu,500-year
River Rch & RM= Lynn Creek T1,Reach-1,8030
     242     307     358     208     415     827     555
River Rch & RM= Lynn Creek T1,Reach-1,5976
     549     731     876     521    1040    2076    1465
Boundary for River Rch & Prof#=Lynn Creek T1,Reach-1,1
Up Type=0
Dn Type=3
Dn Slope=0.005
Boundary for River Rch & Prof#=Lynn Creek T1,Reach-1,2
Up Type=0
Dn Type=3
Dn Slope=0.005
Boundary for River Rch & Prof#=Lynn Creek T1,Reach-1,3
Up Type=0
Dn Type=3
Dn Slope=0.005
Boundary for River Rch & Prof#=Lynn Creek T1,Reach-1,4
Up Type=0
Dn Type=3
Dn Slope=0.005
Boundary for River Rch & Prof#=Lynn Creek T1,Reach-1,5
Up Type=0
Dn Type=3
Dn Slope=0.005
Boundary for River Rch & Prof#=Lynn Creek T1,Reach-1,6
Up Type=0
Dn Type=3
Dn Slope=0.005
Boundary for River Rch & Prof#=Lynn Creek T1,Reach-1,7
Up Type=0
Dn Type=3
Dn Slope=0.005

--- Lynn Creek T1.g01 (geometry) ---

Geom Title=Existing Conditions

River Reach=Lynn Creek T1,Reach-1
Reach XY= 30
      2720226.00      6777361.00      2720221.22      6777265.78
      2720027.47      6777257.46      2719874.54      6777114.54
      2719681.86      6777108.93      2719565.36      6777011.65
      2719469.25      6777051.86      2719289.33      6776824.39
      2719173.57      6776805.45      2719079.33      6776719.00
      2719026.00      6776752.96      2718972.77      6776719.23
      2718826.01      6776803.47      2718611.96      6776711.13
      2718526.00      6776761.00      2718449.86      6776633.84
      2718279.38      6776518.78      2718164.53      6776609.26
      2718075.94      6776568.84      2718022.78      6776602.73
      2717570.06      6776363.26      2717336.50      6776359.78
      2716816.34      6776212.38      2715681.94      6776008.74
      2714570.47      6775663.39      2714231.94      6775608.73
      2714020.47      6775513.39      2713129.21      6775269.16
      2713072.66      6775303.49      2713026.00      6775261.00

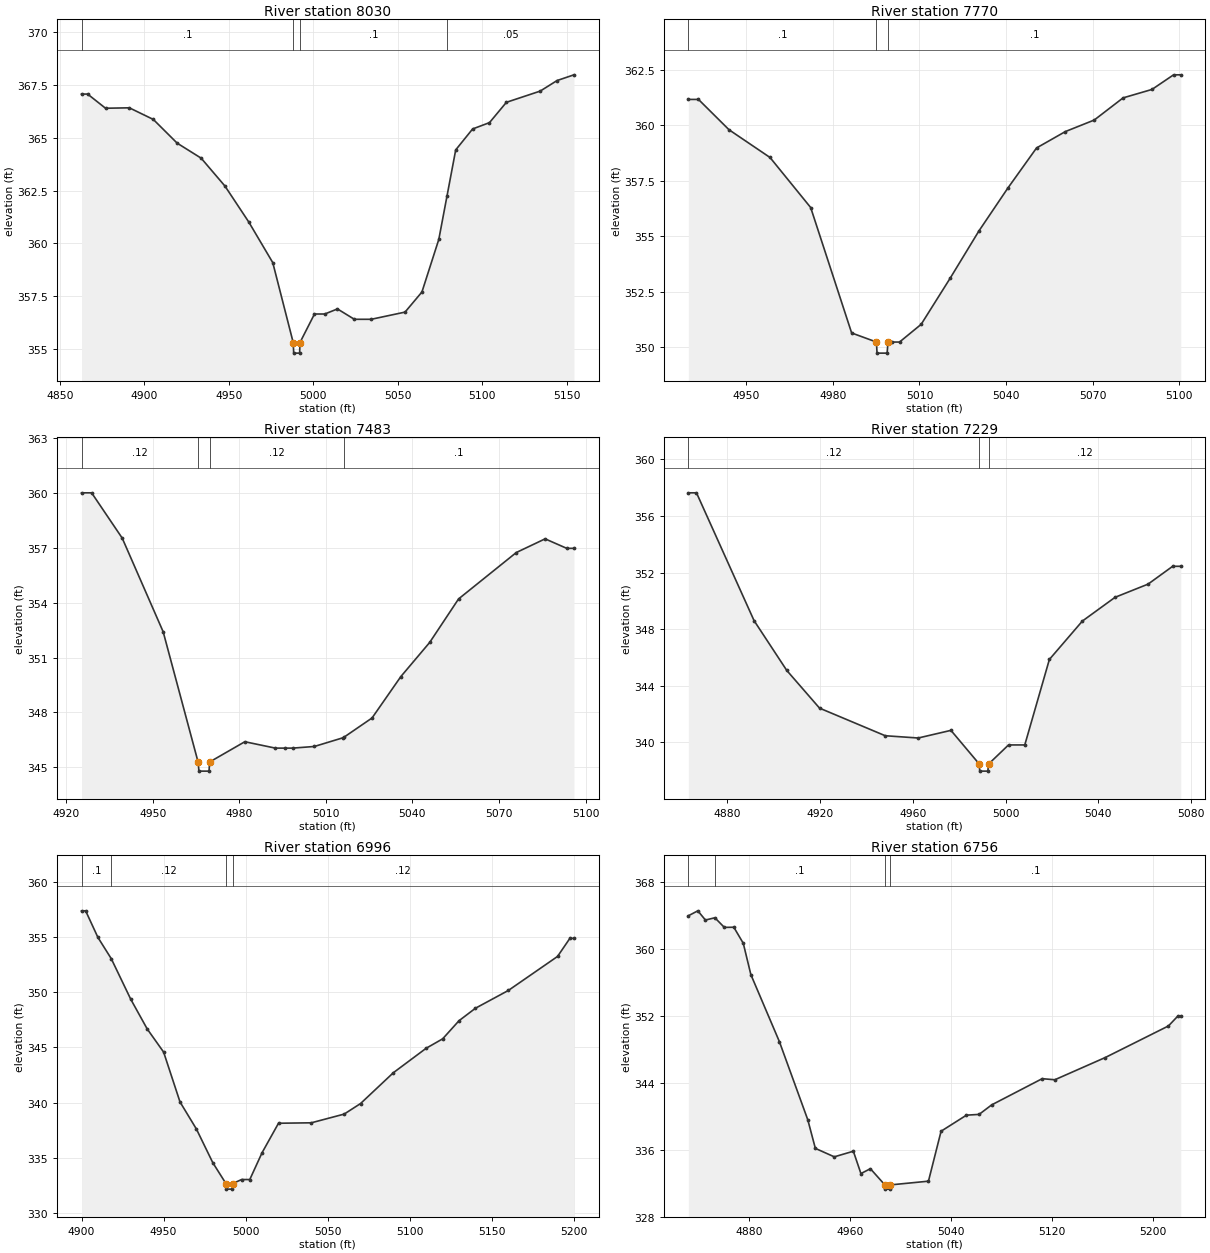
Type RM Length L Ch R = 1,8030,260,260,260
BEGIN DESCRIPTION:
Lynn Creek T1 19.0
END DESCRIPTION:
XS GIS Cut Line= 3
      2720126.03      6777160.97      2720026.00      6777261.00
      2720026.00      6777411.04
#Sta/Elev= 30
  4862.8  367.06  4866.4  367.06  4877.0  366.39  4891.1  366.41  4905.3  365.86
  4919.4  364.74  4933.6  364.03  4947.7  362.71  4961.8  361.01  4976.0  359.09
  4988.1  355.31  4988.4  354.81  4991.9  354.81  4992.1  355.31  5000.7  356.66
  5006.8  356.66  5014.3  356.90  5024.3  356.41  5034.3  356.41  5054.3  356.75
  5064.3  357.70  5074.3  360.19  5079.1  362.22  5084.3  364.42  5094.3  365.41
  5104.3  365.71  5114.3  366.67  5134.3  367.20  5144.3  367.70  5154.3  367.97
#Mann=4,-1,0
  4862.8     0.1       0  4988.1    0.07       0  4992.1     0.1       0
  5079.1    0.05       0
Bank Sta=4988.1,4992.1
Exp/Cntr=0.3,0.1

Type RM Length L Ch R = 1,7770,287,287,287
BEGIN DESCRIPTION:
Lynn Creek T1 18.0
END DESCRIPTION:
XS GIS Cut Line= 3
      2719876.00      6777061.00      2719826.00      6777111.00
      2719826.00      6777210.99
#Sta/Elev= 23
  4929.9  361.17  4933.4  361.17  4944.0  359.80  4958.2  358.55  4972.3  356.29
  4986.5  350.63  4995.1  350.22  4995.3  349.72  4998.8  349.72  4999.1  350.22
  5000.6  350.22  5003.1  350.22  5010.6  351.02  5020.6  353.09  5030.6  355.23
  5040.6  357.16  5050.6  358.98  5060.6  359.72  5070.6  360.24  5080.6  361.24
  5090.6  361.62  5098.1  362.28  5100.6  362.28
#Mann=3,-1,0
  4929.9     0.1       0  4995.1    0.07       0  4999.1     0.1       0
Bank Sta=4995.1,4999.1
Exp/Cntr=0.3,0.1

Type RM Length L Ch R = 1,7483,254,254,254
BEGIN DESCRIPTION:
Lynn Creek T1 17.0
END DESCRIPTION:
XS GIS Cut Line= 3
      2719626.00      6776961.00      2719576.00      6777011.00
      2719576.00      6777110.99
#Sta/Elev= 23
  4925.3  360.02  4928.8  360.02  4939.4  357.54  4953.6  352.41  4965.7  345.28
  4966.0  344.78  4969.5  344.78  4969.7  345.28  4981.9  346.39  4992.5  346.04
  4996.0  346.04  4998.5  346.04  5006.0  346.13  5016.0  346.61  5016.3  346.64
  5026.0  347.69  5036.0  349.96  5046.0  351.83  5056.0  354.21  5076.0  356.75
  5086.0  357.50  5093.5  356.98  5096.0  356.98
#Mann=4,-1,0
  4925.3    0.12       0  4965.7    0.07       0  4969.7    0.12       0
  5016.3     0.1       0
Bank Sta=4965.7,4969.7
Exp/Cntr=0.3,0.1

Type RM Length L Ch R = 1,7229,233,233,233
BEGIN DESCRIPTION:
Lynn Creek T1 16.0
END DESCRIPTION:
XS GIS Cut Line= 3
      2719475.98      6776861.02      2719376.00      6776961.00
      2719326.00      6777011.00
#Sta/Elev= 20
  4863.4  357.63  4866.9  357.63  4891.7  348.60  4905.8  345.08  4919.9  342.42
  4948.2  340.47  4962.4  340.31  4976.5  340.85  4988.7  338.47  4988.9  337.97
  4992.4  337.97  4992.7  338.47  5001.3  339.82  5008.3  339.82  5018.9  345.86
  5033.1  348.57  5047.2  350.25  5061.4  351.18  5072.0  352.44  5075.5  352.44
#Mann=3,-1,0
  4863.4    0.12       0  4988.7    0.07       0  4992.7    0.12       0
Bank Sta=4988.7,4992.7
Exp/Cntr=0.3,0.1

Type RM Length L Ch R = 1,6996,240,240,240
BEGIN DESCRIPTION:
Lynn Creek T1 15.0
END DESCRIPTION:
XS GIS Cut Line= 3
      2719226.00      6776710.99      2719226.00      6776811.00
      2719226.00      6777010.99
#Sta/Elev= 30
  4900.0  357.40  4902.5  357.40  4910.0  354.98  4918.1  353.06  4930.0  349.37
  4940.0  346.68  4950.0  344.58  4960.0  340.05  4970.0  337.59  4980.0  334.53
  4988.0  332.64  4988.3  332.14  4991.8  332.14  4992.0  332.64  4997.5  333.01
  5002.5  333.01  5010.0  335.45  5020.0  338.12  5040.0  338.16  5060.0  338.95
  5070.0  339.91  5090.0  342.71  5110.0  344.93  5120.0  345.78  5130.0  347.43
  5140.0  348.56  5160.0  350.17  5190.0  353.26  5197.5  354.90  5200.0  354.90
#Mann=4,-1,0
  4900.0     0.1       0  4918.1    0.12       0  4988.0    0.07       0
  4992.0    0.12       0
Bank Sta=4988,4992
Exp/Cntr=0.3,0.1

Type RM Length L Ch R = 1,6756,248,248,248
BEGIN DESCRIPTION:
Lynn Creek T1 14.0
END DESCRIPTION:
XS GIS Cut Line= 3
      2719125.98      6776611.02      2719026.00      6776761.00
      2719023.03      6776970.83
#Sta/Elev= 30
  4831.7  363.97  4839.2  364.56  4845.2  363.46  4852.7  363.73  4860.2  362.58
  4867.7  362.60  4875.2  360.68  4881.2  356.94  4903.8  348.93  4926.3  339.59
  4932.3  336.17  4947.3  335.16  4962.4  335.83  4968.4  333.16  4975.9  333.74
  4987.4  331.80  4987.7  331.30  4991.2  331.30  4991.4  331.80  5021.9  332.25
  5031.9  338.22  5052.0  340.14  5062.0  340.23  5072.0  341.37  5112.0  344.50
  5122.0  344.37  5162.0  347.03  5212.0  350.80  5219.4  351.97  5221.8  351.97
#Mann=4,-1,0
  4831.7    0.12       0  4852.7     0.1       0  4987.4    0.07       0
  4991.4     0.1       0
Bank Sta=4987.4,4991.4
Exp/Cntr=0.3,0.1

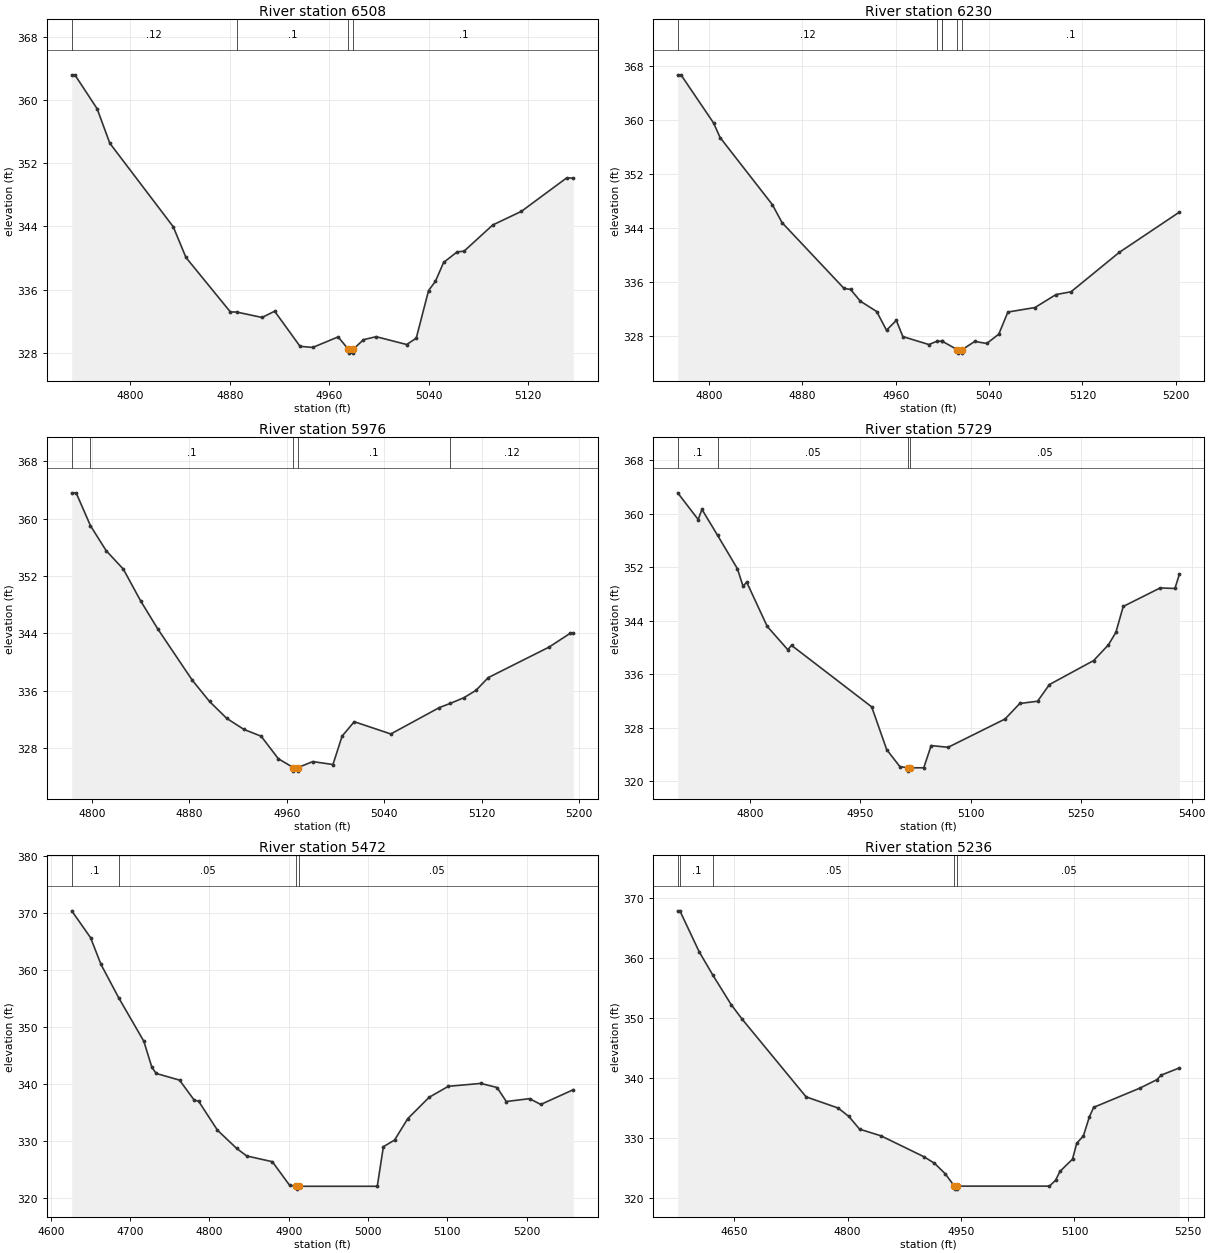
Type RM Length L Ch R = 1,6508,278,278,278
BEGIN DESCRIPTION:
Lynn Creek T1 13.0
END DESCRIPTION:
XS GIS Cut Line= 3
      2718776.00      6776561.02      2718826.00      6776811.00
      2718764.57      6776945.94
#Sta/Elev= 30
  4753.0  363.17  4755.5  363.17  4773.4  358.88  4783.6  354.52  4834.6  343.95
  4844.8  340.07  4880.5  333.18  4885.5  333.17  4906.0  332.48  4916.1  333.27
  4936.5  328.83  4946.7  328.69  4967.1  330.02  4975.3  328.47  4975.6  327.97
  4979.1  327.97  4979.3  328.47  4987.5  329.67  4997.7  330.05  5022.2  329.06
  5029.9  329.86  5039.8  335.88  5045.3  337.05  5051.9  339.44  5062.8  340.78
  5068.3  340.86  5091.4  344.18  5114.4  345.90  5150.7  350.12  5156.2  350.12
#Mann=4,-1,0
  4753.0    0.12       0  4885.5     0.1       0  4975.3    0.07       0
  4979.3     0.1       0
Bank Sta=4975.3,4979.3
Exp/Cntr=0.3,0.1

Type RM Length L Ch R = 1,6230,254,254,254
BEGIN DESCRIPTION:
Lynn Creek T1 12.0
END DESCRIPTION:
XS GIS Cut Line= 3
      2718676.00      6776511.01      2718576.00      6776711.00
      2718626.01      6776911.04
#Sta/Elev= 30
  4773.2  366.66  4776.0  366.66  4803.9  359.54  4809.5  357.38  4854.3  347.44
  4862.6  344.78  4915.7  335.04  4921.3  334.89  4929.7  333.15  4943.7  331.62
  4952.1  328.85  4960.5  330.31  4966.1  327.91  4988.4  326.73  4995.5  327.23
  4999.5  327.23  5000.0  327.21  5012.8  325.96  5013.1  325.46  5016.6  325.46
  5016.8  325.96  5027.7  327.19  5038.0  326.89  5048.3  328.27  5056.1  331.54
  5079.3  332.21  5097.3  334.13  5110.2  334.54  5151.4  340.36  5203.0  346.33
#Mann=6,-1,0
  4773.2    0.12       0  4995.5     0.1       0  4999.5    0.12       0
  5000.0     0.1       0  5012.8    0.07       0  5016.8     0.1       0
Bank Sta=5012.8,5016.8
Exp/Cntr=0.3,0.1

Type RM Length L Ch R = 1,5976,247,247,247
BEGIN DESCRIPTION:
Lynn Creek T1 11.0
END DESCRIPTION:
XS GIS Cut Line= 3
      2718576.01      6776460.99      2718426.00      6776611.00
      2718426.00      6776810.95
#Sta/Elev= 30
  4783.3  363.61  4786.9  363.61  4798.7  359.02  4811.6  355.54  4825.7  352.97
  4839.9  348.54  4854.0  344.63  4882.3  337.49  4896.5  334.52  4910.6  332.17
  4924.7  330.63  4938.9  329.68  4953.0  326.54  4965.2  325.31  4965.4  324.81
  4968.9  324.81  4969.2  325.31  4981.3  326.14  4997.9  325.73  5005.4  329.69
  5015.4  331.70  5045.4  329.99  5085.4  333.68  5094.4  334.26  5105.4  335.04
  5115.4  336.07  5125.4  337.84  5175.4  342.10  5192.9  344.04  5195.4  344.04
#Mann=5,-1,0
  4783.3    0.12       0  4798.7     0.1       0  4965.2    0.07       0
  4969.2     0.1       0  5094.4    0.12       0
Bank Sta=4965.2,4969.2
Exp/Cntr=0.3,0.1

Type RM Length L Ch R = 1,5729,257,257,257
BEGIN DESCRIPTION:
Lynn Creek T1 10.0
END DESCRIPTION:
XS GIS Cut Line= 3
      2718275.99      6776261.05      2718226.00      6776561.00
      2718195.20      6776936.95
#Sta/Elev= 30
  4702.0  363.14  4729.8  359.14  4734.9  360.66  4756.1  356.79  4783.1  351.78
  4790.7  349.17  4795.7  349.77  4823.6  343.15  4851.5  339.67  4856.6  340.32
  4965.5  331.11  4985.8  324.73  5003.6  322.19  5014.1  322.00  5014.4  321.50
  5018.1  322.00  5036.2  322.00  5046.2  325.32  5069.3  325.07  5146.6  329.30
  5166.6  331.62  5190.8  331.96  5206.8  334.45  5267.0  338.05  5287.0  340.40
  5297.1  342.26  5307.1  346.14  5357.3  348.91  5377.3  348.83  5383.3  350.94
#Mann=4,-1,0
  4702.0     0.1       0  4756.1    0.05       0  5014.1    0.05       0
  5018.1    0.05       0
Bank Sta=5014.1,5018.1
Exp/Cntr=0.3,0.1

Type RM Length L Ch R = 1,5472,236,236,236
BEGIN DESCRIPTION:
Lynn Creek T1 9.0
END DESCRIPTION:
XS GIS Cut Line= 3
      2718171.10      6776256.85      2718026.00      6776611.00
      2717971.82      6776854.93
#Sta/Elev= 30
  4626.3  370.41  4650.0  365.70  4663.2  360.99  4685.5  355.13  4717.2  347.49
  4727.4  342.89  4732.8  341.83  4762.2  340.66  4780.8  337.13  4786.2  336.97
  4810.1  331.85  4834.1  328.68  4846.9  327.33  4879.3  326.32  4901.0  322.18
  4909.5  322.00  4909.8  321.50  4913.5  322.00  5011.6  322.00  5019.3  328.96
  5033.4  330.12  5050.0  333.88  5076.9  337.63  5101.2  339.57  5142.2  340.08
  5162.7  339.36  5174.3  336.90  5203.7  337.40  5217.8  336.38  5258.9  338.98
#Mann=4,-1,0
  4626.3     0.1       0  4685.5    0.05       0  4909.5    0.03       0
  4913.5    0.05       0
Bank Sta=4909.5,4913.5
Exp/Cntr=0.3,0.1

Type RM Length L Ch R = 1,5236,236,236,236
BEGIN DESCRIPTION:
Lynn Creek T1 8.0
END DESCRIPTION:
XS GIS Cut Line= 3
      2718125.99      6776211.01      2717826.00      6776511.00
      2717718.71      6776724.40
#Sta/Elev= 30
  4575.5  367.86  4578.4  367.86  4603.8  361.06  4621.9  357.16  4646.2  352.23
  4660.3  349.87  4745.2  336.87  4787.6  335.01  4801.8  333.60  4815.9  331.49
  4844.2  330.38  4900.8  326.91  4914.9  325.81  4929.0  324.08  4941.2  322.00
  4941.4  321.50  4944.9  321.50  4945.2  322.00  5066.9  322.00  5075.1  322.99
  5080.7  324.44  5097.4  326.50  5103.0  329.15  5111.7  330.35  5119.7  333.54
  5125.3  335.12  5186.7  338.34  5209.0  339.74  5214.6  340.49  5238.6  341.69
#Mann=5,-1,0
  4575.5    0.12       0  4578.4     0.1       0  4621.9    0.05       0
  4941.2    0.03       0  4945.2    0.05       0
Bank Sta=4941.2,4945.2
Exp/Cntr=0.3,0.1

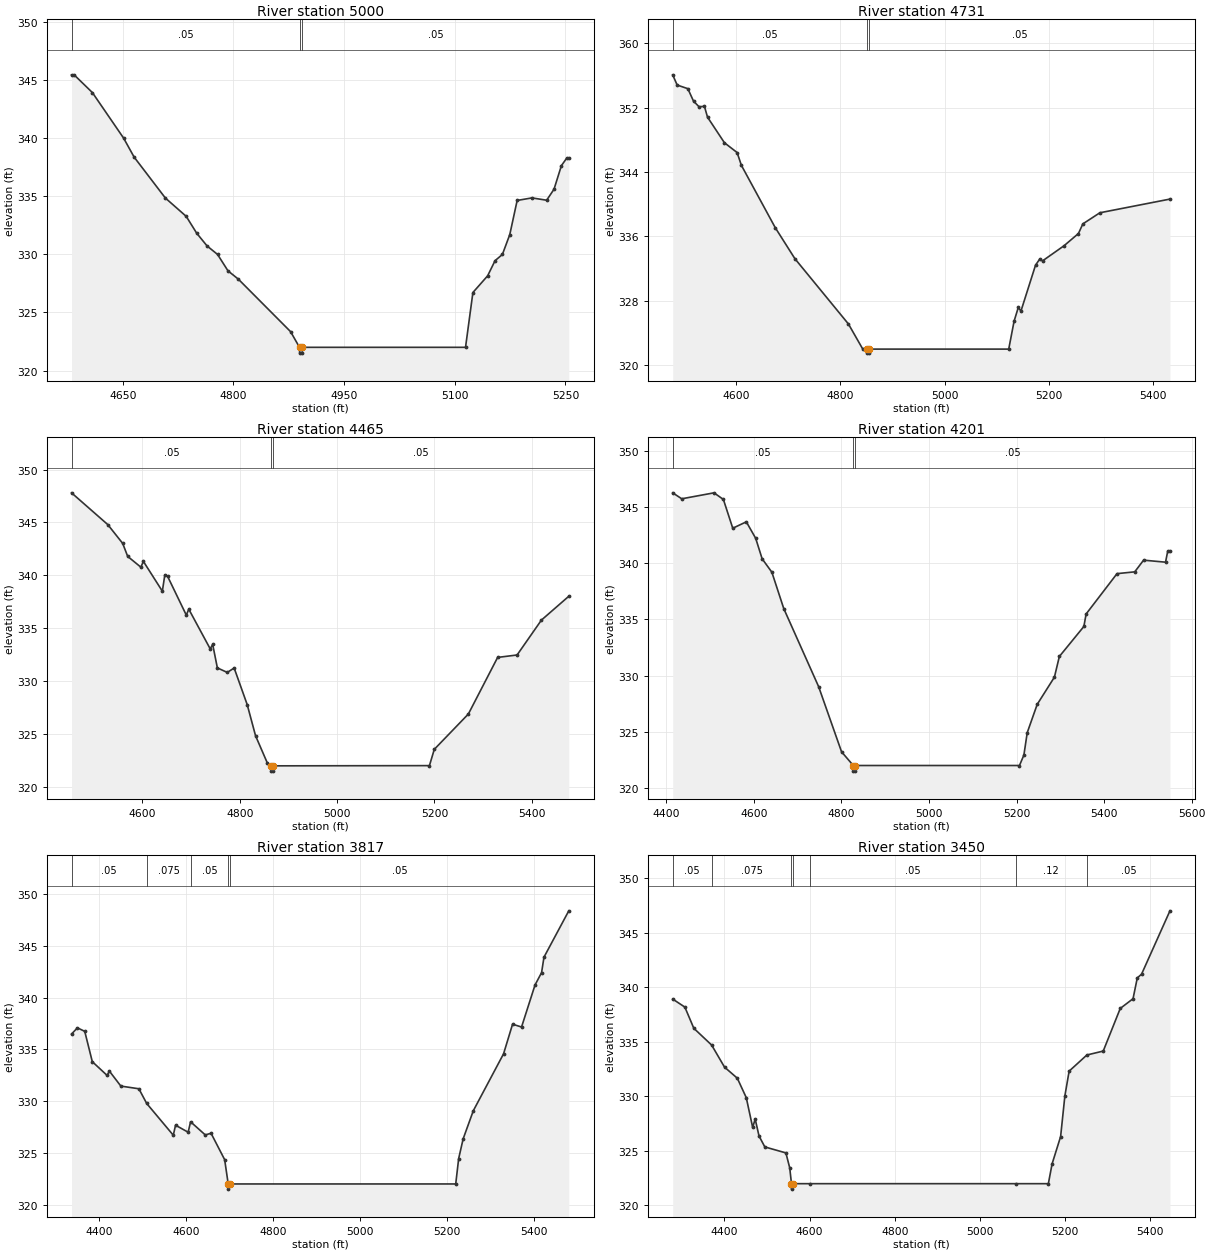
Type RM Length L Ch R = 1,5000,269,269,269
BEGIN DESCRIPTION:
Lynn Creek T1 7.0
END DESCRIPTION:
XS GIS Cut Line= 3
      2717925.98      6776111.02      2717626.00      6776411.00
      2717626.00      6776660.97
#Sta/Elev= 30
  4580.4  345.47  4583.9  345.47  4608.7  343.94  4651.1  340.01  4665.2  338.39
  4707.6  334.86  4735.9  333.28  4750.1  331.83  4764.2  330.73  4778.4  330.00
  4792.5  328.59  4806.6  327.87  4877.4  323.35  4889.5  322.00  4889.7  321.50
  4893.2  321.50  4893.5  322.00  5114.6  322.00  5124.6  326.72  5144.6  328.16
  5154.6  329.46  5164.6  330.00  5174.6  331.71  5184.6  334.65  5204.6  334.87
  5224.6  334.67  5234.6  335.62  5244.6  337.65  5252.1  338.32  5254.6  338.32
#Mann=3,-1,0
  4580.4    0.05       0  4889.5    0.03       0  4893.5    0.05       0
Bank Sta=4889.5,4893.5
Exp/Cntr=0.3,0.1

Type RM Length L Ch R = 1,4731,266,266,266
BEGIN DESCRIPTION:
Lynn Creek T1 6.0
END DESCRIPTION:
XS GIS Cut Line= 3
      2717531.07      6775862.77      2717376.00      6776361.00
      2717271.41      6776781.58
#Sta/Elev= 30
  4477.8  356.08  4486.4  354.81  4506.9  354.36  4517.8  352.81  4528.3  352.12
  4538.8  352.16  4544.7  350.82  4577.2  347.64  4601.6  346.42  4609.7  344.84
  4674.8  337.09  4712.6  333.23  4815.4  325.12  4842.5  322.05  4851.2  322.00
  4851.5  321.50  4855.0  321.50  4855.2  322.00  5123.3  322.00  5133.6  325.47
  5141.7  327.18  5146.8  326.73  5174.8  332.43  5183.0  333.20  5188.2  332.96
  5229.5  334.84  5257.2  336.36  5265.7  337.56  5298.4  338.94  5433.0  340.64
#Mann=3,-1,0
  4477.8    0.05       0  4851.2    0.03       0  4855.2    0.05       0
Bank Sta=4851.2,4855.2
Exp/Cntr=0.3,0.1

Type RM Length L Ch R = 1,4465,264,264,264
BEGIN DESCRIPTION:
Lynn Creek T1 5.0
END DESCRIPTION:
XS GIS Cut Line= 3
      2717241.54      6775778.25      2717126.00      6776311.00
      2717107.91      6776787.13
#Sta/Elev= 30
  4454.5  347.80  4528.9  344.80  4559.6  343.02  4569.9  341.79  4597.0  340.77
  4602.1  341.32  4641.1  338.50  4646.2  340.05  4651.7  339.92  4690.3  336.24
  4695.4  336.80  4739.4  333.05  4744.5  333.47  4754.1  331.25  4774.5  330.82
  4788.6  331.24  4815.4  327.78  4832.6  324.83  4856.4  322.30  4864.6  321.99
  4864.9  321.49  4868.4  321.49  4868.6  321.99  5189.8  322.01  5199.8  323.55
  5269.8  326.89  5329.9  332.24  5369.9  332.47  5419.9  335.77  5476.1  338.02
#Mann=3,-1,0
  4454.5    0.05       0  4864.6    0.03       0  4868.6    0.05       0
Bank Sta=4864.6,4868.6
Exp/Cntr=0.3,0.1

Type RM Length L Ch R = 1,4201,384,384,384
BEGIN DESCRIPTION:
Lynn Creek T1 4.0
END DESCRIPTION:
XS GIS Cut Line= 3
      2717180.26      6775755.99      2716876.00      6776261.00
      2716961.87      6776800.42
#Sta/Elev= 30
  4414.6  346.26  4435.3  345.73  4509.0  346.26  4530.4  345.67  4551.8  343.11
  4582.8  343.68  4604.2  342.21  4618.9  340.39  4641.1  339.20  4668.3  335.96
  4747.9  329.02  4800.3  323.22  4827.1  322.00  4827.3  321.50  4830.8  321.50
  4831.1  322.00  5206.7  322.00  5216.8  322.93  5224.4  324.92  5247.2  327.44
  5286.5  329.86  5297.8  331.70  5353.8  334.37  5358.9  335.48  5429.5  339.07
  5470.0  339.23  5490.2  340.27  5540.3  340.09  5545.4  341.08  5550.4  341.09
#Mann=3,-1,0
  4414.6    0.05       0  4827.1    0.03       0  4831.1    0.05       0
Bank Sta=4827.1,4831.1
Exp/Cntr=0.3,0.1

Type RM Length L Ch R = 1,3817,367,367,367
BEGIN DESCRIPTION:
Lynn Creek T1 3.0
END DESCRIPTION:
XS GIS Cut Line= 3
      2716704.29      6775521.68      2716526.00      6776161.00
      2716405.15      6776626.25
#Sta/Elev= 30
  4336.7  336.49  4350.3  337.09  4367.1  336.75  4384.5  333.82  4418.6  332.49
  4423.8  332.91  4450.2  331.46  4491.7  331.20  4509.7  329.78  4570.9  326.71
  4576.1  327.68  4605.1  327.00  4610.7  328.01  4644.5  326.74  4657.8  326.90
  4689.1  324.35  4697.3  322.00  4697.6  321.50  4701.3  322.00  5220.9  322.00
  5227.7  324.46  5238.0  326.36  5261.4  329.08  5331.0  334.58  5351.7  337.44
  5372.4  337.17  5403.4  341.23  5418.5  342.43  5424.0  343.92  5481.1  348.40
#Mann=5,-1,0
  4336.7    0.05       0  4509.7   0.075       0  4610.7    0.05       0
  4697.3    0.03       0  4701.3    0.05       0
Bank Sta=4697.3,4701.3
Exp/Cntr=0.3,0.1

Type RM Length L Ch R = 1,3450,381,381,381
BEGIN DESCRIPTION:
Lynn Creek T1 2.0
END DESCRIPTION:
XS GIS Cut Line= 3
      2716576.01      6775510.98      2716176.00      6776111.00
      2716190.19      6776557.64
#Sta/Elev= 30
  4278.5  338.93  4307.1  338.19  4328.1  336.25  4370.0  334.71  4400.2  332.69
  4430.3  331.67  4451.3  329.89  4466.3  327.17  4472.3  327.92  4481.3  326.37
  4494.9  325.37  4544.4  324.82  4553.4  323.45  4557.5  322.00  4557.7  321.50
  4561.5  322.00  4601.9  322.00  5083.8  322.00  5160.9  322.00  5169.7  323.82
  5189.7  326.32  5199.7  330.05  5209.7  332.32  5251.4  333.80  5289.8  334.16
  5329.8  338.07  5359.8  338.96  5369.8  340.87  5379.8  341.21  5446.5  347.02
#Mann=7,-1,0
  4278.5    0.05       0  4370.0   0.075       0  4557.5    0.03       0
  4561.5   0.075       0  4601.9    0.05       0  5083.8    0.12       0
  5251.4    0.05       0
Bank Sta=4557.5,4561.5
Exp/Cntr=0.3,0.1

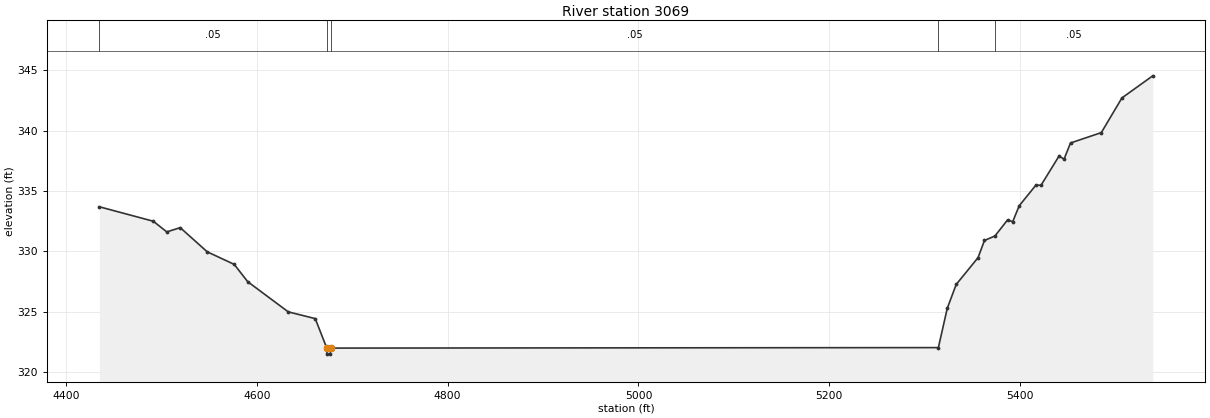
Type RM Length L Ch R = 1,3069,0,0,0
BEGIN DESCRIPTION:
Lynn Creek T1 1.0
END DESCRIPTION:
XS GIS Cut Line= 3
      2716225.99      6775611.01      2715826.00      6776011.00
      2716026.01      6776511.02
#Sta/Elev= 30
  4434.9  333.69  4491.5  332.49  4505.6  331.61  4519.7  331.96  4548.0  329.96
  4576.3  328.92  4590.4  327.49  4632.9  324.99  4661.2  324.43  4673.3  321.99
  4673.5  321.49  4677.0  321.49  4677.3  321.99  5314.4  322.03  5323.7  325.28
  5333.1  327.26  5356.0  329.48  5362.7  330.90  5373.7  331.27  5387.0  332.61
  5392.3  332.45  5399.1  333.77  5416.6  335.48  5422.0  335.47  5440.8  337.88
  5446.2  337.64  5452.9  338.97  5485.2  339.83  5506.8  342.70  5539.1  344.53
#Mann=5,-1,0
  4434.9    0.05       0  4673.3    0.03       0  4677.3    0.05       0
  5314.4    0.12       0  5373.7    0.05       0
Bank Sta=4673.3,4677.3
Exp/Cntr=0.3,0.1

Chan Stop Cuts=-1