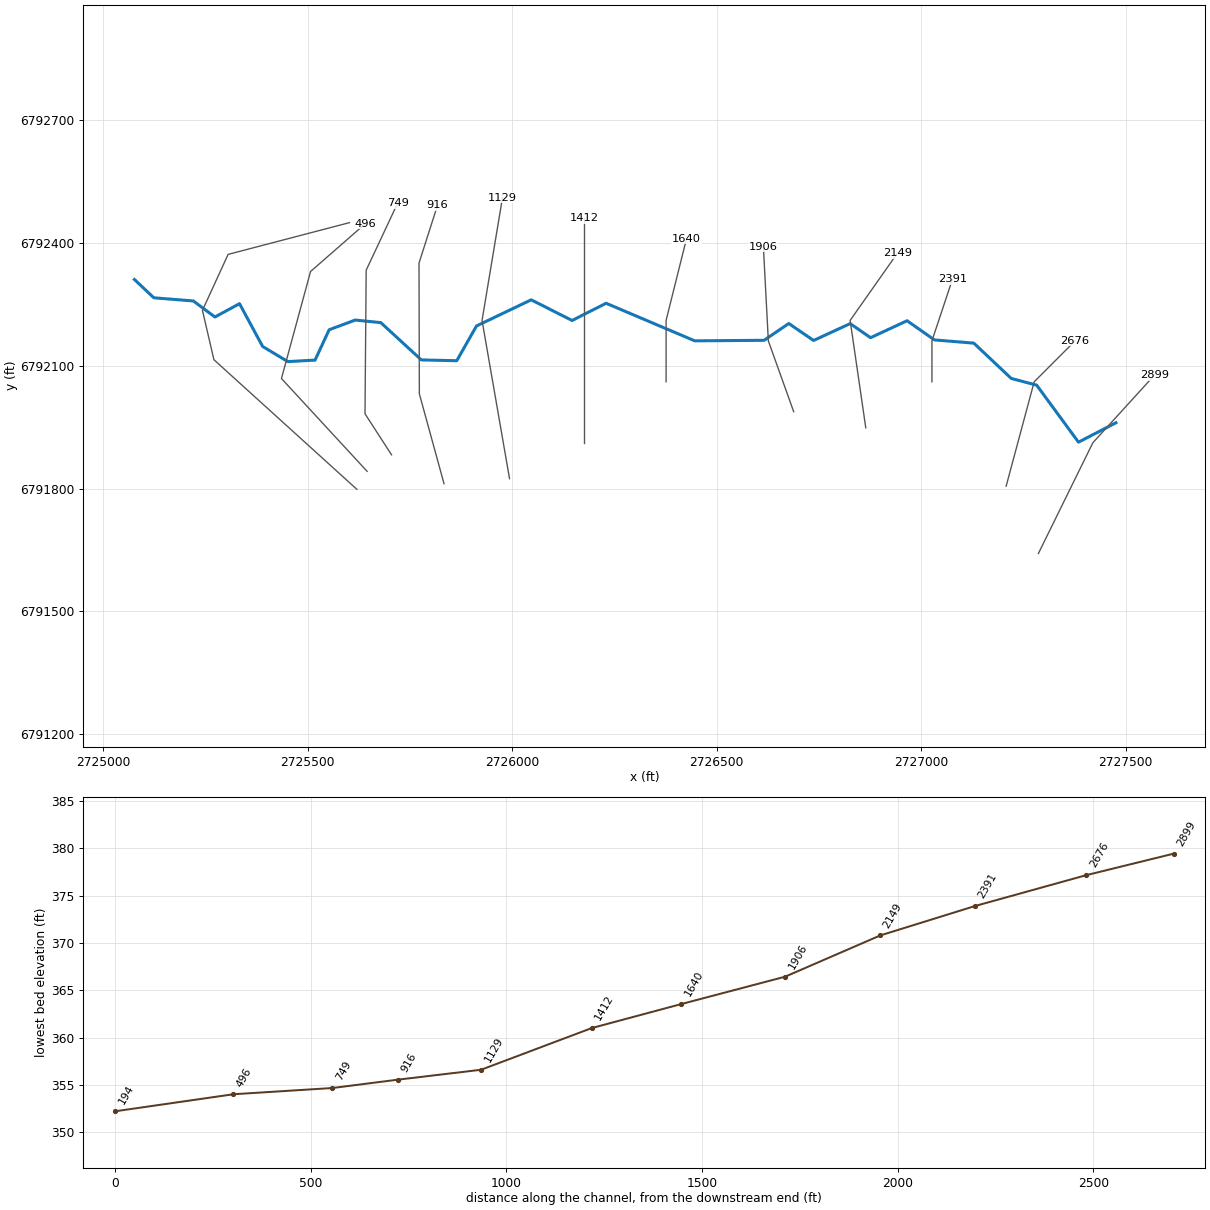
--- Lynn Creek T 10.prj (project) ---

Proj Title=Lynn Creek T 10 Base Level Engineering
Current Plan=p01
Default Exp/Contr=0.3,0.1
English Units
Geom File=g01
Flow File=f01
Plan File=p01
BEGIN DESCRIPTION:
Lynn Creek T 10
END DESCRIPTION:

--- Lynn Creek T 10.p01 (plan) ---

Plan Title=Multiple Run
Short Identifier=Multiple
Geom File=g01
Flow File=f01
Subcritical Flow
K Sum by GR= 0
Std Step Tol= 0.01
Critical Tol= 0.01
Num of Std Step Trials= 20
Max Error Tol= 0.3
Flow Tol Ratio= 0.001
Split Flow NTrial= 30
Split Flow Tol= 0.02
Split Flow Ratio= 0.02
Log Output Level= 0
Friction Slope Method= 1
Unsteady Friction Slope Method= 2
Unsteady Bridges Friction Slope Method= 1
Parabolic Critical Depth
Global Vel Dist=  1 , 1 , 1
Global Log Level= 0
CheckData=True
Encroach Param= -1, 0, 0, 0
BEGIN DESCRIPTION:
Multiple Run
END DESCRIPTION:

--- Lynn Creek T 10.f01 (steady flow) ---

Flow Title=Multiple
Number of Profiles=7
Profile Names=10-year,25-year,50-year,1pct_min,100-year,1pct_plu,500-year
River Rch & RM= Lynn Creek T 10,Reach-1,2899
     202     253     291     168     334     667     438
Boundary for River Rch & Prof#=Lynn Creek T 10,Reach-1,1
Up Type=0
Dn Type=3
Dn Slope=0.005
Boundary for River Rch & Prof#=Lynn Creek T 10,Reach-1,2
Up Type=0
Dn Type=3
Dn Slope=0.005
Boundary for River Rch & Prof#=Lynn Creek T 10,Reach-1,3
Up Type=0
Dn Type=3
Dn Slope=0.005
Boundary for River Rch & Prof#=Lynn Creek T 10,Reach-1,4
Up Type=0
Dn Type=3
Dn Slope=0.005
Boundary for River Rch & Prof#=Lynn Creek T 10,Reach-1,5
Up Type=0
Dn Type=3
Dn Slope=0.005
Boundary for River Rch & Prof#=Lynn Creek T 10,Reach-1,6
Up Type=0
Dn Type=3
Dn Slope=0.005
Boundary for River Rch & Prof#=Lynn Creek T 10,Reach-1,7
Up Type=0
Dn Type=3
Dn Slope=0.005

--- Lynn Creek T 10.g01 (geometry) ---

Geom Title=Existing Conditions

River Reach=Lynn Creek T 10,Reach-1
Reach XY= 30
      2727476.00      6791961.00      2727384.35      6791913.52
      2727282.07      6792052.85      2727219.96      6792069.18
      2727128.42      6792155.46      2727031.97      6792163.38
      2726965.29      6792210.19      2726875.92      6792168.82
      2726826.08      6792203.18      2726736.64      6792161.98
      2726676.01      6792203.41      2726615.56      6792162.38
      2726446.03      6792161.07      2726229.29      6792252.90
      2726146.20      6792210.80      2726046.18      6792261.29
      2725912.46      6792197.45      2725864.12      6792112.52
      2725777.57      6792114.44      2725678.42      6792205.59
      2725615.89      6792211.86      2725552.16      6792188.18
      2725517.65      6792114.00      2725451.07      6792110.38
      2725389.47      6792147.38      2725332.95      6792251.82
      2725272.79      6792219.29      2725220.12      6792258.49
      2725123.45      6792266.22      2725076.00      6792311.00

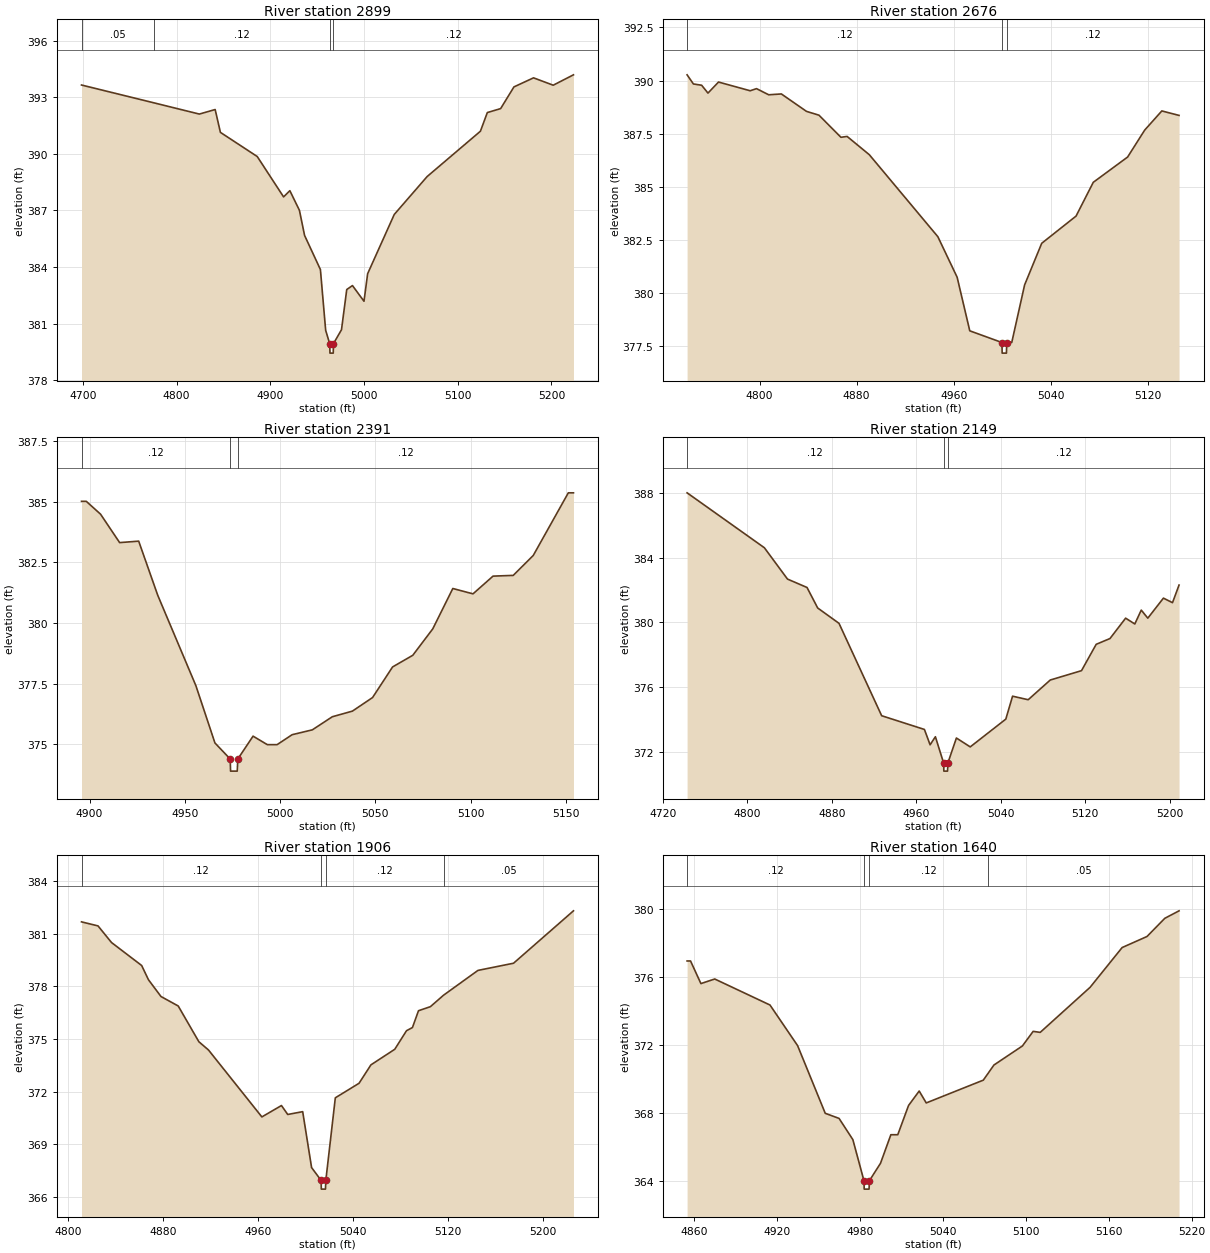
Type RM Length L Ch R = 1,2899,223,223,223
BEGIN DESCRIPTION:
Lynn Creek T 10 9.0
END DESCRIPTION:
XS GIS Cut Line= 3
      2727286.31      6791641.58      2727419.40      6791912.00
      2727569.99      6792077.16
#Sta/Elev= 30
  4698.6  393.65  4776.3  392.70  4824.3  392.11  4841.2  392.35  4846.8  391.14
  4886.1  389.86  4914.2  387.72  4920.9  388.05  4931.1  387.01  4936.6  385.68
  4953.5  383.87  4959.1  380.65  4963.4  379.94  4963.7  379.44  4967.2  379.44
  4967.4  379.94  4976.0  380.68  4981.6  382.81  4987.7  383.02  5000.0  382.19
  5003.9  383.65  5032.3  386.79  5067.4  388.80  5124.2  391.20  5131.6  392.19
  5145.8  392.40  5160.0  393.55  5180.9  394.03  5201.9  393.64  5223.5  394.19
#Mann=4,-1,0
  4698.6    0.05       0  4776.3    0.12       0  4963.4    0.07       0
  4967.4    0.12       0
Bank Sta=4963.4,4967.4
Exp/Cntr=0.3,0.1

Type RM Length L Ch R = 1,2676,285,285,285
BEGIN DESCRIPTION:
Lynn Creek T 10 8.0
END DESCRIPTION:
XS GIS Cut Line= 3
      2727207.43      6791806.00      2727276.00      6792061.00
      2727376.01      6792161.01
#Sta/Elev= 30
  4740.3  390.27  4745.5  389.84  4752.3  389.78  4757.5  389.41  4766.2  389.93
  4792.3  389.52  4797.5  389.62  4807.6  389.33  4818.0  389.37  4838.7  388.55
  4849.0  388.37  4867.1  387.33  4872.2  387.37  4890.5  386.51  4947.0  382.65
  4962.9  380.74  4973.3  378.22  4999.8  377.67  5000.0  377.17  5003.5  377.17
  5003.8  377.67  5007.9  377.67  5018.5  380.38  5032.6  382.34  5060.9  383.62
  5075.1  385.21  5103.4  386.40  5117.5  387.67  5131.6  388.57  5145.8  388.36
#Mann=3,-1,0
  4740.3    0.12       0  4999.8    0.07       0  5003.8    0.12       0
Bank Sta=4999.8,5003.8
Exp/Cntr=0.3,0.1

Type RM Length L Ch R = 1,2391,242,242,242
BEGIN DESCRIPTION:
Lynn Creek T 10 7.0
END DESCRIPTION:
XS GIS Cut Line= 3
      2727026.00      6792061.03      2727026.00      6792161.00
      2727076.01      6792311.02
#Sta/Elev= 30
  4895.8  385.01  4898.3  385.01  4905.8  384.48  4915.8  383.31  4925.8  383.37
  4935.8  381.14  4955.8  377.42  4965.8  375.06  4973.8  374.40  4974.0  373.90
  4977.5  373.90  4977.8  374.40  4985.8  375.34  4993.3  374.99  4998.4  374.99
  5006.3  375.40  5016.9  375.60  5027.4  376.14  5037.9  376.37  5048.5  376.93
  5059.0  378.19  5069.6  378.67  5080.1  379.76  5090.6  381.42  5101.2  381.20
  5111.7  381.93  5122.3  381.96  5132.8  382.78  5151.2  385.36  5153.9  385.36
#Mann=3,-1,0
  4895.8    0.12       0  4973.8    0.07       0  4977.8    0.12       0
Bank Sta=4973.8,4977.8
Exp/Cntr=0.3,0.1

Type RM Length L Ch R = 1,2149,243,243,243
BEGIN DESCRIPTION:
Lynn Creek T 10 6.0
END DESCRIPTION:
XS GIS Cut Line= 3
      2726864.24      6791948.58      2726826.00      6792211.00
      2726941.61      6792375.20
#Sta/Elev= 30
  4742.9  388.02  4816.1  384.62  4838.0  382.68  4856.5  382.16  4866.6  380.89
  4886.8  379.94  4927.2  374.22  4967.7  373.37  4973.1  372.42  4978.1  372.92
  4985.9  371.29  4986.1  370.79  4989.6  370.79  4989.9  371.29  4998.0  372.84
  5011.1  372.29  5044.8  374.01  5051.2  375.43  5066.0  375.21  5086.9  376.43
  5116.5  377.01  5130.4  378.64  5143.5  379.00  5158.3  380.26  5167.0  379.90
  5173.1  380.76  5179.3  380.26  5194.1  381.50  5202.7  381.22  5208.9  382.31
#Mann=3,-1,0
  4742.9    0.12       0  4985.9    0.07       0  4989.9    0.12       0
Bank Sta=4985.9,4989.9
Exp/Cntr=0.3,0.1

Type RM Length L Ch R = 1,1906,266,266,266
BEGIN DESCRIPTION:
Lynn Creek T 10 5.0
END DESCRIPTION:
XS GIS Cut Line= 3
      2726688.00      6791987.92      2726626.00      6792161.00
      2726613.85      6792391.43
#Sta/Elev= 30
  4811.5  381.68  4825.4  381.45  4836.8  380.50  4862.2  379.19  4867.9  378.38
  4878.5  377.42  4893.0  376.88  4910.4  374.84  4918.5  374.37  4963.5  370.55
  4980.0  371.20  4985.3  370.69  4997.9  370.85  5005.4  367.66  5013.4  366.93
  5013.6  366.43  5017.1  366.43  5017.4  366.93  5025.4  371.64  5045.4  372.47
  5055.4  373.52  5075.5  374.41  5085.4  375.47  5090.4  375.65  5095.5  376.61
  5105.5  376.84  5116.7  377.50  5145.6  378.91  5175.6  379.32  5226.1  382.31
#Mann=4,-1,0
  4811.5    0.12       0  5013.4    0.07       0  5017.4    0.12       0
  5116.7    0.05       0
Bank Sta=5013.4,5017.4
Exp/Cntr=0.3,0.1

Type RM Length L Ch R = 1,1640,228,228,228
BEGIN DESCRIPTION:
Lynn Creek T 10 4.0
END DESCRIPTION:
XS GIS Cut Line= 3
      2726376.00      6792061.05      2726376.00      6792211.00
      2726426.00      6792410.99
#Sta/Elev= 30
  4854.7  376.95  4857.2  376.95  4864.7  375.62  4874.7  375.89  4914.7  374.36
  4934.7  371.97  4954.7  367.99  4964.7  367.69  4974.7  366.44  4982.7  364.03
  4982.9  363.53  4986.4  363.53  4986.7  364.03  4994.7  365.05  5002.2  366.73
  5007.2  366.73  5015.0  368.45  5022.7  369.30  5027.8  368.60  5069.1  369.94
  5072.4  370.32  5076.8  370.83  5097.4  371.95  5105.2  372.81  5110.3  372.75
  5146.4  375.40  5169.6  377.74  5187.6  378.39  5200.5  379.46  5210.8  379.90
#Mann=4,-1,0
  4854.7    0.12       0  4982.7    0.07       0  4986.7    0.12       0
  5072.4    0.05       0
Bank Sta=4982.7,4986.7
Exp/Cntr=0.3,0.1

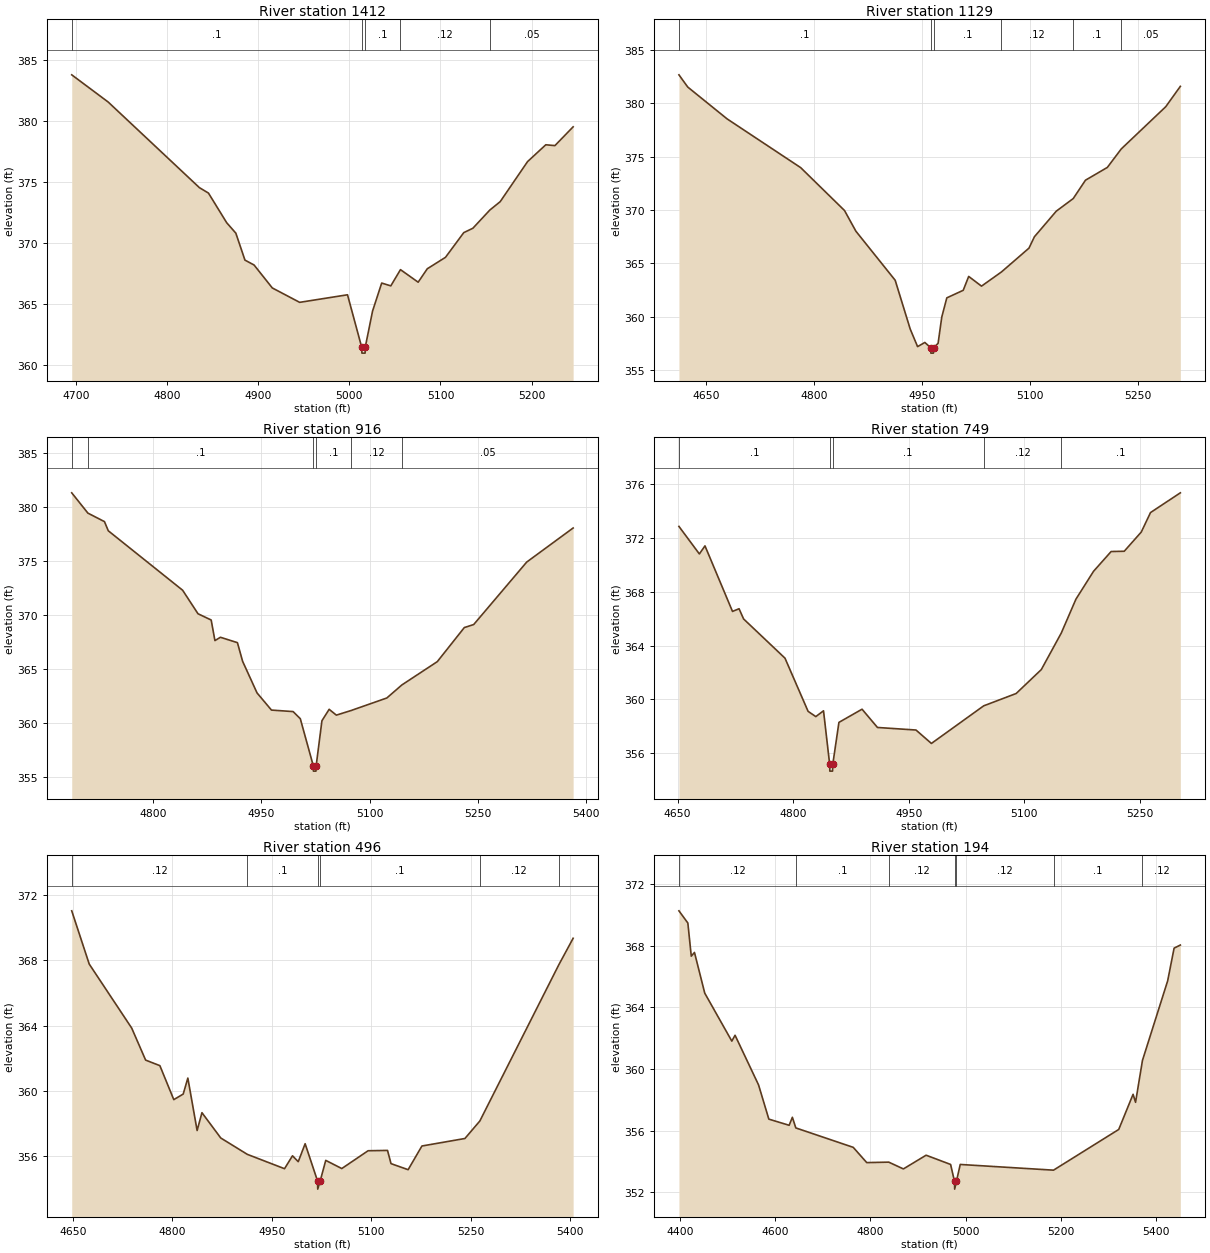
Type RM Length L Ch R = 1,1412,283,283,283
BEGIN DESCRIPTION:
Lynn Creek T 10 3.0
END DESCRIPTION:
XS GIS Cut Line= 3
      2726176.00      6791910.96      2726176.00      6792211.00
      2726176.00      6792460.96
#Sta/Elev= 30
  4695.5  383.80  4735.5  381.57  4835.5  374.56  4845.5  374.11  4865.5  371.68
  4875.5  370.83  4885.5  368.62  4895.5  368.22  4915.5  366.34  4945.5  365.16
  4998.0  365.78  5013.5  361.50  5013.8  361.00  5017.3  361.00  5017.5  361.50
  5025.5  364.45  5035.5  366.74  5045.5  366.51  5056.1  367.84  5075.5  366.81
  5085.5  367.91  5105.5  368.85  5125.5  370.87  5135.5  371.23  5154.1  372.72
  5165.5  373.41  5195.5  376.69  5215.5  378.07  5225.5  378.00  5245.5  379.54
#Mann=5,-1,0
  4695.5     0.1       0  5013.5    0.07       0  5017.5     0.1       0
  5056.1    0.12       0  5154.1    0.05       0
Bank Sta=5013.5,5017.5
Exp/Cntr=0.3,0.1

Type RM Length L Ch R = 1,1129,213,213,213
BEGIN DESCRIPTION:
Lynn Creek T 10 2.0
END DESCRIPTION:
XS GIS Cut Line= 3
      2725993.19      6791824.42      2725926.00      6792211.00
      2725976.00      6792510.98
#Sta/Elev= 30
  4611.9  382.68  4624.2  381.53  4678.8  378.55  4781.0  373.98  4841.9  369.96
  4857.7  368.02  4912.3  363.42  4933.2  358.84  4943.4  357.20  4953.5  357.59
  4961.7  357.09  4961.9  356.59  4965.4  356.59  4965.7  357.09  4971.9  357.51
  4977.0  359.97  4984.0  361.77  5006.8  362.48  5014.4  363.78  5032.2  362.87
  5059.9  364.20  5098.1  366.43  5105.7  367.50  5136.1  369.90  5159.6  371.08
  5176.6  372.80  5207.0  374.00  5226.3  375.73  5288.1  379.69  5308.4  381.60
#Mann=6,-1,0
  4611.9     0.1       0  4961.7    0.07       0  4965.7     0.1       0
  5059.9    0.12       0  5159.6     0.1       0  5226.3    0.05       0
Bank Sta=4961.7,4965.7
Exp/Cntr=0.3,0.1

Type RM Length L Ch R = 1,916,167,167,167
BEGIN DESCRIPTION:
Mapping XS 52627af9
END DESCRIPTION:
XS GIS Cut Line= 4
      2725832.99      6791812.16      2725772.70      6792031.57
      2725771.86      6792351.06      2725817.10      6792492.36
#Sta/Elev= 30
  4686.9  381.34  4709.3  379.46  4732.3  378.67  4737.6  377.82  4840.7  372.31
  4862.0  370.13  4880.3  369.55  4885.5  367.64  4893.1  367.95  4916.7  367.45
  4923.9  365.72  4943.9  362.79  4963.9  361.20  4993.9  361.06  5003.9  360.40
  5021.9  356.04  5022.1  355.54  5025.6  355.54  5025.9  356.04  5033.9  360.21
  5043.9  361.27  5053.9  360.73  5074.4  361.16  5123.9  362.32  5144.8  363.53
  5193.9  365.69  5231.4  368.85  5244.4  369.13  5317.9  374.92  5382.3  378.08
#Mann=6,-1,0
  4686.9    0.12       0  4709.3     0.1       0  5021.9    0.07       0
  5025.9     0.1       0  5074.4    0.12       0  5144.8    0.05       0
Bank Sta=5021.9,5025.9
Exp/Cntr=0.3,0.1

Type RM Length L Ch R = 1,749,253,253,253
BEGIN DESCRIPTION:
Mapping XS 0ca0ec23
END DESCRIPTION:
XS GIS Cut Line= 4
      2725704.71      6791882.61      2725639.82      6791982.87
      2725642.68      6792333.63      2725719.37      6792496.93
#Sta/Elev= 30
  4651.7  372.88  4678.2  370.83  4685.5  371.43  4721.2  366.55  4729.7  366.75
  4735.6  365.99  4789.3  363.07  4819.3  359.11  4829.3  358.72  4839.3  359.15
  4847.3  355.16  4847.5  354.66  4851.0  354.66  4851.3  355.16  4859.3  358.29
  4889.3  359.27  4909.3  357.91  4959.3  357.72  4979.3  356.72  5047.1  359.52
  5089.3  360.44  5121.9  362.22  5147.8  364.94  5166.8  367.46  5189.7  369.54
  5212.5  371.01  5229.5  371.03  5251.6  372.46  5263.6  373.91  5302.3  375.38
#Mann=5,-1,0
  4651.7     0.1       0  4847.3    0.07       0  4851.3     0.1       0
  5047.1    0.12       0  5147.8     0.1       0
Bank Sta=4847.3,4851.3
Exp/Cntr=0.3,0.1

Type RM Length L Ch R = 1,496,302,302,302
BEGIN DESCRIPTION:
Mapping XS 8d71d7a3
END DESCRIPTION:
XS GIS Cut Line= 4
      2725644.96      6791842.27      2725435.52      6792069.03
      2725506.66      6792330.45      2725640.05      6792446.78
#Sta/Elev= 30
  4648.2  371.04  4674.6  367.78  4738.7  363.86  4759.7  361.90  4781.2  361.56
  4802.2  359.48  4816.4  359.82  4823.4  360.80  4837.4  357.59  4844.7  358.68
  4873.1  357.13  4913.1  356.13  4969.3  355.25  4981.3  356.04  4990.0  355.68
  5000.4  356.78  5019.1  354.50  5019.4  354.00  5023.1  354.50  5031.5  355.76
  5055.7  355.26  5095.4  356.35  5124.7  356.37  5130.0  355.56  5155.8  355.19
  5176.6  356.64  5241.5  357.10  5264.0  358.17  5383.1  367.73  5404.8  369.36
#Mann=6,-1,0
  4648.2    0.12       0  4913.1     0.1       0  5019.1    0.07       0
  5023.1     0.1       0  5264.0    0.12       0  5383.1     0.1       0
Bank Sta=5019.1,5023.1
Exp/Cntr=0.3,0.1

Type RM Length L Ch R = 1,194,0,0,0
BEGIN DESCRIPTION:
Lynn Creek T 10 1.0
END DESCRIPTION:
XS GIS Cut Line= 5
      2725619.87      6791798.38      2725270.40      6792114.97
      2725242.31      6792235.51      2725305.12      6792372.27
      2725601.73      6792449.83
#Sta/Elev= 30
  4398.1  370.25  4416.8  369.46  4424.0  367.31  4430.7  367.55  4452.3  364.91
  4509.1  361.80  4515.9  362.18  4565.2  358.96  4586.8  356.74  4629.4  356.34
  4636.2  356.86  4643.4  356.17  4763.9  354.91  4792.3  353.92  4838.5  353.95
  4869.2  353.51  4916.9  354.40  4968.3  353.80  4976.5  352.70  4976.8  352.20
  4980.5  352.70  4988.5  353.80  5184.3  353.43  5321.2  356.07  5351.3  358.35
  5356.5  357.83  5371.0  360.55  5423.9  365.71  5437.4  367.83  5450.5  368.03
#Mann=7,-1,0
  4398.1    0.12       0  4643.4     0.1       0  4838.5    0.12       0
  4976.5    0.07       0  4980.5    0.12       0  5184.3     0.1       0
  5371.0    0.12       0
Bank Sta=4976.5,4980.5
Exp/Cntr=0.3,0.1

Chan Stop Cuts=-1