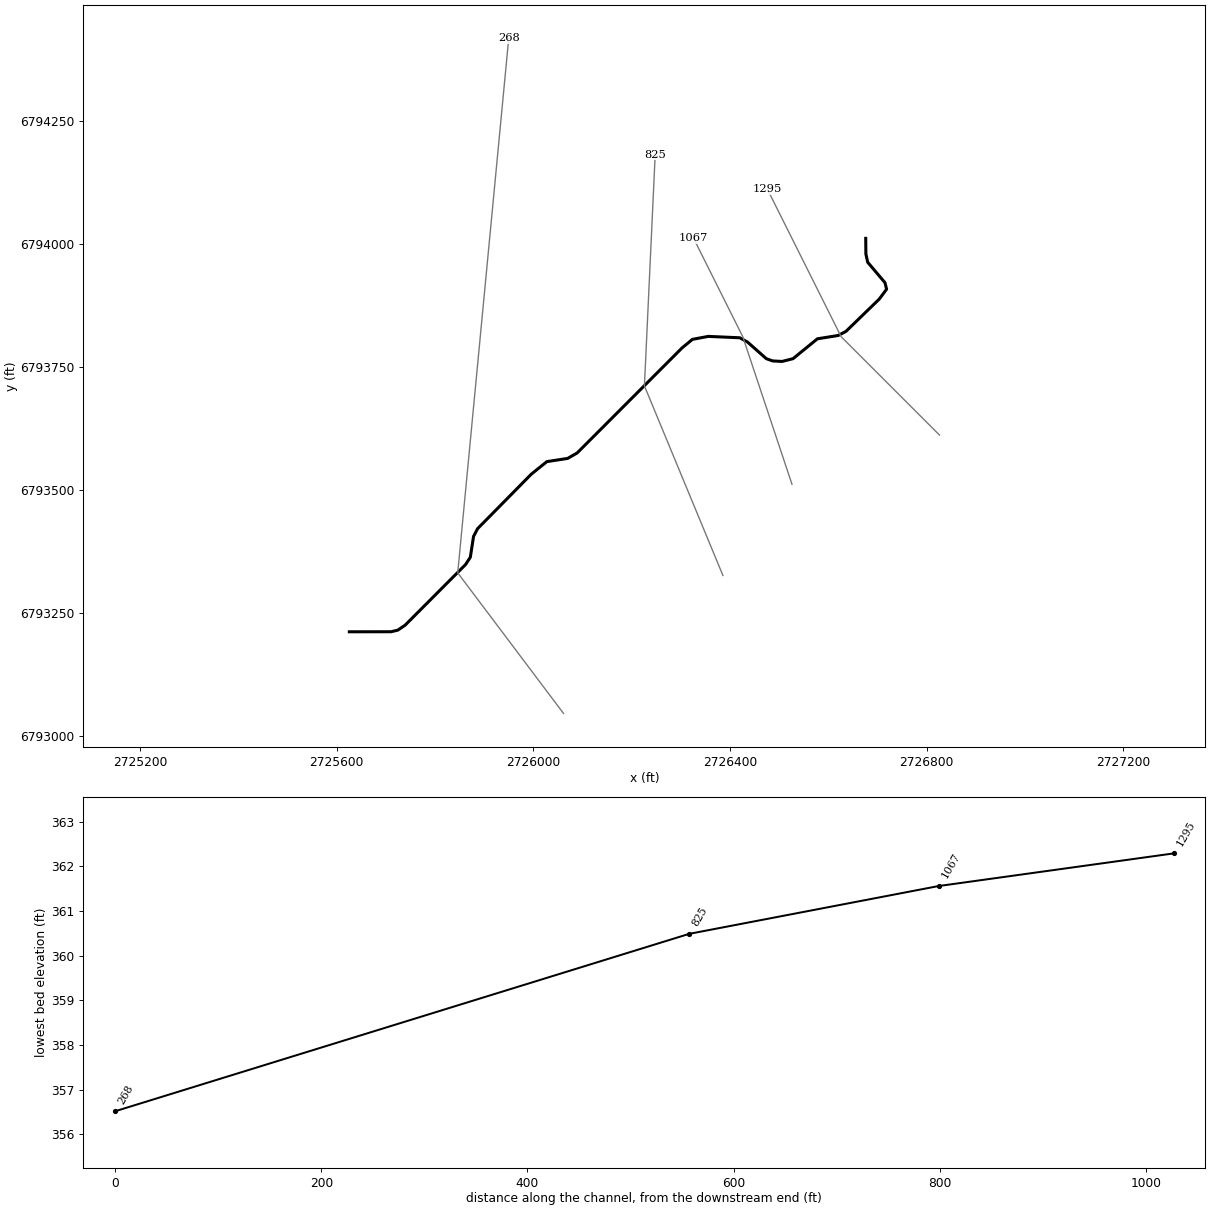
--- Lynn Creek T 11.prj (project) ---

Proj Title=Lynn Creek T 11 Base Level Engineering
Current Plan=p01
Default Exp/Contr=0.3,0.1
English Units
Geom File=g01
Flow File=f01
Plan File=p01
BEGIN DESCRIPTION:
Lynn Creek T 11
END DESCRIPTION:

--- Lynn Creek T 11.p01 (plan) ---

Plan Title=Multiple Run
Short Identifier=Multiple
Geom File=g01
Flow File=f01
Subcritical Flow
K Sum by GR= 0
Std Step Tol= 0.01
Critical Tol= 0.01
Num of Std Step Trials= 20
Max Error Tol= 0.3
Flow Tol Ratio= 0.001
Split Flow NTrial= 30
Split Flow Tol= 0.02
Split Flow Ratio= 0.02
Log Output Level= 0
Friction Slope Method= 1
Unsteady Friction Slope Method= 2
Unsteady Bridges Friction Slope Method= 1
Parabolic Critical Depth
Global Vel Dist=  1 , 1 , 1
Global Log Level= 0
CheckData=True
Encroach Param= -1, 0, 0, 0
BEGIN DESCRIPTION:
Multiple Run
END DESCRIPTION:

--- Lynn Creek T 11.f01 (steady flow) ---

Flow Title=Multiple
Number of Profiles=7
Profile Names=10-year,25-year,50-year,1pct_min,100-year,1pct_plu,500-year
River Rch & RM= Lynn Creek T 11,Reach-1,1295
     361     469     553     325     648    1292     886
Boundary for River Rch & Prof#=Lynn Creek T 11,Reach-1,1
Up Type=0
Dn Type=3
Dn Slope=0.005
Boundary for River Rch & Prof#=Lynn Creek T 11,Reach-1,2
Up Type=0
Dn Type=3
Dn Slope=0.005
Boundary for River Rch & Prof#=Lynn Creek T 11,Reach-1,3
Up Type=0
Dn Type=3
Dn Slope=0.005
Boundary for River Rch & Prof#=Lynn Creek T 11,Reach-1,4
Up Type=0
Dn Type=3
Dn Slope=0.005
Boundary for River Rch & Prof#=Lynn Creek T 11,Reach-1,5
Up Type=0
Dn Type=3
Dn Slope=0.005
Boundary for River Rch & Prof#=Lynn Creek T 11,Reach-1,6
Up Type=0
Dn Type=3
Dn Slope=0.005
Boundary for River Rch & Prof#=Lynn Creek T 11,Reach-1,7
Up Type=0
Dn Type=3
Dn Slope=0.005

--- Lynn Creek T 11.g01 (geometry) ---

Geom Title=Existing Conditions

River Reach=Lynn Creek T 11,Reach-1
Reach XY= 30
      2726676.00      6794011.00      2726676.32      6793979.12
      2726680.02      6793962.36      2726715.12      6793920.89
      2726718.42      6793907.59      2726703.58      6793887.60
      2726635.73      6793821.76      2726619.98      6793813.49
      2726577.74      6793806.75      2726528.20      6793766.34
      2726505.83      6793760.71      2726486.69      6793761.77
      2726473.82      6793766.38      2726435.65      6793800.13
      2726420.03      6793808.81      2726355.92      6793811.67
      2726323.57      6793805.60      2726302.48      6793788.16
      2726089.21      6793574.63      2726069.95      6793563.53
      2726027.65      6793557.02      2725995.84      6793531.39
      2725886.78      6793420.68      2725878.53      6793404.95
      2725872.02      6793362.65      2725862.37      6793347.79
      2725739.33      6793224.35      2725724.60      6793214.38
      2725710.95      6793211.12      2725626.00      6793211.00

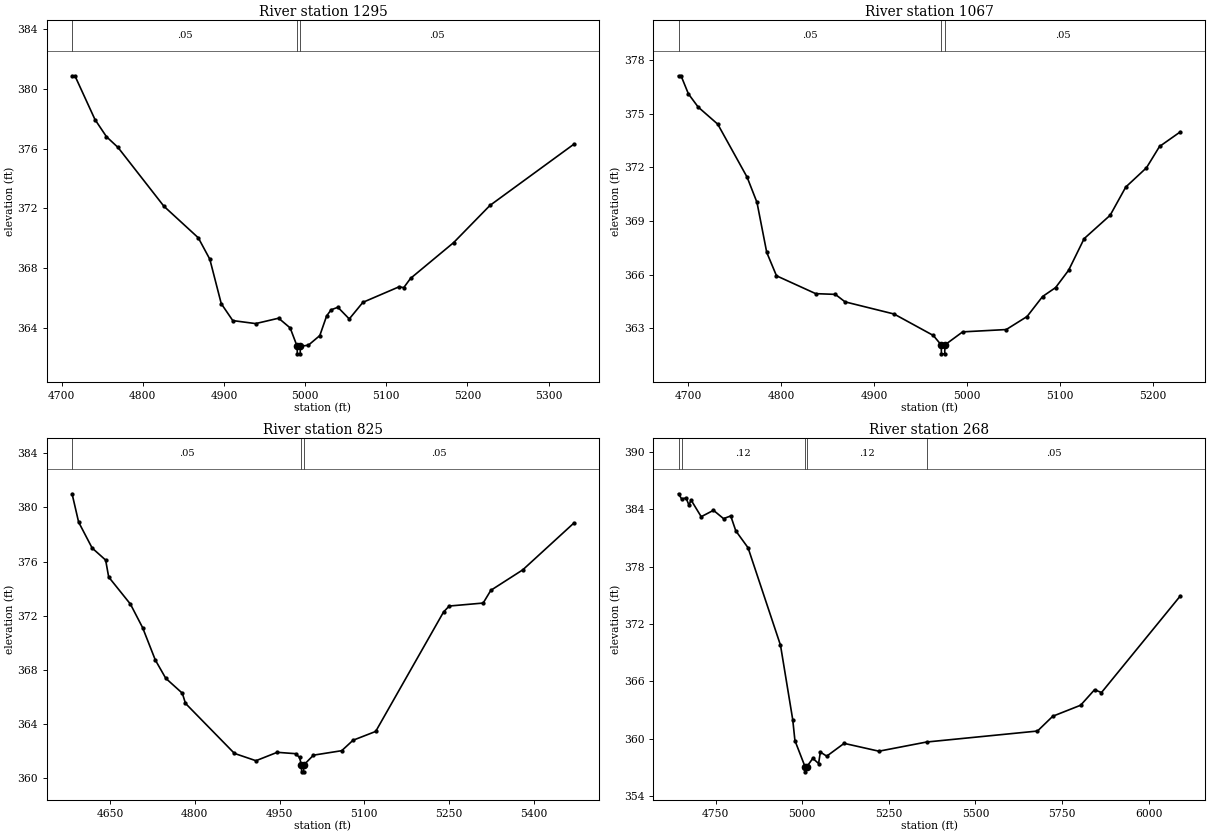
Type RM Length L Ch R = 1,1295,228,228,228
BEGIN DESCRIPTION:
Lynn Creek T 11 4.0
END DESCRIPTION:
XS GIS Cut Line= 3
      2726825.98      6793611.02      2726626.00      6793811.00
      2726476.01      6794110.98
#Sta/Elev= 30
  4712.9  380.86  4716.4  380.86  4741.1  377.94  4755.3  376.79  4769.4  376.08
  4826.0  372.15  4868.4  370.04  4882.6  368.61  4896.7  365.64  4910.9  364.51
  4939.1  364.31  4967.4  364.67  4981.6  364.02  4990.2  362.79  4990.4  362.29
  4993.9  362.29  4994.2  362.79  5004.1  362.87  5018.1  363.51  5026.5  364.82
  5032.0  365.23  5040.4  365.40  5054.4  364.62  5071.2  365.73  5115.9  366.77
  5121.5  366.71  5129.9  367.33  5183.0  369.72  5227.7  372.20  5331.1  376.29
#Mann=3,-1,0
  4712.9    0.05       0  4990.2    0.04       0  4994.2    0.05       0
Bank Sta=4990.2,4994.2
Exp/Cntr=0.3,0.1

Type RM Length L Ch R = 1,1067,242,242,242
BEGIN DESCRIPTION:
Lynn Creek T 11 3.0
END DESCRIPTION:
XS GIS Cut Line= 3
      2726526.01      6793510.97      2726426.00      6793811.00
      2726325.99      6794011.03
#Sta/Elev= 30
  4689.5  377.13  4692.2  377.13  4700.1  376.12  4710.6  375.38  4731.7  374.42
  4763.3  371.45  4773.9  370.04  4784.4  367.24  4794.9  365.93  4837.1  364.93
  4858.2  364.89  4868.7  364.47  4921.4  363.79  4963.6  362.59  4972.1  362.06
  4972.4  361.56  4975.9  361.56  4976.1  362.06  4995.2  362.79  5042.1  362.92
  5064.5  363.65  5081.2  364.77  5095.2  365.27  5109.2  366.24  5125.9  368.01
  5153.9  369.32  5170.7  370.90  5193.0  371.98  5207.0  373.17  5229.4  373.99
#Mann=3,-1,0
  4689.5    0.05       0  4972.1    0.04       0  4976.1    0.05       0
Bank Sta=4972.1,4976.1
Exp/Cntr=0.3,0.1

Type RM Length L Ch R = 1,825,557,557,557
BEGIN DESCRIPTION:
Lynn Creek T 11 2.0
END DESCRIPTION:
XS GIS Cut Line= 3
      2726385.57      6793325.58      2726226.00      6793711.00
      2726247.90      6794181.34
#Sta/Elev= 30
  4582.8  381.00  4594.4  378.91  4618.3  377.00  4642.2  376.11  4647.6  374.86
  4686.1  372.86  4707.7  371.12  4730.1  368.74  4748.6  367.39  4777.9  366.29
  4783.5  365.54  4870.1  361.85  4908.2  361.31  4945.8  361.93  4978.3  361.83
  4985.3  361.55  4988.7  360.99  4989.0  360.49  4992.5  360.49  4992.7  360.99
  5010.0  361.72  5060.0  362.05  5080.0  362.82  5120.1  363.47  5240.2  372.28
  5250.2  372.72  5310.3  372.94  5323.9  373.88  5380.4  375.39  5470.8  378.84
#Mann=3,-1,0
  4582.8    0.05       0  4988.7    0.04       0  4992.7    0.05       0
Bank Sta=4988.7,4992.7
Exp/Cntr=0.3,0.1

Type RM Length L Ch R = 1,268,0,0,0
BEGIN DESCRIPTION:
Lynn Creek T 11 1.0
END DESCRIPTION:
XS GIS Cut Line= 3
      2726061.41      6793045.11      2725846.39      6793330.84
      2725950.09      6794417.70
#Sta/Elev= 30
  4642.4  385.62  4651.3  385.08  4664.1  385.18  4672.4  384.44  4678.7  384.96
  4707.9  383.22  4743.3  383.89  4772.4  383.02  4793.2  383.30  4807.8  381.74
  4843.2  379.97  4936.9  369.77  4972.3  361.97  4978.6  359.79  5008.2  357.02
  5008.5  356.52  5012.2  357.02  5030.3  357.93  5047.0  357.39  5052.0  358.59
  5070.5  358.16  5120.7  359.50  5221.2  358.68  5358.7  359.64  5679.2  360.79
  5723.4  362.34  5803.8  363.49  5844.0  365.11  5864.1  364.82  6091.8  374.93
#Mann=5,-1,0
  4642.4    0.05       0  4651.3    0.12       0  5008.2    0.07       0
  5012.2    0.12       0  5358.7    0.05       0
Bank Sta=5008.2,5012.2
Exp/Cntr=0.3,0.1

Chan Stop Cuts=-1