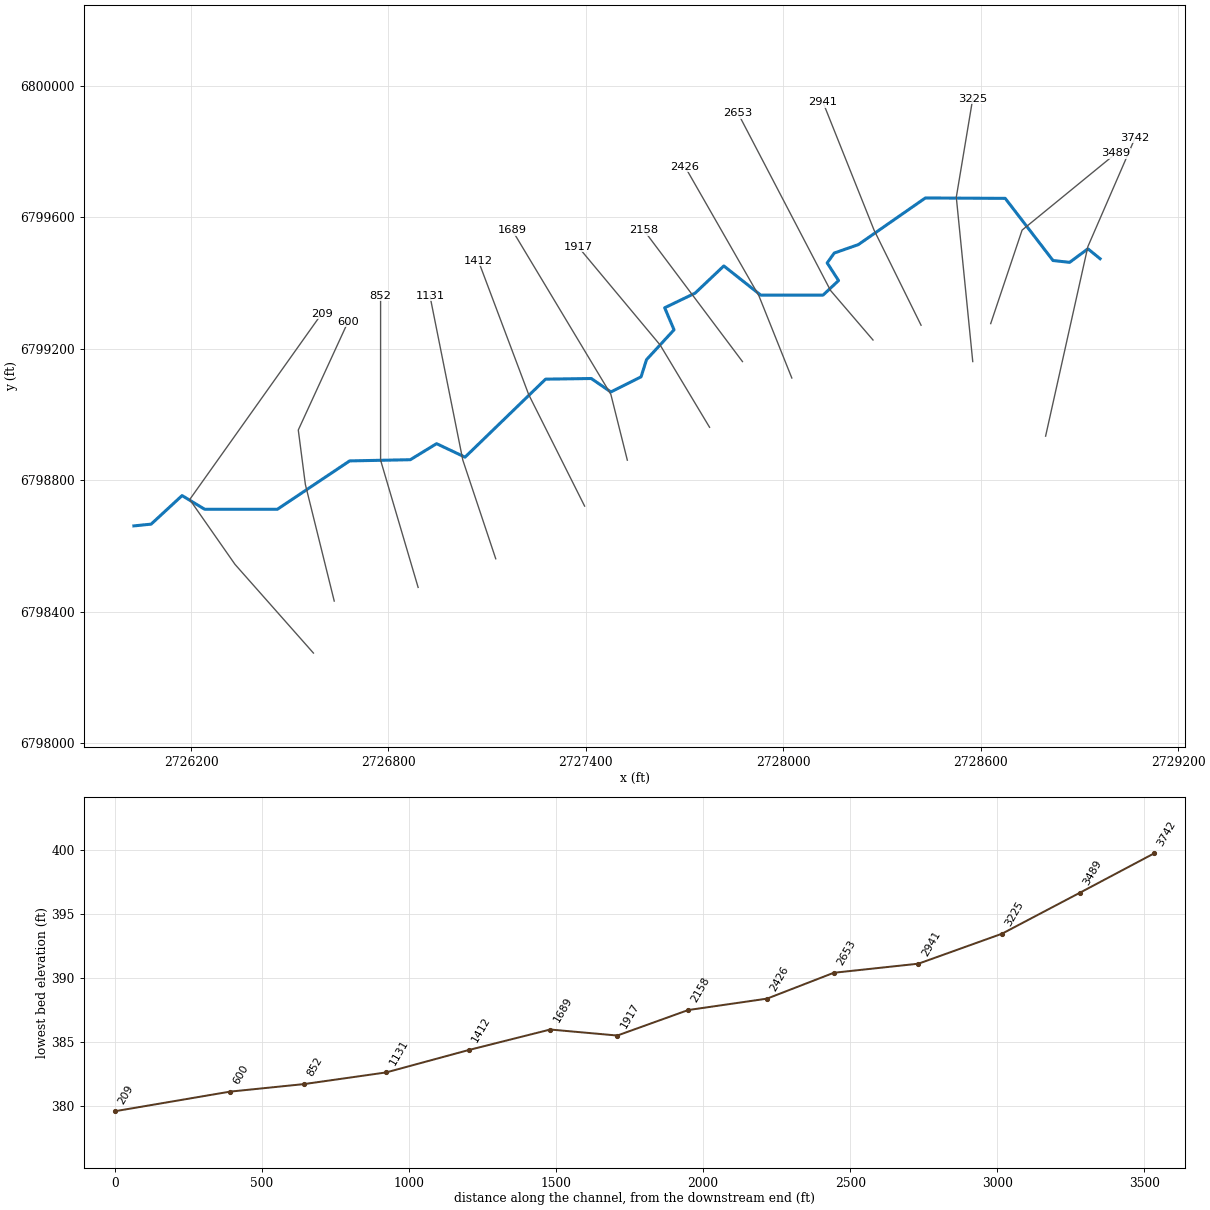
--- Lynn Creek T 12.prj (project) ---

Proj Title=Lynn Creek T 12 Base Level Engineering
Current Plan=p01
Default Exp/Contr=0.3,0.1
English Units
Geom File=g01
Flow File=f01
Plan File=p01
BEGIN DESCRIPTION:
Lynn Creek T 12
END DESCRIPTION:

--- Lynn Creek T 12.p01 (plan) ---

Plan Title=Multiple Run
Short Identifier=Multiple
Geom File=g01
Flow File=f01
Subcritical Flow
K Sum by GR= 0
Std Step Tol= 0.01
Critical Tol= 0.01
Num of Std Step Trials= 20
Max Error Tol= 0.3
Flow Tol Ratio= 0.001
Split Flow NTrial= 30
Split Flow Tol= 0.02
Split Flow Ratio= 0.02
Log Output Level= 0
Friction Slope Method= 1
Unsteady Friction Slope Method= 2
Unsteady Bridges Friction Slope Method= 1
Parabolic Critical Depth
Global Vel Dist=  1 , 1 , 1
Global Log Level= 0
CheckData=True
Encroach Param= -1, 0, 0, 0
BEGIN DESCRIPTION:
Multiple Run
END DESCRIPTION:

--- Lynn Creek T 12.f01 (steady flow) ---

Flow Title=Multiple
Number of Profiles=7
Profile Names=10-year,25-year,50-year,1pct_min,100-year,1pct_plu,500-year
River Rch & RM= Lynn Creek T 12,Reach-1,3742
     382     497     586     344     687    1370     939
Boundary for River Rch & Prof#=Lynn Creek T 12,Reach-1,1
Up Type=0
Dn Type=3
Dn Slope=0.005
Boundary for River Rch & Prof#=Lynn Creek T 12,Reach-1,2
Up Type=0
Dn Type=3
Dn Slope=0.005
Boundary for River Rch & Prof#=Lynn Creek T 12,Reach-1,3
Up Type=0
Dn Type=3
Dn Slope=0.005
Boundary for River Rch & Prof#=Lynn Creek T 12,Reach-1,4
Up Type=0
Dn Type=3
Dn Slope=0.005
Boundary for River Rch & Prof#=Lynn Creek T 12,Reach-1,5
Up Type=0
Dn Type=3
Dn Slope=0.005
Boundary for River Rch & Prof#=Lynn Creek T 12,Reach-1,6
Up Type=0
Dn Type=3
Dn Slope=0.005
Boundary for River Rch & Prof#=Lynn Creek T 12,Reach-1,7
Up Type=0
Dn Type=3
Dn Slope=0.005

--- Lynn Creek T 12.g01 (geometry) ---

Geom Title=Existing Conditions

River Reach=Lynn Creek T 12,Reach-1
Reach XY= 30
      2728963.14      6799473.86      2728926.13      6799504.04
      2728870.37      6799462.87      2728819.93      6799468.48
      2728674.75      6799657.55      2728431.93      6799658.76
      2728228.23      6799516.87      2728155.02      6799491.21
      2728133.48      6799461.20      2728168.11      6799407.39
      2728120.95      6799363.17      2727931.44      6799363.19
      2727819.34      6799452.02      2727732.01      6799369.20
      2727639.50      6799324.68      2727667.98      6799257.68
      2727584.32      6799166.75      2727567.79      6799114.63
      2727476.04      6799068.52      2727416.40      6799109.46
      2727277.47      6799107.47      2727032.73      6798870.15
      2726946.21      6798911.21      2726866.35      6798862.40
      2726681.93      6798858.76      2726462.14      6798711.54
      2726241.16      6798711.66      2726172.58      6798753.22
      2726078.52      6798666.35      2726026.00      6798661.00

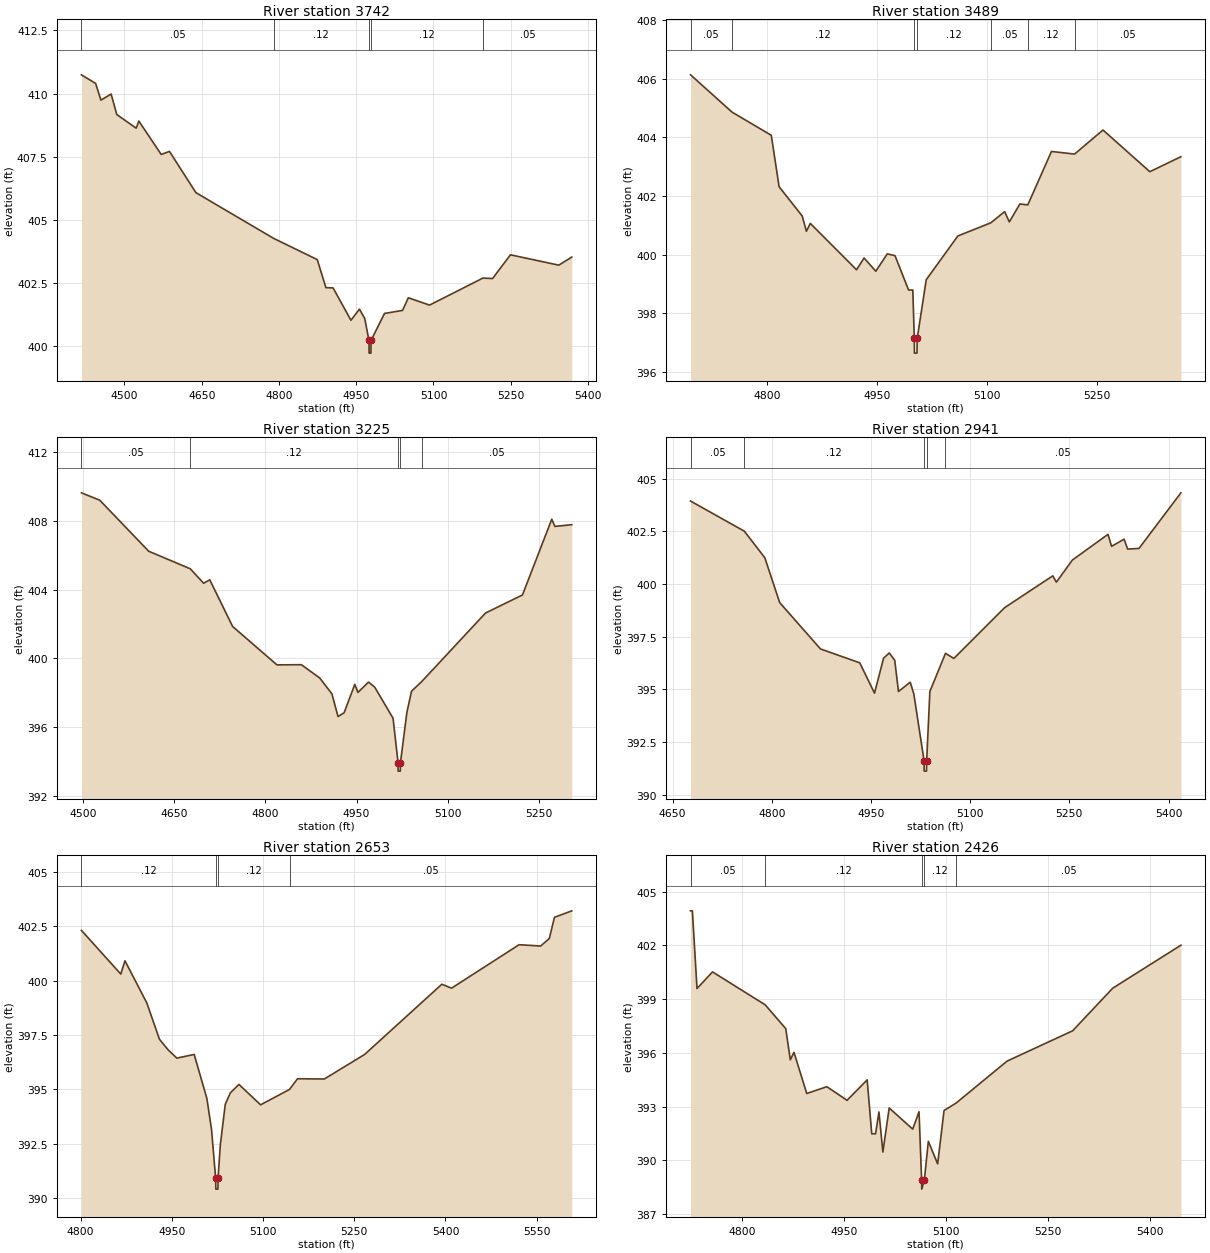
Type RM Length L Ch R = 1,3742,253,253,253
BEGIN DESCRIPTION:
1805
END DESCRIPTION:
XS GIS Cut Line= 3
      2728797.46      6798934.08      2728926.00      6799511.00
      2729069.69      6799842.21
#Sta/Elev= 30
  4416.5  410.74  4444.1  410.40  4454.3  409.74  4474.2  409.98  4485.1  409.17
  4522.8  408.63  4528.0  408.91  4571.4  407.59  4587.5  407.71  4638.7  406.08
  4789.7  404.27  4874.4  403.43  4891.2  402.32  4905.1  402.31  4939.8  401.03
  4956.3  401.47  4966.6  401.10  4974.8  400.23  4975.1  399.73  4978.6  399.73
  4978.8  400.23  5005.0  401.30  5040.0  401.42  5051.2  401.92  5092.4  401.63
  5196.2  402.70  5214.7  402.68  5249.5  403.62  5343.4  403.21  5368.6  403.53
#Mann=5,-1,0
  4416.5    0.05       0  4789.7    0.12       0  4974.8    0.07       0
  4978.8    0.12       0  5196.2    0.05       0
Bank Sta=4974.8,4978.8
Exp/Cntr=0.3,0.1

Type RM Length L Ch R = 1,3489,264,264,264
BEGIN DESCRIPTION:
1804
END DESCRIPTION:
XS GIS Cut Line= 3
      2728630.56      6799276.49      2728726.00      6799561.00
      2729011.60      6799794.67
#Sta/Elev= 30
  4695.3  406.13  4751.9  404.86  4805.5  404.07  4816.1  402.32  4847.7  401.32
  4853.4  400.80  4858.7  401.07  4921.8  399.49  4932.1  399.89  4948.1  399.44
  4963.7  400.03  4974.3  399.97  4992.8  398.80  4998.6  398.80  5000.6  397.15
  5000.8  396.65  5004.3  396.65  5004.6  397.15  5016.9  399.15  5060.0  400.64
  5105.1  401.09  5123.9  401.47  5130.3  401.12  5144.7  401.73  5155.5  401.70
  5187.8  403.52  5219.3  403.43  5258.1  404.25  5322.0  402.83  5364.4  403.34
#Mann=7,-1,0
  4695.3    0.05       0  4751.9    0.12       0  5000.6    0.07       0
  5004.6    0.12       0  5105.1    0.05       0  5155.5    0.12       0
  5219.3    0.05       0
Bank Sta=5000.6,5004.6
Exp/Cntr=0.3,0.1

Type RM Length L Ch R = 1,3225,284,284,284
BEGIN DESCRIPTION:
1803
END DESCRIPTION:
XS GIS Cut Line= 3
      2728576.00      6799161.00      2728526.00      6799661.00
      2728575.99      6799960.97
#Sta/Elev= 30
  4497.4  409.62  4527.6  409.19  4608.0  406.23  4676.4  405.21  4698.4  404.37
  4708.5  404.57  4746.1  401.86  4819.0  399.63  4859.2  399.64  4889.3  398.87
  4909.4  397.95  4919.5  396.63  4929.5  396.85  4947.1  398.50  4952.2  398.03
  4969.7  398.63  4979.8  398.34  5010.0  396.53  5018.2  393.96  5018.4  393.46
  5021.9  393.46  5022.2  393.96  5032.8  396.88  5040.4  398.10  5057.7  398.68
  5162.1  402.64  5222.9  403.69  5271.1  408.09  5276.2  407.67  5304.0  407.77
#Mann=5,-1,0
  4497.4    0.05       0  4676.4    0.12       0  5018.2    0.07       0
  5022.2    0.12       0  5057.7    0.05       0
Bank Sta=5018.2,5022.2
Exp/Cntr=0.3,0.1

Type RM Length L Ch R = 1,2941,288,288,288
BEGIN DESCRIPTION:
1802
END DESCRIPTION:
XS GIS Cut Line= 3
      2728418.88      6799271.55      2728276.00      6799561.00
      2728120.77      6799949.87
#Sta/Elev= 30
  4677.2  403.94  4758.5  402.51  4789.5  401.25  4812.0  399.12  4873.7  396.92
  4933.1  396.26  4955.4  394.82  4969.1  396.48  4977.7  396.73  4986.0  396.38
  4991.6  394.90  5009.4  395.34  5014.8  394.79  5030.3  391.62  5030.5  391.12
  5034.0  391.12  5034.3  391.62  5039.1  394.90  5062.7  396.71  5075.4  396.47
  5152.2  398.88  5225.0  400.39  5230.4  400.09  5254.6  401.14  5308.5  402.36
  5313.9  401.79  5332.8  402.13  5338.2  401.66  5355.3  401.69  5418.7  404.33
#Mann=5,-1,0
  4677.2    0.05       0  4758.5    0.12       0  5030.3    0.07       0
  5034.3    0.12       0  5062.7    0.05       0
Bank Sta=5030.3,5034.3
Exp/Cntr=0.3,0.1

Type RM Length L Ch R = 1,2653,227,227,227
BEGIN DESCRIPTION:
1801
END DESCRIPTION:
XS GIS Cut Line= 3
      2728272.82      6799226.60      2728143.62      6799377.43
      2727862.65      6799916.28
#Sta/Elev= 30
  4801.4  402.32  4866.1  400.31  4873.0  400.92  4908.9  398.98  4929.7  397.31
  4944.0  396.82  4958.3  396.44  4986.8  396.61  5007.7  394.58  5015.3  393.16
  5022.1  390.91  5022.4  390.41  5025.9  390.41  5026.1  390.91  5029.8  392.45
  5037.9  394.31  5046.2  394.84  5060.4  395.23  5096.0  394.29  5143.6  395.00
  5156.7  395.49  5200.9  395.48  5267.1  396.61  5394.0  399.84  5410.0  399.66
  5521.0  401.66  5556.6  401.60  5570.8  401.95  5579.2  402.92  5607.7  403.22
#Mann=4,-1,0
  4801.4    0.12       0  5022.1    0.07       0  5026.1    0.12       0
  5143.6    0.05       0
Bank Sta=5022.1,5026.1
Exp/Cntr=0.3,0.1

Type RM Length L Ch R = 1,2426,268,268,268
BEGIN DESCRIPTION:
1800
END DESCRIPTION:
XS GIS Cut Line= 3
      2728026.01      6799110.96      2727926.00      6799361.00
      2727701.53      6799753.56
#Sta/Elev= 30
  4723.6  403.93  4726.3  403.93  4733.1  399.59  4755.9  400.52  4833.5  398.68
  4863.7  397.35  4870.4  395.61  4875.8  396.03  4894.6  393.73  4924.2  394.11
  4953.9  393.35  4983.5  394.49  4990.2  391.48  4995.8  391.48  5000.8  392.70
  5006.6  390.46  5015.9  392.92  5050.5  391.74  5059.8  392.71  5063.6  388.89
  5063.8  388.39  5067.6  388.89  5073.5  391.06  5087.2  389.80  5096.6  392.78
  5114.5  393.20  5189.4  395.54  5285.8  397.23  5344.8  399.61  5445.1  402.01
#Mann=5,-1,0
  4723.6    0.05       0  4833.5    0.12       0  5063.6    0.07       0
  5067.6    0.12       0  5114.5    0.05       0
Bank Sta=5063.6,5067.6
Exp/Cntr=0.3,0.1

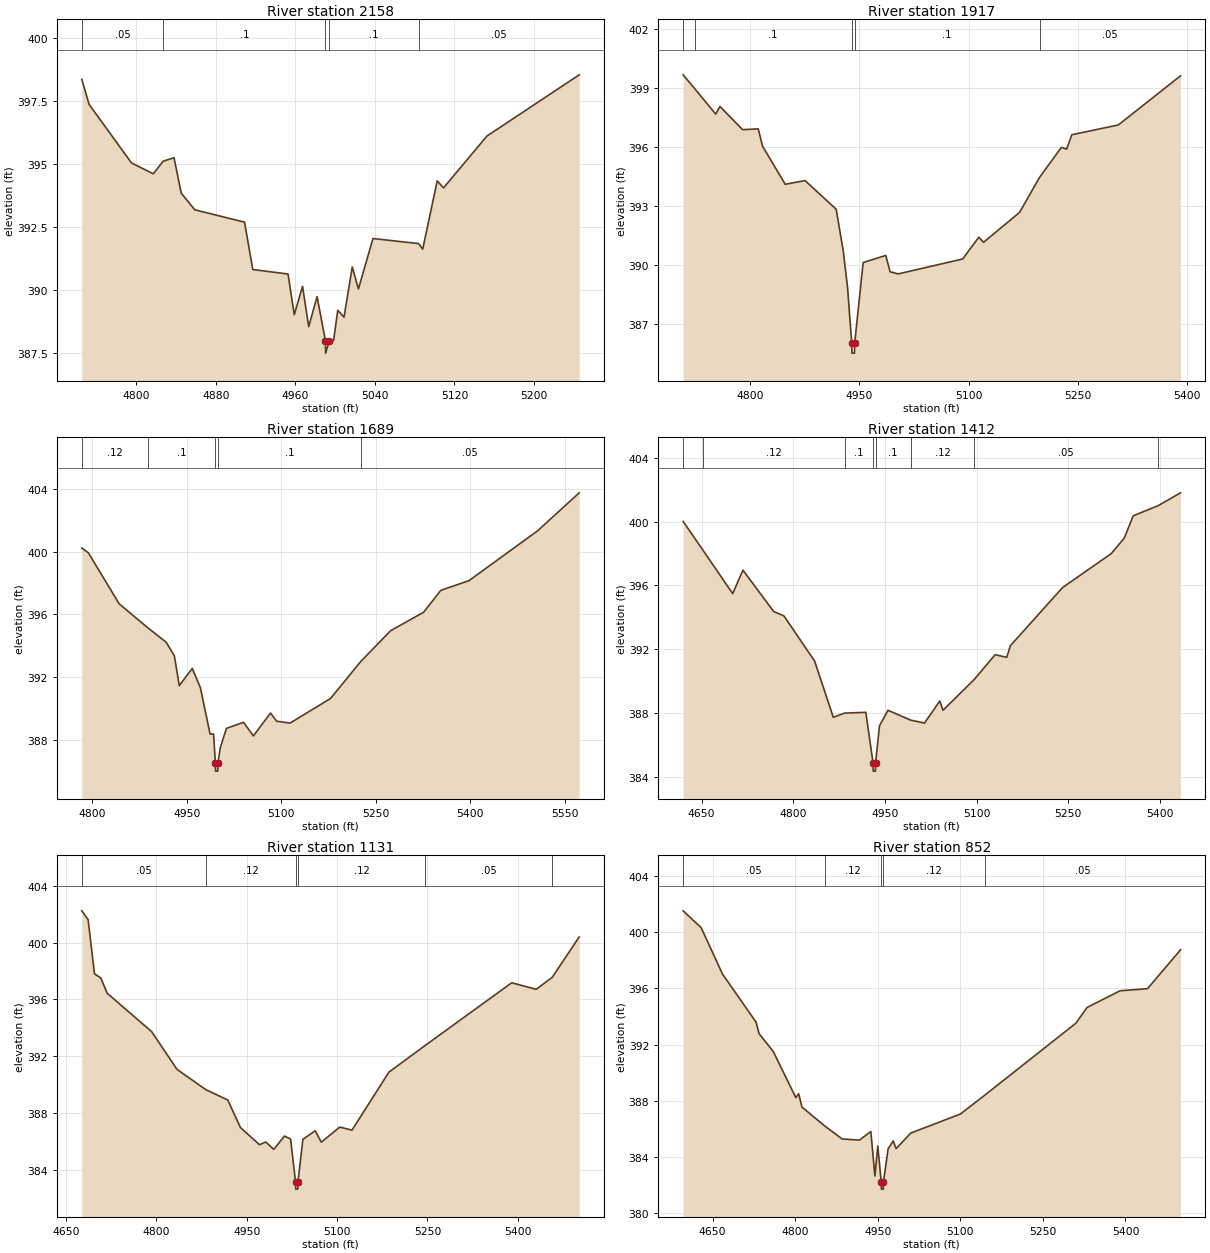
Type RM Length L Ch R = 1,2158,241,241,241
BEGIN DESCRIPTION:
1799
END DESCRIPTION:
XS GIS Cut Line= 3
      2727876.01      6799160.98      2727726.00      6799361.00
      2727576.01      6799560.98
#Sta/Elev= 30
  4745.4  398.37  4752.7  397.38  4795.4  395.05  4817.3  394.62  4827.2  395.12
  4838.1  395.26  4845.4  393.85  4859.0  393.19  4909.0  392.70  4917.3  390.82
  4952.7  390.64  4959.0  389.03  4967.3  390.15  4973.5  388.55  4981.9  389.74
  4990.3  388.00  4990.5  387.50  4994.3  388.00  4998.5  388.00  5002.7  389.20
  5009.0  388.93  5017.3  390.92  5023.5  390.05  5038.1  392.05  5083.9  391.85
  5088.1  391.63  5102.7  394.34  5109.0  394.06  5152.7  396.12  5245.4  398.55
#Mann=5,-1,0
  4745.4    0.05       0  4827.2     0.1       0  4990.3    0.07       0
  4994.3     0.1       0  5083.9    0.05       0
Bank Sta=4990.3,4994.3
Exp/Cntr=0.3,0.1

Type RM Length L Ch R = 1,1917,228,228,228
BEGIN DESCRIPTION:
1798
END DESCRIPTION:
XS GIS Cut Line= 3
      2727776.00      6798960.99      2727626.00      6799211.00
      2727375.98      6799511.02
#Sta/Elev= 30
  4708.6  399.67  4724.2  398.98  4753.3  397.67  4759.1  398.06  4790.2  396.88
  4811.6  396.92  4817.5  396.04  4848.6  394.10  4875.8  394.29  4918.5  392.83
  4928.2  390.70  4934.1  388.84  4939.8  386.01  4940.1  385.51  4943.6  385.51
  4943.8  386.01  4955.5  390.12  4986.5  390.48  4992.4  389.65  5003.4  389.54
  5091.9  390.30  5114.1  391.41  5120.6  391.15  5170.0  392.67  5197.5  394.46
  5227.3  395.98  5234.5  395.89  5241.6  396.62  5305.4  397.12  5390.7  399.62
#Mann=5,-1,0
  4708.6    0.05       0  4724.2     0.1       0  4939.8    0.07       0
  4943.8     0.1       0  5197.5    0.05       0
Bank Sta=4939.8,4943.8
Exp/Cntr=0.3,0.1

Type RM Length L Ch R = 1,1689,277,277,277
BEGIN DESCRIPTION:
1797
END DESCRIPTION:
XS GIS Cut Line= 3
      2727526.01      6798860.96      2727476.00      6799061.00
      2727176.00      6799561.01
#Sta/Elev= 30
  4783.4  400.23  4793.8  399.93  4842.7  396.67  4888.4  395.13  4917.4  394.21
  4930.3  393.35  4938.1  391.44  4958.7  392.54  4971.6  391.31  4987.0  388.35
  4992.5  388.35  4995.4  386.48  4995.6  385.98  4999.1  385.98  4999.4  386.48
  5003.2  387.48  5012.9  388.71  5040.1  389.10  5055.7  388.23  5082.9  389.69
  5092.6  389.17  5114.0  389.05  5178.1  390.62  5226.2  392.99  5273.4  394.95
  5325.8  396.13  5353.1  397.53  5397.8  398.15  5506.6  401.33  5572.7  403.76
#Mann=5,-1,0
  4783.4    0.12       0  4888.4     0.1       0  4995.4    0.07       0
  4999.4     0.1       0  5226.2    0.05       0
Bank Sta=4995.4,4999.4
Exp/Cntr=0.3,0.1

Type RM Length L Ch R = 1,1412,281,281,281
BEGIN DESCRIPTION:
1796
END DESCRIPTION:
XS GIS Cut Line= 3
      2727396.18      6798721.22      2727226.00      6799061.00
      2727073.28      6799467.33
#Sta/Elev= 30
  4619.7  400.01  4652.9  398.17  4700.8  395.49  4717.6  396.96  4767.9  394.37
  4784.6  394.10  4834.9  391.27  4865.5  387.75  4883.9  388.01  4918.7  388.06
  4930.6  384.88  4930.9  384.38  4934.4  384.38  4934.6  384.88  4941.1  387.22
  4955.0  388.19  4992.2  387.57  5014.8  387.39  5039.7  388.77  5045.1  388.19
  5096.2  390.12  5130.4  391.67  5149.3  391.50  5155.3  392.23  5240.7  395.87
  5320.2  397.99  5341.6  398.96  5356.3  400.36  5396.8  400.99  5433.8  401.80
#Mann=8,-1,0
  4619.7    0.05       0  4652.9    0.12       0  4883.9     0.1       0
  4930.6    0.07       0  4934.6     0.1       0  4992.2    0.12       0
  5096.2    0.05       0  5396.8    0.12       0
Bank Sta=4930.6,4934.6
Exp/Cntr=0.3,0.1

Type RM Length L Ch R = 1,1131,279,279,279
BEGIN DESCRIPTION:
1795
END DESCRIPTION:
XS GIS Cut Line= 3
      2727126.00      6798561.00      2727026.00      6798861.00
      2726926.01      6799360.97
#Sta/Elev= 30
  4676.0  402.24  4686.5  401.62  4697.1  397.80  4707.6  397.51  4718.2  396.43
  4792.0  393.73  4834.1  391.07  4882.0  389.64  4918.4  388.91  4939.5  386.97
  4971.1  385.76  4981.7  385.95  4994.8  385.43  5012.6  386.37  5022.8  386.16
  5031.0  383.13  5031.3  382.63  5034.8  382.63  5035.0  383.13  5043.2  386.14
  5063.6  386.74  5073.8  385.94  5104.4  387.00  5124.8  386.79  5186.0  390.87
  5246.5  392.76  5390.0  397.17  5430.7  396.71  5457.2  397.55  5502.1  400.40
#Mann=6,-1,0
  4676.0    0.05       0  4882.0    0.12       0  5031.0    0.07       0
  5035.0    0.12       0  5246.5    0.05       0  5457.2    0.12       0
Bank Sta=5031,5035
Exp/Cntr=0.3,0.1

Type RM Length L Ch R = 1,852,252,252,252
BEGIN DESCRIPTION:
1794
END DESCRIPTION:
XS GIS Cut Line= 3
      2726890.08      6798473.86      2726776.00      6798861.00
      2726776.00      6799361.00
#Sta/Elev= 30
  4596.4  401.52  4629.2  400.32  4667.8  397.03  4728.9  393.60  4734.4  392.78
  4760.2  391.51  4801.1  388.23  4806.3  388.50  4812.3  387.56  4853.7  386.21
  4885.3  385.29  4916.7  385.21  4937.4  385.82  4944.8  382.65  4950.0  384.79
  4956.3  382.22  4956.5  381.72  4960.0  381.72  4960.3  382.22  4968.7  384.58
  4978.1  385.15  4983.3  384.60  5010.0  385.71  5100.0  387.06  5144.9  388.42
  5310.0  393.53  5330.0  394.64  5390.0  395.83  5440.0  395.98  5500.0  398.75
#Mann=5,-1,0
  4596.4    0.05       0  4853.7    0.12       0  4956.3    0.07       0
  4960.3    0.12       0  5144.9    0.05       0
Bank Sta=4956.3,4960.3
Exp/Cntr=0.3,0.1

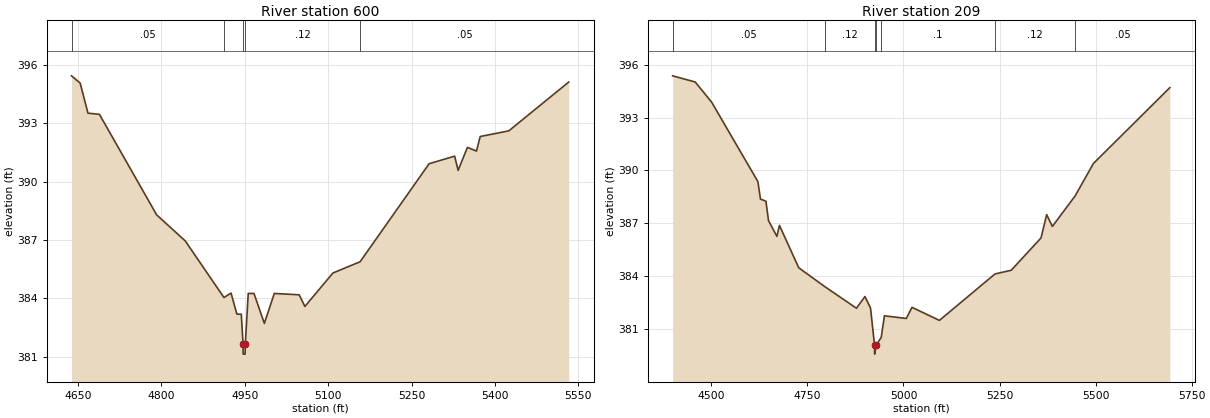
Type RM Length L Ch R = 1,600,391,391,391
BEGIN DESCRIPTION:
2327
END DESCRIPTION:
XS GIS Cut Line= 4
      2726635.07      6798432.29      2726547.34      6798787.02
      2726525.82      6798952.77      2726676.98      6799281.85
#Sta/Elev= 30
  4638.1  395.44  4653.6  395.07  4667.7  393.52  4688.3  393.46  4791.3  388.29
  4842.8  386.95  4912.4  384.04  4925.2  384.27  4935.5  383.19  4943.6  383.18
  4946.8  381.63  4947.0  381.13  4950.5  381.13  4950.8  381.63  4956.1  384.25
  4966.4  384.25  4985.1  382.71  5003.0  384.25  5047.8  384.18  5058.0  383.58
  5108.4  385.30  5157.4  385.88  5281.6  390.92  5327.5  391.31  5333.8  390.58
  5350.5  391.76  5366.8  391.57  5373.5  392.32  5425.0  392.61  5532.8  395.12
#Mann=5,-1,0
  4638.1    0.05       0  4912.4    0.12       0  4946.8    0.07       0
  4950.8    0.12       0  5157.4    0.05       0
Bank Sta=4946.8,4950.8
Exp/Cntr=0.3,0.1

Type RM Length L Ch R = 1,209,0,0,0
BEGIN DESCRIPTION:
1793
END DESCRIPTION:
XS GIS Cut Line= 4
      2726571.85      6798274.09      2726333.41      6798543.95
      2726195.80      6798741.30      2726596.95      6799306.63
#Sta/Elev= 30
  4399.3  395.36  4458.1  395.01  4500.8  393.87  4621.2  389.37  4627.9  388.38
  4642.1  388.26  4648.8  387.16  4670.6  386.27  4677.3  386.89  4727.5  384.49
  4794.8  383.43  4877.7  382.20  4899.7  382.86  4914.3  382.21  4924.8  380.10
  4925.0  379.60  4928.8  380.10  4942.2  380.55  4950.4  381.77  5007.4  381.62
  5022.2  382.25  5093.5  381.51  5238.2  384.14  5280.5  384.35  5358.0  386.18
  5372.7  387.50  5387.5  386.83  5446.4  388.55  5494.5  390.40  5693.2  394.69
#Mann=7,-1,0
  4399.3    0.05       0  4794.8    0.12       0  4924.8    0.07       0
  4928.8    0.12       0  4942.2     0.1       0  5238.2    0.12       0
  5446.4    0.05       0
Bank Sta=4924.8,4928.8
Exp/Cntr=0.3,0.1

Chan Stop Cuts=-1