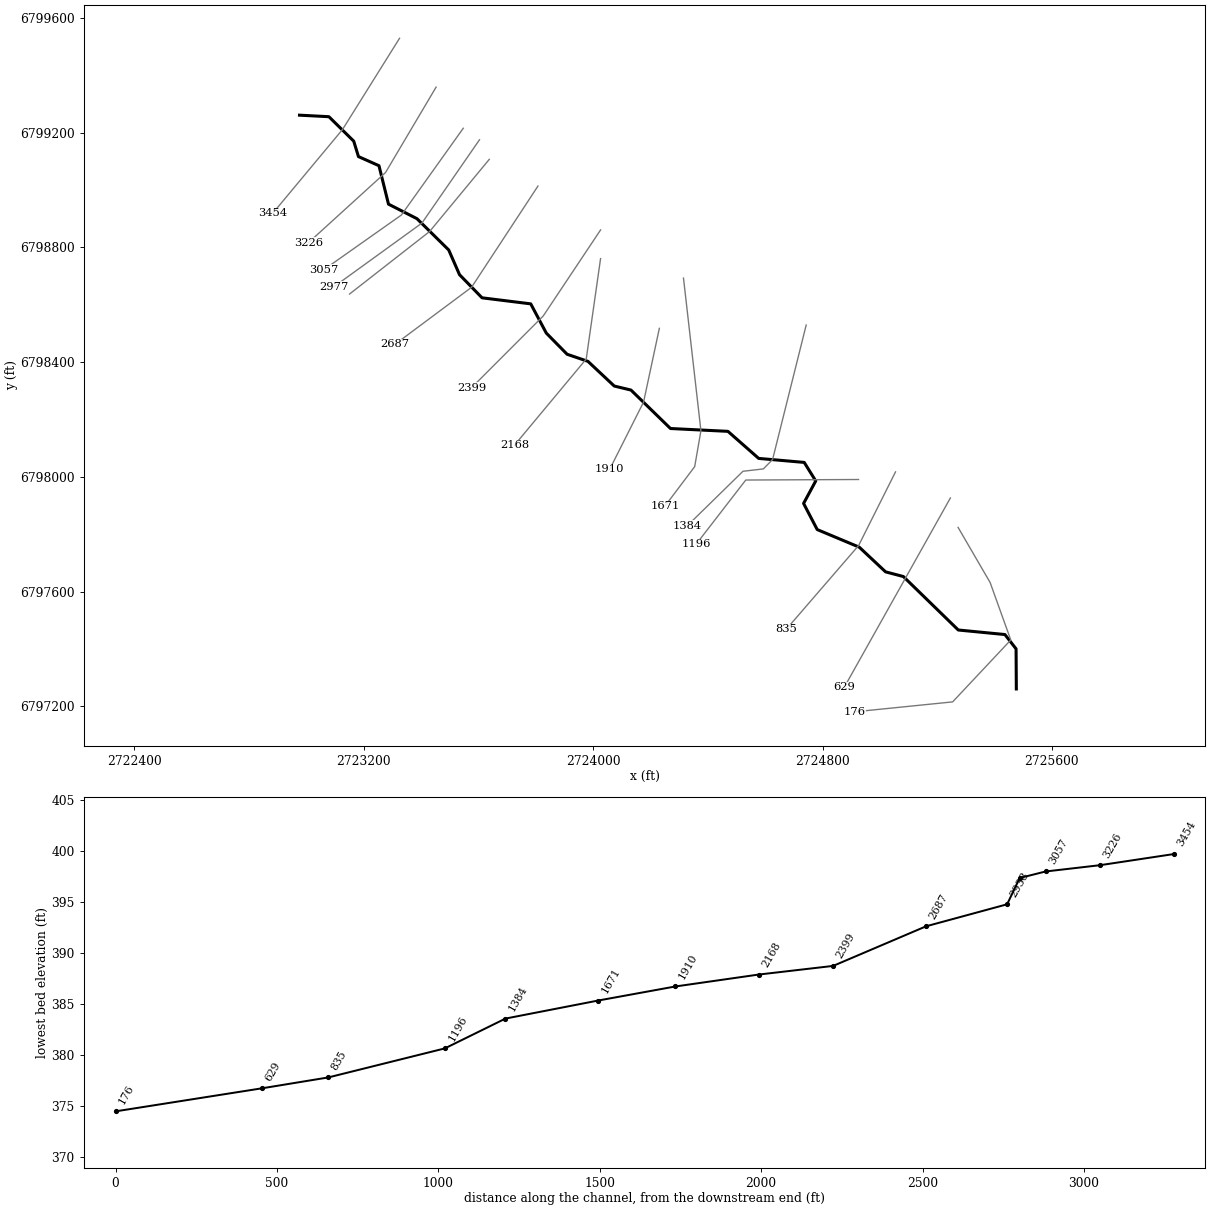
--- Lynn Creek T 13.prj (project) ---

Proj Title=Lynn Creek T 13 Base Level Engineering
Current Plan=p01
Default Exp/Contr=0.3,0.1
English Units
Geom File=g01
Flow File=f01
Plan File=p01
BEGIN DESCRIPTION:
Lynn Creek T 13
END DESCRIPTION:

--- Lynn Creek T 13.p01 (plan) ---

Plan Title=Multiple Run
Short Identifier=Multiple
Geom File=g01
Flow File=f01
Subcritical Flow
K Sum by GR= 0
Std Step Tol= 0.01
Critical Tol= 0.01
Num of Std Step Trials= 20
Max Error Tol= 0.3
Flow Tol Ratio= 0.001
Split Flow NTrial= 30
Split Flow Tol= 0.02
Split Flow Ratio= 0.02
Log Output Level= 0
Friction Slope Method= 1
Unsteady Friction Slope Method= 2
Unsteady Bridges Friction Slope Method= 1
Parabolic Critical Depth
Global Vel Dist=  1 , 1 , 1
Global Log Level= 0
CheckData=True
Encroach Param= -1, 0, 0, 0
BEGIN DESCRIPTION:
Multiple Run
END DESCRIPTION:

--- Lynn Creek T 13.f01 (steady flow) ---

Flow Title=Multiple
Number of Profiles=7
Profile Names=10-year,25-year,50-year,1pct_min,100-year,1pct_plu,500-year
River Rch & RM= Lynn Creek T 13,Reach-1,3454
     262     332     385     222     444     885     587
Boundary for River Rch & Prof#=Lynn Creek T 13,Reach-1,1
Up Type=0
Dn Type=3
Dn Slope=0.005
Boundary for River Rch & Prof#=Lynn Creek T 13,Reach-1,2
Up Type=0
Dn Type=3
Dn Slope=0.005
Boundary for River Rch & Prof#=Lynn Creek T 13,Reach-1,3
Up Type=0
Dn Type=3
Dn Slope=0.005
Boundary for River Rch & Prof#=Lynn Creek T 13,Reach-1,4
Up Type=0
Dn Type=3
Dn Slope=0.005
Boundary for River Rch & Prof#=Lynn Creek T 13,Reach-1,5
Up Type=0
Dn Type=3
Dn Slope=0.005
Boundary for River Rch & Prof#=Lynn Creek T 13,Reach-1,6
Up Type=0
Dn Type=3
Dn Slope=0.005
Boundary for River Rch & Prof#=Lynn Creek T 13,Reach-1,7
Up Type=0
Dn Type=3
Dn Slope=0.005

--- Lynn Creek T 13.g01 (geometry) ---

Geom Title=Existing Conditions

River Reach=Lynn Creek T 13,Reach-1
Reach XY= 30
      2722976.00      6799261.00      2723078.51      6799255.66
      2723165.12      6799170.44      2723181.65      6799116.64
      2723253.16      6799084.84      2723286.39      6798950.90
      2723385.66      6798900.21      2723496.39      6798791.16
      2723534.15      6798704.93      2723612.66      6798624.36
      2723782.47      6798603.30      2723836.78      6798501.32
      2723909.29      6798427.64      2723982.04      6798402.82
      2724073.72      6798316.87      2724132.05      6798302.84
      2724269.81      6798168.81      2724470.14      6798158.93
      2724577.47      6798064.56      2724736.23      6798050.65
      2724776.45      6797986.10      2724734.05      6797907.66
      2724781.55      6797816.59      2724928.29      6797755.15
      2725019.96      6797669.18      2725082.05      6797652.84
      2725273.55      6797466.47      2725436.18      6797450.68
      2725475.09      6797400.77      2725476.00      6797261.00

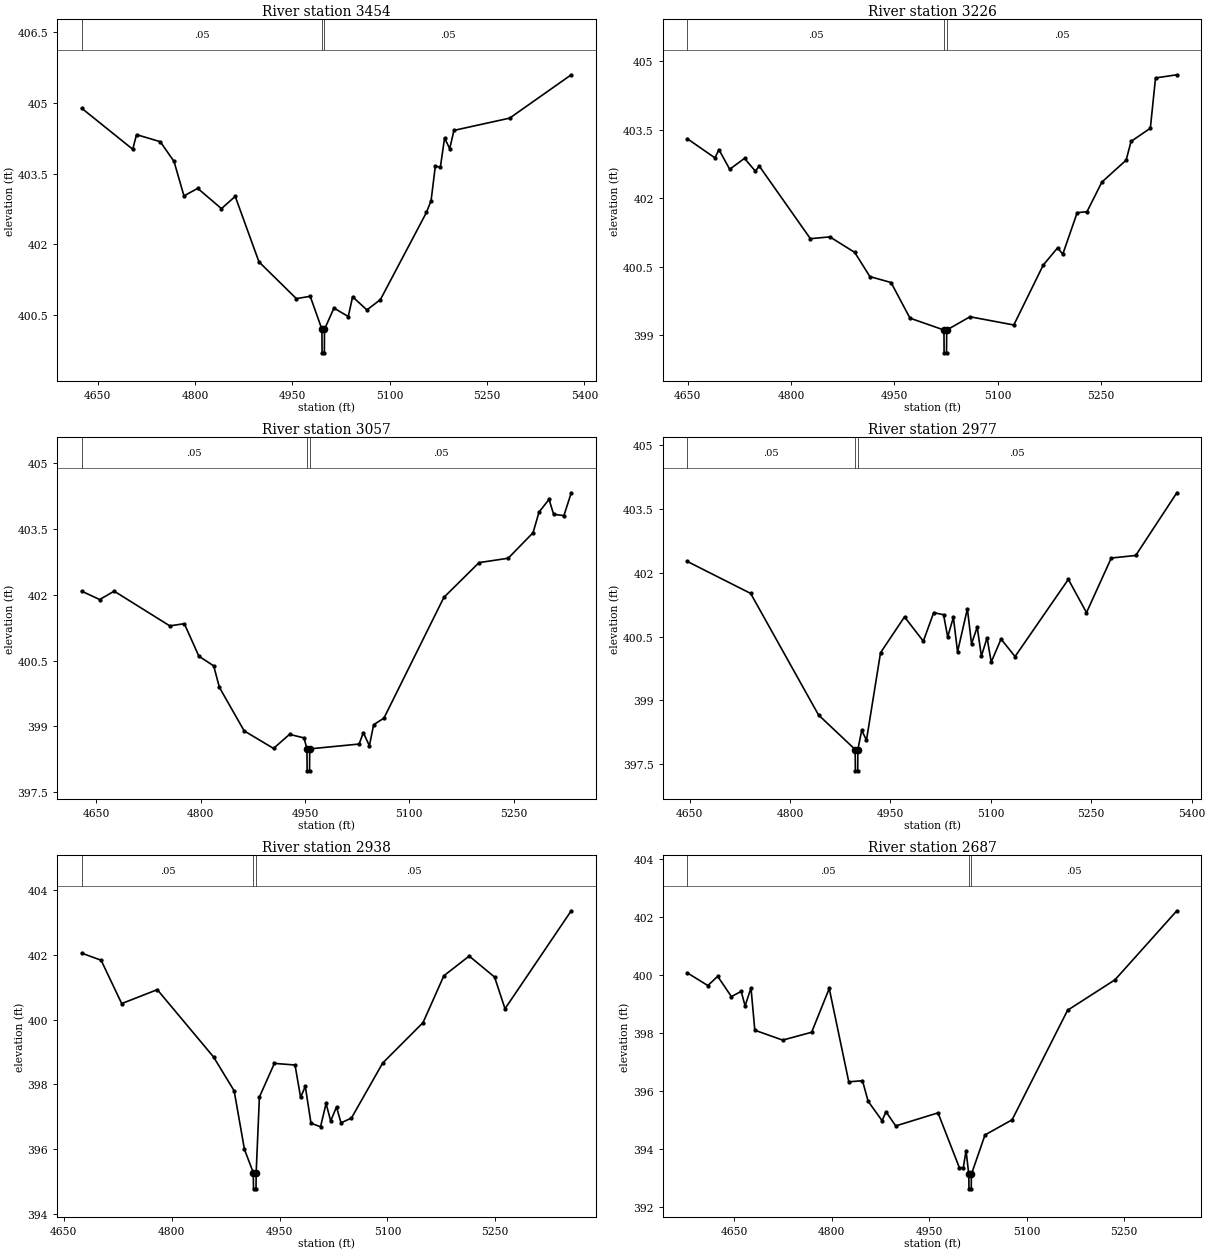
Type RM Length L Ch R = 1,3454,228,228,228
BEGIN DESCRIPTION:
Lynn Creek T 13 11.0
END DESCRIPTION:
XS GIS Cut Line= 3
      2723324.93      6799529.07      2723126.00      6799211.00
      2722883.15      6798919.57
#Sta/Elev= 30
  4625.3  404.89  4703.9  404.02  4709.8  404.33  4746.4  404.18  4767.6  403.76
  4782.9  403.03  4804.1  403.19  4840.7  402.76  4861.9  403.02  4898.5  401.63
  4956.2  400.85  4977.5  400.90  4995.5  400.20  4995.8  399.70  4999.3  399.70
  4999.5  400.20  5014.1  400.65  5036.2  400.47  5042.8  400.89  5064.9  400.61
  5085.7  400.83  5156.7  402.68  5163.8  402.93  5170.3  403.66  5178.1  403.64
  5184.6  404.26  5192.5  404.03  5199.0  404.42  5284.9  404.68  5379.8  405.60
#Mann=3,-1,0
  4625.3    0.05       0  4995.5    0.04       0  4999.5    0.05       0
Bank Sta=4995.5,4999.5
Exp/Cntr=0.3,0.1

Type RM Length L Ch R = 1,3226,169,169,169
BEGIN DESCRIPTION:
Lynn Creek T 13 10.0
END DESCRIPTION:
XS GIS Cut Line= 3
      2723452.42      6799358.82      2723276.00      6799061.00
      2723006.85      6798816.32
#Sta/Elev= 30
  4649.7  403.30  4689.8  402.88  4695.6  403.06  4711.2  402.63  4732.7  402.87
  4748.3  402.59  4754.1  402.70  4828.2  401.11  4856.4  401.15  4892.5  400.81
  4914.5  400.28  4945.2  400.15  4972.6  399.37  5021.9  399.11  5022.1  398.61
  5025.6  398.61  5025.9  399.11  5059.7  399.40  5123.2  399.22  5165.8  400.53
  5186.7  400.91  5194.2  400.77  5215.1  401.68  5229.3  401.70  5250.9  402.35
  5286.1  402.83  5293.2  403.24  5321.2  403.53  5328.7  404.63  5359.6  404.70
#Mann=3,-1,0
  4649.7    0.05       0  5021.9    0.04       0  5025.9    0.05       0
Bank Sta=5021.9,5025.9
Exp/Cntr=0.3,0.1

Type RM Length L Ch R = 1,3057,80,80,80
BEGIN DESCRIPTION:
Mapping XS 93ec8348
END DESCRIPTION:
XS GIS Cut Line= 3
      2723547.15      6799215.41      2723331.34      6798912.95
      2723059.96      6798721.63
#Sta/Elev= 30
  4629.1  402.08  4654.9  401.89  4675.8  402.08  4755.7  401.29  4776.6  401.34
  4797.5  400.60  4818.8  400.38  4827.0  399.89  4862.6  398.90  4904.8  398.50
  4927.8  398.82  4948.7  398.74  4952.8  398.49  4953.1  397.99  4956.6  397.99
  4956.8  398.49  5027.8  398.60  5033.9  398.86  5042.6  398.56  5048.7  399.04
  5063.5  399.19  5149.7  401.94  5200.2  402.73  5242.1  402.83  5277.8  403.41
  5286.4  403.88  5300.8  404.17  5307.4  403.83  5322.2  403.80  5332.7  404.32
#Mann=3,-1,0
  4629.1    0.05       0  4952.8    0.05       0  4956.8    0.05       0
Bank Sta=4952.8,4956.8
Exp/Cntr=0.3,0.1

Type RM Length L Ch R = 1,2977,39,39,39
BEGIN DESCRIPTION:
Lynn Creek T 13 9.0
END DESCRIPTION:
XS GIS Cut Line= 3
      2723603.77      6799175.29      2723402.82      6798884.70
      2723096.67      6798663.33
#Sta/Elev= 30
  4646.7  402.26  4741.3  401.51  4842.7  398.66  4897.4  397.85  4897.7  397.35
  4901.2  397.35  4901.4  397.85  4907.2  398.30  4914.3  398.07  4935.3  400.12
  4971.1  400.96  4999.2  400.39  5014.7  401.06  5029.4  401.01  5035.6  400.49
  5044.1  400.95  5050.3  400.14  5065.0  401.15  5071.2  400.33  5079.7  400.72
  5085.9  400.04  5094.4  400.47  5100.6  399.90  5115.3  400.44  5136.2  400.03
  5215.8  401.84  5242.9  401.06  5279.9  402.34  5316.4  402.40  5377.8  403.87
#Mann=3,-1,0
  4646.7    0.05       0  4897.4    0.04       0  4901.4    0.05       0
Bank Sta=4897.4,4901.4
Exp/Cntr=0.3,0.1

Type RM Length L Ch R = 1,2938,251,251,251
BEGIN DESCRIPTION:
Mapping XS 460532d8
END DESCRIPTION:
XS GIS Cut Line= 3
      2723637.92      6799107.11      2723429.76      6798855.49
      2723150.60      6798637.59
#Sta/Elev= 30
  4674.9  402.06  4701.9  401.84  4730.5  400.50  4780.0  400.93  4858.2  398.85
  4886.9  397.80  4901.2  395.99  4913.5  395.27  4913.8  394.77  4917.3  394.77
  4917.5  395.27  4922.0  397.61  4942.8  398.65  4971.5  398.60  4979.3  397.60
  4985.8  397.94  4993.7  396.80  5007.0  396.69  5014.7  397.41  5021.1  396.87
  5029.2  397.30  5035.5  396.81  5050.0  396.96  5093.4  398.66  5149.5  399.91
  5178.5  401.36  5213.7  401.97  5249.0  401.32  5263.5  400.34  5355.6  403.37
#Mann=3,-1,0
  4674.9    0.05       0  4913.5    0.04       0  4917.5    0.05       0
Bank Sta=4913.5,4917.5
Exp/Cntr=0.3,0.1

Type RM Length L Ch R = 1,2687,288,288,288
BEGIN DESCRIPTION:
Lynn Creek T 13 8.0
END DESCRIPTION:
XS GIS Cut Line= 3
      2723807.58      6799013.78      2723576.00      6798661.00
      2723309.77      6798462.80
#Sta/Elev= 30
  4577.5  400.06  4609.2  399.62  4624.3  399.94  4645.4  399.24  4660.5  399.42
  4666.5  398.92  4675.6  399.54  4681.5  398.08  4724.4  397.74  4769.0  398.01
  4796.1  399.52  4826.2  396.30  4847.3  396.34  4856.0  395.63  4877.5  394.96
  4883.5  395.27  4898.5  394.78  4963.6  395.23  4996.5  393.34  5002.6  393.34
  5006.8  393.93  5011.0  393.11  5011.3  392.61  5014.8  392.61  5015.0  393.11
  5036.0  394.47  5077.7  394.99  5163.2  398.77  5236.2  399.82  5331.4  402.20
#Mann=3,-1,0
  4577.5    0.05       0  5011.0    0.05       0  5015.0    0.05       0
Bank Sta=5011,5015
Exp/Cntr=0.3,0.1

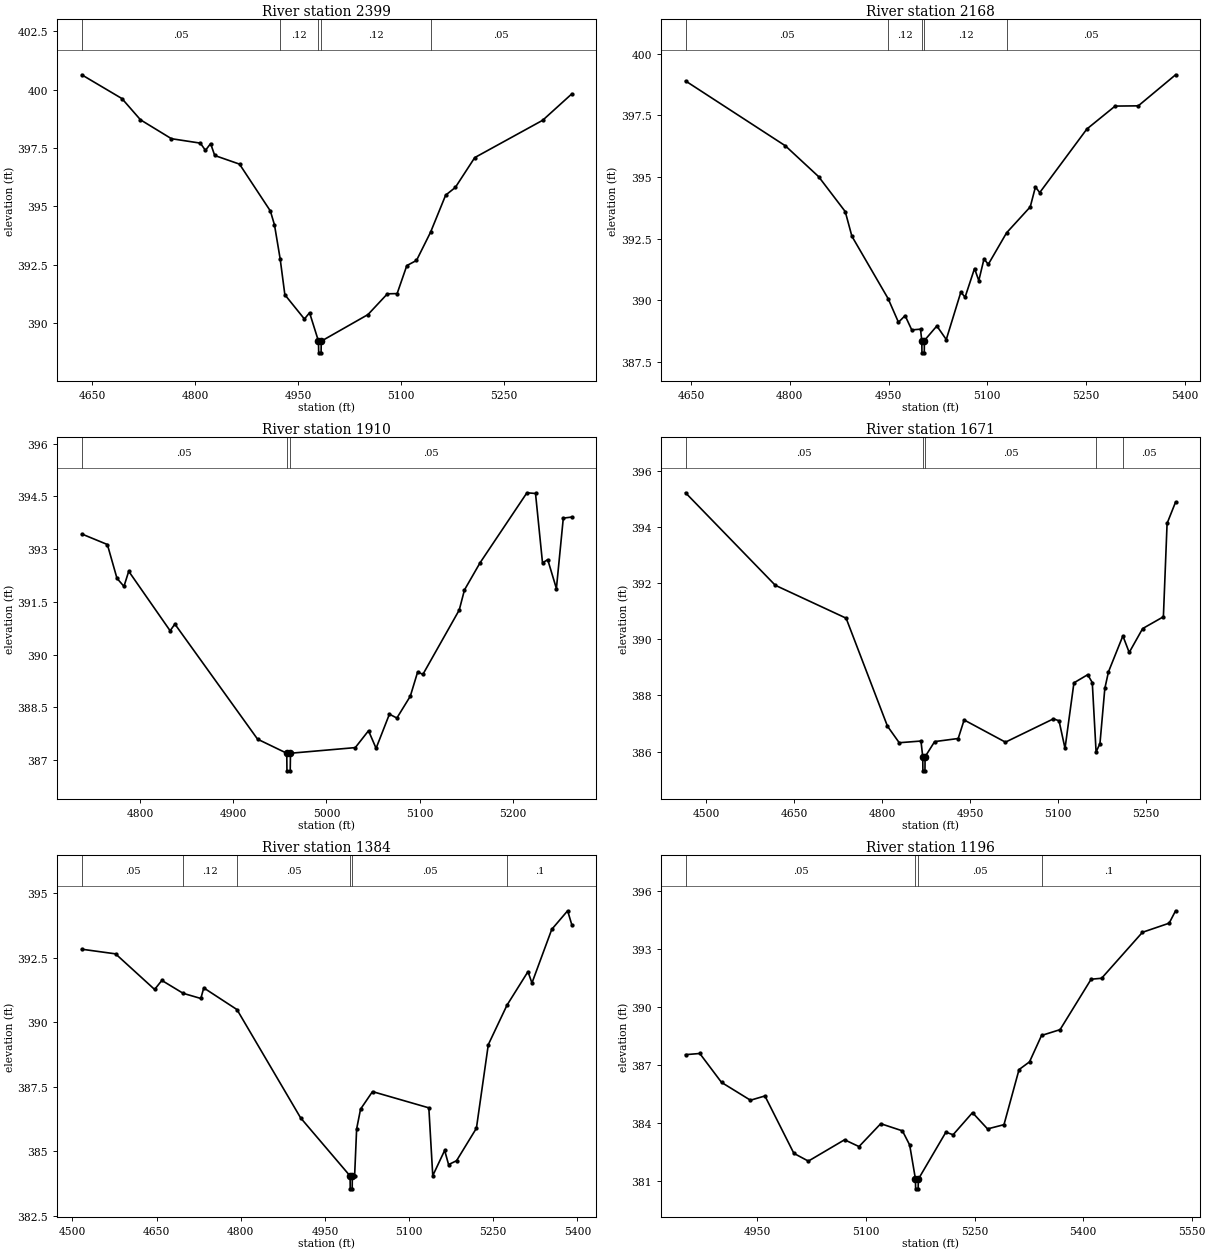
Type RM Length L Ch R = 1,2399,231,231,231
BEGIN DESCRIPTION:
Lynn Creek T 13 7.0
END DESCRIPTION:
XS GIS Cut Line= 3
      2724026.01      6798861.01      2723826.00      6798561.00
      2723576.02      6798311.02
#Sta/Elev= 30
  4634.8  400.64  4693.4  399.62  4720.4  398.71  4765.5  397.90  4807.6  397.71
  4815.1  397.40  4822.6  397.69  4828.6  397.18  4864.7  396.81  4909.7  394.80
  4915.7  394.20  4924.0  392.74  4930.8  391.21  4959.3  390.17  4966.8  390.44
  4979.8  389.22  4980.1  388.72  4983.6  388.72  4983.8  389.22  5051.9  390.36
  5080.2  391.25  5094.4  391.26  5108.5  392.46  5122.6  392.68  5143.1  393.89
  5165.1  395.48  5179.2  395.81  5207.5  397.09  5306.5  398.69  5348.9  399.82
#Mann=5,-1,0
  4634.8    0.05       0  4924.0    0.12       0  4979.8    0.07       0
  4983.8    0.12       0  5143.1    0.05       0
Bank Sta=4979.8,4983.8
Exp/Cntr=0.3,0.1

Type RM Length L Ch R = 1,2168,258,258,258
BEGIN DESCRIPTION:
Lynn Creek T 13 6.0
END DESCRIPTION:
XS GIS Cut Line= 3
      2724026.00      6798761.02      2723976.00      6798411.00
      2723725.99      6798110.99
#Sta/Elev= 30
  4641.8  398.90  4793.3  396.27  4843.8  395.02  4884.3  393.60  4894.4  392.60
  4949.4  390.07  4965.1  389.11  4975.2  389.38  4985.3  388.80  4998.6  388.83
  5000.5  388.37  5000.8  387.87  5004.3  387.87  5004.5  388.37  5023.4  388.96
  5037.7  388.41  5059.8  390.33  5066.3  390.13  5080.6  391.29  5087.1  390.80
  5095.0  391.68  5101.5  391.46  5129.3  392.74  5165.2  393.79  5173.1  394.60
  5179.6  394.37  5251.2  396.95  5294.1  397.88  5329.3  397.89  5385.9  399.15
#Mann=5,-1,0
  4641.8    0.05       0  4949.4    0.12       0  5000.5    0.07       0
  5004.5    0.12       0  5129.3    0.05       0
Bank Sta=5000.5,5004.5
Exp/Cntr=0.3,0.1

Type RM Length L Ch R = 1,1910,239,239,239
BEGIN DESCRIPTION:
Lynn Creek T 13 5.0
END DESCRIPTION:
XS GIS Cut Line= 3
      2724230.99      6798517.94      2724176.00      6798261.00
      2724057.67      6798026.30
#Sta/Elev= 30
  4737.5  393.43  4765.0  393.13  4775.3  392.17  4782.8  391.94  4787.9  392.37
  4832.3  390.68  4837.4  390.87  4926.1  387.60  4957.4  387.20  4957.6  386.70
  4961.1  386.70  4961.4  387.20  5030.9  387.36  5045.1  387.84  5053.2  387.34
  5067.5  388.31  5075.5  388.20  5089.9  388.82  5097.8  389.51  5103.4  389.44
  5142.4  391.27  5148.0  391.84  5164.7  392.61  5215.0  394.60  5224.2  394.58
  5231.7  392.61  5237.3  392.70  5246.6  391.88  5254.0  393.88  5263.1  393.91
#Mann=3,-1,0
  4737.5    0.05       0  4957.4    0.04       0  4961.4    0.05       0
Bank Sta=4957.4,4961.4
Exp/Cntr=0.3,0.1

Type RM Length L Ch R = 1,1671,287,287,287
BEGIN DESCRIPTION:
Lynn Creek T 13 4.0
END DESCRIPTION:
XS GIS Cut Line= 4
      2724315.18      6798693.13      2724376.00      6798161.00
      2724354.24      6798035.93      2724249.90      6797897.49
#Sta/Elev= 30
  4464.4  395.21  4617.5  391.92  4738.3  390.75  4808.8  386.91  4828.9  386.32
  4866.0  386.38  4869.0  385.82  4869.3  385.32  4872.8  385.32  4873.0  385.82
  4889.3  386.36  4929.5  386.47  4939.6  387.13  5010.1  386.34  5092.0  387.17
  5101.5  387.10  5111.7  386.12  5126.9  388.45  5150.4  388.74  5158.2  388.46
  5164.7  385.99  5171.3  386.29  5179.6  388.25  5185.8  388.84  5210.4  390.12
  5221.2  389.53  5244.1  390.38  5279.5  390.80  5285.8  394.12  5300.3  394.88
#Mann=5,-1,0
  4464.4    0.05       0  4869.0    0.03       0  4873.0    0.05       0
  5164.7     0.1       0  5210.4    0.05       0
Bank Sta=4869,4873
Exp/Cntr=0.3,0.1

Type RM Length L Ch R = 1,1384,188,188,188
BEGIN DESCRIPTION:
Lynn Creek T 13 3.0
END DESCRIPTION:
XS GIS Cut Line= 5
      2724743.13      6798529.50      2724626.00      6798061.00
      2724593.95      6798028.04      2724522.63      6798019.75
      2724327.58      6797829.02
#Sta/Elev= 30
  4516.6  392.84  4576.9  392.66  4646.5  391.28  4659.4  391.63  4697.4  391.13
  4728.9  390.93  4734.1  391.34  4793.3  390.50  4906.8  386.30  4994.9  384.05
  4995.2  383.55  4998.7  383.55  4998.9  384.05  5003.0  384.05  5006.6  385.87
  5013.6  386.64  5034.9  387.32  5135.3  386.69  5142.3  384.06  5163.5  385.04
  5170.5  384.49  5184.7  384.64  5220.1  385.90  5241.3  389.14  5274.6  390.67
  5312.0  391.97  5319.1  391.53  5354.4  393.61  5382.7  394.33  5390.1  393.79
#Mann=6,-1,0
  4516.6    0.05       0  4697.4    0.12       0  4793.3    0.05       0
  4994.9    0.04       0  4998.9    0.05       0  5274.6     0.1       0
Bank Sta=4994.9,4998.9
Exp/Cntr=0.3,0.1

Type RM Length L Ch R = 1,1196,361,361,361
BEGIN DESCRIPTION:
Mapping XS eebfcb20
END DESCRIPTION:
XS GIS Cut Line= 3
      2724925.68      6797991.09      2724532.36      6797989.22
      2724358.77      6797764.74
#Sta/Elev= 30
  4850.7  387.54  4870.4  387.60  4900.4  386.11  4940.4  385.19  4960.4  385.41
  5000.4  382.45  5020.4  382.05  5070.4  383.15  5090.4  382.80  5120.4  383.98
  5150.4  383.61  5160.4  382.88  5168.4  381.12  5168.6  380.62  5172.1  380.62
  5172.4  381.12  5210.4  383.54  5220.4  383.41  5247.2  384.55  5268.0  383.71
  5290.7  383.93  5311.5  386.77  5326.0  387.17  5342.6  388.53  5368.2  388.83
  5411.1  391.43  5425.6  391.48  5482.0  393.85  5518.9  394.32  5527.8  394.96
#Mann=4,-1,0
  4850.7    0.05       0  5168.4    0.05       0  5172.4    0.05       0
  5342.6     0.1       0
Bank Sta=5168.4,5172.4
Exp/Cntr=0.3,0.1

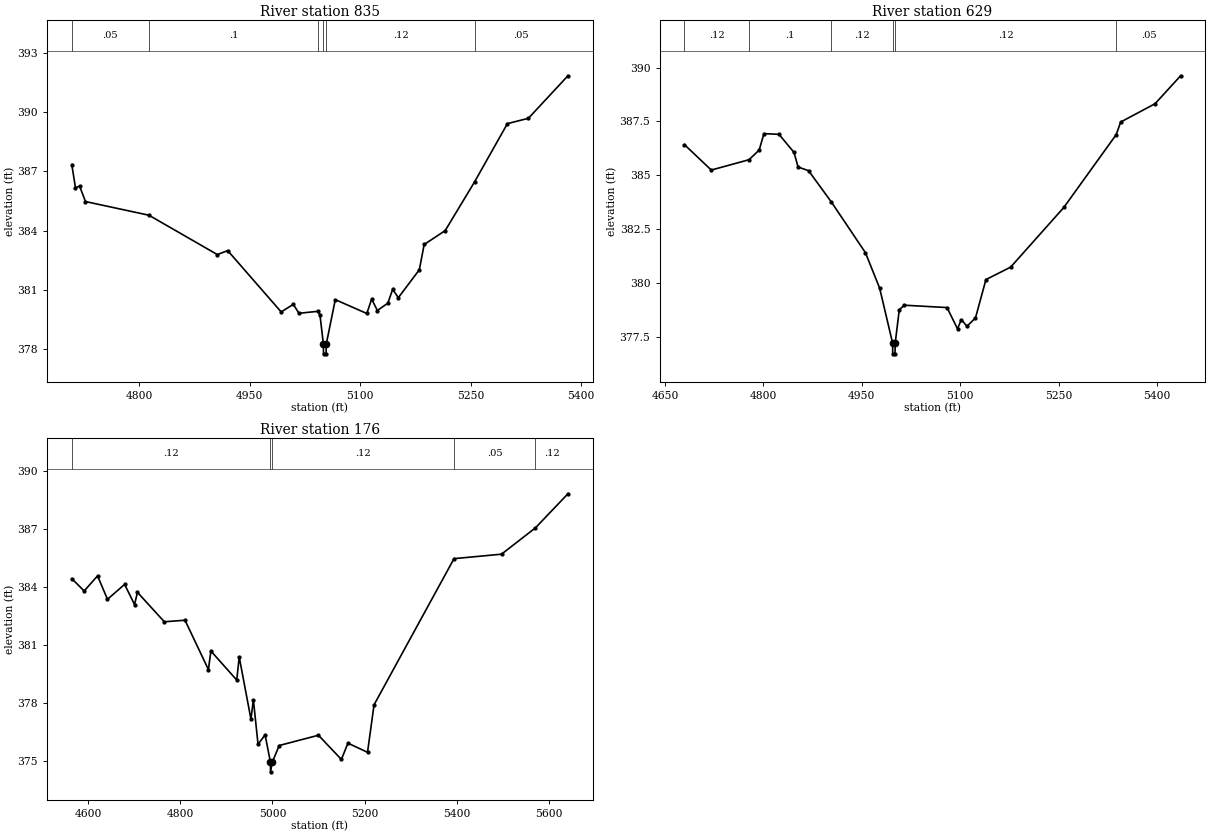
Type RM Length L Ch R = 1,835,206,206,206
BEGIN DESCRIPTION:
Lynn Creek T 13 2.0
END DESCRIPTION:
XS GIS Cut Line= 3
      2725054.64      6798017.64      2724926.00      6797761.00
      2724673.22      6797468.45
#Sta/Elev= 30
  4708.3  387.34  4713.3  386.17  4718.9  386.25  4726.9  385.47  4813.0  384.78
  4905.9  382.79  4920.0  382.99  4992.6  379.89  5009.1  380.27  5016.8  379.82
  5042.3  379.92  5045.3  379.74  5049.9  378.27  5050.1  377.77  5053.6  377.77
  5053.9  378.27  5066.1  380.51  5108.9  379.81  5115.5  380.54  5123.2  379.96
  5137.4  380.33  5144.0  381.03  5151.7  380.61  5180.2  382.02  5186.8  383.30
  5215.3  384.00  5255.3  386.47  5299.8  389.41  5328.3  389.68  5382.0  391.83
#Mann=6,-1,0
  4708.3    0.05       0  4813.0     0.1       0  5042.3    0.12       0
  5049.9    0.07       0  5053.9    0.12       0  5255.3    0.05       0
Bank Sta=5049.9,5053.9
Exp/Cntr=0.3,0.1

Type RM Length L Ch R = 1,629,453,453,453
BEGIN DESCRIPTION:
Mapping XS 4877f4bf
END DESCRIPTION:
XS GIS Cut Line= 2
      2725245.96      6797926.67      2724875.96      6797266.94
#Sta/Elev= 30
  4679.7  386.42  4720.6  385.24  4778.2  385.72  4793.6  386.17  4800.9  386.93
  4823.8  386.90  4846.7  386.06  4852.9  385.38  4868.9  385.21  4903.8  383.75
  4955.6  381.40  4977.3  379.75  4997.0  377.20  4997.2  376.70  5000.7  376.70
  5001.0  377.20  5007.2  378.75  5014.9  378.96  5080.0  378.85  5096.0  377.86
  5101.7  378.29  5110.4  377.98  5123.4  378.37  5139.3  380.15  5177.0  380.73
  5258.0  383.50  5338.0  386.89  5344.7  387.47  5397.1  388.32  5436.1  389.62
#Mann=6,-1,0
  4679.7    0.12       0  4778.2     0.1       0  4903.8    0.12       0
  4997.0    0.07       0  5001.0    0.12       0  5338.0    0.05       0
Bank Sta=4997,5001
Exp/Cntr=0.3,0.1

Type RM Length L Ch R = 1,176,0,0,0
BEGIN DESCRIPTION:
Lynn Creek T 13 1.0
END DESCRIPTION:
XS GIS Cut Line= 5
      2725272.85      6797824.18      2725384.69      6797631.83
      2725456.60      6797431.66      2725253.91      6797215.92
      2724910.69      6797181.17
#Sta/Elev= 30
  4564.8  384.42  4591.6  383.78  4620.7  384.56  4642.2  383.35  4679.4  384.12
  4700.9  383.08  4707.3  383.71  4765.5  382.19  4810.4  382.27  4861.2  379.72
  4866.5  380.68  4922.6  379.18  4928.0  380.37  4953.4  377.16  4958.7  378.16
  4968.8  375.86  4984.1  376.35  4995.7  374.94  4995.9  374.44  4999.7  374.94
  5014.8  375.80  5099.8  376.33  5149.6  375.08  5163.8  375.92  5206.3  375.45
  5220.4  377.90  5393.9  385.45  5496.9  385.68  5570.5  387.04  5641.0  388.80
#Mann=5,-1,0
  4564.8    0.12       0  4995.7    0.07       0  4999.7    0.12       0
  5393.9    0.05       0  5570.5    0.12       0
Bank Sta=4995.7,4999.7
Exp/Cntr=0.3,0.1

Chan Stop Cuts=-1