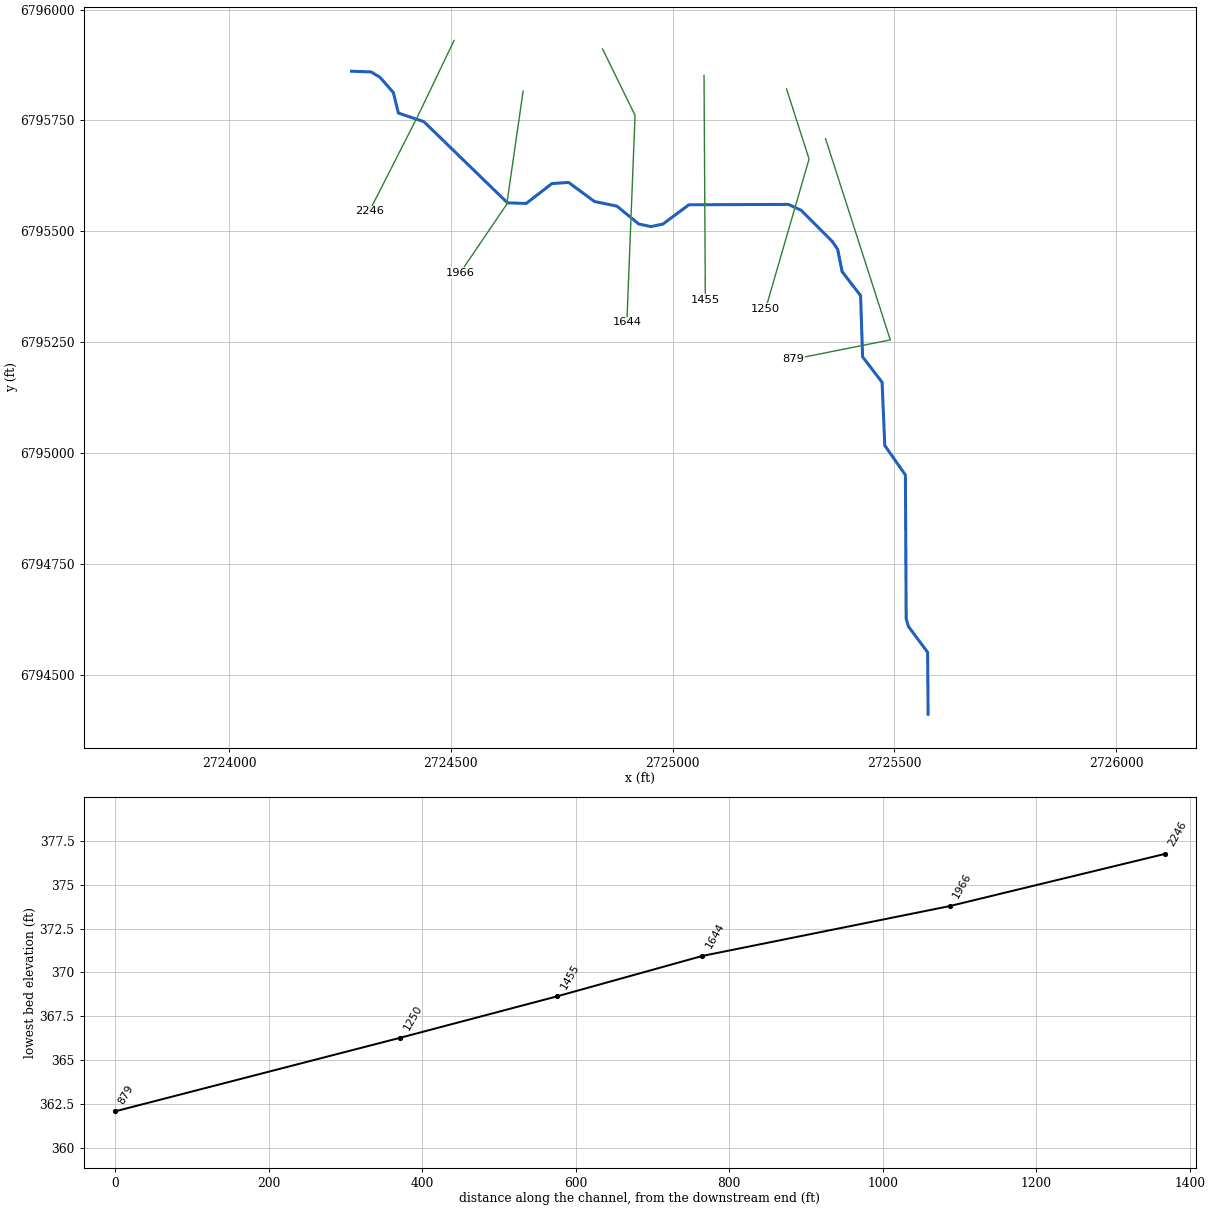
--- Lynn Creek T 14.prj (project) ---

Proj Title=Lynn Creek T 14 Base Level Engineering
Current Plan=p01
Default Exp/Contr=0.3,0.1
English Units
Geom File=g01
Flow File=f01
Plan File=p01
BEGIN DESCRIPTION:
Lynn Creek T 14
END DESCRIPTION:

--- Lynn Creek T 14.p01 (plan) ---

Plan Title=Multiple Run
Short Identifier=Multiple
Geom File=g01
Flow File=f01
Subcritical Flow
K Sum by GR= 0
Std Step Tol= 0.01
Critical Tol= 0.01
Num of Std Step Trials= 20
Max Error Tol= 0.3
Flow Tol Ratio= 0.001
Split Flow NTrial= 30
Split Flow Tol= 0.02
Split Flow Ratio= 0.02
Log Output Level= 0
Friction Slope Method= 1
Unsteady Friction Slope Method= 2
Unsteady Bridges Friction Slope Method= 1
Parabolic Critical Depth
Global Vel Dist=  1 , 1 , 1
Global Log Level= 0
CheckData=True
Encroach Param= -1, 0, 0, 0
BEGIN DESCRIPTION:
Multiple Run
END DESCRIPTION:

--- Lynn Creek T 14.f01 (steady flow) ---

Flow Title=Multiple
Number of Profiles=7
Profile Names=10-year,25-year,50-year,1pct_min,100-year,1pct_plu,500-year
River Rch & RM= Lynn Creek T 14,Reach-1,2246
     200     249     286     164     327     652     425
Boundary for River Rch & Prof#=Lynn Creek T 14,Reach-1,1
Up Type=0
Dn Type=3
Dn Slope=0.005
Boundary for River Rch & Prof#=Lynn Creek T 14,Reach-1,2
Up Type=0
Dn Type=3
Dn Slope=0.005
Boundary for River Rch & Prof#=Lynn Creek T 14,Reach-1,3
Up Type=0
Dn Type=3
Dn Slope=0.005
Boundary for River Rch & Prof#=Lynn Creek T 14,Reach-1,4
Up Type=0
Dn Type=3
Dn Slope=0.005
Boundary for River Rch & Prof#=Lynn Creek T 14,Reach-1,5
Up Type=0
Dn Type=3
Dn Slope=0.005
Boundary for River Rch & Prof#=Lynn Creek T 14,Reach-1,6
Up Type=0
Dn Type=3
Dn Slope=0.005
Boundary for River Rch & Prof#=Lynn Creek T 14,Reach-1,7
Up Type=0
Dn Type=3
Dn Slope=0.005

--- Lynn Creek T 14.g01 (geometry) ---

Geom Title=Existing Conditions

River Reach=Lynn Creek T 14,Reach-1
Reach XY= 30
      2724276.00      6795861.00      2724320.12      6795859.40
      2724339.74      6795847.64      2724370.14      6795813.14
      2724381.60      6795766.62      2724438.98      6795747.28
      2724627.63      6795564.13      2724669.87      6795562.81
      2724727.72      6795607.60      2724765.31      6795610.25
      2724823.80      6795567.15      2724874.28      6795556.78
      2724923.80      6795516.34      2724951.00      6795510.59
      2724978.18      6795516.37      2725036.50      6795559.76
      2725260.85      6795560.62      2725289.34      6795547.64
      2725359.37      6795477.71      2725372.06      6795459.38
      2725382.14      6795408.83      2725423.75      6795355.07
      2725428.27      6795216.94      2725472.21      6795159.43
      2725478.27      6795016.94      2725524.78      6794950.50
      2725526.52      6794626.22      2725531.74      6794608.66
      2725574.83      6794550.52      2725576.00      6794411.00

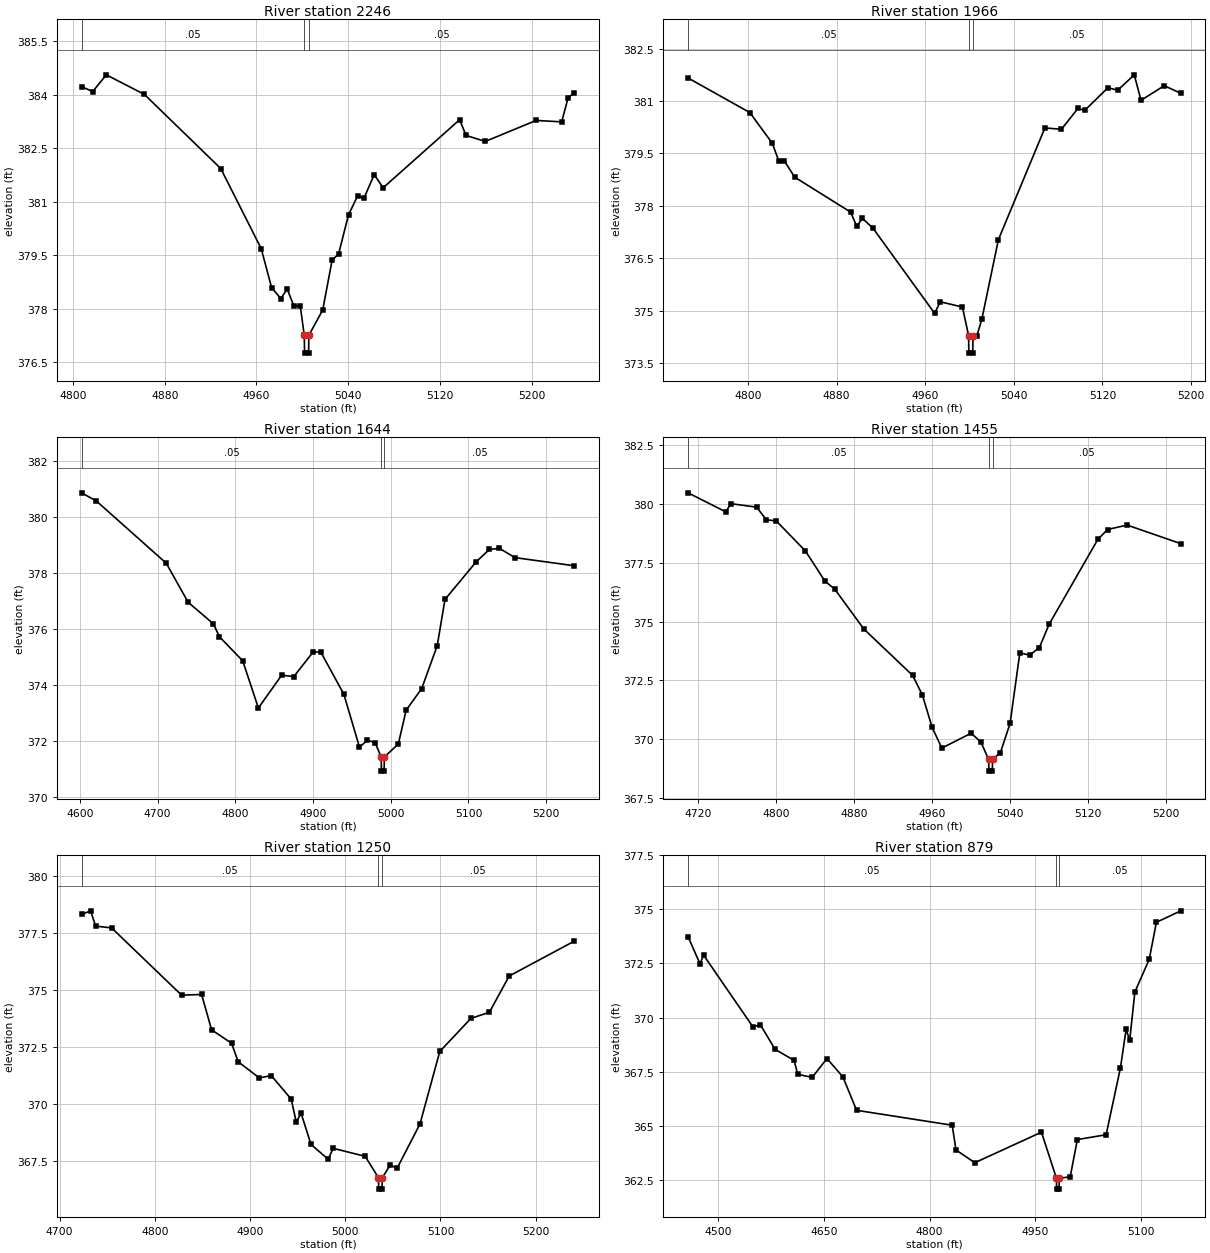
Type RM Length L Ch R = 1,2246,280,280,280
BEGIN DESCRIPTION:
Lynn Creek T 14 3.0
END DESCRIPTION:
XS GIS Cut Line= 3
      2724507.22      6795930.45      2724426.00      6795761.00
      2724316.37      6795545.49
#Sta/Elev= 30
  4807.5  384.23  4817.2  384.09  4829.1  384.56  4862.3  384.01  4928.9  381.93
  4964.2  379.68  4973.2  378.59  4981.3  378.28  4986.8  378.55  4992.6  378.08
  4998.2  378.08  5001.7  377.25  5002.0  376.75  5005.5  376.75  5005.7  377.25
  5017.8  377.96  5026.0  379.36  5031.6  379.53  5040.3  380.63  5048.2  381.16
  5053.8  381.10  5062.7  381.76  5070.5  381.39  5137.2  383.30  5142.8  382.86
  5159.5  382.69  5203.9  383.28  5226.2  383.24  5231.8  383.92  5237.2  384.05
#Mann=3,-1,0
  4807.5    0.05       0  5001.7    0.04       0  5005.7    0.05       0
Bank Sta=5001.7,5005.7
Exp/Cntr=0.3,0.1

Type RM Length L Ch R = 1,1966,322,322,322
BEGIN DESCRIPTION:
Lynn Creek T 14 2.0
END DESCRIPTION:
XS GIS Cut Line= 3
      2724662.86      6795816.27      2724626.00      6795561.00
      2724520.84      6795406.28
#Sta/Elev= 30
  4745.8  381.66  4801.6  380.67  4821.9  379.79  4827.8  379.28  4832.9  379.28
  4842.1  378.82  4892.6  377.82  4898.2  377.41  4903.2  377.64  4912.8  377.36
  4968.5  374.92  4973.6  375.25  4993.6  375.10  4999.2  374.28  4999.4  373.78
  5002.9  373.78  5003.2  374.28  5006.7  374.28  5011.2  374.76  5026.1  377.03
  5068.1  380.23  5083.0  380.19  5098.0  380.79  5104.0  380.73  5125.0  381.38
  5133.9  381.31  5148.8  381.75  5154.9  381.02  5175.9  381.44  5190.8  381.22
#Mann=3,-1,0
  4745.8    0.05       0  4999.2    0.04       0  5003.2    0.05       0
Bank Sta=4999.2,5003.2
Exp/Cntr=0.3,0.1

Type RM Length L Ch R = 1,1644,189,189,189
BEGIN DESCRIPTION:
Mapping XS 01746f9a
END DESCRIPTION:
XS GIS Cut Line= 3
      2724841.85      6795911.41      2724915.22      6795761.58
      2724896.76      6795294.78
#Sta/Elev= 30
  4602.2  380.86  4621.2  380.57  4711.2  378.35  4739.3  376.96  4771.8  376.19
  4779.6  375.73  4809.6  374.87  4829.7  373.19  4859.7  374.36  4875.3  374.31
  4899.7  375.17  4909.7  375.20  4939.7  373.68  4959.8  371.79  4969.8  372.04
  4979.8  371.96  4987.8  371.44  4988.0  370.94  4991.5  370.94  4991.8  371.44
  5009.8  371.91  5019.8  373.11  5039.8  373.88  5059.8  375.41  5069.8  377.06
  5109.9  378.40  5126.9  378.84  5139.9  378.88  5159.9  378.55  5236.2  378.26
#Mann=3,-1,0
  4602.2    0.05       0  4987.8    0.04       0  4991.8    0.05       0
Bank Sta=4987.8,4991.8
Exp/Cntr=0.3,0.1

Type RM Length L Ch R = 1,1455,205,205,205
BEGIN DESCRIPTION:
Mapping XS e4080591
END DESCRIPTION:
XS GIS Cut Line= 2
      2725070.75      6795851.40      2725073.71      6795345.91
#Sta/Elev= 30
  4710.0  380.47  4748.8  379.66  4753.8  380.01  4780.4  379.86  4790.4  379.32
  4800.4  379.28  4830.4  378.00  4850.4  376.72  4860.4  376.38  4890.4  374.68
  4940.4  372.71  4950.4  371.88  4960.4  370.50  4970.4  369.62  5000.4  370.25
  5010.4  369.88  5018.4  369.14  5018.7  368.64  5022.2  368.64  5022.4  369.14
  5030.4  369.42  5040.4  370.67  5050.4  373.67  5060.4  373.57  5070.4  373.89
  5080.4  374.88  5130.4  378.49  5140.4  378.91  5160.4  379.10  5215.5  378.31
#Mann=3,-1,0
  4710.0    0.05       0  5018.4    0.04       0  5022.4    0.05       0
Bank Sta=5018.4,5022.4
Exp/Cntr=0.3,0.1

Type RM Length L Ch R = 1,1250,371,371,371
BEGIN DESCRIPTION:
Mapping XS a65c678d
END DESCRIPTION:
XS GIS Cut Line= 3
      2725256.82      6795821.08      2725307.58      6795662.96
      2725209.72      6795325.32
#Sta/Elev= 30
  4723.0  378.32  4732.5  378.48  4737.8  377.81  4754.6  377.73  4828.1  374.78
  4849.1  374.81  4859.6  373.26  4880.6  372.67  4887.5  371.86  4909.7  371.15
  4922.3  371.25  4943.2  370.22  4948.5  369.22  4953.7  369.59  4964.0  368.23
  4982.1  367.58  4987.3  368.06  5020.9  367.71  5034.9  366.77  5035.1  366.27
  5038.6  366.27  5038.9  366.77  5047.3  367.33  5054.4  367.18  5078.5  369.13
  5099.3  372.31  5132.0  373.76  5151.4  374.03  5172.2  375.62  5240.6  377.15
#Mann=3,-1,0
  4723.0    0.05       0  5034.9    0.04       0  5038.9    0.05       0
Bank Sta=5034.9,5038.9
Exp/Cntr=0.3,0.1

Type RM Length L Ch R = 1,879,0,0,0
BEGIN DESCRIPTION:
Lynn Creek T 14 1.0
END DESCRIPTION:
XS GIS Cut Line= 3
      2725344.77      6795708.81      2725490.68      6795255.06
      2725272.03      6795211.37
#Sta/Elev= 30
  4457.1  373.74  4474.0  372.49  4479.3  372.88  4549.3  369.57  4559.8  369.67
  4580.8  368.53  4607.6  368.03  4612.9  367.38  4633.4  367.24  4654.4  368.11
  4677.0  367.26  4696.4  365.72  4832.2  365.03  4837.5  363.89  4864.3  363.30
  4958.9  364.71  4980.2  362.58  4980.4  362.08  4983.9  362.08  4984.2  362.58
  4999.7  362.65  5009.9  364.37  5050.7  364.59  5071.1  367.69  5079.1  369.46
  5084.2  368.95  5091.5  371.18  5111.9  372.69  5122.1  374.40  5156.7  374.93
#Mann=3,-1,0
  4457.1    0.05       0  4980.2    0.04       0  4984.2    0.05       0
Bank Sta=4980.2,4984.2
Exp/Cntr=0.3,0.1

Chan Stop Cuts=-1