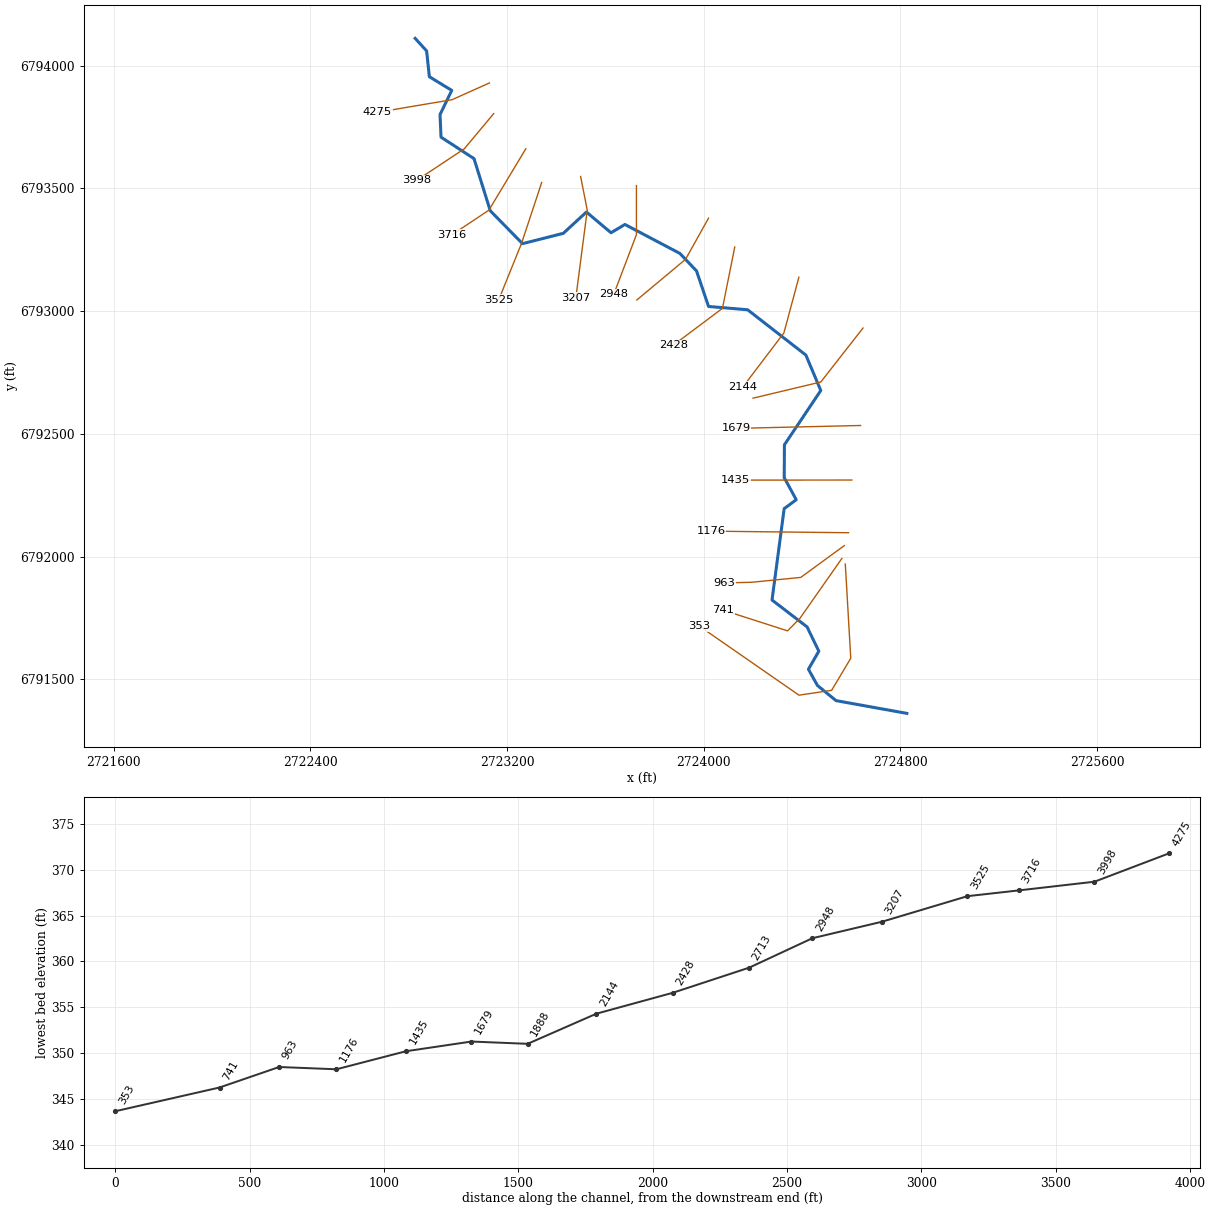
--- Lynn Creek T 15.prj (project) ---

Proj Title=Lynn Creek T 15 Base Level Engineering
Current Plan=p01
Default Exp/Contr=0.3,0.1
English Units
Geom File=g01
Flow File=f01
Plan File=p01
BEGIN DESCRIPTION:
Lynn Creek T 15
END DESCRIPTION:

--- Lynn Creek T 15.p01 (plan) ---

Plan Title=Multiple Run
Short Identifier=Multiple
Geom File=g01
Flow File=f01
Subcritical Flow
K Sum by GR= 0
Std Step Tol= 0.01
Critical Tol= 0.01
Num of Std Step Trials= 20
Max Error Tol= 0.3
Flow Tol Ratio= 0.001
Split Flow NTrial= 30
Split Flow Tol= 0.02
Split Flow Ratio= 0.02
Log Output Level= 0
Friction Slope Method= 1
Unsteady Friction Slope Method= 2
Unsteady Bridges Friction Slope Method= 1
Parabolic Critical Depth
Global Vel Dist=  1 , 1 , 1
Global Log Level= 0
CheckData=True
Encroach Param= -1, 0, 0, 0
BEGIN DESCRIPTION:
Multiple Run
END DESCRIPTION:

--- Lynn Creek T 15.f01 (steady flow) ---

Flow Title=Multiple
Number of Profiles=7
Profile Names=10-year,25-year,50-year,1pct_min,100-year,1pct_plu,500-year
River Rch & RM= Lynn Creek T 15,Reach-1,4275
     385     501     592     348     695    1387     955
Boundary for River Rch & Prof#=Lynn Creek T 15,Reach-1,1
Up Type=0
Dn Type=3
Dn Slope=0.005
Boundary for River Rch & Prof#=Lynn Creek T 15,Reach-1,2
Up Type=0
Dn Type=3
Dn Slope=0.005
Boundary for River Rch & Prof#=Lynn Creek T 15,Reach-1,3
Up Type=0
Dn Type=3
Dn Slope=0.005
Boundary for River Rch & Prof#=Lynn Creek T 15,Reach-1,4
Up Type=0
Dn Type=3
Dn Slope=0.005
Boundary for River Rch & Prof#=Lynn Creek T 15,Reach-1,5
Up Type=0
Dn Type=3
Dn Slope=0.005
Boundary for River Rch & Prof#=Lynn Creek T 15,Reach-1,6
Up Type=0
Dn Type=3
Dn Slope=0.005
Boundary for River Rch & Prof#=Lynn Creek T 15,Reach-1,7
Up Type=0
Dn Type=3
Dn Slope=0.005

--- Lynn Creek T 15.g01 (geometry) ---

Geom Title=Existing Conditions

River Reach=Lynn Creek T 15,Reach-1
Reach XY= 30
      2722826.00      6794111.00      2722872.61      6794059.59
      2722883.78      6793954.55      2722974.81      6793898.98
      2722927.13      6793800.47      2722931.30      6793708.33
      2723065.37      6793621.00      2723131.52      6793408.57
      2723262.62      6793274.53      2723428.43      6793316.55
      2723522.67      6793403.38      2723622.66      6793319.02
      2723679.23      6793352.75      2723902.89      6793234.74
      2723970.48      6793163.44      2724019.48      6793018.68
      2724178.35      6793005.29      2724415.24      6792820.68
      2724475.93      6792676.39      2724328.05      6792455.14
      2724327.23      6792321.48      2724376.06      6792231.44
      2724327.00      6792195.06      2724277.61      6791822.83
      2724420.20      6791713.30      2724467.93      6791614.31
      2724425.73      6791540.77      2724462.51      6791474.55
      2724537.95      6791412.93      2724826.00      6791361.00

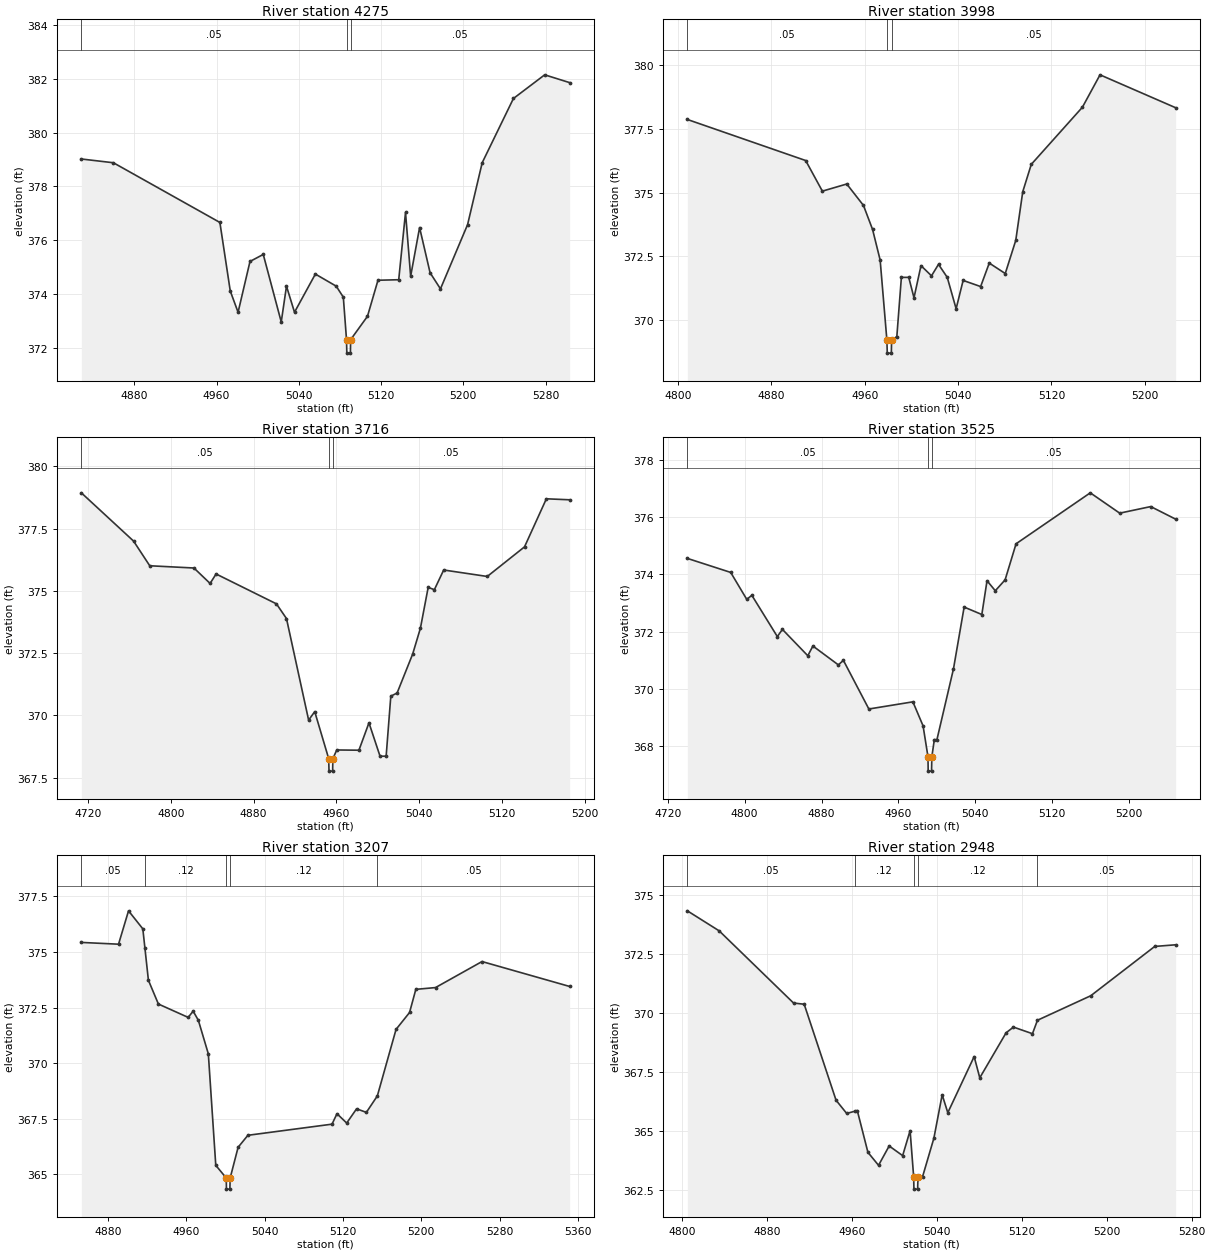
Type RM Length L Ch R = 1,4275,277,277,277
BEGIN DESCRIPTION:
Lynn Creek T 15 11.0
END DESCRIPTION:
XS GIS Cut Line= 3
      2723128.23      6793929.30      2722976.00      6793861.00
      2722672.07      6793809.61
#Sta/Elev= 30
  4828.4  379.02  4859.6  378.88  4963.2  376.66  4973.3  374.11  4980.9  373.32
  4992.5  375.21  5005.4  375.47  5022.9  372.96  5028.0  374.29  5035.8  373.32
  5056.1  374.74  5076.4  374.29  5083.3  373.88  5086.4  372.30  5086.7  371.80
  5090.2  371.80  5090.4  372.30  5106.8  373.17  5117.0  374.51  5137.2  374.53
  5143.8  377.03  5148.8  374.66  5157.5  376.47  5167.7  374.79  5177.8  374.19
  5204.2  376.58  5218.4  378.88  5248.8  381.27  5279.2  382.15  5303.5  381.86
#Mann=3,-1,0
  4828.4    0.05       0  5086.4    0.03       0  5090.4    0.05       0
Bank Sta=5086.4,5090.4
Exp/Cntr=0.3,0.1

Type RM Length L Ch R = 1,3998,282,282,282
BEGIN DESCRIPTION:
Lynn Creek T 15 10.0
END DESCRIPTION:
XS GIS Cut Line= 3
      2723145.51      6793804.41      2723026.00      6793661.00
      2722832.96      6793532.81
#Sta/Elev= 30
  4808.0  377.87  4909.4  376.26  4923.7  375.06  4944.6  375.34  4958.9  374.50
  4966.7  373.56  4973.2  372.36  4979.0  369.21  4979.3  368.71  4982.8  368.71
  4983.0  369.21  4987.5  369.36  4991.4  371.68  4997.7  371.68  5002.2  370.88
  5008.2  372.14  5017.2  371.74  5023.2  372.19  5030.7  371.68  5038.3  370.45
  5044.3  371.56  5059.3  371.32  5066.7  372.24  5080.4  371.83  5089.4  373.13
  5095.4  375.04  5102.7  376.11  5146.5  378.35  5161.6  379.62  5226.4  378.33
#Mann=3,-1,0
  4808.0    0.05       0  4979.0    0.04       0  4983.0    0.05       0
Bank Sta=4979,4983
Exp/Cntr=0.3,0.1

Type RM Length L Ch R = 1,3716,191,191,191
BEGIN DESCRIPTION:
Lynn Creek T 15 9.0
END DESCRIPTION:
XS GIS Cut Line= 3
      2723276.00      6793660.99      2723126.00      6793411.00
      2722976.01      6793311.01
#Sta/Elev= 30
  4713.6  378.94  4764.1  377.00  4779.7  376.01  4822.4  375.92  4838.0  375.30
  4843.8  375.68  4902.1  374.48  4911.8  373.89  4933.2  369.81  4939.1  370.15
  4952.6  368.26  4952.9  367.76  4956.4  367.76  4956.6  368.26  4960.4  368.61
  4981.8  368.60  4991.5  369.70  5002.2  368.36  5008.1  368.36  5012.6  370.77
  5018.7  370.90  5033.7  372.46  5041.2  373.50  5048.7  375.14  5054.7  375.05
  5063.7  375.84  5105.8  375.58  5141.8  376.77  5162.9  378.70  5185.4  378.66
#Mann=3,-1,0
  4713.6    0.05       0  4952.6    0.04       0  4956.6    0.05       0
Bank Sta=4952.6,4956.6
Exp/Cntr=0.3,0.1

Type RM Length L Ch R = 1,3525,318,318,318
BEGIN DESCRIPTION:
Lynn Creek T 15 8.0
END DESCRIPTION:
XS GIS Cut Line= 3
      2723340.70      6793523.80      2723259.29      6793277.29
      2723166.43      6793047.01
#Sta/Elev= 30
  4740.4  374.56  4785.5  374.07  4802.2  373.13  4807.5  373.27  4834.0  371.83
  4839.3  372.08  4865.7  371.16  4871.0  371.50  4897.5  370.84  4902.7  371.00
  4929.2  369.30  4975.0  369.55  4985.6  368.71  4990.7  367.63  4990.9  367.13
  4994.4  367.13  4994.7  367.63  4997.3  368.23  5000.0  368.23  5017.2  370.70
  5028.3  372.86  5046.7  372.60  5052.1  373.78  5060.7  373.43  5070.9  373.81
  5082.3  375.07  5159.5  376.85  5190.1  376.14  5222.4  376.37  5248.3  375.93
#Mann=3,-1,0
  4740.4    0.05       0  4990.7    0.04       0  4994.7    0.05       0
Bank Sta=4990.7,4994.7
Exp/Cntr=0.3,0.1

Type RM Length L Ch R = 1,3207,259,259,259
BEGIN DESCRIPTION:
Lynn Creek T 15 7.0
END DESCRIPTION:
XS GIS Cut Line= 3
      2723499.03      6793548.26      2723526.00      6793411.00
      2723479.74      6793055.18
#Sta/Elev= 30
  4852.8  375.43  4890.8  375.35  4901.0  376.85  4915.6  376.04  4917.7  375.19
  4921.3  373.73  4931.5  372.66  4961.9  372.06  4967.0  372.34  4972.3  371.93
  4982.5  370.42  4990.1  365.41  5000.8  364.84  5001.0  364.34  5004.5  364.34
  5004.8  364.84  5012.9  366.22  5022.9  366.76  5108.8  367.26  5113.9  367.73
  5123.8  367.31  5133.9  367.95  5143.9  367.79  5155.1  368.53  5174.2  371.52
  5188.0  372.28  5194.4  373.32  5214.5  373.40  5262.0  374.57  5351.5  373.45
#Mann=5,-1,0
  4852.8    0.05       0  4917.7    0.12       0  5000.8    0.07       0
  5004.8    0.12       0  5155.1    0.05       0
Bank Sta=5000.8,5004.8
Exp/Cntr=0.3,0.1

Type RM Length L Ch R = 1,2948,235,235,235
BEGIN DESCRIPTION:
Lynn Creek T 15 6.0
END DESCRIPTION:
XS GIS Cut Line= 3
      2723726.00      6793511.03      2723726.00      6793311.00
      2723633.78      6793068.26
#Sta/Elev= 30
  4805.2  374.34  4835.2  373.49  4905.2  370.43  4915.2  370.38  4945.2  366.31
  4955.2  365.75  4962.7  365.84  4965.2  365.87  4975.2  364.10  4985.2  363.55
  4995.2  364.37  5007.9  363.96  5014.9  365.02  5018.3  363.04  5018.5  362.54
  5022.0  362.54  5022.3  363.04  5026.6  363.06  5037.3  364.70  5045.1  366.54
  5050.4  365.78  5075.2  368.16  5080.5  367.26  5105.3  369.17  5112.2  369.41
  5130.1  369.13  5134.8  369.70  5185.0  370.74  5245.2  372.83  5264.9  372.90
#Mann=5,-1,0
  4805.2    0.05       0  4962.7    0.12       0  5018.3    0.07       0
  5022.3    0.12       0  5134.8    0.05       0
Bank Sta=5018.3,5022.3
Exp/Cntr=0.3,0.1

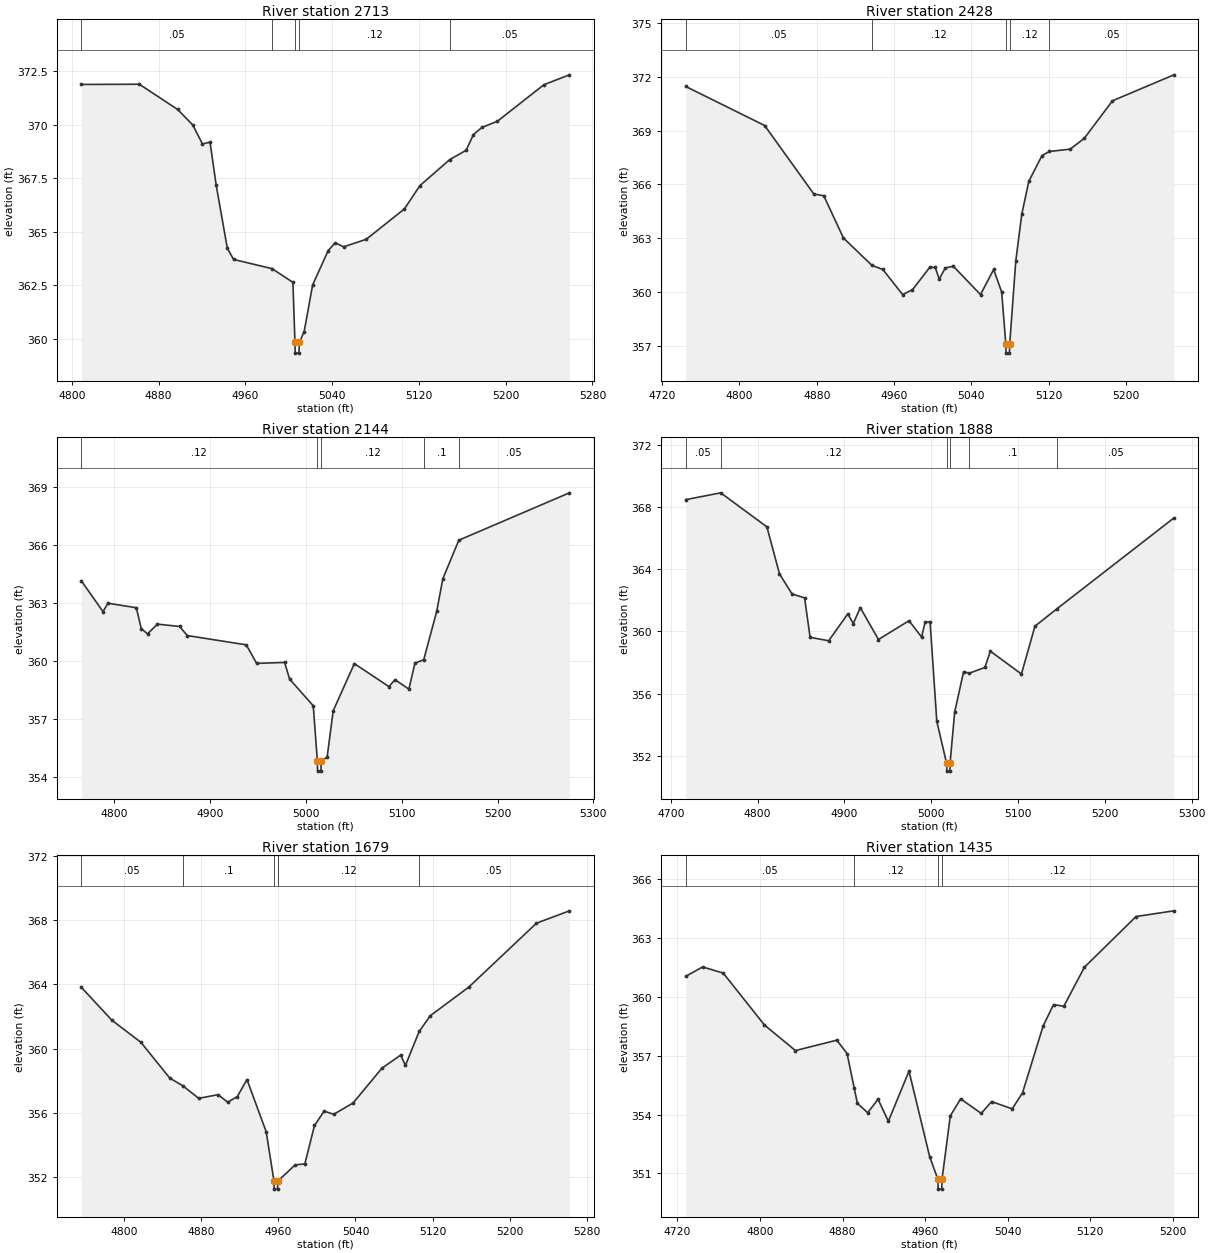
Type RM Length L Ch R = 1,2713,285,285,285
BEGIN DESCRIPTION:
Lynn Creek T 15 5.0
END DESCRIPTION:
XS GIS Cut Line= 3
      2724019.37      6793378.56      2723926.00      6793211.00
      2723727.95      6793045.22
#Sta/Elev= 30
  4808.7  371.89  4862.2  371.90  4897.5  370.72  4911.4  370.00  4920.4  369.11
  4927.4  369.19  4933.1  367.17  4943.3  364.24  4949.1  363.71  4984.5  363.28
  5003.8  362.64  5005.7  359.83  5005.9  359.33  5009.4  359.33  5009.7  359.83
  5014.2  360.34  5022.0  362.52  5036.3  364.12  5042.8  364.49  5050.6  364.30
  5071.4  364.65  5106.6  366.07  5120.9  367.16  5148.5  368.38  5163.5  368.81
  5170.3  369.55  5178.1  369.88  5192.4  370.17  5235.3  371.88  5258.8  372.34
#Mann=5,-1,0
  4808.7    0.05       0  4984.5    0.12       0  5005.7    0.07       0
  5009.7    0.12       0  5148.5    0.05       0
Bank Sta=5005.7,5009.7
Exp/Cntr=0.3,0.1

Type RM Length L Ch R = 1,2428,284,284,284
BEGIN DESCRIPTION:
Lynn Creek T 15 4.0
END DESCRIPTION:
XS GIS Cut Line= 3
      2724126.00      6793260.98      2724076.00      6793011.00
      2723876.03      6792861.02
#Sta/Elev= 30
  4744.5  371.47  4826.1  369.29  4877.1  365.46  4887.3  365.37  4907.6  363.01
  4937.1  361.48  4948.4  361.25  4968.8  359.85  4979.0  360.12  4996.9  361.37
  5002.6  361.37  5006.7  360.71  5013.0  361.34  5021.3  361.43  5049.4  359.85
  5063.0  361.25  5071.3  359.99  5075.6  357.08  5075.8  356.58  5079.3  356.58
  5079.6  357.08  5085.9  361.73  5092.1  364.34  5099.4  366.18  5113.0  367.61
  5120.6  367.84  5142.1  367.97  5156.7  368.57  5185.9  370.67  5249.4  372.12
#Mann=5,-1,0
  4744.5    0.05       0  4937.1    0.12       0  5075.6    0.07       0
  5079.6    0.12       0  5120.6    0.05       0
Bank Sta=5075.6,5079.6
Exp/Cntr=0.3,0.1

Type RM Length L Ch R = 1,2144,256,256,256
BEGIN DESCRIPTION:
Lynn Creek T 15 3.0
END DESCRIPTION:
XS GIS Cut Line= 3
      2724386.90      6793137.77      2724326.00      6792911.00
      2724159.97      6792692.16
#Sta/Elev= 30
  4765.5  364.14  4788.1  362.55  4793.3  362.98  4822.9  362.75  4828.1  361.66
  4834.6  361.40  4845.0  361.90  4868.1  361.78  4876.1  361.31  4937.7  360.83
  4948.5  359.87  4977.7  359.92  4982.9  359.06  5007.6  357.68  5011.9  354.80
  5012.1  354.30  5015.6  354.30  5015.9  354.80  5022.1  355.03  5028.4  357.42
  5050.5  359.86  5086.6  358.67  5092.9  359.03  5107.4  358.54  5113.7  359.88
  5122.9  360.06  5136.5  362.57  5142.8  364.24  5159.5  366.24  5275.0  368.69
#Mann=5,-1,0
  4765.5    0.12       0  5011.9    0.07       0  5015.9    0.12       0
  5122.9     0.1       0  5159.5    0.05       0
Bank Sta=5011.9,5015.9
Exp/Cntr=0.3,0.1

Type RM Length L Ch R = 1,1888,209,209,209
BEGIN DESCRIPTION:
Lynn Creek T 15 2.0
END DESCRIPTION:
XS GIS Cut Line= 3
      2724647.71      6792930.82      2724476.00      6792711.00
      2724200.39      6792645.17
#Sta/Elev= 30
  4717.2  368.48  4757.5  368.92  4810.7  366.73  4825.2  363.70  4839.7  362.41
  4854.1  362.16  4860.5  359.62  4881.9  359.40  4903.9  361.13  4910.2  360.51
  4918.3  361.53  4939.2  359.48  4974.4  360.69  4988.9  359.64  4993.0  360.61
  4998.7  360.61  5006.4  354.22  5017.7  351.51  5018.0  351.01  5021.5  351.01
  5021.7  351.51  5027.0  354.81  5037.3  357.41  5043.7  357.31  5061.8  357.68
  5068.1  358.73  5103.9  357.26  5119.5  360.34  5144.9  361.46  5279.5  367.30
#Mann=6,-1,0
  4717.2    0.05       0  4757.5    0.12       0  5017.7    0.07       0
  5021.7    0.12       0  5043.7     0.1       0  5144.9    0.05       0
Bank Sta=5017.7,5021.7
Exp/Cntr=0.3,0.1

Type RM Length L Ch R = 1,1679,244,244,244
BEGIN DESCRIPTION:
Mapping XS ea80092c
END DESCRIPTION:
XS GIS Cut Line= 2
      2724637.65      6792533.81      2724131.78      6792522.03
#Sta/Elev= 30
  4755.8  363.82  4787.5  361.77  4817.5  360.40  4847.5  358.17  4860.8  357.70
  4877.5  356.91  4897.5  357.14  4907.5  356.67  4917.5  357.02  4927.5  358.08
  4947.5  354.82  4955.5  351.76  4955.7  351.26  4959.2  351.26  4959.5  351.76
  4959.7  351.77  4977.5  352.77  4987.5  352.83  4997.5  355.22  5007.5  356.11
  5017.5  355.92  5037.5  356.62  5067.5  358.79  5086.8  359.60  5091.8  358.96
  5106.0  361.07  5117.5  362.05  5157.6  363.84  5227.6  367.81  5261.8  368.58
#Mann=6,-1,0
  4755.8    0.05       0  4860.8     0.1       0  4955.5    0.07       0
  4959.5     0.1       0  4959.7    0.12       0  5106.0    0.05       0
Bank Sta=4955.5,4959.5
Exp/Cntr=0.3,0.1

Type RM Length L Ch R = 1,1435,259,259,259
BEGIN DESCRIPTION:
Mapping XS 76edbe82
END DESCRIPTION:
XS GIS Cut Line= 2
      2724602.28      6792311.54      2724129.38      6792311.32
#Sta/Elev= 30
  4728.1  361.04  4744.4  361.52  4764.4  361.21  4804.4  358.56  4834.4  357.26
  4874.4  357.79  4884.4  357.11  4891.4  355.33  4894.4  354.57  4904.4  354.09
  4914.4  354.78  4924.4  353.66  4944.4  356.21  4964.4  351.86  4972.4  350.70
  4972.6  350.20  4976.1  350.20  4976.4  350.70  4984.4  353.93  4994.4  354.80
  5014.4  354.06  5024.4  354.66  5044.4  354.29  5054.4  355.11  5074.4  358.52
  5084.4  359.60  5094.4  359.52  5114.4  361.51  5164.4  364.09  5201.0  364.38
#Mann=4,-1,0
  4728.1    0.05       0  4891.4    0.12       0  4972.4    0.07       0
  4976.4    0.12       0
Bank Sta=4972.4,4976.4
Exp/Cntr=0.3,0.1

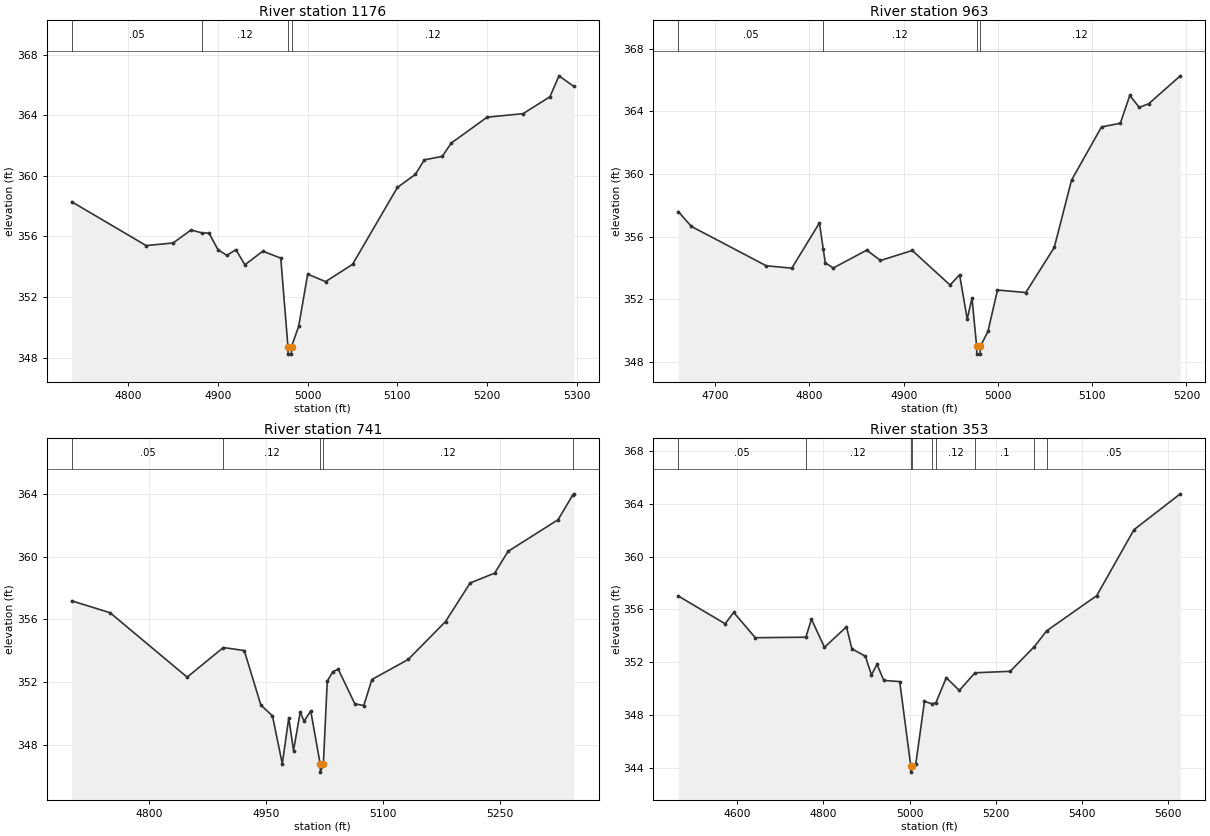
Type RM Length L Ch R = 1,1176,213,213,213
BEGIN DESCRIPTION:
Mapping XS d1b8ee3d
END DESCRIPTION:
XS GIS Cut Line= 2
      2724588.85      6792096.92      2724029.38      6792103.32
#Sta/Elev= 30
  4737.2  358.29  4820.1  355.40  4850.1  355.57  4870.1  356.43  4882.0  356.24
  4890.1  356.22  4900.1  355.13  4910.1  354.75  4920.1  355.13  4930.1  354.13
  4950.1  355.03  4970.1  354.57  4978.1  348.73  4978.3  348.23  4981.8  348.23
  4982.1  348.73  4990.1  350.08  5000.1  353.51  5020.1  353.02  5050.1  354.16
  5100.1  359.24  5120.1  360.10  5130.1  361.06  5150.1  361.29  5160.1  362.17
  5200.1  363.88  5240.1  364.11  5270.1  365.23  5280.1  366.61  5296.7  365.91
#Mann=4,-1,0
  4737.2    0.05       0  4882.0    0.12       0  4978.1    0.07       0
  4982.1    0.12       0
Bank Sta=4978.1,4982.1
Exp/Cntr=0.3,0.1

Type RM Length L Ch R = 1,963,222,222,222
BEGIN DESCRIPTION:
Mapping XS 7bfde603
END DESCRIPTION:
XS GIS Cut Line= 4
      2724571.73      6792044.57      2724394.51      6791914.88
      2724194.52      6791895.07      2724082.42      6791892.47
#Sta/Elev= 30
  4660.8  357.60  4674.7  356.65  4754.2  354.13  4781.3  353.98  4810.6  356.87
  4814.7  355.18  4816.8  354.32  4825.3  353.99  4860.8  355.13  4875.4  354.47
  4909.1  355.11  4949.2  352.90  4959.3  353.56  4967.4  350.73  4972.5  352.06
  4977.4  348.98  4977.6  348.48  4981.1  348.48  4981.4  348.98  4989.4  349.93
  4999.5  352.58  5029.6  352.42  5059.8  355.31  5078.1  359.61  5109.9  363.01
  5129.9  363.25  5139.9  365.03  5149.9  364.26  5159.9  364.49  5193.5  366.28
#Mann=4,-1,0
  4660.8    0.05       0  4814.7    0.12       0  4977.4    0.07       0
  4981.4    0.12       0
Bank Sta=4977.4,4981.4
Exp/Cntr=0.3,0.1

Type RM Length L Ch R = 1,741,388,388,388
BEGIN DESCRIPTION:
Mapping XS 8d653eb5
END DESCRIPTION:
XS GIS Cut Line= 4
      2724561.90      6791992.38      2724391.04      6791748.12
      2724340.73      6791697.16      2724079.28      6791781.42
#Sta/Elev= 30
  4700.8  357.17  4750.0  356.41  4848.9  352.30  4895.3  354.19  4922.2  354.00
  4943.5  350.52  4958.4  349.83  4971.0  346.77  4979.3  349.70  4985.4  347.62
  4994.1  350.09  4998.9  349.48  5007.5  350.15  5019.7  346.74  5019.9  346.24
  5023.7  346.74  5028.7  352.04  5035.8  352.65  5042.8  352.81  5064.1  350.60
  5075.6  350.49  5086.0  352.15  5132.6  353.43  5180.5  355.85  5212.1  358.31
  5243.6  358.94  5260.8  360.33  5325.0  362.35  5343.6  363.91  5345.2  364.00
#Mann=5,-1,0
  4700.8    0.05       0  4895.3    0.12       0  5019.7    0.07       0
  5023.7    0.12       0  5343.6    0.05       0
Bank Sta=5019.7,5023.7
Exp/Cntr=0.3,0.1

Type RM Length L Ch R = 1,353,0,0,0
BEGIN DESCRIPTION:
Lynn Creek T 15 1.0
END DESCRIPTION:
XS GIS Cut Line= 5
      2724575.69      6791969.52      2724597.87      6791585.54
      2724520.16      6791454.93      2724387.31      6791435.17
      2723981.83      6791716.63
#Sta/Elev= 30
  4463.4  357.02  4572.1  354.91  4592.1  355.77  4642.2  353.85  4759.5  353.89
  4772.4  355.26  4802.5  353.12  4853.6  354.68  4866.1  353.01  4897.3  352.45
  4911.5  351.03  4924.5  351.83  4940.1  350.61  4977.1  350.52  5002.6  344.15
  5002.9  343.65  5006.6  344.15  5014.3  344.25  5034.5  349.02  5051.2  348.84
  5060.8  348.90  5085.1  350.82  5115.4  349.85  5151.7  351.19  5233.3  351.30
  5289.5  353.18  5317.8  354.37  5434.0  357.04  5520.5  362.05  5627.9  364.77
#Mann=9,-1,0
  4463.4    0.05       0  4759.5    0.12       0  5002.6    0.07       0
  5006.6    0.12       0  5051.2     0.1       0  5060.8    0.12       0
  5151.7     0.1       0  5289.5    0.12       0  5317.8    0.05       0
Bank Sta=5002.6,5006.6
Exp/Cntr=0.3,0.1

Chan Stop Cuts=-1