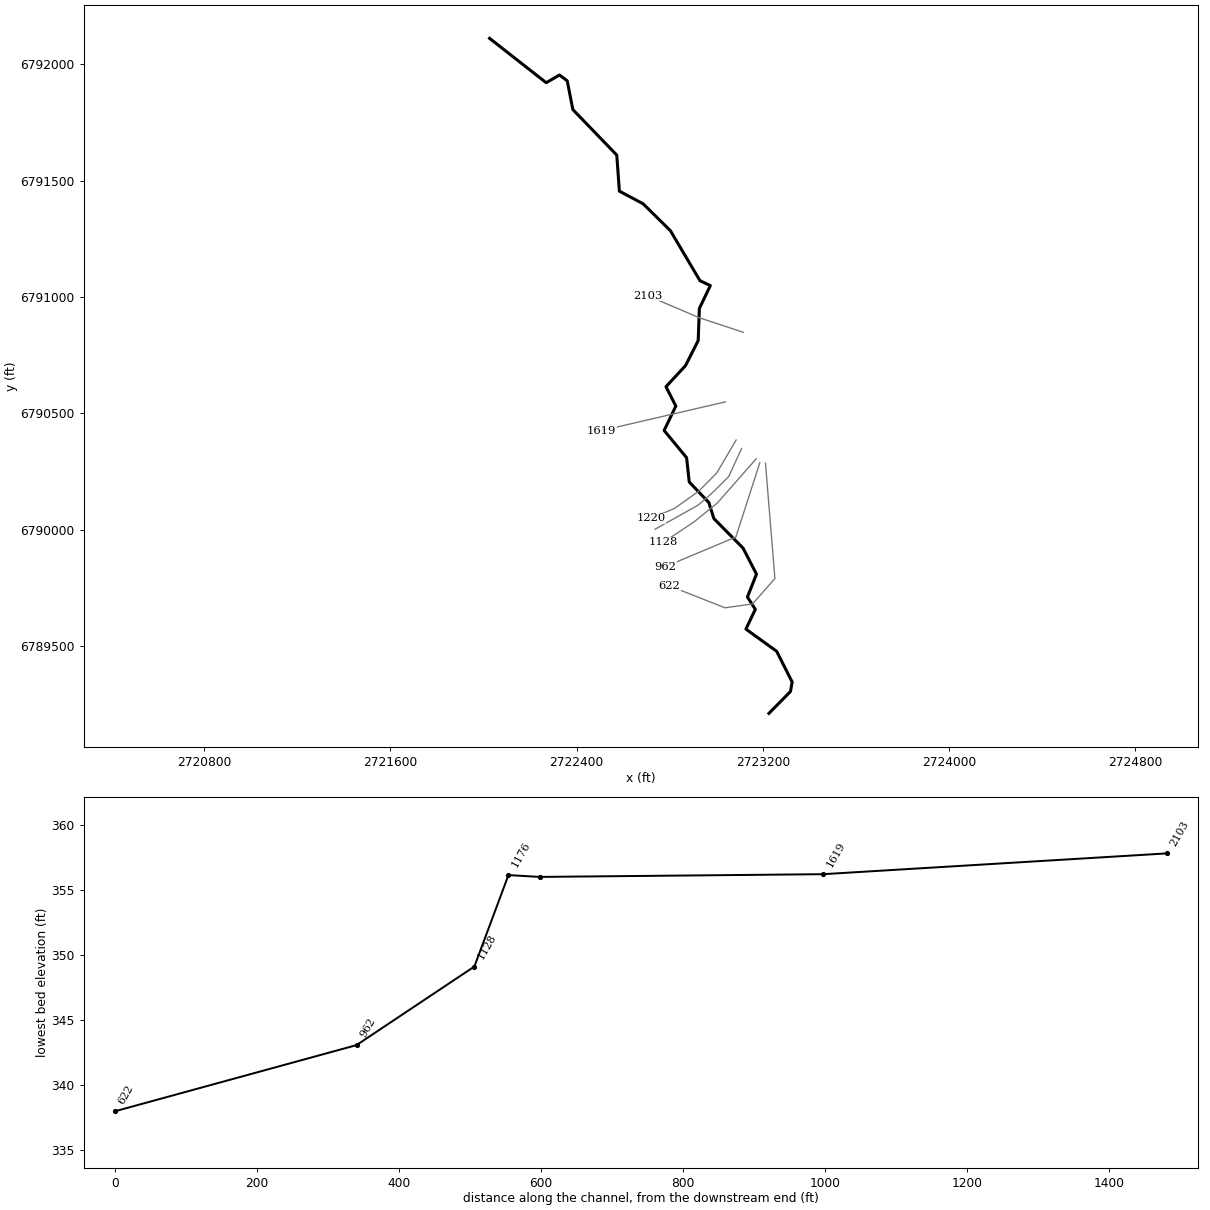
--- Lynn Creek T 16.prj (project) ---

Proj Title=Lynn Creek T 16 Base Level Engineering
Current Plan=p01
Default Exp/Contr=0.3,0.1
English Units
Geom File=g01
Flow File=f01
Plan File=p01
BEGIN DESCRIPTION:
Lynn Creek T 16
END DESCRIPTION:

--- Lynn Creek T 16.p01 (plan) ---

Plan Title=Multiple Run
Short Identifier=Multiple
Geom File=g01
Flow File=f01
Subcritical Flow
K Sum by GR= 0
Std Step Tol= 0.01
Critical Tol= 0.01
Num of Std Step Trials= 20
Max Error Tol= 0.3
Flow Tol Ratio= 0.001
Split Flow NTrial= 30
Split Flow Tol= 0.02
Split Flow Ratio= 0.02
Log Output Level= 0
Friction Slope Method= 1
Unsteady Friction Slope Method= 2
Unsteady Bridges Friction Slope Method= 1
Parabolic Critical Depth
Global Vel Dist=  1 , 1 , 1
Global Log Level= 0
CheckData=True
Encroach Param= -1, 0, 0, 0
BEGIN DESCRIPTION:
Multiple Run
END DESCRIPTION:

--- Lynn Creek T 16.f01 (steady flow) ---

Flow Title=Multiple
Number of Profiles=7
Profile Names=10-year,25-year,50-year,1pct_min,100-year,1pct_plu,500-year
River Rch & RM= Lynn Creek T 16,Reach-1,2103
     139     169     191     108     215     429     271
Boundary for River Rch & Prof#=Lynn Creek T 16,Reach-1,1
Up Type=0
Dn Type=3
Dn Slope=0.005
Boundary for River Rch & Prof#=Lynn Creek T 16,Reach-1,2
Up Type=0
Dn Type=3
Dn Slope=0.005
Boundary for River Rch & Prof#=Lynn Creek T 16,Reach-1,3
Up Type=0
Dn Type=3
Dn Slope=0.005
Boundary for River Rch & Prof#=Lynn Creek T 16,Reach-1,4
Up Type=0
Dn Type=3
Dn Slope=0.005
Boundary for River Rch & Prof#=Lynn Creek T 16,Reach-1,5
Up Type=0
Dn Type=3
Dn Slope=0.005
Boundary for River Rch & Prof#=Lynn Creek T 16,Reach-1,6
Up Type=0
Dn Type=3
Dn Slope=0.005
Boundary for River Rch & Prof#=Lynn Creek T 16,Reach-1,7
Up Type=0
Dn Type=3
Dn Slope=0.005

--- Lynn Creek T 16.g01 (geometry) ---

Geom Title=Existing Conditions

River Reach=Lynn Creek T 16,Reach-1
Reach XY= 30
      2722026.00      6792111.00      2722269.35      6791920.32
      2722326.24      6791953.54      2722359.54      6791928.61
      2722383.86      6791804.83      2722572.46      6791609.53
      2722583.70      6791454.53      2722685.66      6791400.21
      2722802.99      6791284.47      2722930.00      6791069.64
      2722974.53      6791048.87      2722927.26      6790950.52
      2722922.24      6790812.56      2722867.82      6790704.94
      2722783.83      6790614.40      2722826.19      6790531.20
      2722775.96      6790426.34      2722872.37      6790309.50
      2722883.88      6790204.84      2722967.82      6790117.04
      2722989.63      6790047.79      2723115.24      6789920.68
      2723172.63      6789809.26      2723133.82      6789710.91
      2723167.67      6789657.73      2723127.22      6789573.03
      2723259.37      6789477.71      2723326.00      6789345.59
      2723318.62      6789304.92      2723226.00      6789211.00

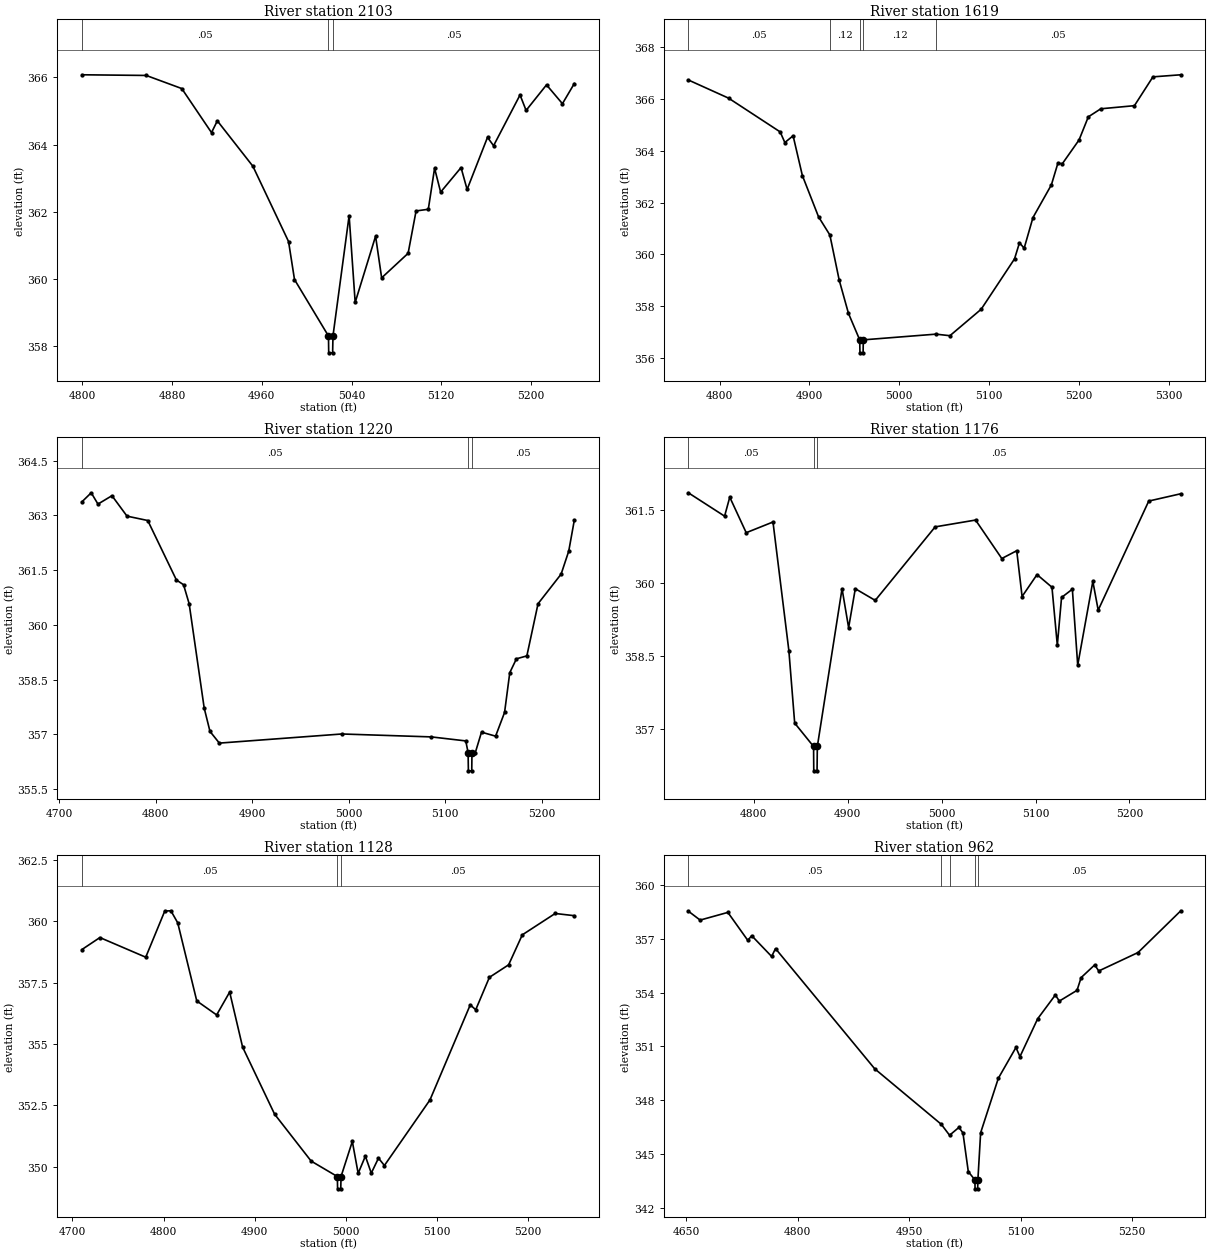
Type RM Length L Ch R = 1,2103,484,484,484
BEGIN DESCRIPTION:
Lynn Creek T 16 2.0
END DESCRIPTION:
XS GIS Cut Line= 3
      2723116.03      6790848.19      2722926.00      6790911.00
      2722706.28      6791004.93
#Sta/Elev= 30
  4799.5  366.08  4856.9  366.06  4888.6  365.67  4915.1  364.36  4920.3  364.71
  4952.0  363.36  4983.8  361.12  4989.1  359.99  5019.4  358.31  5019.6  357.81
  5023.1  357.81  5023.4  358.31  5037.8  361.89  5043.2  359.31  5061.4  361.28
  5066.8  360.04  5090.4  360.77  5097.5  362.03  5108.4  362.08  5114.0  363.30
  5119.4  362.59  5137.6  363.32  5143.0  362.67  5161.2  364.22  5166.6  363.97
  5190.2  365.48  5195.6  365.02  5213.8  365.78  5228.0  365.22  5238.6  365.82
#Mann=3,-1,0
  4799.5    0.05       0  5019.4    0.04       0  5023.4    0.05       0
Bank Sta=5019.4,5023.4
Exp/Cntr=0.3,0.1

Type RM Length L Ch R = 1,1619,399,399,399
BEGIN DESCRIPTION:
Mapping XS 7fcf6ee1
END DESCRIPTION:
XS GIS Cut Line= 2
      2723039.61      6790549.31      2722505.76      6790425.57
#Sta/Elev= 30
  4765.2  366.72  4810.0  366.02  4867.4  364.72  4872.6  364.31  4881.8  364.57
  4892.1  363.04  4910.1  361.45  4922.7  360.75  4933.1  359.01  4943.4  357.73
  4955.9  356.71  4956.2  356.21  4959.7  356.21  4959.9  356.71  5040.7  356.93
  5056.3  356.87  5091.1  357.89  5128.2  359.83  5133.7  360.45  5138.9  360.24
  5148.7  361.42  5169.2  362.68  5176.4  363.51  5181.5  363.50  5200.0  364.41
  5210.3  365.30  5224.2  365.61  5261.6  365.73  5282.2  366.84  5313.2  366.92
#Mann=5,-1,0
  4765.2    0.05       0  4922.7    0.12       0  4955.9    0.07       0
  4959.9    0.12       0  5040.7    0.05       0
Bank Sta=4955.9,4959.9
Exp/Cntr=0.3,0.1

Type RM Length L Ch R = 1,1220,44,44,44
BEGIN DESCRIPTION:
Mapping XS 2492ae2e
END DESCRIPTION:
XS GIS Cut Line= 5
      2723085.35      6790385.38      2723001.50      6790243.20
      2722923.87      6790164.76      2722819.65      6790090.91
      2722720.60      6790049.80
#Sta/Elev= 30
  4723.3  363.37  4733.0  363.62  4740.0  363.31  4754.5  363.54  4770.1  362.98
  4791.6  362.86  4821.3  361.23  4828.7  361.10  4834.5  360.58  4850.1  357.72
  4856.1  357.08  4865.8  356.76  4992.8  357.01  5085.5  356.93  5121.2  356.82
  5123.6  356.50  5123.9  356.00  5127.4  356.00  5127.6  356.50  5131.1  356.50
  5137.5  357.06  5152.1  356.95  5161.4  357.60  5166.8  358.69  5173.7  359.07
  5184.5  359.15  5196.1  360.58  5220.0  361.39  5227.9  362.02  5233.7  362.87
#Mann=3,-1,0
  4723.3    0.05       0  5123.6    0.04       0  5127.6    0.05       0
Bank Sta=5123.6,5127.6
Exp/Cntr=0.3,0.1

Type RM Length L Ch R = 1,1176,48,48,48
BEGIN DESCRIPTION:
Mapping XS 084945fb
END DESCRIPTION:
XS GIS Cut Line= 6
      2723108.32      6790348.32      2723053.70      6790228.83
      2722991.15      6790166.33      2722954.40      6790133.00
      2722920.85      6790104.95      2722736.75      6790001.96
#Sta/Elev= 30
  4730.5  361.85  4769.1  361.37  4774.6  361.76  4792.1  361.03  4820.6  361.25
  4837.5  358.61  4843.7  357.12  4863.8  356.64  4864.0  356.14  4867.5  356.14
  4867.8  356.64  4894.1  359.88  4901.1  359.08  4908.2  359.88  4929.4  359.64
  4993.2  361.15  5036.2  361.29  5064.1  360.50  5080.0  360.66  5085.7  359.72
  5101.6  360.17  5117.5  359.91  5123.2  358.72  5127.7  359.70  5139.2  359.87
  5144.9  358.31  5161.0  360.03  5166.7  359.44  5220.5  361.68  5254.6  361.83
#Mann=3,-1,0
  4730.5    0.05       0  4863.8    0.04       0  4867.8    0.05       0
Bank Sta=4863.8,4867.8
Exp/Cntr=0.3,0.1

Type RM Length L Ch R = 1,1128,166,166,166
BEGIN DESCRIPTION:
Mapping XS ea78099e
END DESCRIPTION:
XS GIS Cut Line= 4
      2723171.13      6790304.29      2723004.49      6790114.69
      2722903.76      6790033.11      2722771.87      6789945.47
#Sta/Elev= 30
  4710.3  358.84  4730.1  359.33  4780.4  358.53  4801.3  360.41  4808.0  360.42
  4815.5  359.93  4836.4  356.75  4858.2  356.18  4872.5  357.11  4886.7  354.87
  4921.8  352.14  4961.9  350.23  4990.7  349.60  4990.9  349.10  4994.4  349.10
  4994.7  349.60  5007.1  351.03  5013.5  349.73  5021.4  350.43  5027.9  349.74
  5035.8  350.35  5042.3  350.05  5092.3  352.72  5136.5  356.59  5142.5  356.39
  5157.5  357.71  5178.6  358.22  5193.6  359.44  5229.7  360.31  5250.7  360.22
#Mann=3,-1,0
  4710.3    0.05       0  4990.7    0.04       0  4994.7    0.05       0
Bank Sta=4990.7,4994.7
Exp/Cntr=0.3,0.1

Type RM Length L Ch R = 1,962,340,340,340
BEGIN DESCRIPTION:
Mapping XS 40b34741
END DESCRIPTION:
XS GIS Cut Line= 3
      2723186.96      6790287.77      2723084.03      6789968.47
      2722782.37      6789841.95
#Sta/Elev= 30
  4652.9  358.55  4668.8  358.05  4706.1  358.48  4732.9  356.92  4738.2  357.18
  4765.0  356.02  4770.2  356.46  4903.7  349.75  4993.3  346.65  5004.4  346.04
  5017.0  346.48  5022.4  346.17  5029.6  344.01  5038.5  343.55  5038.7  343.05
  5042.2  343.05  5042.5  343.55  5046.2  346.18  5070.0  349.22  5093.7  350.94
  5099.1  350.43  5122.9  352.54  5146.7  353.87  5152.1  353.53  5175.9  354.13
  5181.4  354.84  5199.7  355.55  5205.1  355.21  5258.0  356.24  5315.5  358.57
#Mann=5,-1,0
  4652.9    0.05       0  4993.3     0.1       0  5004.4    0.05       0
  5038.5    0.07       0  5042.5    0.05       0
Bank Sta=5038.5,5042.5
Exp/Cntr=0.3,0.1

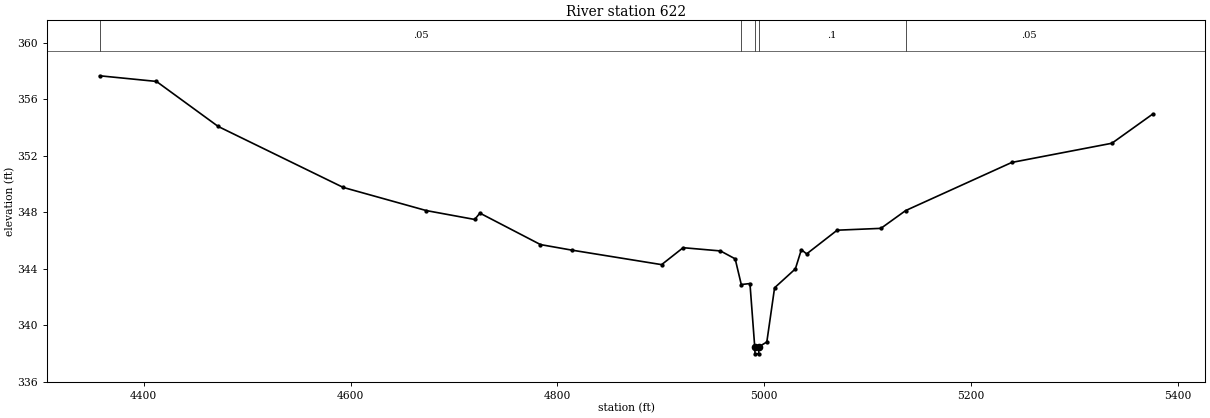
Type RM Length L Ch R = 1,622,0,0,0
BEGIN DESCRIPTION:
Lynn Creek T 16 1.0
END DESCRIPTION:
XS GIS Cut Line= 5
      2723211.28      6790285.75      2723251.83      6789790.40
      2723155.76      6789681.01      2723037.36      6789664.62
      2722799.24      6789758.53
#Sta/Elev= 30
  4357.4  357.66  4412.3  357.26  4472.0  354.07  4592.9  349.75  4673.2  348.11
  4720.0  347.48  4725.0  347.93  4783.6  345.70  4813.7  345.31  4900.7  344.28
  4921.5  345.48  4957.6  345.25  4971.8  344.69  4977.7  342.87  4986.1  342.94
  4990.7  338.46  4991.0  337.96  4994.5  337.96  4994.7  338.46  5002.4  338.80
  5009.9  342.64  5030.0  343.98  5035.8  345.34  5040.9  345.04  5070.4  346.72
  5112.7  346.85  5136.6  348.11  5239.2  351.52  5336.0  352.88  5375.5  354.95
#Mann=5,-1,0
  4357.4    0.05       0  4977.7     0.1       0  4990.7    0.07       0
  4994.7     0.1       0  5136.6    0.05       0
Bank Sta=4990.7,4994.7
Exp/Cntr=0.3,0.1

Chan Stop Cuts=-1