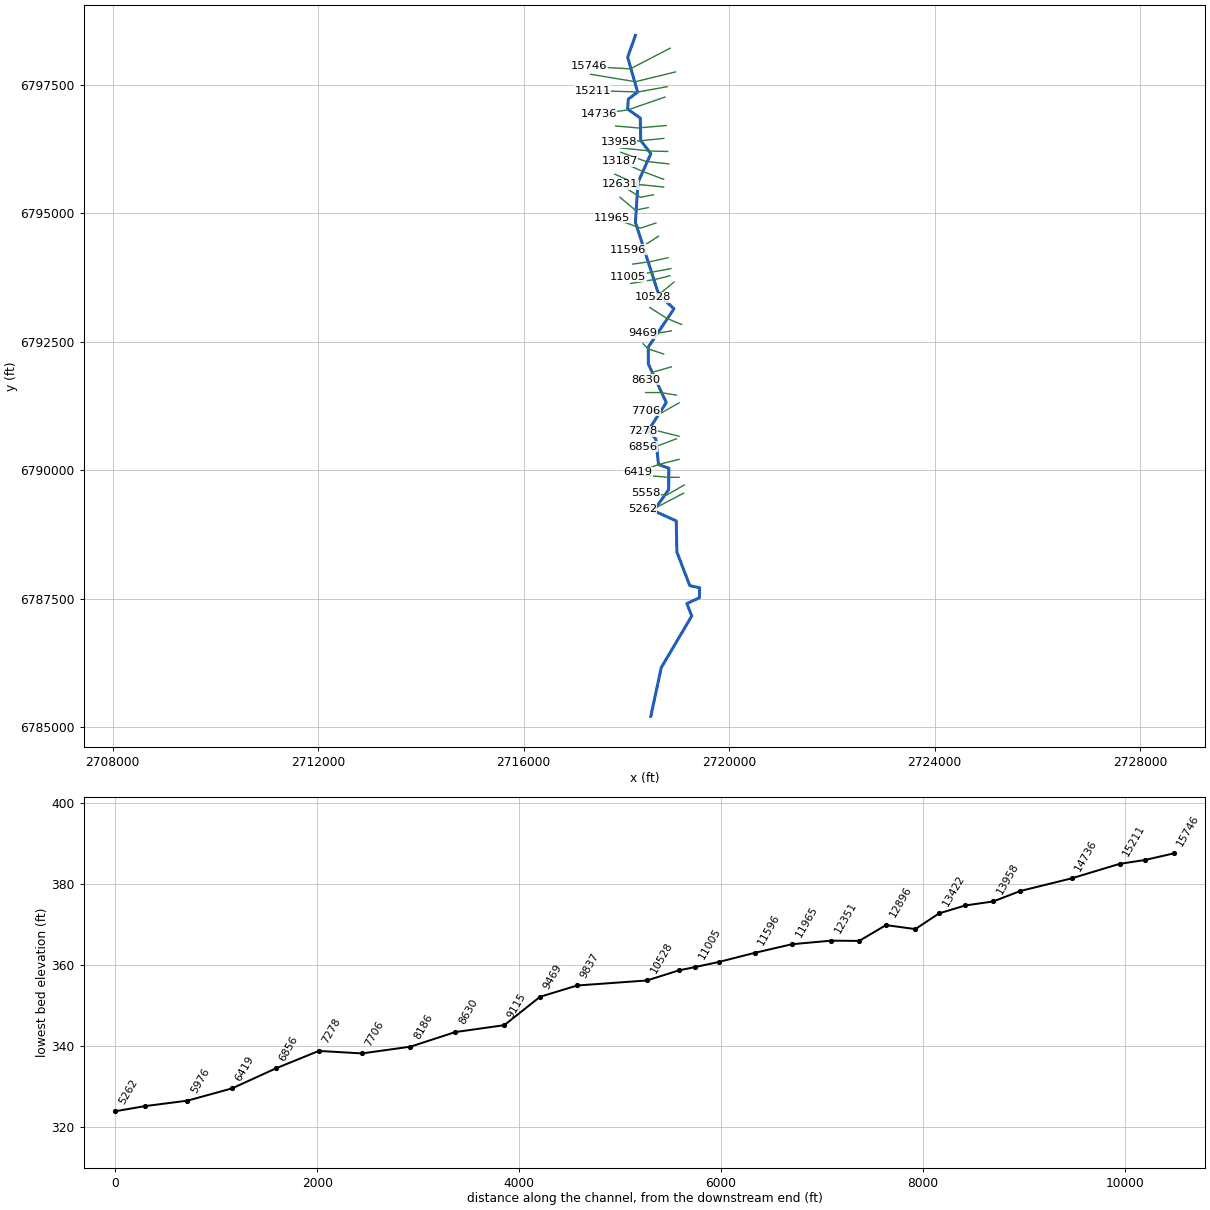
--- Lynn Creek T 17.prj (project) ---

Proj Title=Lynn Creek T 17 Base Level Engineering
Current Plan=p01
Default Exp/Contr=0.3,0.1
English Units
Geom File=g01
Flow File=f01
Plan File=p01
Y Axis Title=Elevation
X Axis Title(PF)=Main Channel Distance
X Axis Title(XS)=Station
BEGIN DESCRIPTION:
Lynn Creek T 17
END DESCRIPTION:
DSS Export Rating Curves= 0
DSS Export Rating Curve Sorted= 0
DSS Export Volume Flow Curves= 0
DXF OffsetX= 0
DXF OffsetY= 0
DXF ScaleX= 1
DXF ScaleY= 10

--- Lynn Creek T 17.p01 (plan) ---

Plan Title=Multiple Run
Short Identifier=Multiple
Geom File=g01
Flow File=f01
Subcritical Flow
K Sum by GR= 0
Std Step Tol= 0.01
Critical Tol= 0.01
Num of Std Step Trials= 20
Max Error Tol= 0.3
Flow Tol Ratio= 0.001
Split Flow NTrial= 30
Split Flow Tol= 0.02
Split Flow Ratio= 0.02
Log Output Level= 0
Friction Slope Method= 1
Unsteady Friction Slope Method= 2
Unsteady Bridges Friction Slope Method= 1
Parabolic Critical Depth
Global Vel Dist=  1 , 1 , 1
Global Log Level= 0
CheckData=True
Encroach Param= -1, 0, 0, 0
BEGIN DESCRIPTION:
Multiple Run
END DESCRIPTION:

--- Lynn Creek T 17.f01 (steady flow) ---

Flow Title=Multiple
Number of Profiles=7
Profile Names=10-year,25-year,50-year,1pct_min,100-year,1pct_plu,500-year
River Rch & RM= Lynn Creek T 17,Reach-1,15746
     667     898    1084     650    1297    2587    1853
River Rch & RM= Lynn Creek T 17,Reach-1,8630
     722     977    1186     714    1425    2843    2054
River Rch & RM= Lynn Creek T 17,Reach-1,7278
     924    1269    1554     943    1882    3755    2759
River Rch & RM= Lynn Creek T 17,Reach-1,6419
    1099    1523    1875    1144    2282    4553    3379
River Rch & RM= Lynn Creek T 17,Reach-1,2980
    1131    1567    1931    1178    2349    4688    3480
River Rch & RM= Lynn Creek T 17,Reach-1,2554
    1151    1591    1957    1191    2376    4741    3504
Boundary for River Rch & Prof#=Lynn Creek T 17,Reach-1,1
Up Type=0
Dn Type=3
Dn Slope=0.005
Boundary for River Rch & Prof#=Lynn Creek T 17,Reach-1,2
Up Type=0
Dn Type=3
Dn Slope=0.005
Boundary for River Rch & Prof#=Lynn Creek T 17,Reach-1,3
Up Type=0
Dn Type=3
Dn Slope=0.005
Boundary for River Rch & Prof#=Lynn Creek T 17,Reach-1,4
Up Type=0
Dn Type=3
Dn Slope=0.005
Boundary for River Rch & Prof#=Lynn Creek T 17,Reach-1,5
Up Type=0
Dn Type=3
Dn Slope=0.005
Boundary for River Rch & Prof#=Lynn Creek T 17,Reach-1,6
Up Type=0
Dn Type=3
Dn Slope=0.005
Boundary for River Rch & Prof#=Lynn Creek T 17,Reach-1,7
Up Type=0
Dn Type=3
Dn Slope=0.005

--- Lynn Creek T 17.g01 (geometry) ---

Geom Title=Existing Conditions

River Reach=Lynn Creek T 17,Reach-1
Reach XY= 30
      2718176.00      6798461.00      2718025.69      6798035.89
      2718218.91      6797360.99      2718037.11      6797221.32
      2718026.25      6797026.21      2718272.79      6796853.01
      2718278.18      6796416.45      2718477.03      6796160.64
      2718226.93      6795601.15      2718176.54      6794824.86
      2718628.26      6793422.31      2718926.47      6793140.84
      2718426.51      6792395.79      2718428.24      6792066.93
      2718776.85      6791316.04      2718426.64      6790770.69
      2718573.65      6790605.50      2718626.00      6790111.00
      2718826.56      6790038.43      2718824.11      6789622.14
      2718532.97      6789210.75      2718970.91      6789013.30
      2718983.79      6788407.58      2719233.36      6787754.62
      2719426.00      6787711.00      2719421.01      6787516.00
      2719177.72      6787405.38      2719272.71      6787162.36
      2718679.83      6786159.42      2718476.00      6785211.00

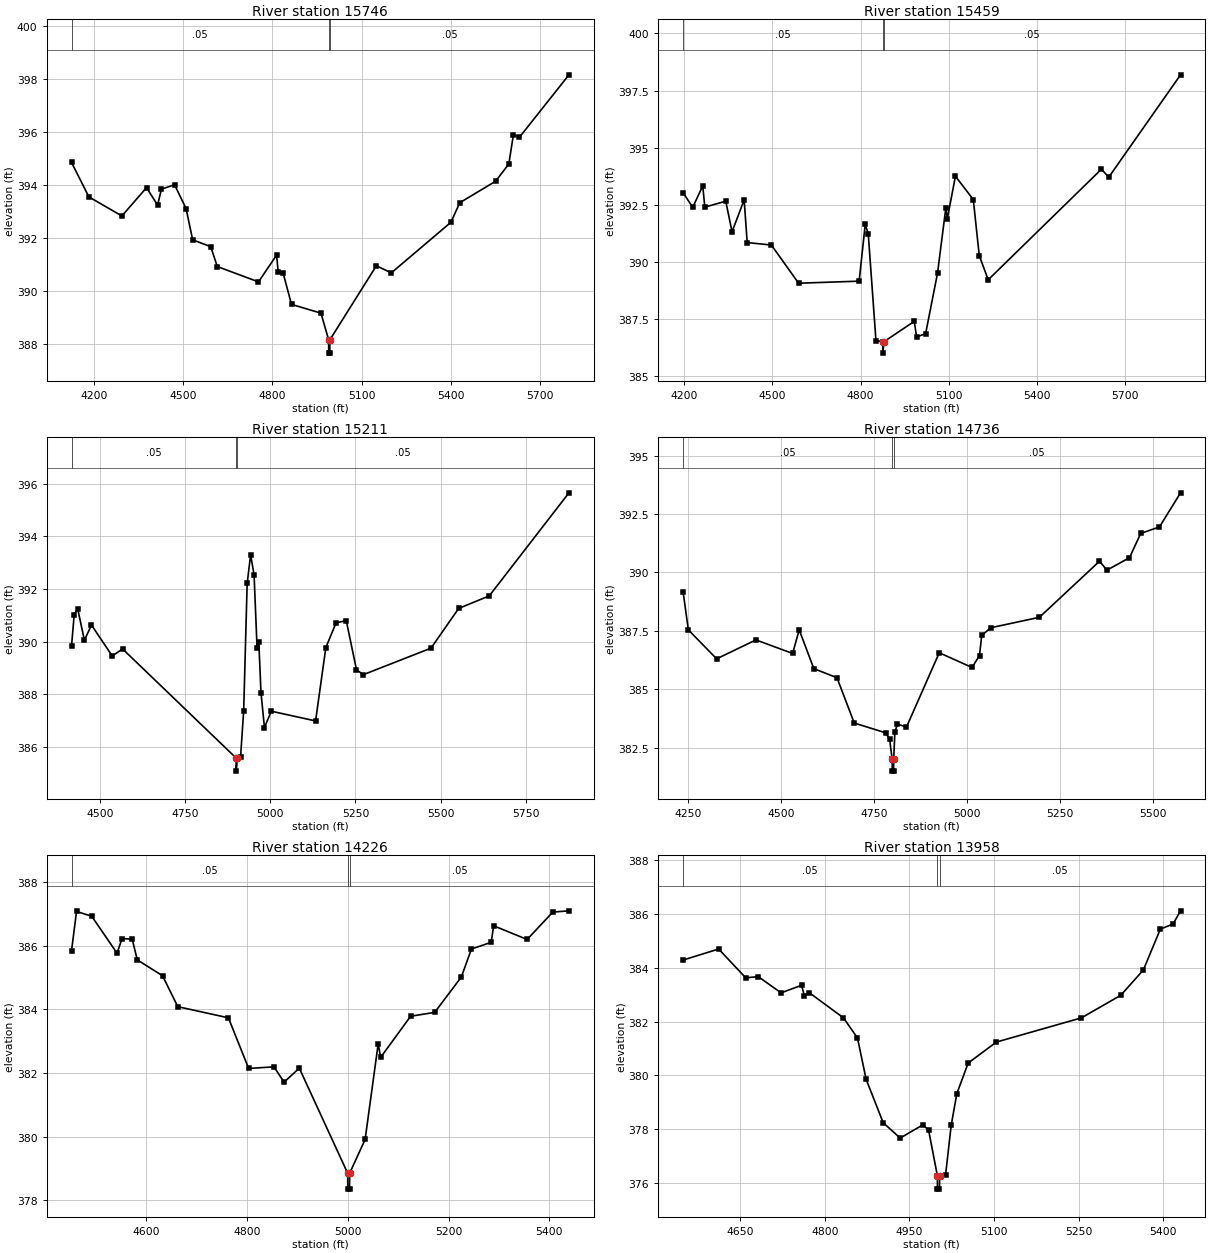
Type RM Length L Ch R = 1,15746,287,287,287
BEGIN DESCRIPTION:
Lynn Creek T 17 38.0
END DESCRIPTION:
XS GIS Cut Line= 3
      2718852.89      6798213.04      2718076.00      6797811.00
      2717279.64      6797857.94
#Sta/Elev= 30
  4124.8  394.85  4183.2  393.55  4294.1  392.83  4377.0  393.90  4414.1  393.24
  4427.0  393.84  4471.2  394.01  4509.9  393.11  4532.0  391.93  4592.8  391.67
  4614.9  390.92  4753.4  390.34  4814.2  391.35  4819.8  390.70  4836.3  390.67
  4864.4  389.49  4963.5  389.16  4989.3  388.15  4989.6  387.65  4993.1  387.65
  4993.3  388.15  5149.8  390.95  5199.9  390.68  5400.3  392.59  5430.3  393.33
  5550.5  394.14  5595.0  394.79  5610.6  395.90  5630.7  395.80  5797.3  398.16
#Mann=3,-1,0
  4124.8    0.05       0  4989.3    0.04       0  4993.3    0.05       0
Bank Sta=4989.3,4993.3
Exp/Cntr=0.3,0.1

Type RM Length L Ch R = 1,15459,248,248,248
BEGIN DESCRIPTION:
Lynn Creek T 17 37.0
END DESCRIPTION:
XS GIS Cut Line= 3
      2718957.68      6797751.33      2718176.00      6797561.00
      2717300.54      6797705.93
#Sta/Elev= 30
  4196.3  393.03  4228.9  392.39  4263.0  393.33  4270.1  392.40  4341.3  392.66
  4362.7  391.32  4403.9  392.72  4414.2  390.85  4496.5  390.74  4589.1  389.07
  4795.0  389.16  4815.7  391.64  4825.9  391.24  4852.2  386.56  4875.3  386.51
  4875.6  386.01  4879.3  386.51  4982.5  387.40  4990.5  386.72  5021.1  386.86
  5061.6  389.51  5089.8  392.36  5094.9  391.89  5122.5  393.75  5183.3  392.73
  5203.5  390.28  5234.0  389.22  5619.1  394.06  5644.1  393.71  5888.2  398.19
#Mann=3,-1,0
  4196.3    0.05       0  4875.3    0.04       0  4879.3    0.05       0
Bank Sta=4875.3,4879.3
Exp/Cntr=0.3,0.1

Type RM Length L Ch R = 1,15211,475,475,475
BEGIN DESCRIPTION:
Lynn Creek T 17 36.0
END DESCRIPTION:
XS GIS Cut Line= 3
      2718793.69      6797463.53      2718226.00      6797361.00
      2717342.10      6797388.45
#Sta/Elev= 30
  4416.0  389.84  4423.8  391.02  4434.0  391.25  4453.8  390.05  4474.6  390.63
  4535.6  389.45  4565.9  389.72  4899.4  385.57  4899.7  385.07  4903.4  385.57
  4912.6  385.62  4921.7  387.37  4931.9  392.21  4942.1  393.30  4952.2  392.54
  4961.0  389.76  4966.1  390.00  4972.5  388.06  4982.7  386.73  5002.9  387.35
  5132.9  386.98  5163.0  389.77  5193.0  390.71  5223.0  390.80  5253.0  388.93
  5273.0  388.74  5472.1  389.75  5553.1  391.26  5643.2  391.74  5877.2  395.66
#Mann=3,-1,0
  4416.0    0.05       0  4899.4    0.04       0  4903.4    0.05       0
Bank Sta=4899.4,4903.4
Exp/Cntr=0.3,0.1

Type RM Length L Ch R = 1,14736,510,510,510
BEGIN DESCRIPTION:
Lynn Creek T 17 35.0
END DESCRIPTION:
XS GIS Cut Line= 3
      2718751.29      6797261.66      2718026.00      6797011.00
      2717459.78      6796934.12
#Sta/Elev= 30
  4236.4  389.16  4250.5  387.54  4326.6  386.30  4432.3  387.11  4531.1  386.53
  4548.8  387.54  4588.2  385.88  4650.5  385.49  4697.0  383.55  4781.6  383.13
  4792.2  382.85  4799.1  381.99  4799.4  381.49  4802.9  381.49  4803.1  381.99
  4806.4  383.18  4813.3  383.50  4837.6  383.38  4925.8  386.56  5013.9  385.93
  5034.1  386.44  5040.0  387.30  5064.3  387.63  5195.5  388.08  5357.0  390.48
  5377.2  390.10  5437.7  390.63  5468.0  391.67  5518.5  391.95  5575.2  393.41
#Mann=3,-1,0
  4236.4    0.05       0  4799.1    0.04       0  4803.1    0.05       0
Bank Sta=4799.1,4803.1
Exp/Cntr=0.3,0.1

Type RM Length L Ch R = 1,14226,268,268,268
BEGIN DESCRIPTION:
Lynn Creek T 17 34.0
END DESCRIPTION:
XS GIS Cut Line= 3
      2718775.86      6796708.07      2718226.00      6796661.00
      2717793.46      6796699.22
#Sta/Elev= 30
  4452.6  385.84  4462.5  387.07  4492.6  386.92  4542.8  385.76  4552.8  386.22
  4572.9  386.20  4582.9  385.55  4633.1  385.05  4663.2  384.08  4763.6  383.73
  4803.7  382.14  4853.9  382.19  4874.0  381.71  4904.1  382.15  5000.0  378.85
  5000.2  378.35  5003.7  378.35  5004.0  378.85  5034.6  379.91  5060.5  382.91
  5065.5  382.49  5124.9  383.78  5172.5  383.90  5225.3  385.01  5245.4  385.89
  5284.5  386.10  5289.5  386.62  5355.8  386.19  5406.6  387.05  5438.7  387.09
#Mann=3,-1,0
  4452.6    0.05       0  5000.0    0.04       0  5004.0    0.05       0
Bank Sta=5000,5004
Exp/Cntr=0.3,0.1

Type RM Length L Ch R = 1,13958,277,277,277
BEGIN DESCRIPTION:
Lynn Creek T 17 33.0
END DESCRIPTION:
XS GIS Cut Line= 3
      2718728.69      6796457.60      2718276.00      6796411.00
      2717850.27      6796385.03
#Sta/Elev= 30
  4549.0  384.29  4612.0  384.70  4659.8  383.63  4682.4  383.67  4722.6  383.07
  4758.9  383.35  4763.9  382.96  4772.9  383.07  4833.2  382.14  4858.0  381.39
  4873.4  379.85  4903.6  378.24  4933.7  377.67  4973.9  378.16  4984.0  377.97
  4999.6  376.27  4999.8  375.77  5003.3  375.77  5003.6  376.27  5014.1  376.29
  5024.1  378.14  5034.1  379.32  5054.2  380.46  5104.3  381.24  5255.0  382.14
  5324.7  382.98  5364.7  383.92  5394.8  385.44  5417.3  385.63  5430.6  386.12
#Mann=3,-1,0
  4549.0    0.05       0  4999.6    0.04       0  5003.6    0.05       0
Bank Sta=4999.6,5003.6
Exp/Cntr=0.3,0.1

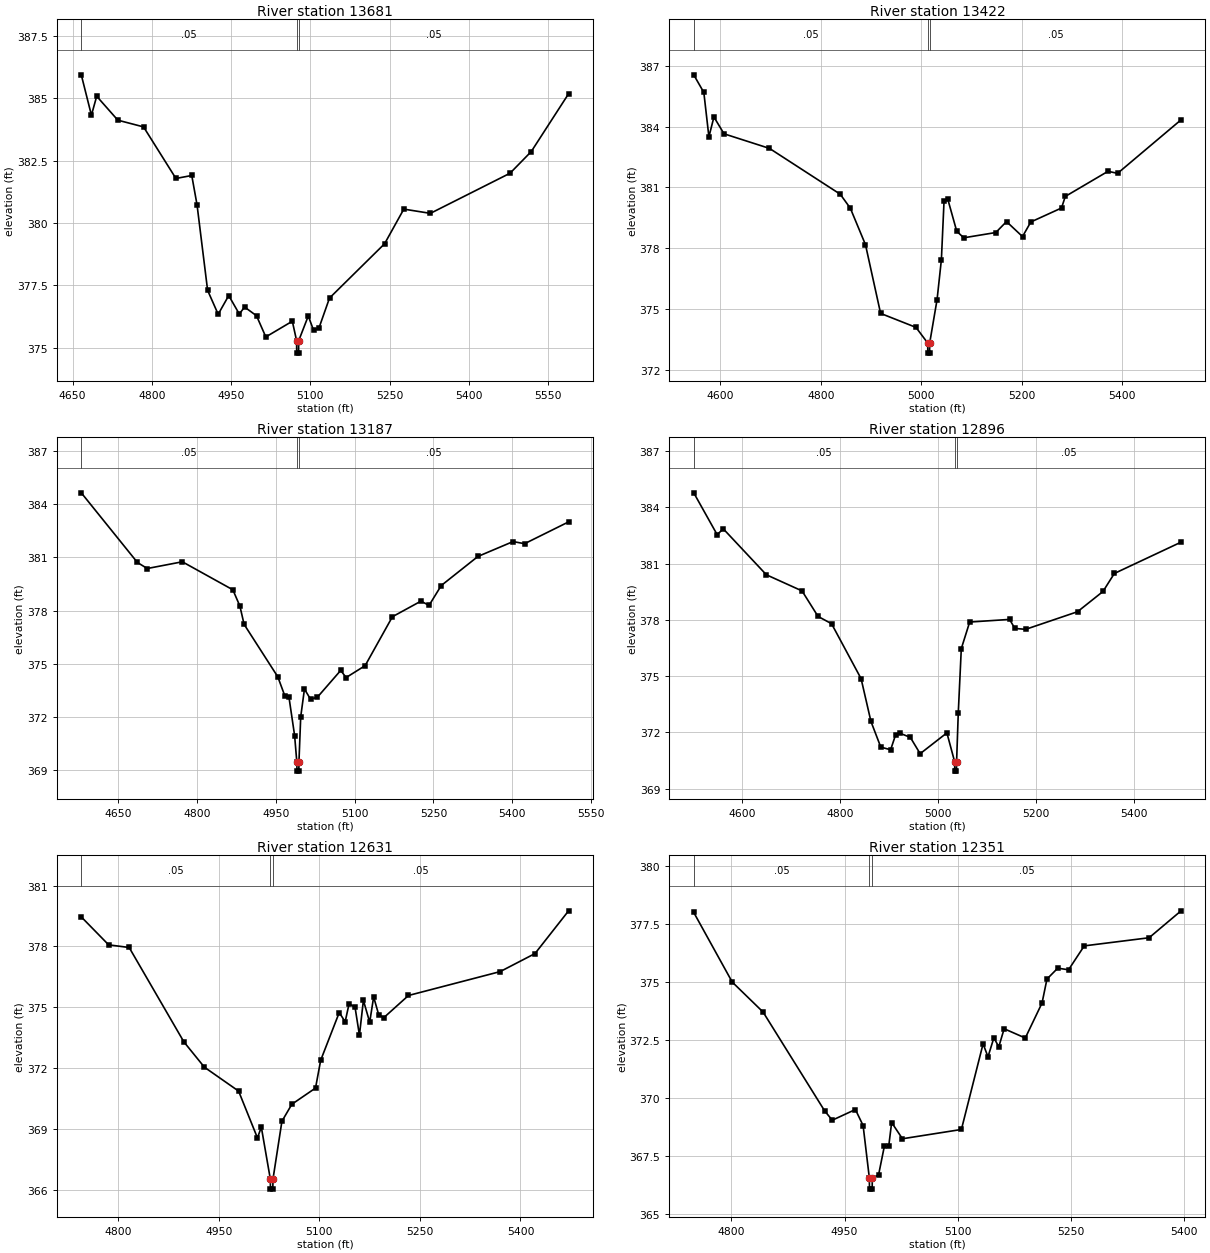
Type RM Length L Ch R = 1,13681,259,259,259
BEGIN DESCRIPTION:
Lynn Creek T 17 32.0
END DESCRIPTION:
XS GIS Cut Line= 3
      2718805.15      6796203.07      2718476.00      6796211.00
      2717885.68      6796271.88
#Sta/Elev= 30
  4666.3  385.95  4685.5  384.33  4695.5  385.09  4735.5  384.13  4784.2  383.86
  4845.5  381.79  4875.5  381.91  4885.5  380.73  4905.5  377.30  4925.5  376.34
  4945.5  377.09  4965.5  376.35  4975.5  376.63  4998.1  376.28  5015.7  375.43
  5065.9  376.06  5074.0  375.28  5074.2  374.78  5077.7  374.78  5078.0  375.28
  5096.1  376.27  5106.1  375.70  5116.2  375.78  5136.3  376.99  5240.6  379.17
  5277.0  380.56  5327.3  380.39  5478.1  382.00  5518.3  382.87  5589.0  385.19
#Mann=3,-1,0
  4666.3    0.05       0  5074.0    0.04       0  5078.0    0.05       0
Bank Sta=5074,5078
Exp/Cntr=0.3,0.1

Type RM Length L Ch R = 1,13422,235,235,235
BEGIN DESCRIPTION:
Lynn Creek T 17 31.0
END DESCRIPTION:
XS GIS Cut Line= 3
      2718825.97      6795961.00      2718376.00      6796011.00
      2717889.29      6796188.18
#Sta/Elev= 30
  4546.8  386.55  4566.9  385.68  4577.0  383.49  4587.0  384.47  4607.1  383.64
  4697.7  382.92  4838.6  380.66  4858.7  379.97  4888.9  378.17  4919.0  374.78
  4989.5  374.09  5012.8  373.32  5013.1  372.82  5016.6  372.82  5016.8  373.32
  5031.5  375.46  5040.1  377.43  5045.4  380.33  5052.8  380.42  5070.7  378.83
  5084.7  378.51  5148.5  378.77  5169.8  379.31  5201.7  378.57  5218.2  379.29
  5279.4  379.98  5286.9  380.55  5372.0  381.79  5391.1  381.69  5517.5  384.33
#Mann=3,-1,0
  4546.8    0.05       0  5012.8    0.04       0  5016.8    0.05       0
Bank Sta=5012.8,5016.8
Exp/Cntr=0.3,0.1

Type RM Length L Ch R = 1,13187,291,291,291
BEGIN DESCRIPTION:
Lynn Creek T 17 30.0
END DESCRIPTION:
XS GIS Cut Line= 3
      2718725.97      6795661.01      2718326.00      6795811.00
      2717869.57      6796014.49
#Sta/Elev= 30
  4580.1  384.64  4686.9  380.71  4705.6  380.37  4772.3  380.75  4868.4  379.17
  4881.8  378.25  4889.8  377.22  4953.9  374.26  4967.2  373.19  4975.2  373.10
  4985.9  370.94  4990.1  369.44  4990.4  368.94  4993.9  368.94  4994.1  369.44
  4997.5  372.01  5004.6  373.57  5016.1  373.00  5029.2  373.11  5073.5  374.62
  5083.9  374.22  5120.0  374.89  5171.9  377.65  5226.2  378.53  5241.6  378.29
  5264.8  379.41  5334.5  381.05  5401.4  381.89  5423.3  381.77  5507.0  383.00
#Mann=3,-1,0
  4580.1    0.05       0  4990.1    0.04       0  4994.1    0.05       0
Bank Sta=4990.1,4994.1
Exp/Cntr=0.3,0.1

Type RM Length L Ch R = 1,12896,265,265,265
BEGIN DESCRIPTION:
Lynn Creek T 17 29.0
END DESCRIPTION:
XS GIS Cut Line= 3
      2718726.02      6795511.00      2718226.00      6795561.00
      2717775.96      6795761.02
#Sta/Elev= 30
  4502.0  384.77  4549.8  382.54  4562.3  382.85  4650.3  380.40  4723.1  379.54
  4755.8  378.18  4783.4  377.79  4843.7  374.86  4863.8  372.58  4883.9  371.21
  4904.0  371.07  4914.1  371.86  4924.1  371.94  4944.2  371.73  4964.3  370.86
  5018.9  371.97  5034.7  370.43  5034.9  369.93  5038.4  369.93  5038.7  370.43
  5042.1  373.02  5048.3  376.46  5065.4  377.88  5146.8  378.02  5157.7  377.54
  5179.6  377.49  5285.6  378.43  5337.6  379.51  5360.8  380.47  5497.0  382.14
#Mann=3,-1,0
  4502.0    0.05       0  5034.7    0.04       0  5038.7    0.05       0
Bank Sta=5034.7,5038.7
Exp/Cntr=0.3,0.1

Type RM Length L Ch R = 1,12631,280,280,280
BEGIN DESCRIPTION:
Lynn Creek T 17 28.0
END DESCRIPTION:
XS GIS Cut Line= 3
      2718526.04      6795361.01      2718276.00      6795311.00
      2717875.99      6795561.01
#Sta/Elev= 30
  4745.1  379.46  4785.9  378.08  4816.5  377.95  4898.1  373.29  4928.7  372.04
  4979.7  370.86  5007.8  368.55  5013.6  369.08  5027.0  366.52  5027.2  366.02
  5030.7  366.02  5031.0  366.52  5044.3  369.37  5059.1  370.21  5094.4  371.01
  5102.1  372.38  5129.8  374.74  5138.6  374.28  5144.5  375.18  5153.4  374.99
  5159.9  373.62  5165.8  375.34  5175.2  374.26  5181.1  375.51  5188.8  374.61
  5196.4  374.49  5233.0  375.58  5369.8  376.76  5421.7  377.65  5471.8  379.76
#Mann=3,-1,0
  4745.1    0.05       0  5027.0    0.04       0  5031.0    0.05       0
Bank Sta=5027,5031
Exp/Cntr=0.3,0.1

Type RM Length L Ch R = 1,12351,386,386,386
BEGIN DESCRIPTION:
Lynn Creek T 17 27.0
END DESCRIPTION:
XS GIS Cut Line= 3
      2718425.98      6795111.00      2718176.00      6795061.00
      2717876.04      6795310.97
#Sta/Elev= 30
  4750.2  378.00  4801.2  375.00  4842.0  373.71  4923.6  369.45  4933.7  369.05
  4964.3  369.51  4974.5  368.82  4982.7  366.58  4983.0  366.08  4986.5  366.08
  4986.7  366.58  4994.9  366.68  5002.6  367.92  5008.4  367.92  5012.3  368.95
  5026.6  368.25  5104.7  368.65  5133.4  372.34  5139.9  371.78  5147.7  372.60
  5154.2  372.21  5161.3  372.99  5189.3  372.59  5211.5  374.10  5218.0  375.13
  5232.3  375.60  5246.6  375.53  5267.4  376.56  5353.3  376.91  5395.6  378.07
#Mann=3,-1,0
  4750.2    0.05       0  4982.7    0.04       0  4986.7    0.05       0
Bank Sta=4982.7,4986.7
Exp/Cntr=0.3,0.1

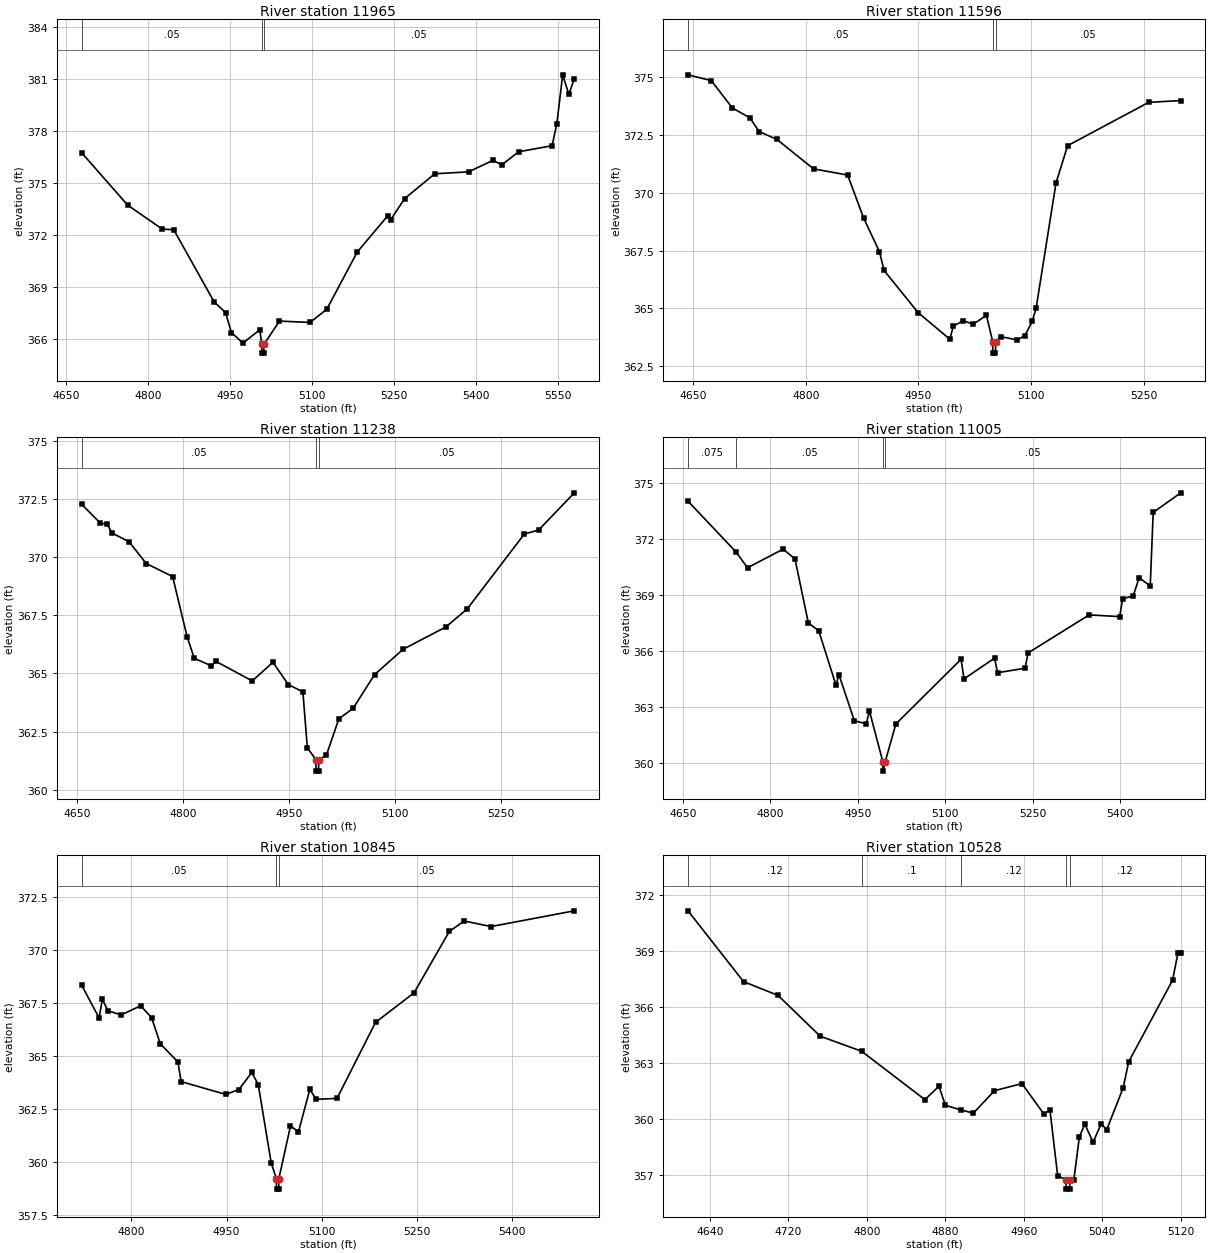
Type RM Length L Ch R = 1,11965,369,369,369
BEGIN DESCRIPTION:
Lynn Creek T 17 26.0
END DESCRIPTION:
XS GIS Cut Line= 3
      2718576.03      6794811.01      2718276.00      6794711.00
      2717725.99      6794911.00
#Sta/Elev= 30
  4678.2  376.77  4762.6  373.74  4825.8  372.36  4846.9  372.32  4920.7  368.16
  4941.7  367.54  4952.3  366.39  4973.4  365.78  5004.4  366.55  5007.8  365.70
  5008.0  365.20  5011.5  365.20  5011.8  365.70  5040.3  367.05  5096.2  366.97
  5126.8  367.73  5182.7  371.04  5238.5  373.13  5243.8  372.90  5269.1  374.11
  5324.3  375.55  5386.2  375.66  5430.7  376.32  5447.3  376.07  5477.9  376.82
  5539.1  377.17  5547.8  378.45  5558.4  381.26  5569.7  380.13  5579.7  381.04
#Mann=3,-1,0
  4678.2    0.05       0  5007.8    0.04       0  5011.8    0.05       0
Bank Sta=5007.8,5011.8
Exp/Cntr=0.3,0.1

Type RM Length L Ch R = 1,11596,358,358,358
BEGIN DESCRIPTION:
Lynn Creek T 17 25.0
END DESCRIPTION:
XS GIS Cut Line= 3
      2718625.61      6794553.74      2718326.00      6794361.00
      2718034.41      6794290.70
#Sta/Elev= 30
  4643.3  375.09  4674.3  374.84  4702.3  373.66  4725.8  373.23  4738.0  372.64
  4761.7  372.30  4810.4  371.03  4855.9  370.76  4877.1  368.91  4898.2  367.45
  4904.4  366.64  4949.7  364.82  4992.0  363.67  4996.6  364.24  5009.8  364.47
  5023.1  364.32  5040.7  364.70  5049.0  363.57  5049.2  363.07  5052.7  363.07
  5053.0  363.57  5059.8  363.78  5081.8  363.64  5092.1  363.83  5101.8  364.46
  5106.9  365.02  5133.3  370.41  5148.8  372.03  5256.7  373.90  5299.5  373.98
#Mann=3,-1,0
  4643.3    0.05       0  5049.0    0.04       0  5053.0    0.05       0
Bank Sta=5049,5053
Exp/Cntr=0.3,0.1

Type RM Length L Ch R = 1,11238,233,233,233
BEGIN DESCRIPTION:
Lynn Creek T 17 24.0
END DESCRIPTION:
XS GIS Cut Line= 3
      2718811.82      6794135.49      2718476.00      6794061.00
      2718126.04      6794011.01
#Sta/Elev= 30
  4656.0  372.28  4682.5  371.47  4692.7  371.41  4698.8  371.05  4723.4  370.66
  4747.5  369.73  4784.9  369.17  4805.4  366.58  4815.6  365.65  4839.8  365.33
  4846.3  365.52  4897.6  364.68  4926.9  365.48  4948.8  364.52  4969.3  364.21
  4975.6  361.80  4987.7  361.30  4988.0  360.80  4991.5  360.80  4991.7  361.30
  5002.5  361.48  5020.2  363.05  5040.4  363.50  5070.7  364.95  5111.1  366.04
  5171.7  367.00  5202.0  367.78  5282.8  371.00  5303.0  371.17  5353.5  372.77
#Mann=3,-1,0
  4656.0    0.05       0  4987.7    0.04       0  4991.7    0.05       0
Bank Sta=4987.7,4991.7
Exp/Cntr=0.3,0.1

Type RM Length L Ch R = 1,11005,160,160,160
BEGIN DESCRIPTION:
Mapping XS 98aa4356
END DESCRIPTION:
XS GIS Cut Line= 2
      2718866.34      6793923.83      2718035.82      6793766.96
#Sta/Elev= 30
  4658.7  374.04  4740.7  371.33  4760.8  370.47  4821.9  371.47  4842.2  370.94
  4865.1  367.51  4882.9  367.09  4912.4  364.18  4917.5  364.74  4944.0  362.26
  4964.3  362.10  4969.9  362.78  4992.9  360.06  4993.1  359.56  4996.9  360.06
  5015.2  362.09  5127.0  365.56  5132.1  364.51  5184.5  365.62  5189.6  364.84
  5236.9  365.08  5241.9  365.90  5346.7  367.94  5399.1  367.85  5404.2  368.81
  5422.3  368.96  5432.5  369.94  5451.5  369.49  5456.6  373.44  5503.9  374.49
#Mann=4,-1,0
  4658.7   0.075       0  4740.7    0.05       0  4992.9    0.04       0
  4996.9    0.05       0
Bank Sta=4992.9,4996.9
Exp/Cntr=0.3,0.1

Type RM Length L Ch R = 1,10845,317,317,317
BEGIN DESCRIPTION:
Lynn Creek T 17 23.0
END DESCRIPTION:
XS GIS Cut Line= 3
      2718846.42      6793783.00      2718576.09      6793716.04
      2718084.83      6793633.78
#Sta/Elev= 30
  4721.5  368.35  4749.1  366.80  4754.3  367.67  4763.1  367.14  4783.7  366.94
  4814.7  367.37  4831.9  366.81  4845.6  365.58  4873.3  364.73  4878.5  363.80
  4948.6  363.20  4969.2  363.42  4989.8  364.23  5000.0  363.66  5020.4  359.97
  5028.5  359.24  5028.8  358.74  5032.3  358.74  5032.5  359.24  5050.8  361.71
  5063.4  361.44  5081.2  363.43  5091.3  362.97  5124.1  363.01  5184.8  366.59
  5245.5  367.98  5301.1  370.87  5324.5  371.36  5366.9  371.10  5498.1  371.84
#Mann=3,-1,0
  4721.5    0.05       0  5028.5    0.03       0  5032.5    0.05       0
Bank Sta=5028.5,5032.5
Exp/Cntr=0.3,0.1

Type RM Length L Ch R = 1,10528,691,691,691
BEGIN DESCRIPTION:
Lynn Creek T 17 22.0
END DESCRIPTION:
XS GIS Cut Line= 3
      2718925.99      6793660.99      2718626.00      6793411.00
      2718526.00      6793361.00
#Sta/Elev= 30
  4617.6  371.14  4674.2  367.35  4709.4  366.61  4752.3  364.43  4794.6  363.62
  4859.1  361.03  4873.4  361.75  4879.9  360.73  4896.3  360.47  4908.5  360.31
  4930.0  361.51  4958.0  361.89  4980.1  360.28  4986.6  360.45  4994.4  356.96
  5002.8  356.74  5003.1  356.24  5006.6  356.24  5006.8  356.74  5010.9  356.74
  5016.5  359.03  5022.1  359.72  5030.5  358.75  5038.8  359.74  5044.4  359.42
  5061.2  361.67  5066.8  363.06  5111.5  367.42  5117.1  368.90  5119.9  368.90
#Mann=5,-1,0
  4617.6    0.12       0  4794.6     0.1       0  4896.3    0.12       0
  5002.8    0.07       0  5006.8    0.12       0
Bank Sta=5002.8,5006.8
Exp/Cntr=0.3,0.1

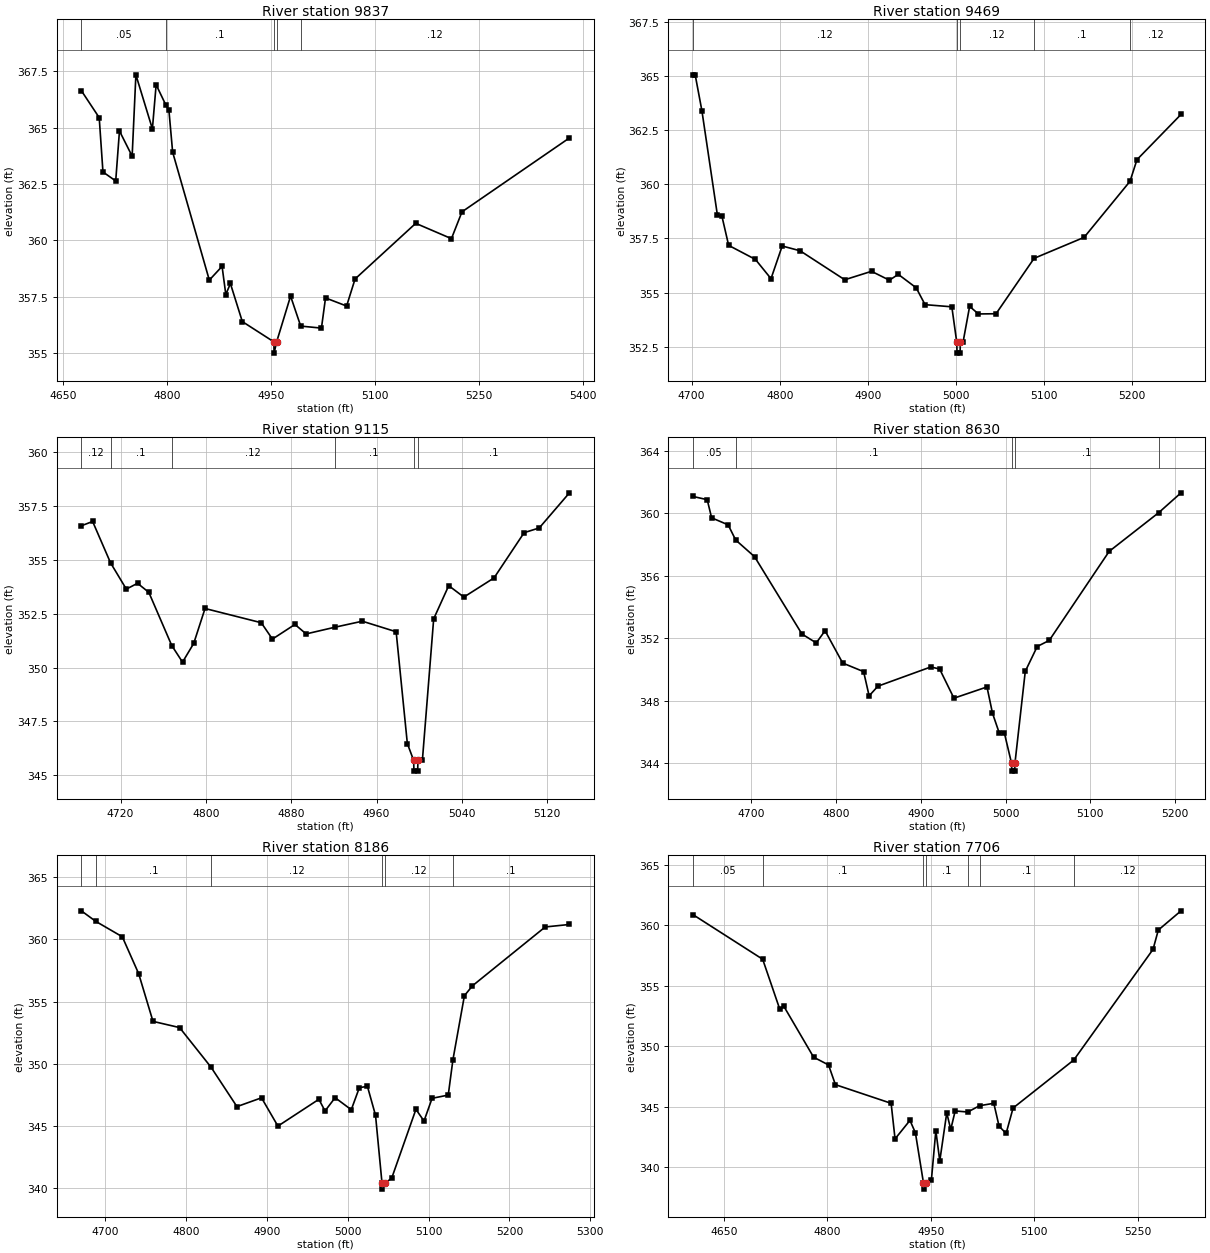
Type RM Length L Ch R = 1,9837,368,368,368
BEGIN DESCRIPTION:
Lynn Creek T 17 21.0
END DESCRIPTION:
XS GIS Cut Line= 3
      2719074.28      6792835.80      2718776.00      6792961.00
      2718456.02      6793166.92
#Sta/Elev= 30
  4676.3  366.65  4702.1  365.45  4707.5  363.04  4725.9  362.64  4731.3  364.86
  4749.6  363.74  4755.0  367.35  4778.8  364.95  4784.2  366.91  4798.2  366.01
  4802.6  365.79  4808.0  363.92  4860.9  358.24  4879.3  358.85  4884.7  357.60
  4891.3  358.09  4908.5  356.40  4954.0  355.50  4954.3  355.00  4958.0  355.50
  4978.1  357.53  4992.7  356.20  5022.6  356.11  5028.5  357.45  5058.9  357.09
  5071.1  358.29  5158.6  360.76  5210.1  360.08  5225.3  361.27  5380.3  364.55
#Mann=5,-1,0
  4676.3    0.05       0  4798.2     0.1       0  4954.0    0.07       0
  4958.0     0.1       0  4992.7    0.12       0
Bank Sta=4954,4958
Exp/Cntr=0.3,0.1

Type RM Length L Ch R = 1,9469,354,354,354
BEGIN DESCRIPTION:
Lynn Creek T 17 20.0
END DESCRIPTION:
XS GIS Cut Line= 3
      2718876.02      6792711.00      2718576.00      6792661.00
      2718325.96      6792661.00
#Sta/Elev= 30
  4701.4  365.06  4704.0  365.06  4711.6  363.41  4729.3  358.56  4734.4  358.52
  4742.0  357.18  4772.4  356.53  4790.1  355.64  4802.8  357.15  4823.1  356.93
  4873.8  355.59  4904.2  355.98  4924.5  355.57  4934.6  355.84  4954.9  355.22
  4965.0  354.44  4995.4  354.34  5001.0  352.70  5001.3  352.20  5004.8  352.20
  5005.0  352.70  5008.1  352.70  5015.6  354.36  5025.6  354.01  5045.6  354.02
  5088.8  356.58  5145.6  357.55  5197.7  360.14  5205.6  361.14  5255.6  363.23
#Mann=5,-1,0
  4701.4    0.12       0  5001.0    0.07       0  5005.0    0.12       0
  5088.8     0.1       0  5197.7    0.12       0
Bank Sta=5001,5005
Exp/Cntr=0.3,0.1

Type RM Length L Ch R = 1,9115,485,485,485
BEGIN DESCRIPTION:
Lynn Creek T 17 19.0
END DESCRIPTION:
XS GIS Cut Line= 3
      2718726.01      6792261.00      2718426.00      6792361.00
      2718325.97      6792461.03
#Sta/Elev= 30
  4683.2  356.58  4693.8  356.78  4710.6  354.86  4725.4  353.64  4735.9  353.91
  4746.5  353.49  4768.0  351.02  4778.1  350.25  4788.6  351.12  4799.2  352.74
  4851.9  352.08  4862.4  351.32  4883.5  352.00  4894.0  351.56  4920.9  351.87
  4946.7  352.15  4978.4  351.66  4988.9  346.47  4994.8  345.69  4995.1  345.19
  4998.6  345.19  4998.8  345.69  5003.0  345.69  5013.6  352.26  5027.7  353.80
  5041.9  353.27  5070.2  354.16  5098.4  356.26  5112.6  356.48  5140.9  358.11
#Mann=6,-1,0
  4683.2    0.12       0  4710.6     0.1       0  4768.0    0.12       0
  4920.9     0.1       0  4994.8    0.07       0  4998.8     0.1       0
Bank Sta=4994.8,4998.8
Exp/Cntr=0.3,0.1

Type RM Length L Ch R = 1,8630,444,444,444
BEGIN DESCRIPTION:
Lynn Creek T 17 18.0
END DESCRIPTION:
XS GIS Cut Line= 3
      2718875.98      6792011.00      2718526.00      6791911.00
      2718376.02      6791761.02
#Sta/Elev= 30
  4631.0  361.08  4647.9  360.87  4653.1  359.71  4672.6  359.26  4681.5  358.29
  4703.8  357.22  4759.7  352.27  4776.6  351.70  4787.0  352.48  4807.8  350.41
  4832.5  349.86  4839.0  348.31  4849.4  348.93  4911.8  350.16  4922.2  350.03
  4939.1  348.16  4978.1  348.88  4984.6  347.20  4992.4  345.96  4998.5  345.96
  5007.1  343.99  5007.4  343.49  5010.9  343.49  5011.1  343.99  5023.3  349.88
  5037.4  351.47  5051.6  351.86  5122.3  357.56  5181.0  360.05  5207.1  361.31
#Mann=5,-1,0
  4631.0    0.05       0  4681.5     0.1       0  5007.1    0.07       0
  5011.1     0.1       0  5181.0    0.05       0
Bank Sta=5007.1,5011.1
Exp/Cntr=0.3,0.1

Type RM Length L Ch R = 1,8186,480,480,480
BEGIN DESCRIPTION:
Lynn Creek T 17 17.0
END DESCRIPTION:
XS GIS Cut Line= 3
      2718975.99      6791461.00      2718676.00      6791511.00
      2718376.03      6791511.00
#Sta/Elev= 30
  4670.1  362.31  4688.0  361.46  4720.8  360.22  4741.1  357.24  4758.8  353.40
  4791.7  352.90  4830.6  349.71  4862.7  346.53  4893.1  347.24  4913.4  344.96
  4964.1  347.12  4971.7  346.18  4984.2  347.25  5004.2  346.28  5014.2  348.06
  5024.2  348.16  5034.2  345.83  5042.2  340.38  5042.5  339.88  5046.3  340.38
  5054.2  340.76  5084.2  346.31  5094.2  345.37  5104.2  347.20  5124.2  347.46
  5130.0  350.31  5144.2  355.47  5154.2  356.27  5244.2  361.01  5274.2  361.21
#Mann=6,-1,0
  4670.1    0.05       0  4688.0     0.1       0  4830.6    0.12       0
  5042.2    0.07       0  5046.3    0.12       0  5130.0     0.1       0
Bank Sta=5042.2,5046.3
Exp/Cntr=0.3,0.1

Type RM Length L Ch R = 1,7706,428,428,428
BEGIN DESCRIPTION:
Lynn Creek T 17 16.0
END DESCRIPTION:
XS GIS Cut Line= 3
      2719025.96      6791310.98      2718676.00      6791111.00
      2718376.00      6791161.00
#Sta/Elev= 30
  4605.2  360.89  4706.3  357.20  4731.1  353.07  4736.9  353.32  4780.1  349.11
  4801.7  348.47  4811.7  346.84  4892.4  345.30  4898.1  342.36  4919.7  343.89
  4927.6  342.86  4939.3  338.71  4939.6  338.21  4943.4  338.71  4950.7  338.94
  4957.2  343.04  4962.9  340.54  4973.0  344.51  4978.8  343.14  4985.2  344.67
  5003.4  344.58  5020.5  345.10  5041.2  345.30  5048.8  343.41  5059.0  342.81
  5069.1  344.91  5157.1  348.88  5271.9  358.02  5279.5  359.61  5312.4  361.20
#Mann=7,-1,0
  4605.2    0.05       0  4706.3     0.1       0  4939.3    0.07       0
  4943.4     0.1       0  5003.4    0.12       0  5020.5     0.1       0
  5157.1    0.12       0
Bank Sta=4939.3,4943.4
Exp/Cntr=0.3,0.1

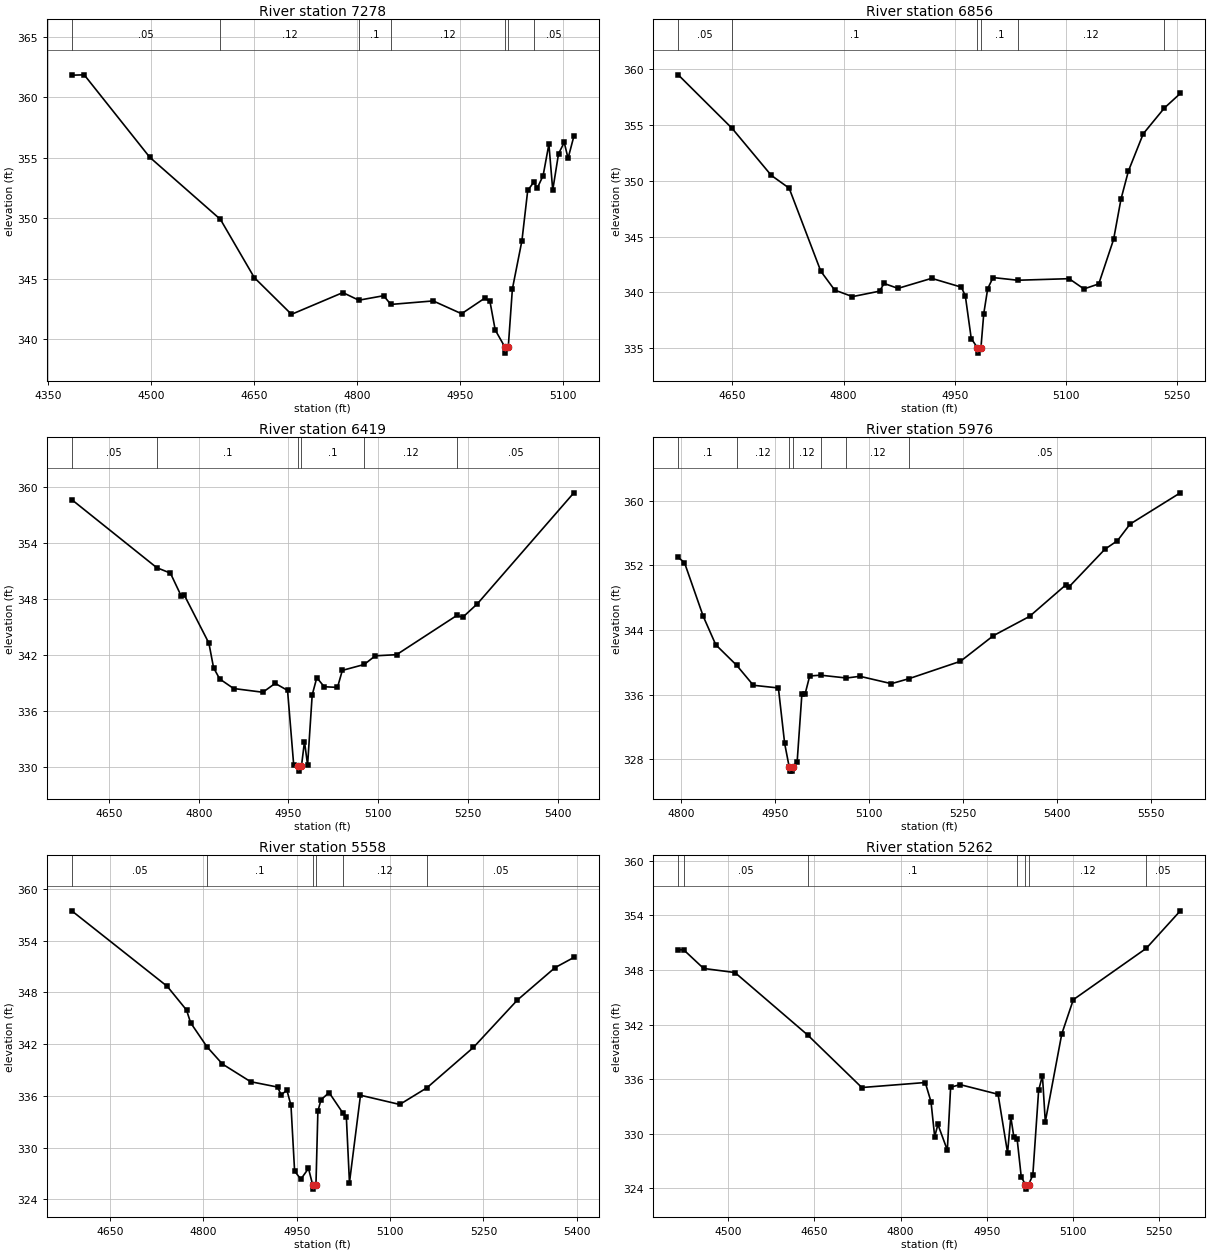
Type RM Length L Ch R = 1,7278,422,422,422
BEGIN DESCRIPTION:
Lynn Creek T 17 15.0
END DESCRIPTION:
XS GIS Cut Line= 3
      2719026.04      6790660.99      2718426.00      6790811.00
      2718326.01      6790761.01
#Sta/Elev= 30
  4384.9  361.83  4403.0  361.86  4498.3  355.04  4601.1  349.90  4650.4  345.08
  4704.5  342.04  4779.2  343.84  4802.4  343.21  4838.5  343.58  4849.0  342.86
  4910.6  343.15  4951.9  342.09  4985.4  343.37  4993.1  343.13  5000.8  340.75
  5014.9  339.33  5015.5  338.83  5019.8  339.33  5025.8  344.14  5039.7  348.14
  5048.1  352.29  5056.7  352.96  5062.1  352.50  5070.5  353.52  5078.9  356.12
  5084.5  352.32  5092.9  355.32  5101.2  356.27  5106.8  354.95  5115.2  356.77
#Mann=7,-1,0
  4384.9    0.05       0  4601.1    0.12       0  4802.4     0.1       0
  4849.0    0.12       0  5014.9    0.07       0  5019.8    0.12       0
  5056.7    0.05       0
Bank Sta=5014.9,5019.8
Exp/Cntr=0.3,0.1

Type RM Length L Ch R = 1,6856,437,437,437
BEGIN DESCRIPTION:
Lynn Creek T 17 14.0
END DESCRIPTION:
XS GIS Cut Line= 3
      2718976.03      6790611.01      2718576.00      6790461.00
      2718326.04      6790461.00
#Sta/Elev= 30
  4576.9  359.52  4649.5  354.72  4702.4  350.50  4726.5  349.35  4769.2  341.90
  4787.9  340.21  4811.9  339.62  4848.4  340.11  4854.6  340.80  4873.3  340.36
  4918.7  341.26  4958.7  340.47  4964.1  339.70  4972.1  335.86  4980.3  335.05
  4980.9  334.55  4985.2  335.05  4989.0  338.10  4994.3  340.33  5001.5  341.33
  5034.8  341.09  5104.1  341.23  5124.1  340.31  5144.1  340.76  5164.1  344.75
  5174.1  348.37  5184.1  350.89  5204.1  354.23  5232.7  356.55  5254.1  357.85
#Mann=6,-1,0
  4576.9    0.05       0  4649.5     0.1       0  4980.3    0.07       0
  4985.2     0.1       0  5034.8    0.12       0  5232.7    0.05       0
Bank Sta=4980.3,4985.2
Exp/Cntr=0.3,0.1

Type RM Length L Ch R = 1,6419,443,443,443
BEGIN DESCRIPTION:
Lynn Creek T 17 13.0
END DESCRIPTION:
XS GIS Cut Line= 3
      2719025.99      6790211.00      2718626.00      6790111.00
      2718226.00      6789961.00
#Sta/Elev= 30
  4587.7  358.62  4729.8  351.34  4752.6  350.76  4770.7  348.31  4775.8  348.41
  4817.0  343.26  4824.8  340.63  4835.1  339.43  4858.3  338.41  4907.2  338.01
  4927.8  338.96  4948.5  338.21  4958.8  330.21  4966.4  330.07  4967.2  329.57
  4971.7  330.07  4976.8  332.74  4982.0  330.22  4989.7  337.72  4997.4  339.57
  5009.8  338.60  5032.0  338.53  5040.1  340.35  5076.6  340.98  5095.2  341.91
  5130.8  342.03  5231.8  346.24  5241.2  346.02  5266.1  347.49  5427.2  359.35
#Mann=6,-1,0
  4587.7    0.05       0  4729.8     0.1       0  4966.4    0.07       0
  4971.7     0.1       0  5076.6    0.12       0  5231.8    0.05       0
Bank Sta=4966.4,4971.7
Exp/Cntr=0.3,0.1

Type RM Length L Ch R = 1,5976,418,418,418
BEGIN DESCRIPTION:
Lynn Creek T 17 12.0
END DESCRIPTION:
XS GIS Cut Line= 3
      2719025.98      6789861.00      2718826.00      6789861.00
      2718225.96      6789911.00
#Sta/Elev= 30
  4795.2  352.97  4805.2  352.32  4835.2  345.67  4855.2  342.16  4888.7  339.61
  4915.2  337.15  4955.2  336.82  4965.2  329.96  4972.5  327.03  4973.3  326.53
  4977.1  326.53  4977.8  327.03  4985.2  327.71  4992.7  336.02  4997.7  336.02
  5005.2  338.30  5022.6  338.40  5064.0  338.05  5085.5  338.26  5135.7  337.35
  5163.5  337.96  5246.1  340.12  5298.7  343.29  5356.4  345.67  5414.1  349.55
  5419.1  349.29  5476.8  353.98  5496.9  355.04  5517.0  357.09  5597.3  360.96
#Mann=7,-1,0
  4795.2     0.1       0  4888.7    0.12       0  4972.5    0.07       0
  4977.8    0.12       0  5022.6     0.1       0  5064.0    0.12       0
  5163.5    0.05       0
Bank Sta=4972.5,4977.8
Exp/Cntr=0.3,0.1

Type RM Length L Ch R = 1,5558,296,296,296
BEGIN DESCRIPTION:
Lynn Creek T 17 11.0
END DESCRIPTION:
XS GIS Cut Line= 3
      2719125.99      6789711.00      2718776.00      6789511.00
      2718376.02      6789561.00
#Sta/Elev= 30
  4588.9  357.47  4742.2  348.71  4773.2  345.96  4779.7  344.49  4805.9  341.71
  4830.8  339.70  4876.1  337.65  4919.3  337.03  4925.1  336.13  4934.4  336.66
  4940.9  334.89  4946.7  327.29  4956.7  326.34  4969.0  327.59  4975.7  325.69
  4976.4  325.19  4981.0  325.69  4984.1  334.24  4989.1  335.55  5002.1  336.39
  5023.9  334.05  5029.8  333.54  5034.8  325.95  5052.5  336.08  5115.5  335.01
  5159.3  336.95  5233.9  341.63  5304.4  347.12  5364.9  350.88  5395.1  352.06
#Mann=6,-1,0
  4588.9    0.05       0  4805.9     0.1       0  4975.7    0.07       0
  4981.0     0.1       0  5023.9    0.12       0  5159.3    0.05       0
Bank Sta=4975.7,4981
Exp/Cntr=0.3,0.1

Type RM Length L Ch R = 1,5262,619,619,619
BEGIN DESCRIPTION:
Lynn Creek T 17 10.0
END DESCRIPTION:
XS GIS Cut Line= 3
      2719115.08      6789553.49      2718595.84      6789281.00
      2718310.98      6789251.33
#Sta/Elev= 30
  4413.6  350.22  4423.0  350.21  4457.7  348.16  4512.2  347.71  4638.8  340.84
  4732.7  335.08  4843.0  335.63  4853.0  333.52  4859.4  329.68  4865.0  331.03
  4881.4  328.20  4887.1  335.11  4903.5  335.40  4969.6  334.34  4986.1  327.91
  4991.7  331.86  4997.1  329.62  5002.8  329.39  5009.9  325.25  5017.2  324.42
  5018.0  323.92  5022.6  324.42  5030.0  325.46  5040.1  334.76  5046.7  336.39
  5051.7  331.32  5080.3  340.96  5100.4  344.73  5227.2  350.37  5286.4  354.49
#Mann=7,-1,0
  4413.6     0.1       0  4423.0    0.05       0  4638.8     0.1       0
  5002.8    0.12       0  5017.2    0.07       0  5022.6    0.12       0
  5227.2    0.05       0
Bank Sta=5017.2,5022.6
Exp/Cntr=0.3,0.1