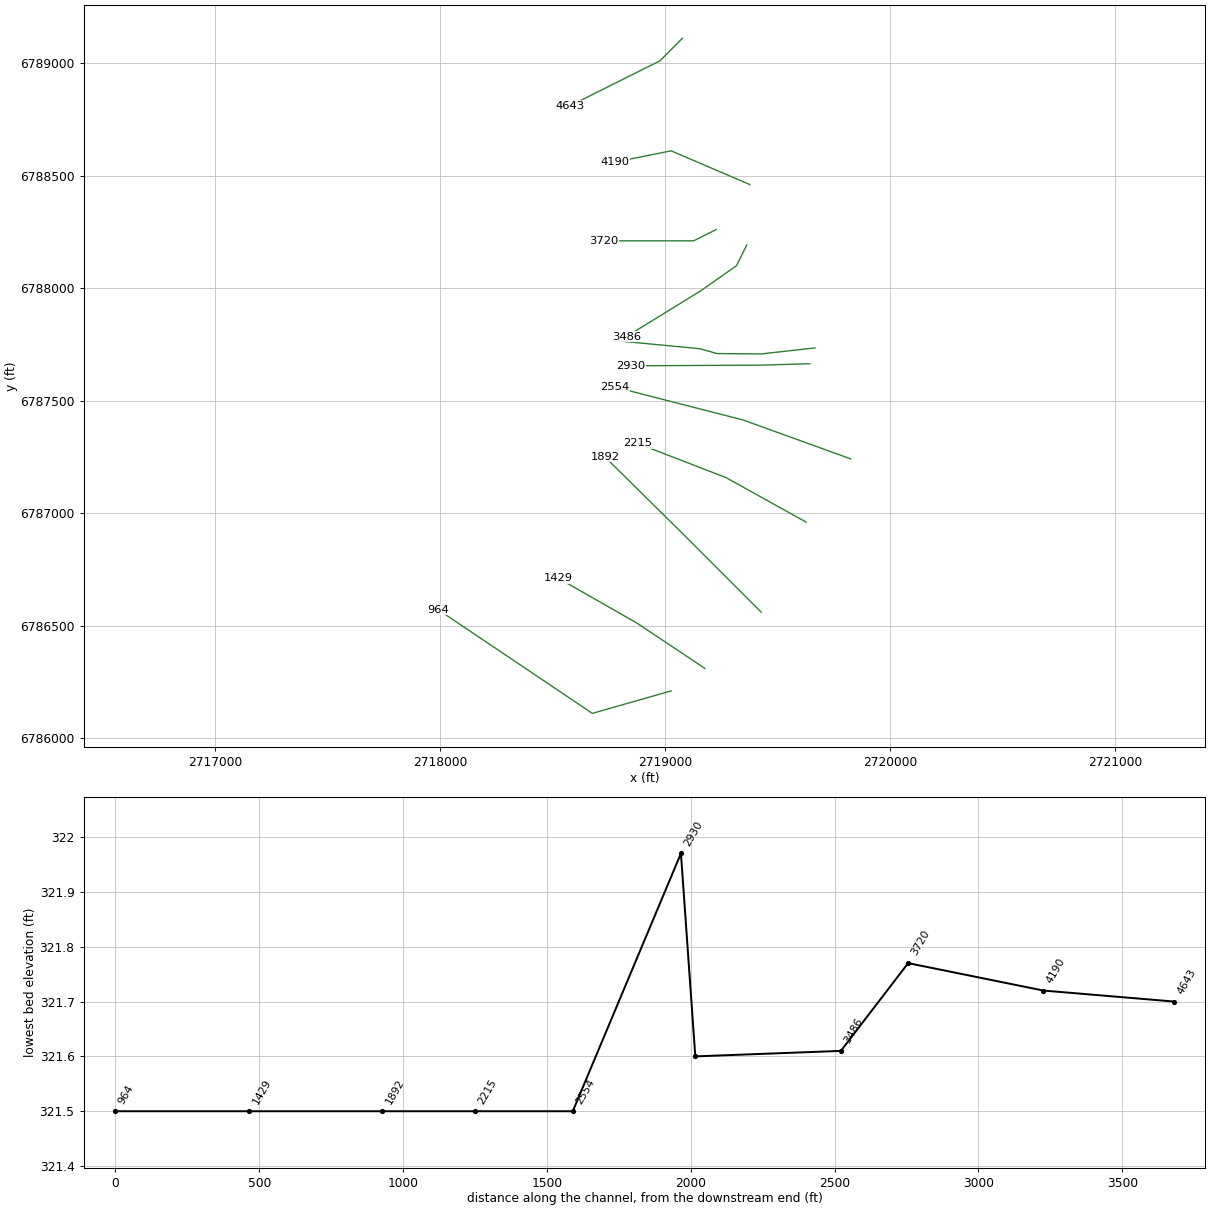
HEC-RAS study Lynn Creek T 17.prj: Lynn Creek T 17 Base Level Engineering

--- Lynn Creek T 17.g01 (geometry) --- (continued)

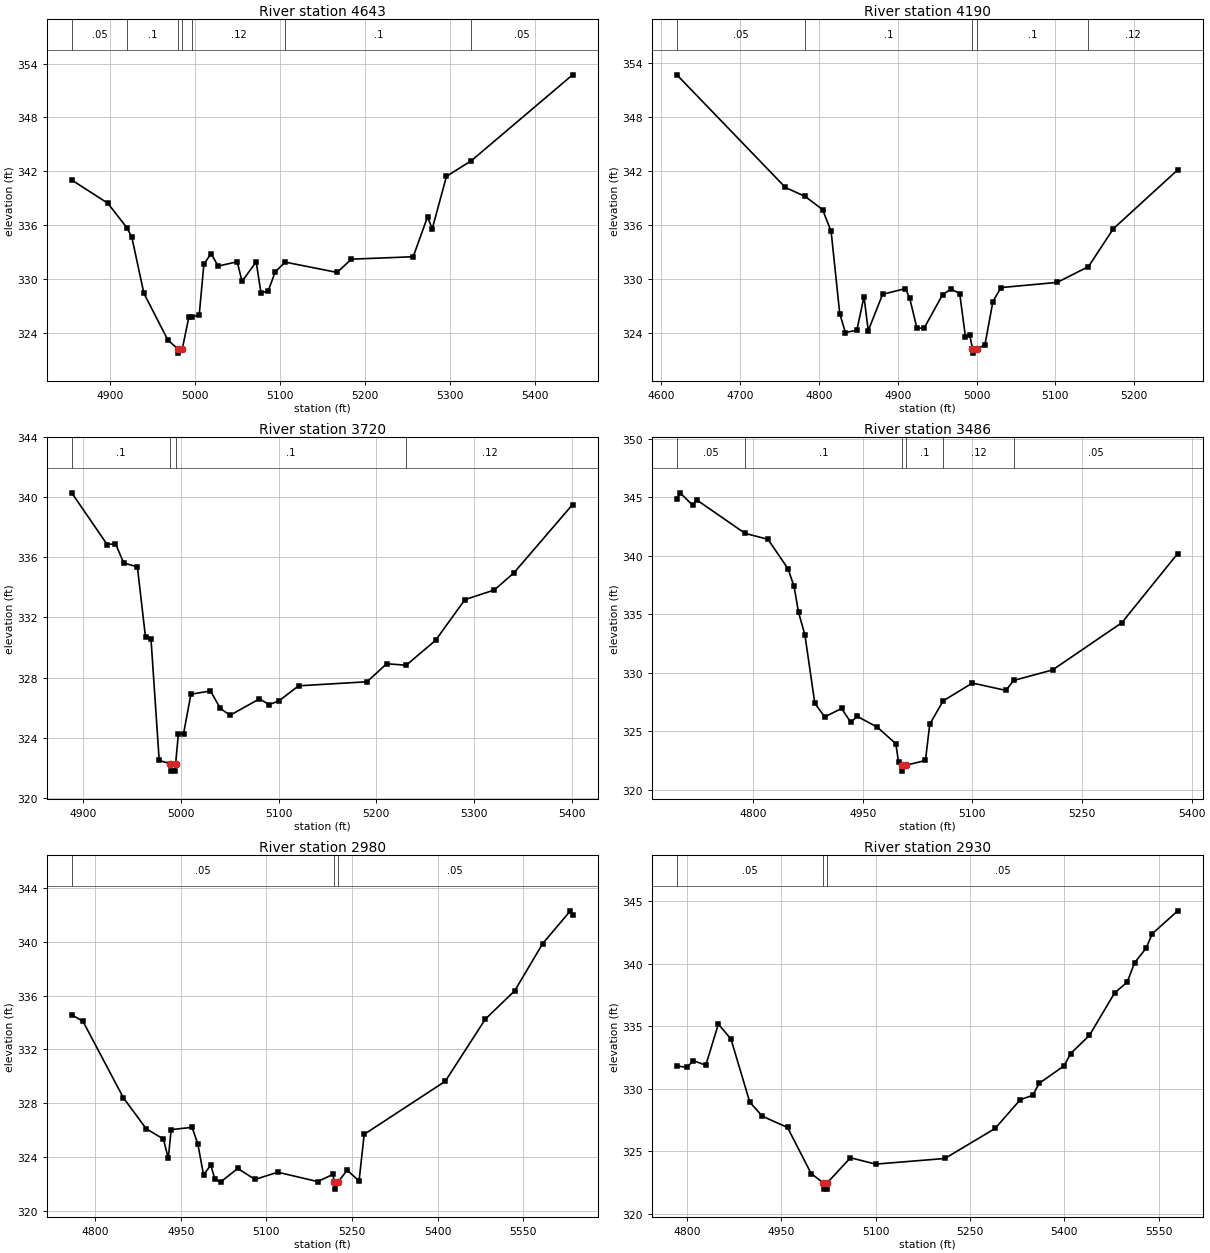
Type RM Length L Ch R = 1,4643,453,453,453
BEGIN DESCRIPTION:
Lynn Creek T 17 9.0
END DESCRIPTION:
XS GIS Cut Line= 3
      2719075.97      6789110.97      2718976.00      6789011.00
      2718575.99      6788810.99
#Sta/Elev= 30
  4855.1  341.01  4897.5  338.42  4920.0  335.68  4925.8  334.61  4939.9  328.38
  4968.2  323.14  4979.5  322.20  4980.4  321.70  4985.1  322.20  4992.9  325.78
  4996.7  325.78  5004.9  325.93  5010.4  331.60  5018.8  332.81  5027.2  331.41
  5049.6  331.89  5055.2  329.71  5071.9  331.87  5077.5  328.43  5085.9  328.62
  5094.3  330.77  5106.0  331.85  5167.0  330.70  5183.7  332.18  5256.4  332.45
  5273.2  336.89  5278.8  335.58  5295.5  341.42  5324.7  343.16  5443.7  352.74
#Mann=7,-1,0
  4855.1    0.05       0  4920.0     0.1       0  4979.5    0.07       0
  4985.1     0.1       0  4996.7    0.12       0  5106.0     0.1       0
  5324.7    0.05       0
Bank Sta=4979.5,4985.1
Exp/Cntr=0.3,0.1

Type RM Length L Ch R = 1,4190,470,470,470
BEGIN DESCRIPTION:
Lynn Creek T 17 8.0
END DESCRIPTION:
XS GIS Cut Line= 3
      2719375.96      6788461.02      2719026.00      6788611.00
      2718775.99      6788561.00
#Sta/Elev= 30
  4619.7  352.72  4757.5  340.17  4782.6  339.17  4804.6  337.71  4815.5  335.27
  4826.4  326.13  4833.6  324.01  4848.1  324.28  4857.2  328.00  4862.6  324.22
  4880.8  328.27  4909.8  328.91  4915.2  327.84  4924.3  324.52  4933.4  324.49
  4956.9  328.23  4967.8  328.86  4978.7  328.35  4985.9  323.55  4991.4  323.72
  4994.9  322.22  4995.8  321.72  5000.5  322.22  5010.6  322.61  5020.8  327.46
  5031.0  329.02  5102.4  329.60  5142.1  331.36  5173.8  335.59  5255.4  342.14
#Mann=5,-1,0
  4619.7    0.05       0  4782.6     0.1       0  4994.9    0.07       0
  5000.5     0.1       0  5142.1    0.12       0
Bank Sta=4994.9,5000.5
Exp/Cntr=0.3,0.1

Type RM Length L Ch R = 1,3720,234,234,234
BEGIN DESCRIPTION:
Lynn Creek T 17 7.0
END DESCRIPTION:
XS GIS Cut Line= 3
      2719225.97      6788260.99      2719126.00      6788211.00
      2718725.97      6788211.00
#Sta/Elev= 30
  4888.7  340.30  4925.0  336.85  4933.4  336.92  4941.8  335.63  4955.8  335.37
  4964.1  330.68  4969.7  330.58  4978.1  322.48  4989.2  322.27  4990.1  321.77
  4994.0  321.77  4994.9  322.27  4997.7  324.27  5003.0  324.27  5010.5  326.89
  5030.5  327.11  5040.5  325.95  5050.5  325.49  5080.5  326.58  5090.5  326.20
  5100.5  326.45  5120.5  327.45  5190.5  327.72  5210.5  328.92  5230.5  328.82
  5260.5  330.48  5290.5  333.19  5320.5  333.83  5340.5  334.97  5400.5  339.52
#Mann=4,-1,0
  4888.7     0.1       0  4989.2    0.07       0  4994.9     0.1       0
  5230.5    0.12       0
Bank Sta=4989.2,4994.9
Exp/Cntr=0.3,0.1

Type RM Length L Ch R = 1,3486,506,506,506
BEGIN DESCRIPTION:
Lynn Creek T 17 6.0
END DESCRIPTION:
XS GIS Cut Line= 4
      2719361.80      6788192.44      2719316.62      6788100.57
      2719157.47      6787988.87      2718826.85      6787785.26
#Sta/Elev= 30
  4695.9  344.87  4700.4  345.37  4717.3  344.32  4722.9  344.77  4789.2  341.91
  4820.5  341.40  4847.9  338.89  4856.2  337.38  4862.3  335.17  4871.0  333.25
  4884.6  327.40  4898.1  326.24  4921.2  326.96  4933.8  325.77  4942.5  326.29
  4970.1  325.36  4995.4  323.95  4999.2  322.35  5003.3  322.11  5004.2  321.61
  5009.1  322.11  5035.9  322.52  5041.8  325.62  5060.2  327.61  5100.1  329.13
  5146.0  328.50  5156.4  329.35  5209.8  330.25  5304.5  334.28  5381.0  340.19
#Mann=6,-1,0
  4695.9    0.05       0  4789.2     0.1       0  5003.3    0.07       0
  5009.1     0.1       0  5060.2    0.12       0  5156.4    0.05       0
Bank Sta=5003.3,5009.1
Exp/Cntr=0.3,0.1

Type RM Length L Ch R = 1,2980,50,50,50
BEGIN DESCRIPTION:
Mapping XS 36771dac
END DESCRIPTION:
XS GIS Cut Line= 5
      2719665.71      6787735.20      2719425.97      6787708.40
      2719230.43      6787709.99      2719153.78      6787731.59
      2718793.84      6787766.06
#Sta/Elev= 30
  4758.8  334.58  4778.6  334.09  4849.1  328.42  4889.3  326.10  4919.5  325.33
  4928.1  323.89  4933.1  326.03  4969.8  326.20  4979.9  324.96  4989.9  322.66
  5002.5  323.39  5010.0  322.32  5020.0  322.14  5050.0  323.14  5080.0  322.32
  5120.0  322.86  5190.0  322.16  5216.8  322.70  5218.9  322.10  5219.9  321.60
  5225.0  322.10  5241.7  323.01  5262.5  322.21  5271.5  325.68  5413.6  329.63
  5483.9  334.26  5535.2  336.36  5584.4  339.88  5632.9  342.32  5636.8  341.98
#Mann=3,-1,0
  4758.8    0.05       0  5218.9    0.05       0  5225.0    0.05       0
Bank Sta=5218.9,5225
Exp/Cntr=0.3,0.1

Type RM Length L Ch R = 1,2930,376,376,376
BEGIN DESCRIPTION:
Mapping XS db525966
END DESCRIPTION:
XS GIS Cut Line= 3
      2719641.97      6787664.95      2719425.85      6787658.66
      2718845.47      6787655.63
#Sta/Elev= 30
  4784.0  331.83  4800.0  331.70  4810.0  332.25  4830.0  331.88  4850.0  335.17
  4870.0  333.98  4900.0  328.92  4920.0  327.80  4960.0  326.90  4997.6  323.21
  5017.0  322.47  5018.0  321.97  5022.1  321.97  5023.1  322.47  5060.1  324.48
  5100.1  323.97  5210.1  324.42  5290.1  326.82  5330.1  329.12  5350.1  329.48
  5360.1  330.43  5400.1  331.84  5410.1  332.81  5440.1  334.26  5480.1  337.66
  5500.1  338.52  5512.0  340.08  5530.1  341.23  5540.1  342.40  5580.6  344.23
#Mann=3,-1,0
  4784.0    0.05       0  5017.0    0.05       0  5023.1    0.05       0
Bank Sta=5017,5023.1
Exp/Cntr=0.3,0.1

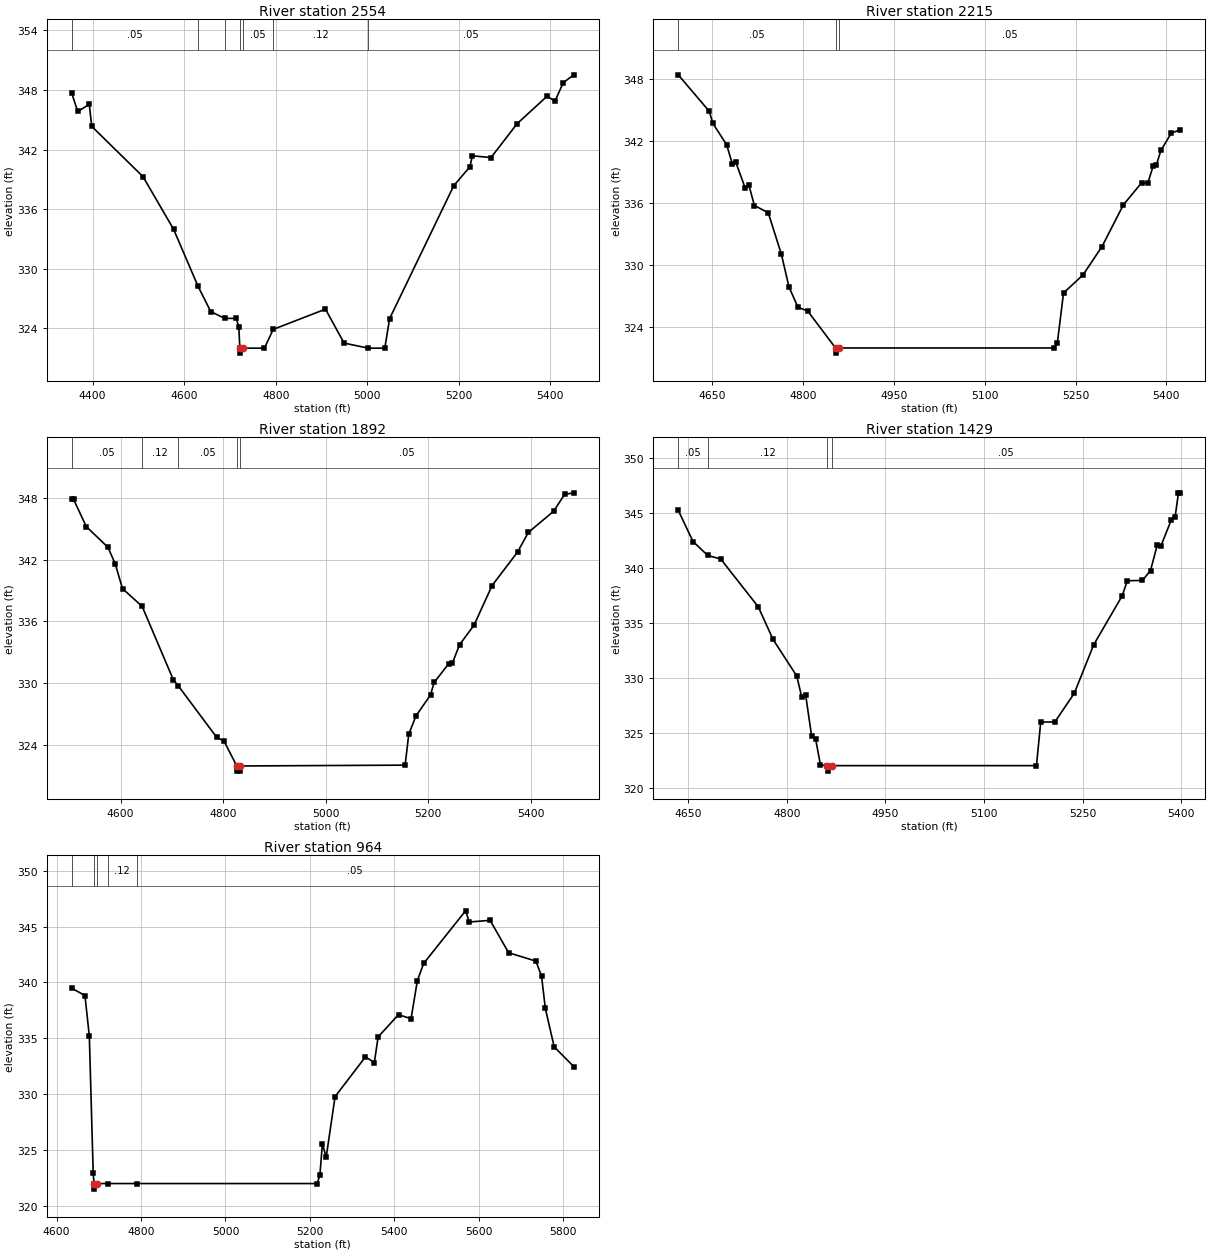
Type RM Length L Ch R = 1,2554,339,339,339
BEGIN DESCRIPTION:
Lynn Creek T 17 5.0
END DESCRIPTION:
XS GIS Cut Line= 3
      2719824.25      6787241.97      2719345.72      6787414.89
      2718775.97      6787561.01
#Sta/Elev= 30
  4354.3  347.67  4367.3  345.84  4392.6  346.55  4397.9  344.34  4510.0  339.27
  4576.6  333.99  4630.3  328.22  4657.9  325.69  4688.3  325.00  4713.9  325.00
  4719.3  324.10  4721.5  322.00  4722.5  321.50  4727.6  322.00  4775.3  322.00
  4794.4  323.89  4908.6  325.93  4949.3  322.51  5002.2  322.00  5038.3  322.00
  5048.7  324.97  5188.8  338.35  5224.2  340.27  5229.6  341.37  5270.4  341.20
  5327.4  344.61  5392.7  347.37  5410.0  346.88  5428.3  348.75  5451.3  349.53
#Mann=7,-1,0
  4354.3    0.05       0  4630.3    0.12       0  4688.3    0.05       0
  4721.5    0.07       0  4727.6    0.05       0  4794.4    0.12       0
  5002.2    0.05       0
Bank Sta=4721.5,4727.6
Exp/Cntr=0.3,0.1

Type RM Length L Ch R = 1,2215,323,323,323
BEGIN DESCRIPTION:
Lynn Creek T 17 4.0
END DESCRIPTION:
XS GIS Cut Line= 3
      2719625.98      6786961.01      2719270.67      6787158.49
      2718876.01      6787311.00
#Sta/Elev= 30
  4593.5  348.44  4644.9  344.90  4650.7  343.74  4673.6  341.66  4682.7  339.85
  4688.4  340.01  4704.4  337.44  4710.1  337.80  4719.3  335.79  4742.2  335.09
  4763.9  331.08  4776.5  327.90  4791.4  325.94  4807.4  325.58  4853.4  322.00
  4854.4  321.50  4859.9  322.00  5214.5  322.00  5219.9  322.48  5230.1  327.32
  5262.3  329.07  5293.7  331.82  5329.0  335.85  5359.0  337.98  5369.5  337.97
  5378.2  339.61  5383.5  339.70  5391.0  341.12  5408.1  342.79  5423.1  343.13
#Mann=3,-1,0
  4593.5    0.05       0  4853.4    0.03       0  4859.9    0.05       0
Bank Sta=4853.4,4859.9
Exp/Cntr=0.3,0.1

Type RM Length L Ch R = 1,1892,463,463,463
BEGIN DESCRIPTION:
Lynn Creek T 17 3.0
END DESCRIPTION:
XS GIS Cut Line= 3
      2719426.00      6786561.00      2719076.00      6786911.00
      2718731.07      6787251.55
#Sta/Elev= 30
  4504.8  347.83  4508.3  347.83  4533.1  345.19  4575.5  343.18  4589.7  341.56
  4603.8  339.18  4642.1  337.46  4702.8  330.37  4712.8  329.75  4787.6  324.77
  4801.8  324.42  4826.8  322.00  4827.9  321.50  4832.3  321.50  4833.3  322.00
  5155.3  322.08  5162.4  325.09  5176.6  326.86  5204.8  328.88  5211.9  330.09
  5240.2  331.90  5247.3  331.94  5261.4  333.74  5289.7  335.64  5325.0  339.48
  5374.6  342.72  5395.7  344.62  5445.3  346.69  5466.4  348.31  5484.5  348.46
#Mann=5,-1,0
  4504.8    0.05       0  4642.1    0.12       0  4712.8    0.05       0
  4826.8    0.03       0  4833.3    0.05       0
Bank Sta=4826.8,4833.3
Exp/Cntr=0.3,0.1

Type RM Length L Ch R = 1,1429,465,465,465
BEGIN DESCRIPTION:
Lynn Creek T 17 2.0
END DESCRIPTION:
XS GIS Cut Line= 3
      2719175.97      6786311.02      2718876.00      6786511.00
      2718526.03      6786710.98
#Sta/Elev= 30
  4634.9  345.23  4657.4  342.39  4679.8  341.12  4699.5  340.80  4756.6  336.45
  4779.1  333.48  4815.1  330.16  4822.7  328.25  4828.7  328.43  4837.7  324.71
  4843.7  324.46  4851.2  322.07  4861.4  322.00  4862.5  321.50  4868.0  322.00
  5179.7  322.00  5186.2  325.96  5207.8  325.98  5237.3  328.59  5266.8  333.00
  5310.0  337.44  5317.9  338.82  5340.9  338.85  5353.2  339.75  5363.3  342.05
  5369.0  341.99  5384.9  344.37  5390.6  344.63  5395.7  346.82  5398.5  346.82
#Mann=4,-1,0
  4634.9    0.05       0  4679.8    0.12       0  4861.4    0.03       0
  4868.0    0.05       0
Bank Sta=4861.4,4868
Exp/Cntr=0.3,0.1

Type RM Length L Ch R = 1,964,0,0,0
BEGIN DESCRIPTION:
Lynn Creek T 17 1.0
END DESCRIPTION:
XS GIS Cut Line= 3
      2719025.97      6786210.99      2718676.00      6786111.00
      2717991.41      6786571.26
#Sta/Elev= 30
  4636.0  339.48  4667.2  338.83  4677.6  335.19  4686.7  322.98  4688.6  322.00
  4689.6  321.50  4695.2  322.00  4721.0  322.00  4789.8  322.00  5216.9  322.00
  5223.5  322.74  5229.5  325.57  5238.4  324.34  5259.5  329.78  5331.5  333.34
  5352.5  332.83  5361.4  335.12  5409.7  337.12  5439.4  336.75  5454.4  340.17
  5469.4  341.71  5568.4  346.41  5577.4  345.41  5626.6  345.56  5670.4  342.66
  5735.0  341.91  5748.4  340.57  5757.4  337.67  5778.4  334.23  5824.9  332.46
#Mann=5,-1,0
  4636.0    0.05       0  4688.6    0.03       0  4695.2    0.05       0
  4721.0    0.12       0  4789.8    0.05       0
Bank Sta=4688.6,4695.2
Exp/Cntr=0.3,0.1

Chan Stop Cuts=-1