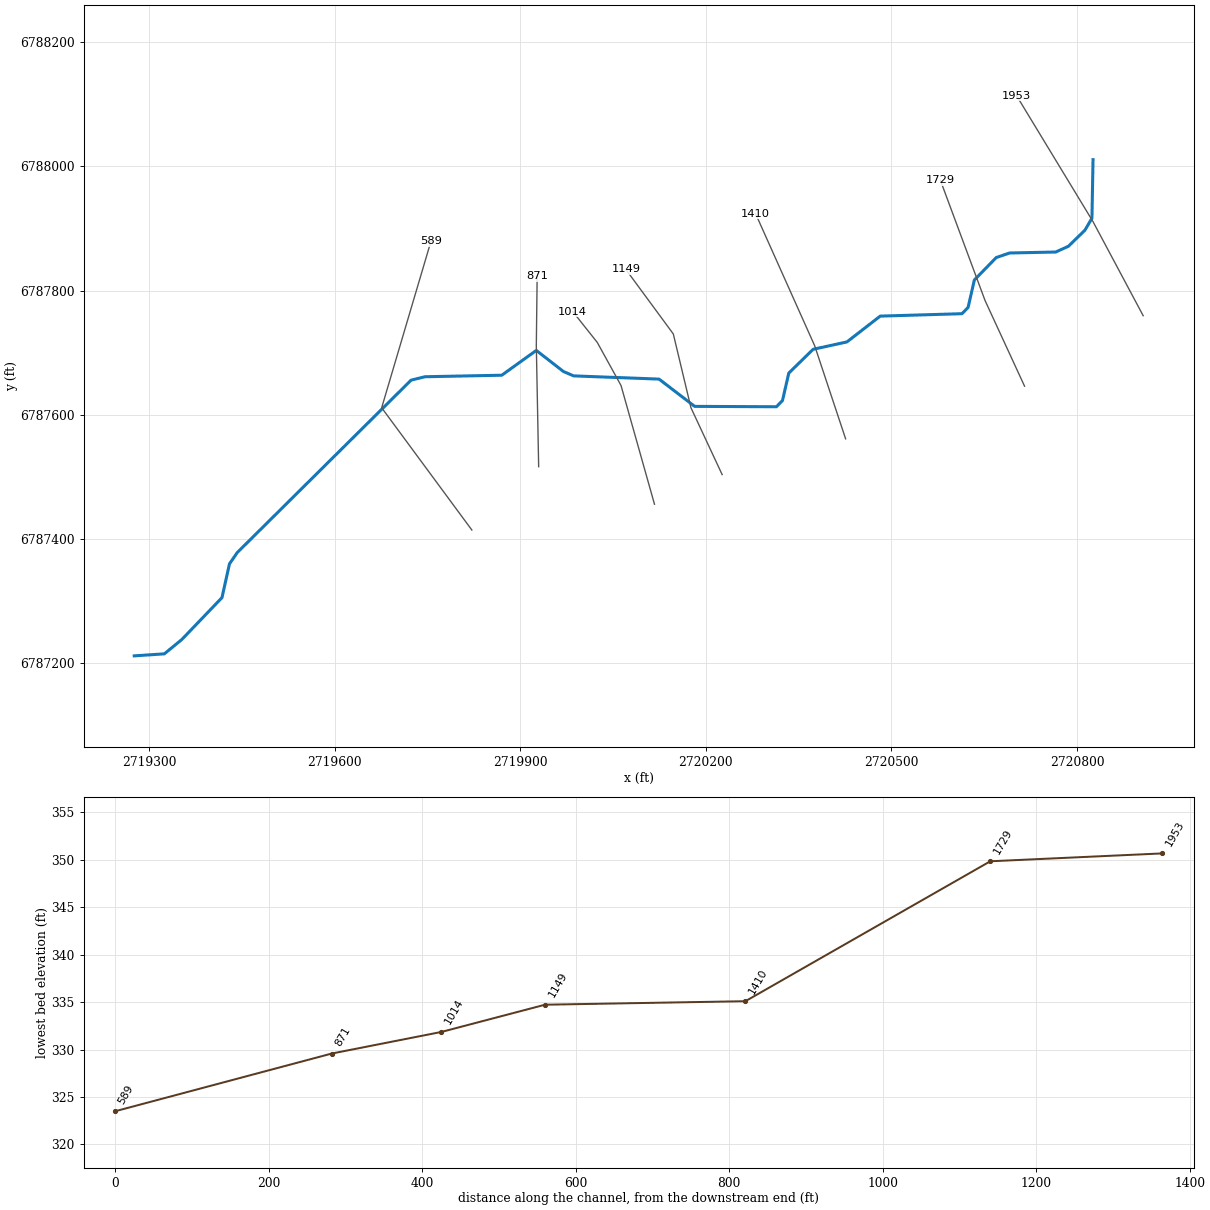
--- Lynn Creek T 18.prj (project) ---

Proj Title=Lynn Creek T 18 Base Level Engineering
Current Plan=p01
Default Exp/Contr=0.3,0.1
English Units
Geom File=g01
Flow File=f01
Plan File=p01
BEGIN DESCRIPTION:
Lynn Creek T 18
END DESCRIPTION:

--- Lynn Creek T 18.p01 (plan) ---

Plan Title=Multiple Run
Short Identifier=Multiple
Geom File=g01
Flow File=f01
Subcritical Flow
K Sum by GR= 0
Std Step Tol= 0.01
Critical Tol= 0.01
Num of Std Step Trials= 20
Max Error Tol= 0.3
Flow Tol Ratio= 0.001
Split Flow NTrial= 30
Split Flow Tol= 0.02
Split Flow Ratio= 0.02
Log Output Level= 0
Friction Slope Method= 1
Unsteady Friction Slope Method= 2
Unsteady Bridges Friction Slope Method= 1
Parabolic Critical Depth
Global Vel Dist=  1 , 1 , 1
Global Log Level= 0
CheckData=True
Encroach Param= -1, 0, 0, 0
BEGIN DESCRIPTION:
Multiple Run
END DESCRIPTION:

--- Lynn Creek T 18.f01 (steady flow) ---

Flow Title=Multiple
Number of Profiles=7
Profile Names=10-year,25-year,50-year,1pct_min,100-year,1pct_plu,500-year
River Rch & RM= Lynn Creek T 18,Reach-1,1953
     153     187     211     119     237     473     299
Boundary for River Rch & Prof#=Lynn Creek T 18,Reach-1,1
Up Type=0
Dn Type=3
Dn Slope=0.005
Boundary for River Rch & Prof#=Lynn Creek T 18,Reach-1,2
Up Type=0
Dn Type=3
Dn Slope=0.005
Boundary for River Rch & Prof#=Lynn Creek T 18,Reach-1,3
Up Type=0
Dn Type=3
Dn Slope=0.005
Boundary for River Rch & Prof#=Lynn Creek T 18,Reach-1,4
Up Type=0
Dn Type=3
Dn Slope=0.005
Boundary for River Rch & Prof#=Lynn Creek T 18,Reach-1,5
Up Type=0
Dn Type=3
Dn Slope=0.005
Boundary for River Rch & Prof#=Lynn Creek T 18,Reach-1,6
Up Type=0
Dn Type=3
Dn Slope=0.005
Boundary for River Rch & Prof#=Lynn Creek T 18,Reach-1,7
Up Type=0
Dn Type=3
Dn Slope=0.005

--- Lynn Creek T 18.g01 (geometry) ---

Geom Title=Existing Conditions

River Reach=Lynn Creek T 18,Reach-1
Reach XY= 30
      2720826.00      6788011.00      2720824.24      6787916.53
      2720812.84      6787897.21      2720786.16      6787871.34
      2720765.68      6787862.09      2720691.10      6787860.51
      2720669.57      6787853.21      2720634.17      6787817.03
      2720624.00      6787772.74      2720614.16      6787762.66
      2720481.94      6787758.75      2720428.15      6787717.15
      2720373.47      6787705.23      2720334.19      6787666.98
      2720324.00      6787622.73      2720314.16      6787612.63
      2720181.95      6787613.25      2720124.43      6787657.21
      2719986.44      6787662.40      2719969.82      6787669.46
      2719926.00      6787703.44      2719870.14      6787663.47
      2719745.99      6787661.02      2719723.55      6787655.53
      2719442.65      6787377.67      2719429.97      6787359.35
      2719417.86      6787304.93      2719352.87      6787237.32
      2719324.66      6787214.27      2719276.00      6787211.00

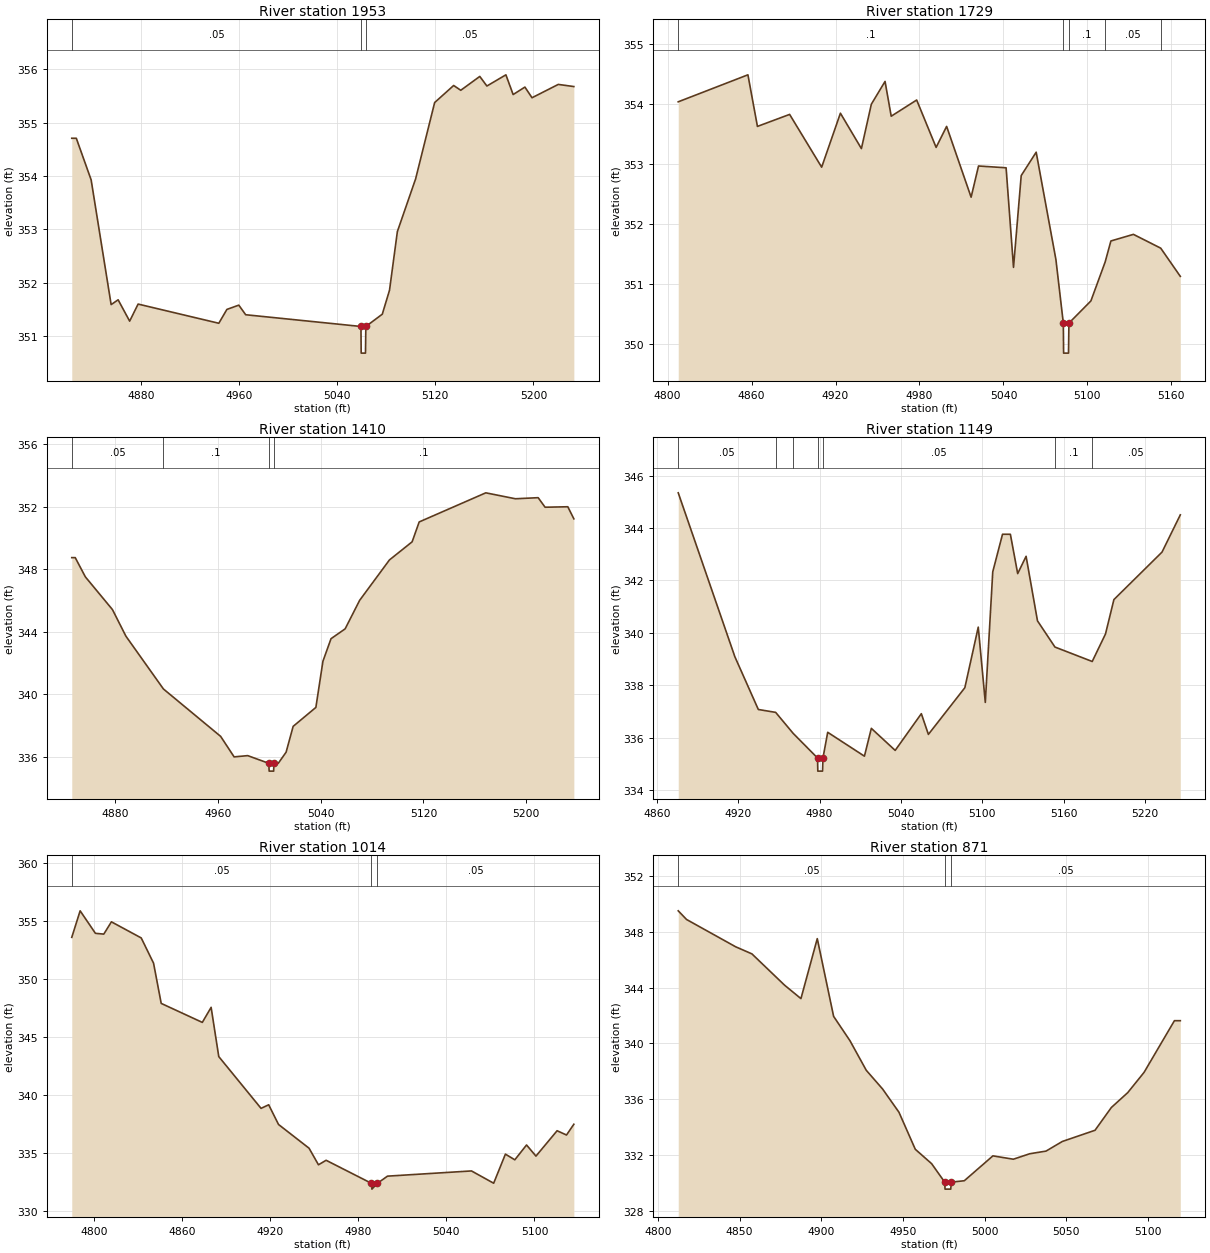
Type RM Length L Ch R = 1,1953,224,224,224
BEGIN DESCRIPTION:
Lynn Creek T 18 6.0
END DESCRIPTION:
XS GIS Cut Line= 3
      2720907.07      6787759.41      2720826.00      6787911.00
      2720702.56      6788113.89
#Sta/Elev= 30
  4823.6  354.71  4827.3  354.71  4839.4  353.93  4855.7  351.59  4861.4  351.68
  4870.8  351.28  4877.7  351.60  4943.5  351.24  4950.1  351.50  4959.8  351.58
  4965.4  351.40  5059.4  351.18  5059.6  350.68  5063.1  350.68  5063.4  351.18
  5076.8  351.41  5082.7  351.86  5089.1  352.96  5104.0  353.95  5119.5  355.38
  5135.0  355.70  5140.8  355.61  5156.3  355.87  5162.1  355.69  5177.6  355.90
  5183.5  355.53  5193.1  355.67  5198.9  355.47  5220.3  355.72  5233.0  355.68
#Mann=3,-1,0
  4823.6    0.05       0  5059.4    0.03       0  5063.4    0.05       0
Bank Sta=5059.4,5063.4
Exp/Cntr=0.3,0.1

Type RM Length L Ch R = 1,1729,319,319,319
BEGIN DESCRIPTION:
Lynn Creek T 18 5.0
END DESCRIPTION:
XS GIS Cut Line= 3
      2720715.32      6787645.76      2720651.43      6787783.90
      2720579.32      6787977.51
#Sta/Elev= 30
  4807.6  354.04  4857.4  354.49  4864.2  353.63  4887.2  353.83  4910.1  352.95
  4923.5  353.85  4938.5  353.26  4945.6  354.00  4955.4  354.38  4959.8  353.80
  4978.0  354.07  4991.9  353.28  4999.4  353.63  5016.9  352.45  5022.2  352.97
  5041.9  352.94  5047.2  351.28  5052.7  352.81  5063.4  353.20  5077.5  351.41
  5082.8  350.35  5083.0  349.85  5086.5  349.85  5086.8  350.35  5102.5  350.72
  5112.7  351.37  5116.8  351.72  5132.9  351.83  5152.4  351.60  5166.4  351.13
#Mann=5,-1,0
  4807.6     0.1       0  5082.8    0.07       0  5086.8     0.1       0
  5112.7    0.05       0  5152.4     0.1       0
Bank Sta=5082.8,5086.8
Exp/Cntr=0.3,0.1

Type RM Length L Ch R = 1,1410,261,261,261
BEGIN DESCRIPTION:
Lynn Creek T 18 4.0
END DESCRIPTION:
XS GIS Cut Line= 3
      2720426.01      6787560.96      2720376.00      6787711.00
      2720280.60      6787923.62
#Sta/Elev= 30
  4846.0  348.74  4848.7  348.74  4856.6  347.51  4877.7  345.42  4888.2  343.72
  4917.4  340.35  4962.0  337.32  4972.5  336.01  4983.1  336.09  4999.5  335.60
  4999.8  335.10  5003.3  335.10  5003.5  335.60  5006.9  335.60  5013.0  336.31
  5018.5  337.96  5036.2  339.17  5041.7  342.12  5048.0  343.56  5059.0  344.19
  5070.3  346.01  5093.5  348.59  5111.2  349.75  5116.7  351.02  5168.6  352.88
  5191.7  352.50  5209.4  352.57  5214.8  351.96  5232.5  351.99  5237.2  351.22
#Mann=4,-1,0
  4846.0    0.05       0  4917.4     0.1       0  4999.5    0.07       0
  5003.5     0.1       0
Bank Sta=4999.5,5003.5
Exp/Cntr=0.3,0.1

Type RM Length L Ch R = 1,1149,135,135,135
BEGIN DESCRIPTION:
Lynn Creek T 18 3.0
END DESCRIPTION:
XS GIS Cut Line= 4
      2720226.42      6787503.25      2720176.00      6787611.00
      2720147.47      6787729.99      2720070.81      6787833.96
#Sta/Elev= 30
  4875.7  345.34  4917.5  339.09  4934.8  337.08  4947.6  336.97  4960.5  336.17
  4978.5  335.23  4978.7  334.73  4982.2  334.73  4982.5  335.23  4986.0  336.21
  5013.1  335.30  5018.2  336.36  5035.8  335.52  5055.1  336.92  5060.3  336.13
  5087.2  337.91  5097.1  340.22  5102.3  337.35  5107.8  342.33  5115.0  343.76
  5120.8  343.76  5126.2  342.26  5132.4  342.92  5140.8  340.46  5153.7  339.46
  5181.2  338.91  5191.0  339.96  5197.2  341.27  5232.7  343.08  5246.2  344.50
#Mann=7,-1,0
  4875.7    0.05       0  4947.6     0.1       0  4960.5    0.05       0
  4978.5    0.03       0  4982.5    0.05       0  5153.7     0.1       0
  5181.2    0.05       0
Bank Sta=4978.5,4982.5
Exp/Cntr=0.3,0.1

Type RM Length L Ch R = 1,1014,143,143,143
BEGIN DESCRIPTION:
Mapping XS e3bdf5ea
END DESCRIPTION:
XS GIS Cut Line= 4
      2720117.04      6787455.48      2720062.95      6787646.86
      2720024.56      6787716.32      2719984.90      6787766.12
#Sta/Elev= 30
  4784.9  353.59  4790.6  355.88  4801.0  353.94  4806.7  353.87  4811.9  354.93
  4832.2  353.54  4840.6  351.36  4845.8  347.89  4873.8  346.25  4879.8  347.55
  4885.0  343.30  4913.8  338.83  4919.0  339.14  4925.7  337.44  4946.5  335.39
  4952.9  333.96  4958.1  334.35  4989.0  332.36  4989.3  331.86  4993.0  332.36
  4999.9  332.98  5057.1  333.43  5072.2  332.37  5080.2  334.88  5086.6  334.39
  5094.6  335.67  5101.0  334.71  5115.4  336.90  5121.8  336.53  5126.8  337.46
#Mann=3,-1,0
  4784.9    0.05       0  4989.0    0.03       0  4993.0    0.05       0
Bank Sta=4989,4993
Exp/Cntr=0.3,0.1

Type RM Length L Ch R = 1,871,282,282,282
BEGIN DESCRIPTION:
Lynn Creek T 18 2.0
END DESCRIPTION:
XS GIS Cut Line= 3
      2719929.80      6787515.95      2719926.00      6787711.00
      2719927.36      6787823.21
#Sta/Elev= 30
  4812.5  349.49  4817.6  348.87  4847.6  346.92  4857.6  346.41  4877.6  344.17
  4887.6  343.21  4897.6  347.50  4907.6  341.94  4917.6  340.20  4927.6  338.08
  4937.6  336.74  4947.6  335.08  4957.6  332.43  4967.6  331.40  4975.6  330.08
  4975.8  329.58  4979.3  329.58  4979.6  330.08  4987.6  330.18  5005.1  331.96
  5017.6  331.72  5027.6  332.11  5037.6  332.30  5047.6  332.99  5067.6  333.79
  5077.6  335.42  5087.6  336.48  5097.6  337.93  5116.2  341.63  5119.8  341.63
#Mann=3,-1,0
  4812.5    0.05       0  4975.6    0.03       0  4979.6    0.05       0
Bank Sta=4975.6,4979.6
Exp/Cntr=0.3,0.1

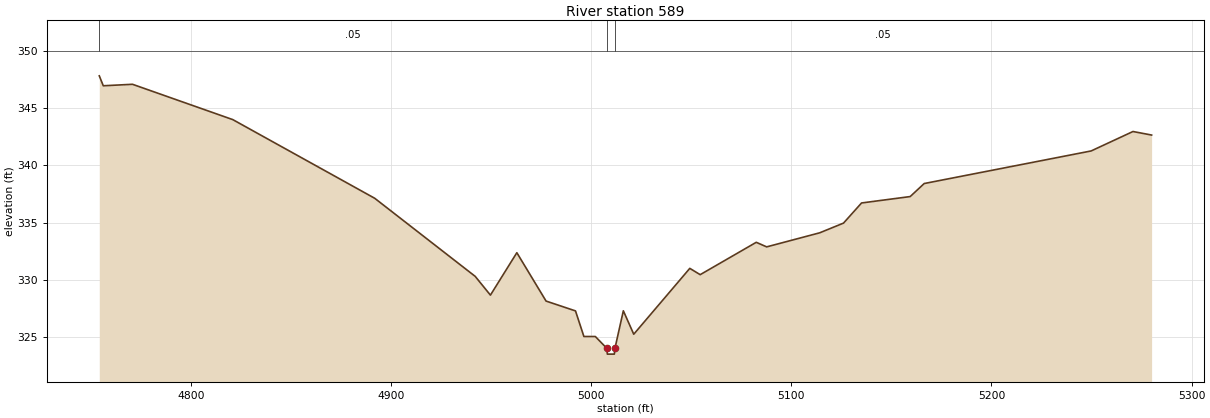
Type RM Length L Ch R = 1,589,0,0,0
BEGIN DESCRIPTION:
Lynn Creek T 18 1.0
END DESCRIPTION:
XS GIS Cut Line= 3
      2719821.78      6787413.89      2719676.00      6787611.00
      2719755.84      6787879.93
#Sta/Elev= 30
  4754.3  347.84  4756.3  346.97  4770.9  347.10  4821.0  344.01  4891.9  337.13
  4942.1  330.30  4949.7  328.66  4962.9  332.37  4977.5  328.14  4992.2  327.28
  4996.4  325.04  5002.1  325.04  5007.9  324.00  5008.1  323.50  5011.6  323.50
  5011.9  324.00  5016.1  327.29  5021.3  325.24  5049.3  331.00  5054.5  330.45
  5082.5  333.28  5087.7  332.88  5114.2  334.11  5126.1  334.96  5135.1  336.72
  5159.4  337.28  5166.4  338.42  5249.8  341.27  5270.7  342.97  5280.0  342.66
#Mann=3,-1,0
  4754.3    0.05       0  5007.9    0.03       0  5011.9    0.05       0
Bank Sta=5007.9,5011.9
Exp/Cntr=0.3,0.1

Chan Stop Cuts=-1