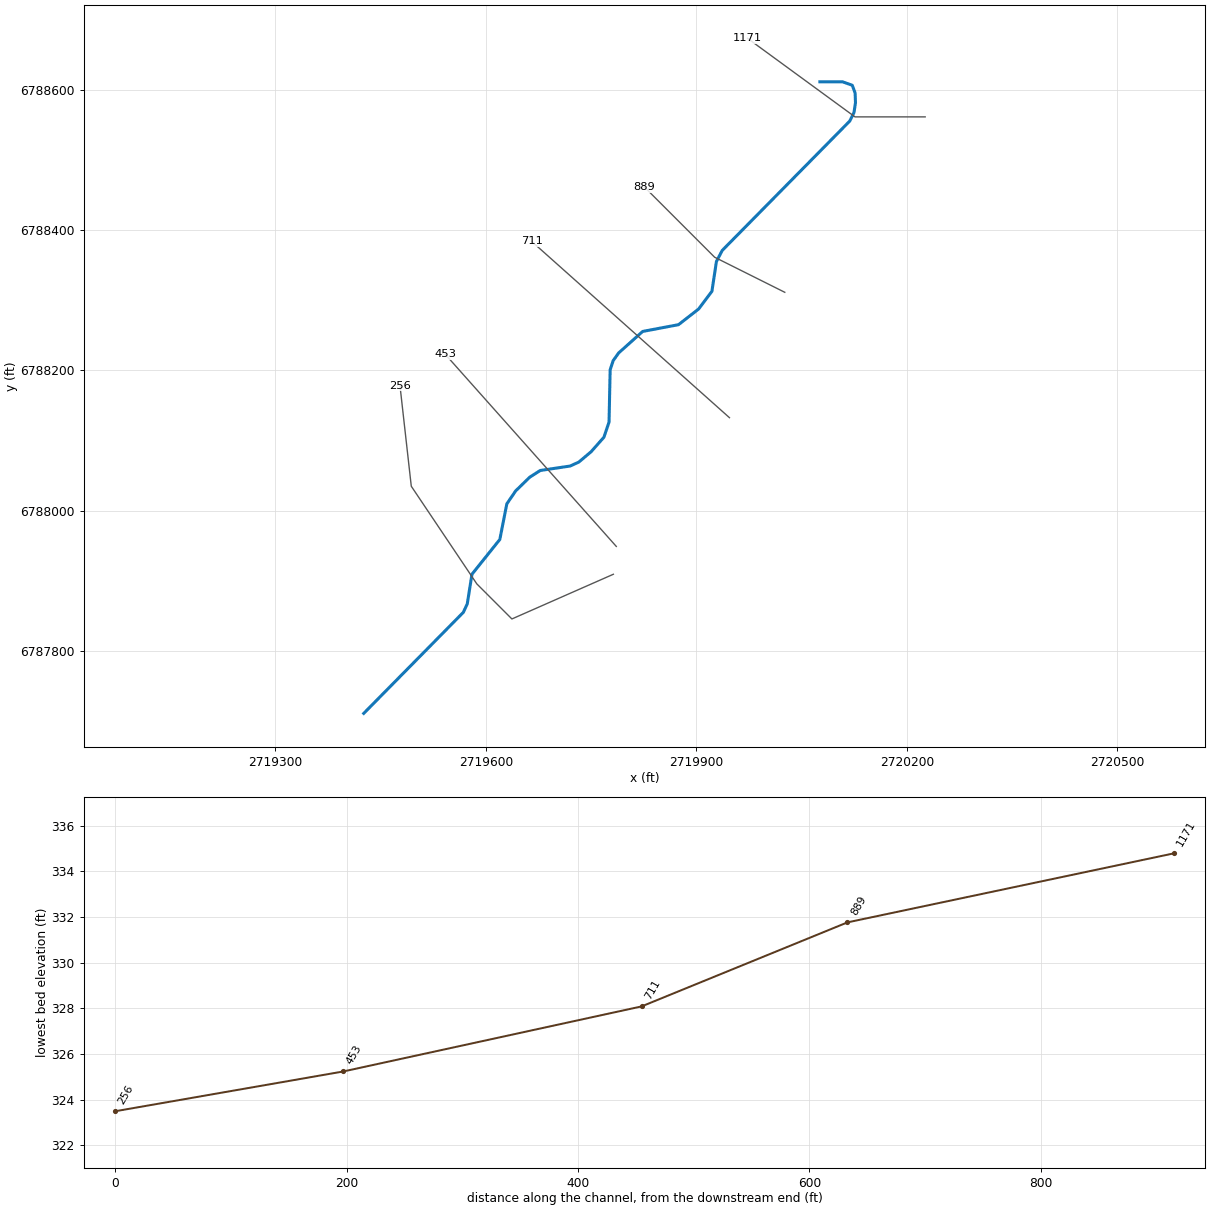
--- Lynn Creek T 19.prj (project) ---

Proj Title=Lynn Creek T 19 Base Level Engineering
Current Plan=p01
Default Exp/Contr=0.3,0.1
English Units
Geom File=g01
Flow File=f01
Plan File=p01
BEGIN DESCRIPTION:
Lynn Creek T 19
END DESCRIPTION:

--- Lynn Creek T 19.p01 (plan) ---

Plan Title=Multiple Run
Short Identifier=Multiple
Geom File=g01
Flow File=f01
Subcritical Flow
K Sum by GR= 0
Std Step Tol= 0.01
Critical Tol= 0.01
Num of Std Step Trials= 20
Max Error Tol= 0.3
Flow Tol Ratio= 0.001
Split Flow NTrial= 30
Split Flow Tol= 0.02
Split Flow Ratio= 0.02
Log Output Level= 0
Friction Slope Method= 1
Unsteady Friction Slope Method= 2
Unsteady Bridges Friction Slope Method= 1
Parabolic Critical Depth
Global Vel Dist=  1 , 1 , 1
Global Log Level= 0
CheckData=True
Encroach Param= -1, 0, 0, 0
BEGIN DESCRIPTION:
Multiple Run
END DESCRIPTION:

--- Lynn Creek T 19.f01 (steady flow) ---

Flow Title=Multiple
Number of Profiles=7
Profile Names=10-year,25-year,50-year,1pct_min,100-year,1pct_plu,500-year
River Rch & RM= Lynn Creek T 19,Reach-1,1171
     138     167     188     106     211     421     265
Boundary for River Rch & Prof#=Lynn Creek T 19,Reach-1,1
Up Type=0
Dn Type=3
Dn Slope=0.005
Boundary for River Rch & Prof#=Lynn Creek T 19,Reach-1,2
Up Type=0
Dn Type=3
Dn Slope=0.005
Boundary for River Rch & Prof#=Lynn Creek T 19,Reach-1,3
Up Type=0
Dn Type=3
Dn Slope=0.005
Boundary for River Rch & Prof#=Lynn Creek T 19,Reach-1,4
Up Type=0
Dn Type=3
Dn Slope=0.005
Boundary for River Rch & Prof#=Lynn Creek T 19,Reach-1,5
Up Type=0
Dn Type=3
Dn Slope=0.005
Boundary for River Rch & Prof#=Lynn Creek T 19,Reach-1,6
Up Type=0
Dn Type=3
Dn Slope=0.005
Boundary for River Rch & Prof#=Lynn Creek T 19,Reach-1,7
Up Type=0
Dn Type=3
Dn Slope=0.005

--- Lynn Creek T 19.g01 (geometry) ---

Geom Title=Existing Conditions

River Reach=Lynn Creek T 19,Reach-1
Reach XY= 30
      2720076.00      6788611.00      2720108.37      6788610.93
      2720122.07      6788606.08      2720126.18      6788595.06
      2720126.69      6788581.22      2720124.58      6788567.21
      2720118.59      6788555.10      2719936.79      6788370.66
      2719928.55      6788354.91      2719922.11      6788312.43
      2719903.13      6788287.17      2719874.54      6788264.90
      2719823.45      6788255.25      2719789.26      6788224.65
      2719781.42      6788213.67      2719777.11      6788200.66
      2719775.52      6788126.10      2719768.25      6788104.55
      2719749.95      6788083.82      2719732.36      6788069.03
      2719720.12      6788063.47      2719677.46      6788057.10
      2719662.45      6788047.51      2719642.49      6788028.05
      2719629.86      6788009.58      2719619.89      6787958.84
      2719580.19      6787909.27      2719573.50      6787867.03
      2719567.86      6787854.94      2719426.00      6787711.00

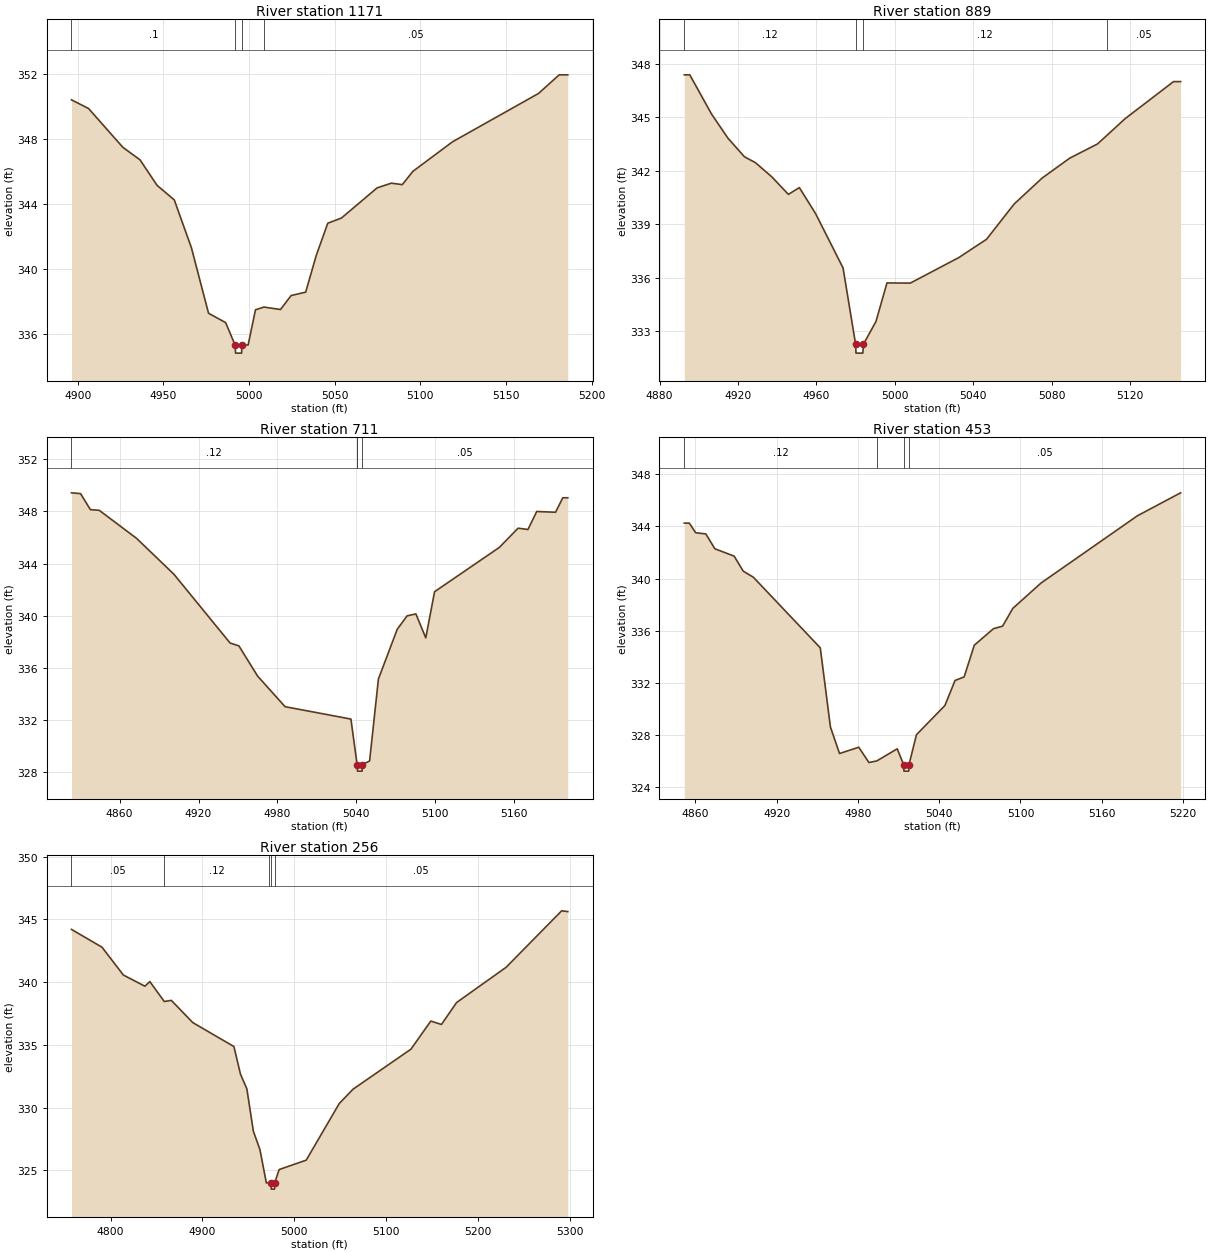
Type RM Length L Ch R = 1,1171,282,282,282
BEGIN DESCRIPTION:
Lynn Creek T 19 3.0
END DESCRIPTION:
XS GIS Cut Line= 3
      2720226.04      6788561.00      2720126.00      6788561.00
      2719972.88      6788672.92
#Sta/Elev= 30
  4896.4  350.41  4906.4  349.87  4926.4  347.48  4936.4  346.71  4946.4  345.13
  4956.4  344.24  4966.4  341.29  4976.4  337.25  4986.4  336.67  4991.9  335.29
  4992.2  334.79  4995.7  334.79  4995.9  335.29  4999.5  335.29  5003.8  337.46
  5008.7  337.63  5018.4  337.48  5024.6  338.34  5033.1  338.55  5039.3  340.82
  5046.0  342.80  5054.0  343.12  5074.8  344.98  5083.1  345.27  5089.5  345.18
  5095.7  346.00  5118.8  347.82  5169.0  350.80  5181.1  351.95  5186.1  351.95
#Mann=4,-1,0
  4896.4     0.1       0  4991.9    0.07       0  4995.9     0.1       0
  5008.7    0.05       0
Bank Sta=4991.9,4995.9
Exp/Cntr=0.3,0.1

Type RM Length L Ch R = 1,889,178,178,178
BEGIN DESCRIPTION:
Lynn Creek T 19 2.0
END DESCRIPTION:
XS GIS Cut Line= 3
      2720025.96      6788311.02      2719926.00      6788361.00
      2719825.99      6788461.01
#Sta/Elev= 28
  4892.6  347.39  4895.4  347.39  4906.5  345.19  4914.9  343.83  4923.3  342.79
  4928.9  342.46  4937.3  341.66  4945.7  340.68  4951.3  341.06  4959.6  339.60
  4973.6  336.55  4980.0  332.27  4980.2  331.77  4983.7  331.77  4984.0  332.27
  4990.4  333.55  4996.0  335.71  5007.9  335.70  5032.6  337.13  5046.8  338.16
  5060.9  340.14  5075.1  341.59  5089.2  342.71  5103.4  343.51  5108.2  343.99
  5117.5  344.93  5142.2  347.01  5145.8  347.01
#Mann=4,-1,0
  4892.6    0.12       0  4980.0    0.07       0  4984.0    0.12       0
  5108.2    0.05       0
Bank Sta=4980,4984
Exp/Cntr=0.3,0.1

Type RM Length L Ch R = 1,711,258,258,258
BEGIN DESCRIPTION:
Mapping XS 28c5adcd
END DESCRIPTION:
XS GIS Cut Line= 2
      2719947.13      6788132.34      2719665.40      6788383.45
#Sta/Elev= 30
  4823.4  349.42  4830.3  349.36  4837.8  348.13  4844.5  348.08  4872.9  345.93
  4901.3  343.18  4944.0  337.91  4950.7  337.69  4964.9  335.38  4985.8  333.03
  5035.9  332.08  5040.5  328.66  5040.6  328.59  5040.9  328.09  5044.4  328.09
  5044.6  328.59  5050.1  328.87  5056.8  335.15  5071.1  338.96  5078.6  339.99
  5085.3  340.14  5092.8  338.30  5099.5  341.84  5148.8  345.24  5163.0  346.71
  5170.5  346.61  5177.2  347.99  5191.5  347.93  5197.0  349.04  5200.8  349.04
#Mann=4,-1,0
  4823.4    0.12       0  5040.5    0.05       0  5040.6    0.07       0
  5044.6    0.05       0
Bank Sta=5040.6,5044.6
Exp/Cntr=0.3,0.1

Type RM Length L Ch R = 1,453,197,197,197
BEGIN DESCRIPTION:
Mapping XS 07a550bd
END DESCRIPTION:
XS GIS Cut Line= 2
      2719785.86      6787948.91      2719542.22      6788222.57
#Sta/Elev= 30
  4851.8  344.25  4855.5  344.25  4860.2  343.51  4867.7  343.42  4874.4  342.28
  4888.6  341.72  4895.3  340.57  4902.8  340.10  4952.2  334.69  4959.7  328.62
  4966.4  326.59  4980.6  327.07  4988.1  325.90  4993.9  326.02  5009.0  326.95
  5013.7  325.74  5014.0  325.24  5017.5  325.24  5017.7  325.74  5023.2  328.03
  5044.2  330.27  5051.7  332.19  5058.4  332.46  5065.9  334.89  5080.1  336.16
  5086.8  336.35  5094.3  337.71  5115.2  339.66  5186.3  344.81  5218.2  346.57
#Mann=4,-1,0
  4851.8    0.12       0  4993.9    0.05       0  5013.7    0.05       0
  5017.7    0.05       0
Bank Sta=5013.7,5017.7
Exp/Cntr=0.3,0.1

Type RM Length L Ch R = 1,256,0,0,0
BEGIN DESCRIPTION:
Lynn Creek T 19 1.0
END DESCRIPTION:
XS GIS Cut Line= 5
      2719781.70      6787909.25      2719637.10      6787845.55
      2719587.10      6787895.55      2719493.72      6788034.66
      2719477.64      6788177.69
#Sta/Elev= 30
  4757.5  344.21  4790.7  342.79  4814.0  340.57  4837.4  339.68  4842.8  340.05
  4858.5  338.46  4866.2  338.55  4889.5  336.78  4934.3  334.87  4941.4  332.68
  4948.4  331.49  4955.5  328.11  4962.6  326.66  4969.6  324.00  4973.0  324.00
  4974.7  324.00  4975.0  323.50  4978.5  323.50  4978.7  324.00  4983.5  325.06
  5013.0  325.81  5049.0  330.33  5064.0  331.47  5127.0  334.66  5148.6  336.90
  5160.2  336.63  5176.7  338.38  5230.6  341.19  5291.0  345.69  5297.7  345.63
#Mann=5,-1,0
  4757.5    0.05       0  4858.5    0.12       0  4973.0    0.05       0
  4974.7    0.05       0  4978.7    0.05       0
Bank Sta=4974.7,4978.7
Exp/Cntr=0.3,0.1

Chan Stop Cuts=-1