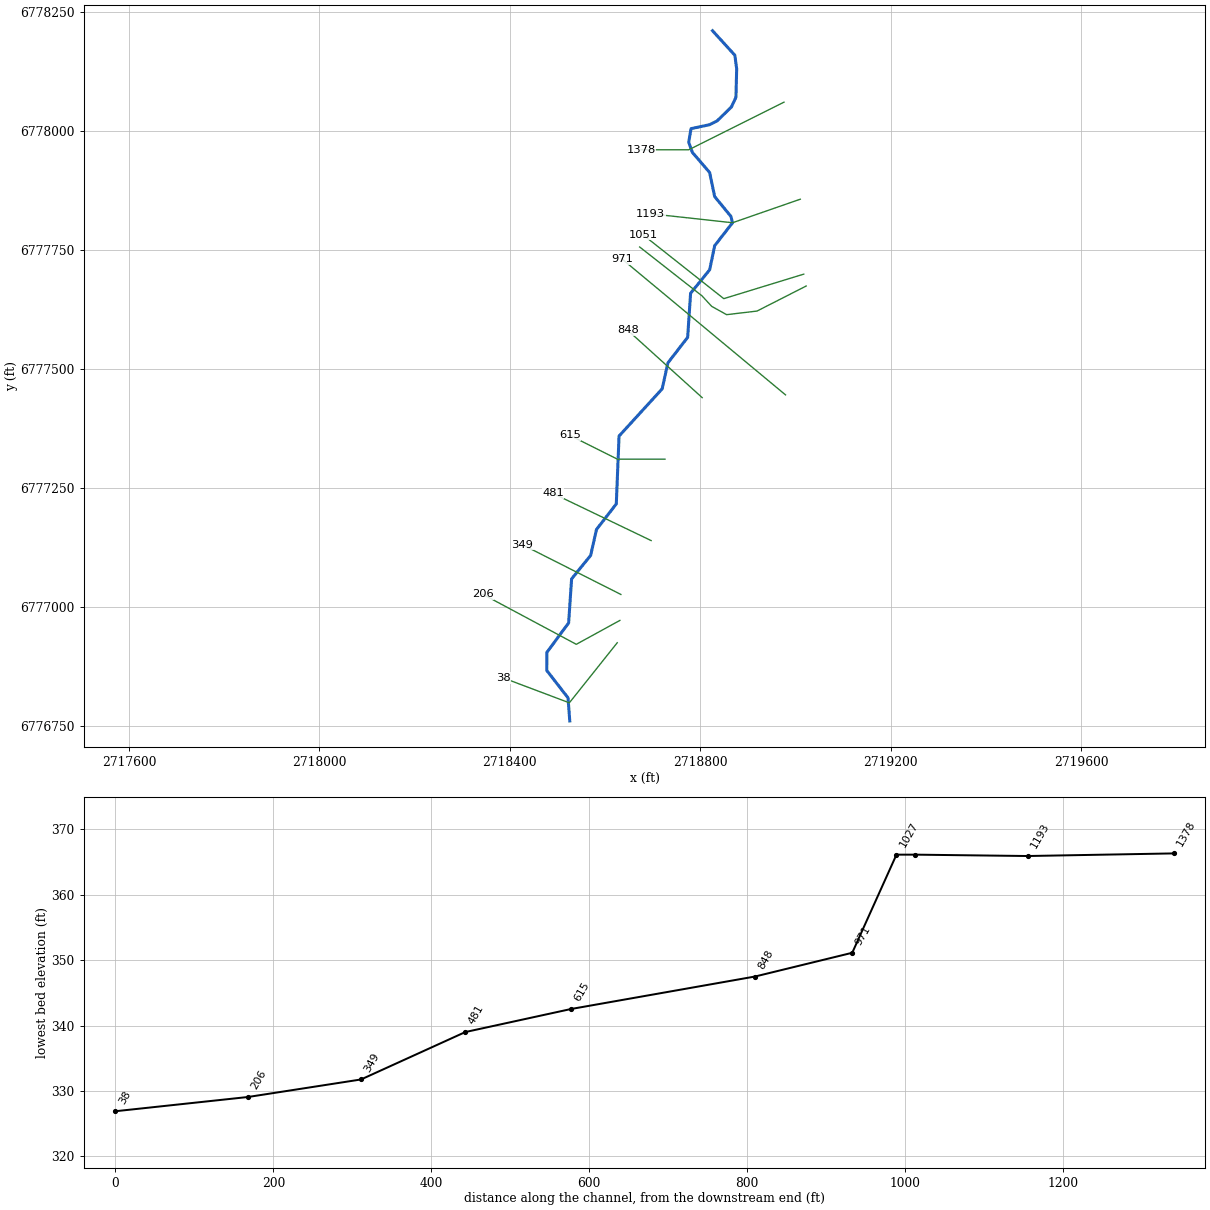
--- Lynn Creek T2.prj (project) ---

Proj Title=Lynn Creek T2 Base Level Engineering
Current Plan=p01
Default Exp/Contr=0.3,0.1
English Units
Geom File=g01
Flow File=f01
Plan File=p01
BEGIN DESCRIPTION:
Lynn Creek T2
END DESCRIPTION:

--- Lynn Creek T2.p01 (plan) ---

Plan Title=Multiple Run
Short Identifier=Multiple
Geom File=g01
Flow File=f01
Subcritical Flow
K Sum by GR= 0
Std Step Tol= 0.01
Critical Tol= 0.01
Num of Std Step Trials= 20
Max Error Tol= 0.3
Flow Tol Ratio= 0.001
Split Flow NTrial= 30
Split Flow Tol= 0.02
Split Flow Ratio= 0.02
Log Output Level= 0
Friction Slope Method= 1
Unsteady Friction Slope Method= 2
Unsteady Bridges Friction Slope Method= 1
Parabolic Critical Depth
Global Vel Dist=  1 , 1 , 1
Global Log Level= 0
CheckData=True
Encroach Param= -1, 0, 0, 0
BEGIN DESCRIPTION:
Multiple Run
END DESCRIPTION:

--- Lynn Creek T2.f01 (steady flow) ---

Flow Title=Multiple
Number of Profiles=7
Profile Names=10-year,25-year,50-year,1pct_min,100-year,1pct_plu,500-year
River Rch & RM= Lynn Creek T2,Reach-1,1378
      81      95     105      58     116     231     140
Boundary for River Rch & Prof#=Lynn Creek T2,Reach-1,1
Up Type=0
Dn Type=3
Dn Slope=0.005
Boundary for River Rch & Prof#=Lynn Creek T2,Reach-1,2
Up Type=0
Dn Type=3
Dn Slope=0.005
Boundary for River Rch & Prof#=Lynn Creek T2,Reach-1,3
Up Type=0
Dn Type=3
Dn Slope=0.005
Boundary for River Rch & Prof#=Lynn Creek T2,Reach-1,4
Up Type=0
Dn Type=3
Dn Slope=0.005
Boundary for River Rch & Prof#=Lynn Creek T2,Reach-1,5
Up Type=0
Dn Type=3
Dn Slope=0.005
Boundary for River Rch & Prof#=Lynn Creek T2,Reach-1,6
Up Type=0
Dn Type=3
Dn Slope=0.005
Boundary for River Rch & Prof#=Lynn Creek T2,Reach-1,7
Up Type=0
Dn Type=3
Dn Slope=0.005

--- Lynn Creek T2.g01 (geometry) ---

Geom Title=Existing Conditions

River Reach=Lynn Creek T2,Reach-1
Reach XY= 30
      2718826.00      6778211.00      2718872.82      6778159.59
      2718876.66      6778131.01      2718875.12      6778071.32
      2718865.64      6778050.91      2718835.71      6778021.73
      2718819.58      6778013.61      2718780.80      6778005.38
      2718775.88      6777976.76      2718783.63      6777955.37
      2718819.85      6777913.22      2718830.42      6777862.64
      2718864.60      6777820.92      2718867.98      6777807.69
      2718830.42      6777759.36      2718819.91      6777708.83
      2718779.83      6777659.42      2718773.67      6777566.97
      2718732.14      6777513.17      2718720.15      6777458.71
      2718629.55      6777359.53      2718623.75      6777216.93
      2718582.12      6777163.18      2718569.89      6777108.82
      2718529.83      6777059.42      2718523.62      6776966.97
      2718477.80      6776904.89      2718477.64      6776867.08
      2718522.31      6776809.51      2718526.00      6776761.00

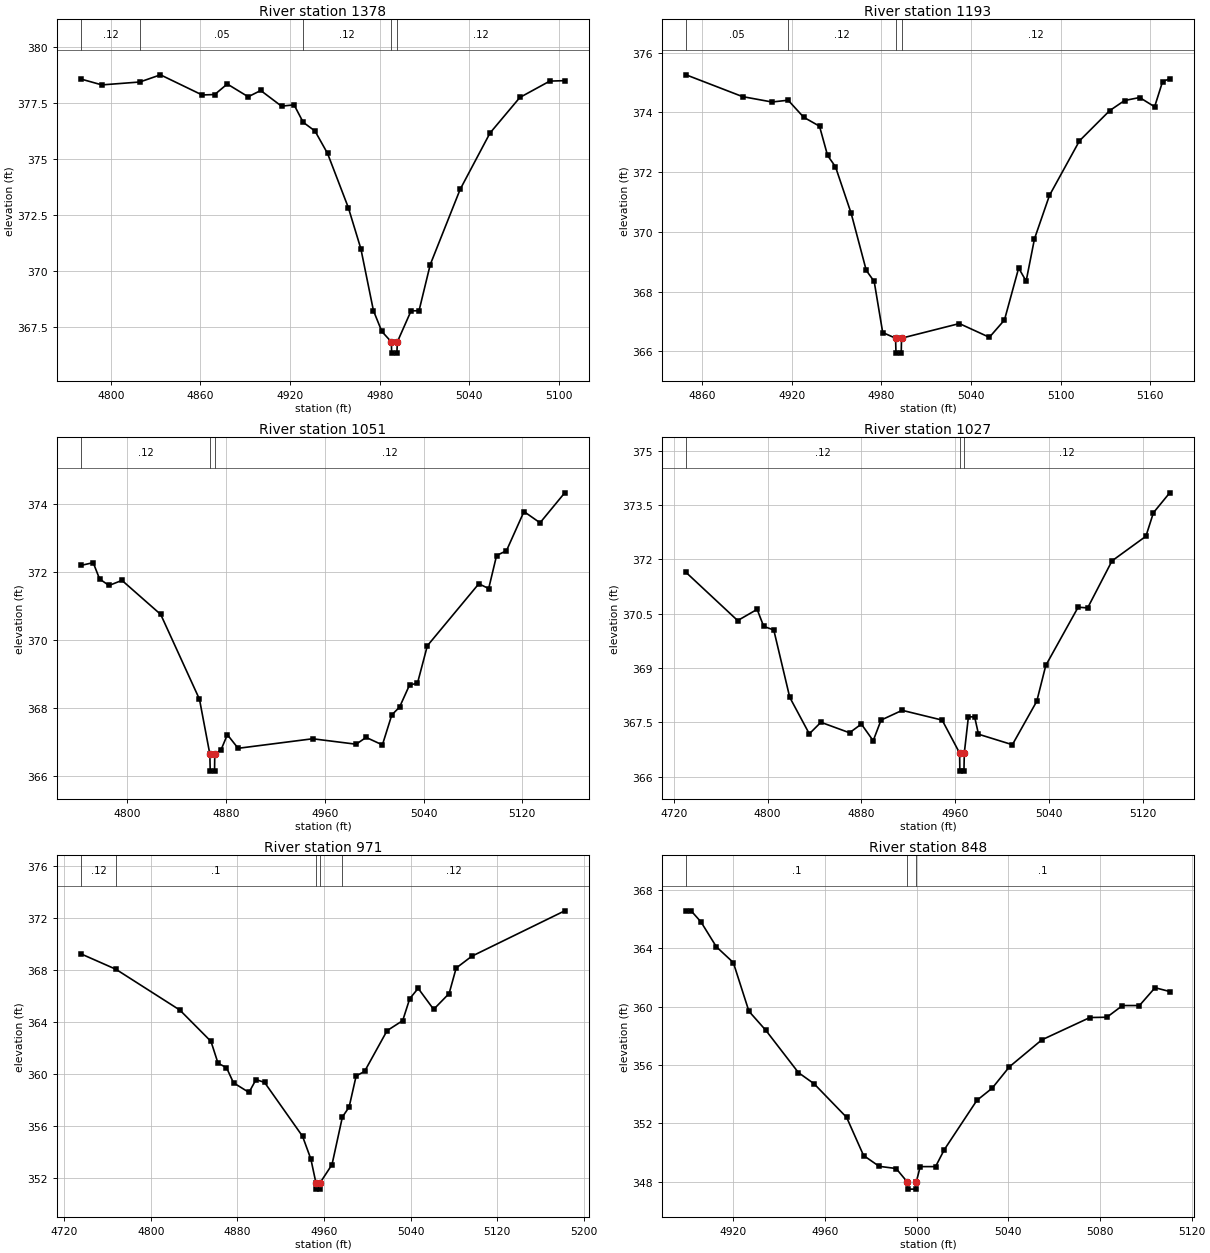
Type RM Length L Ch R = 1,1378,185,185,185
BEGIN DESCRIPTION:
Lynn Creek T2 5.0
END DESCRIPTION:
XS GIS Cut Line= 3
      2718975.97      6778060.98      2718776.00      6777961.00
      2718675.97      6777961.00
#Sta/Elev= 30
  4780.2  378.58  4794.1  378.32  4819.5  378.45  4833.3  378.77  4861.2  377.87
  4869.6  377.89  4878.0  378.36  4892.0  377.79  4900.4  378.07  4914.3  377.37
  4922.7  377.43  4928.8  376.65  4936.7  376.26  4945.1  375.26  4959.0  372.84
  4967.4  371.00  4975.8  368.24  4981.4  367.31  4987.8  366.84  4988.0  366.34
  4991.5  366.34  4991.8  366.84  5001.0  368.23  5006.3  368.23  5013.8  370.29
  5033.8  373.65  5053.8  376.17  5073.8  377.76  5093.8  378.49  5103.8  378.51
#Mann=5,-1,0
  4780.2    0.12       0  4819.5    0.05       0  4928.8    0.12       0
  4987.8    0.07       0  4991.8    0.12       0
Bank Sta=4987.8,4991.8
Exp/Cntr=0.3,0.1

Type RM Length L Ch R = 1,1193,142,142,142
BEGIN DESCRIPTION:
Lynn Creek T2 4.0
END DESCRIPTION:
XS GIS Cut Line= 3
      2719010.34      6777857.14      2718867.98      6777807.69
      2718696.01      6777826.49
#Sta/Elev= 30
  4849.3  375.26  4887.1  374.53  4906.8  374.35  4917.6  374.41  4928.0  373.84
  4938.6  373.54  4944.0  372.56  4949.3  372.18  4959.8  370.62  4969.9  368.71
  4975.2  368.34  4980.9  366.63  4989.5  366.44  4989.8  365.94  4993.3  365.94
  4993.5  366.44  5032.2  366.93  5052.3  366.47  5062.4  367.05  5071.9  368.79
  5076.9  368.35  5082.5  369.77  5092.5  371.22  5112.6  373.05  5132.8  374.06
  5142.8  374.40  5152.9  374.50  5162.9  374.19  5168.2  375.03  5173.0  375.13
#Mann=4,-1,0
  4849.3    0.05       0  4917.6    0.12       0  4989.5    0.07       0
  4993.5    0.12       0
Bank Sta=4989.5,4993.5
Exp/Cntr=0.3,0.1

Type RM Length L Ch R = 1,1051,24,24,24
BEGIN DESCRIPTION:
Mapping XS 86d67849
END DESCRIPTION:
XS GIS Cut Line= 3
      2719017.65      6777699.71      2718849.55      6777648.20
      2718680.15      6777782.19
#Sta/Elev= 30
  4762.6  372.19  4772.4  372.27  4777.6  371.79  4785.2  371.60  4795.7  371.75
  4827.1  370.75  4858.5  368.26  4866.9  366.65  4867.2  366.15  4870.7  366.15
  4870.9  366.65  4875.9  366.77  4881.1  367.22  4889.8  366.82  4950.2  367.10
  4985.4  366.94  4993.5  367.14  5006.7  366.92  5014.3  367.80  5020.6  368.03
  5028.7  368.68  5035.1  368.73  5043.1  369.83  5084.8  371.65  5092.8  371.51
  5099.2  372.48  5107.2  372.62  5121.4  373.77  5134.4  373.44  5154.4  374.32
#Mann=3,-1,0
  4762.6    0.12       0  4866.9    0.07       0  4870.9    0.12       0
Bank Sta=4866.9,4870.9
Exp/Cntr=0.3,0.1

Type RM Length L Ch R = 1,1027,56,56,56
BEGIN DESCRIPTION:
Mapping XS e9d006e7
END DESCRIPTION:
XS GIS Cut Line= 6
      2719022.62      6777674.71      2718919.33      6777622.10
      2718855.48      6777614.56      2718824.16      6777632.02
      2718803.78      6777654.07      2718672.84      6777756.76
#Sta/Elev= 30
  4730.4  371.64  4774.4  370.31  4791.0  370.62  4796.6  370.15  4805.2  370.05
  4818.8  368.19  4835.5  367.18  4845.4  367.50  4869.8  367.21  4879.9  367.45
  4890.0  366.99  4896.7  367.56  4914.7  367.83  4948.8  367.56  4963.7  366.65
  4963.9  366.15  4967.4  366.15  4967.7  366.65  4971.2  367.65  4976.5  367.65
  4979.8  367.17  5008.7  366.88  5029.5  368.08  5037.2  369.07  5064.8  370.68
  5072.9  370.66  5093.7  371.96  5122.6  372.64  5129.0  373.29  5142.9  373.84
#Mann=3,-1,0
  4730.4    0.12       0  4963.7    0.07       0  4967.7    0.12       0
Bank Sta=4963.7,4967.7
Exp/Cntr=0.3,0.1

Type RM Length L Ch R = 1,971,123,123,123
BEGIN DESCRIPTION:
Mapping XS 5dfcead9
END DESCRIPTION:
XS GIS Cut Line= 2
      2718979.31      6777446.00      2718635.68      6777731.57
#Sta/Elev= 30
  4735.6  369.26  4767.7  368.08  4826.9  364.93  4855.6  362.52  4862.1  360.84
  4869.9  360.50  4876.4  359.33  4890.7  358.59  4897.2  359.58  4905.1  359.36
  4940.2  355.21  4947.9  353.45  4952.5  351.64  4952.8  351.14  4956.3  351.14
  4956.5  351.64  4967.4  353.03  4977.0  356.70  4983.2  357.46  4989.7  359.86
  4997.5  360.21  5018.3  363.35  5032.7  364.12  5039.2  365.81  5047.0  366.61
  5061.3  364.99  5075.6  366.21  5082.1  368.17  5096.5  369.08  5182.4  372.58
#Mann=5,-1,0
  4735.6    0.12       0  4767.7     0.1       0  4952.5    0.07       0
  4956.5     0.1       0  4977.0    0.12       0
Bank Sta=4952.5,4956.5
Exp/Cntr=0.3,0.1

Type RM Length L Ch R = 1,848,233,233,233
BEGIN DESCRIPTION:
Lynn Creek T2 3.0
END DESCRIPTION:
XS GIS Cut Line= 3
      2718804.20      6777440.23      2718726.00      6777511.00
      2718647.83      6777581.75
#Sta/Elev= 30
  4899.5  366.55  4901.7  366.55  4906.0  365.79  4912.7  364.09  4920.1  363.01
  4926.9  359.68  4934.3  358.37  4948.5  355.48  4955.3  354.72  4969.5  352.42
  4976.9  349.81  4983.7  349.07  4991.1  348.92  4995.9  348.01  4996.1  347.51
  4999.6  347.51  4999.9  348.01  5001.6  349.05  5008.3  349.05  5012.1  350.21
  5026.3  353.58  5033.0  354.42  5040.5  355.88  5054.6  357.72  5075.6  359.25
  5083.0  359.27  5089.8  360.07  5097.2  360.07  5104.0  361.29  5110.4  361.03
#Mann=3,-1,0
  4899.5     0.1       0  4995.9    0.07       0  4999.9     0.1       0
Bank Sta=4995.9,4999.9
Exp/Cntr=0.3,0.1

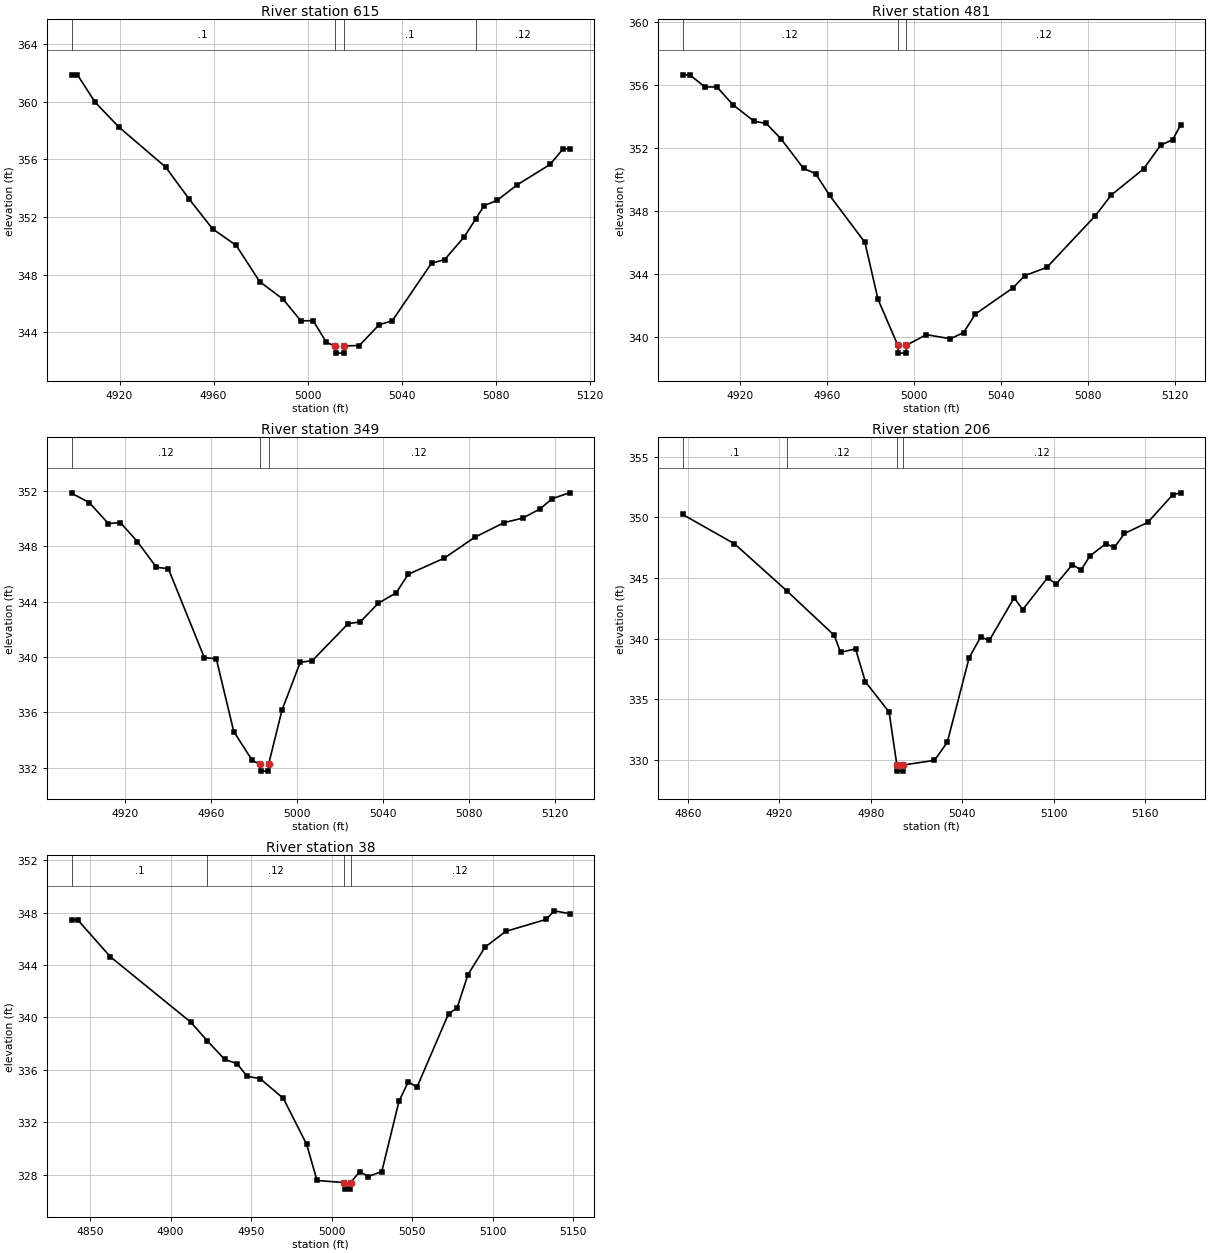
Type RM Length L Ch R = 1,615,134,134,134
BEGIN DESCRIPTION:
Lynn Creek T2 2.0
END DESCRIPTION:
XS GIS Cut Line= 3
      2718726.04      6777311.00      2718626.00      6777311.00
      2718526.04      6777360.98
#Sta/Elev= 30
  4899.6  361.88  4902.1  361.88  4909.6  359.98  4919.6  358.27  4939.6  355.47
  4949.6  353.25  4959.6  351.17  4969.6  350.03  4979.6  347.51  4989.6  346.28
  4997.1  344.79  5002.4  344.79  5008.0  343.28  5011.6  343.04  5011.9  342.54
  5015.4  342.54  5015.6  343.04  5022.0  343.07  5030.4  344.51  5036.0  344.79
  5052.7  348.79  5058.3  349.04  5066.7  350.64  5071.5  351.87  5075.1  352.79
  5080.7  353.17  5089.1  354.23  5103.1  355.65  5108.7  356.74  5111.4  356.74
#Mann=4,-1,0
  4899.6     0.1       0  5011.6    0.07       0  5015.6     0.1       0
  5071.5    0.12       0
Bank Sta=5011.6,5015.6
Exp/Cntr=0.3,0.1

Type RM Length L Ch R = 1,481,132,132,132
BEGIN DESCRIPTION:
Mapping XS 604d7349
END DESCRIPTION:
XS GIS Cut Line= 2
      2718696.95      6777139.95      2718490.68      6777238.96
#Sta/Elev= 30
  4893.7  356.63  4897.0  356.63  4904.0  355.86  4909.5  355.86  4916.9  354.73
  4926.6  353.69  4932.2  353.55  4939.1  352.55  4949.3  350.70  4954.8  350.38
  4961.3  348.99  4977.5  346.02  4983.5  342.42  4992.6  339.51  4992.8  339.01
  4996.3  339.01  4996.6  339.51  5005.7  340.18  5016.8  339.92  5022.8  340.31
  5028.3  341.49  5045.4  343.13  5051.0  343.92  5061.1  344.44  5083.3  347.70
  5090.7  349.02  5105.5  350.67  5113.4  352.18  5118.9  352.52  5122.5  353.44
#Mann=3,-1,0
  4893.7    0.12       0  4992.6    0.07       0  4996.6    0.12       0
Bank Sta=4992.6,4996.6
Exp/Cntr=0.3,0.1

Type RM Length L Ch R = 1,349,143,143,143
BEGIN DESCRIPTION:
Mapping XS 60ae44ae
END DESCRIPTION:
XS GIS Cut Line= 2
      2718633.32      6777026.78      2718426.66      6777131.12
#Sta/Elev= 30
  4895.1  351.82  4903.3  351.15  4912.2  349.63  4917.8  349.70  4925.7  348.33
  4934.5  346.48  4940.1  346.37  4956.8  339.96  4962.4  339.86  4970.5  334.62
  4979.1  332.53  4982.7  332.26  4983.0  331.76  4986.5  331.76  4986.7  332.26
  4992.9  336.15  5001.4  339.62  5007.0  339.73  5023.7  342.41  5029.3  342.53
  5037.7  343.88  5046.0  344.63  5051.6  345.97  5068.3  347.13  5082.5  348.64
  5096.2  349.70  5104.9  350.03  5112.9  350.69  5118.5  351.43  5126.6  351.85
#Mann=3,-1,0
  4895.1    0.12       0  4982.7    0.07       0  4986.7    0.12       0
Bank Sta=4982.7,4986.7
Exp/Cntr=0.3,0.1

Type RM Length L Ch R = 1,206,168,168,168
BEGIN DESCRIPTION:
Mapping XS 29207270
END DESCRIPTION:
XS GIS Cut Line= 3
      2718631.32      6776972.20      2718539.71      6776922.00
      2718343.57      6777026.92
#Sta/Elev= 30
  4856.4  350.24  4890.5  347.82  4924.7  343.96  4956.0  340.27  4960.1  338.88
  4970.0  339.15  4976.4  336.45  4992.0  333.95  4997.1  329.58  4997.3  329.08
  5000.8  329.08  5001.1  329.58  5021.8  329.97  5030.2  331.46  5044.5  338.41
  5052.1  340.14  5057.8  339.86  5074.1  343.37  5079.7  342.39  5096.0  345.01
  5101.7  344.50  5112.3  346.10  5118.0  345.66  5123.8  346.81  5134.2  347.82
  5139.9  347.52  5146.5  348.67  5161.8  349.58  5178.1  351.85  5183.3  352.02
#Mann=4,-1,0
  4856.4     0.1       0  4924.7    0.12       0  4997.1    0.07       0
  5001.1    0.12       0
Bank Sta=4997.1,5001.1
Exp/Cntr=0.3,0.1

Type RM Length L Ch R = 1,38,0,0,0
BEGIN DESCRIPTION:
Lynn Creek T2 1.0
END DESCRIPTION:
XS GIS Cut Line= 3
      2718625.73      6776925.28      2718525.13      6776799.06
      2718387.01      6776851.11
#Sta/Elev= 30
  4838.6  347.45  4842.4  347.45  4862.7  344.63  4912.4  339.66  4922.7  338.24
  4933.6  336.80  4941.2  336.48  4947.6  335.51  4955.6  335.33  4970.0  333.83
  4984.5  330.31  4990.9  327.56  5007.8  327.40  5008.0  326.90  5011.5  326.90
  5011.8  327.40  5017.4  328.24  5022.7  327.86  5031.1  328.24  5041.8  333.62
  5047.6  335.10  5052.9  334.67  5072.5  340.28  5077.8  340.72  5084.6  343.28
  5095.2  345.37  5108.0  346.57  5132.9  347.48  5138.2  348.14  5147.6  347.92
#Mann=4,-1,0
  4838.6     0.1       0  4922.7    0.12       0  5007.8    0.07       0
  5011.8    0.12       0
Bank Sta=5007.8,5011.8
Exp/Cntr=0.3,0.1

Chan Stop Cuts=-1