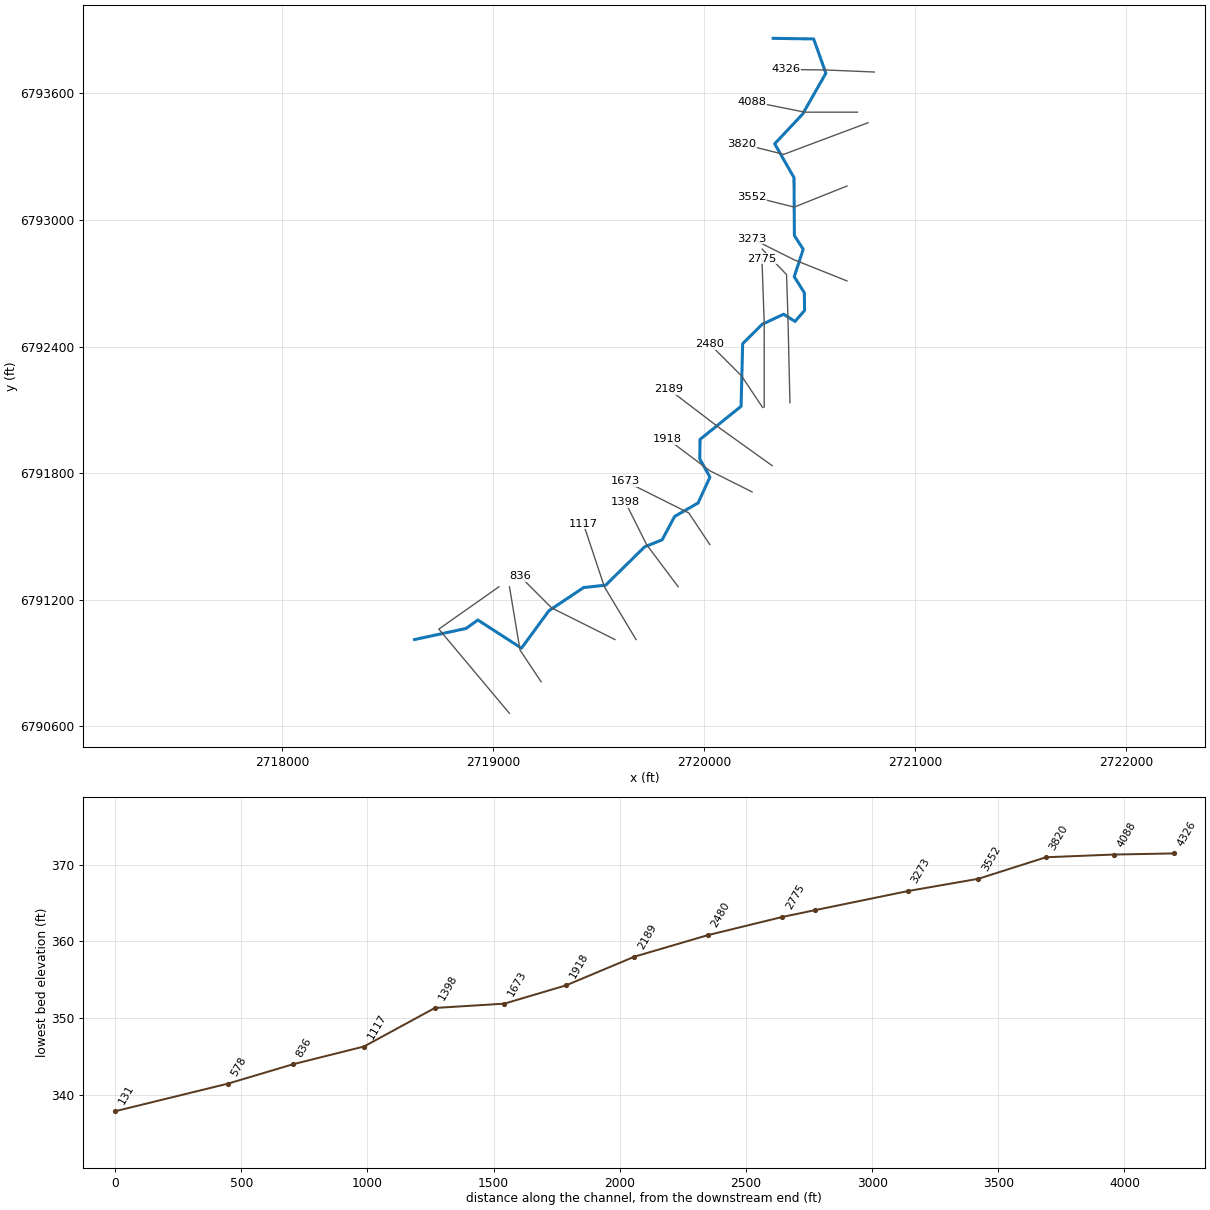
--- Lynn Creek T 20.prj (project) ---

Proj Title=Lynn Creek T 20 Base Level Engineering
Current Plan=p01
Default Exp/Contr=0.3,0.1
English Units
Geom File=g01
Flow File=f01
Plan File=p01
BEGIN DESCRIPTION:
Lynn Creek T 20
END DESCRIPTION:

--- Lynn Creek T 20.p01 (plan) ---

Plan Title=Multiple Run
Short Identifier=Multiple
Geom File=g01
Flow File=f01
Subcritical Flow
K Sum by GR= 0
Std Step Tol= 0.01
Critical Tol= 0.01
Num of Std Step Trials= 20
Max Error Tol= 0.3
Flow Tol Ratio= 0.001
Split Flow NTrial= 30
Split Flow Tol= 0.02
Split Flow Ratio= 0.02
Log Output Level= 0
Friction Slope Method= 1
Unsteady Friction Slope Method= 2
Unsteady Bridges Friction Slope Method= 1
Parabolic Critical Depth
Global Vel Dist=  1 , 1 , 1
Global Log Level= 0
CheckData=True
Encroach Param= -1, 0, 0, 0
BEGIN DESCRIPTION:
Multiple Run
END DESCRIPTION:

--- Lynn Creek T 20.f01 (steady flow) ---

Flow Title=Multiple
Number of Profiles=7
Profile Names=10-year,25-year,50-year,1pct_min,100-year,1pct_plu,500-year
River Rch & RM= Lynn Creek T 20,Reach-1,4326
     222     278     321     184     367     733     480
River Rch & RM= Lynn Creek T 20,Reach-1,3273
     336     433     509     298     594    1185     806
Boundary for River Rch & Prof#=Lynn Creek T 20,Reach-1,1
Up Type=0
Dn Type=3
Dn Slope=0.005
Boundary for River Rch & Prof#=Lynn Creek T 20,Reach-1,2
Up Type=0
Dn Type=3
Dn Slope=0.005
Boundary for River Rch & Prof#=Lynn Creek T 20,Reach-1,3
Up Type=0
Dn Type=3
Dn Slope=0.005
Boundary for River Rch & Prof#=Lynn Creek T 20,Reach-1,4
Up Type=0
Dn Type=3
Dn Slope=0.005
Boundary for River Rch & Prof#=Lynn Creek T 20,Reach-1,5
Up Type=0
Dn Type=3
Dn Slope=0.005
Boundary for River Rch & Prof#=Lynn Creek T 20,Reach-1,6
Up Type=0
Dn Type=3
Dn Slope=0.005
Boundary for River Rch & Prof#=Lynn Creek T 20,Reach-1,7
Up Type=0
Dn Type=3
Dn Slope=0.005

--- Lynn Creek T 20.g01 (geometry) ---

Geom Title=Existing Conditions

River Reach=Lynn Creek T 20,Reach-1
Reach XY= 30
      2720326.00      6793861.00      2720518.04      6793858.08
      2720575.97      6793695.58      2720465.22      6793501.32
      2720333.29      6793361.09      2720424.80      6793200.50
      2720426.66      6792926.16      2720468.44      6792861.00
      2720425.91      6792731.10      2720473.83      6792655.02
      2720475.07      6792571.15      2720429.63      6792518.88
      2720376.10      6792553.22      2720273.70      6792505.20
      2720181.45      6792413.47      2720173.95      6792116.84
      2719979.37      6791959.72      2719978.19      6791866.97
      2720026.29      6791781.17      2719970.27      6791658.45
      2719858.96      6791594.50      2719799.83      6791483.87
      2719716.34      6791450.21      2719532.17      6791268.86
      2719427.50      6791257.37      2719262.76      6791147.38
      2719133.01      6790969.99      2718926.10      6791103.67
      2718870.14      6791063.48      2718626.00      6791011.00

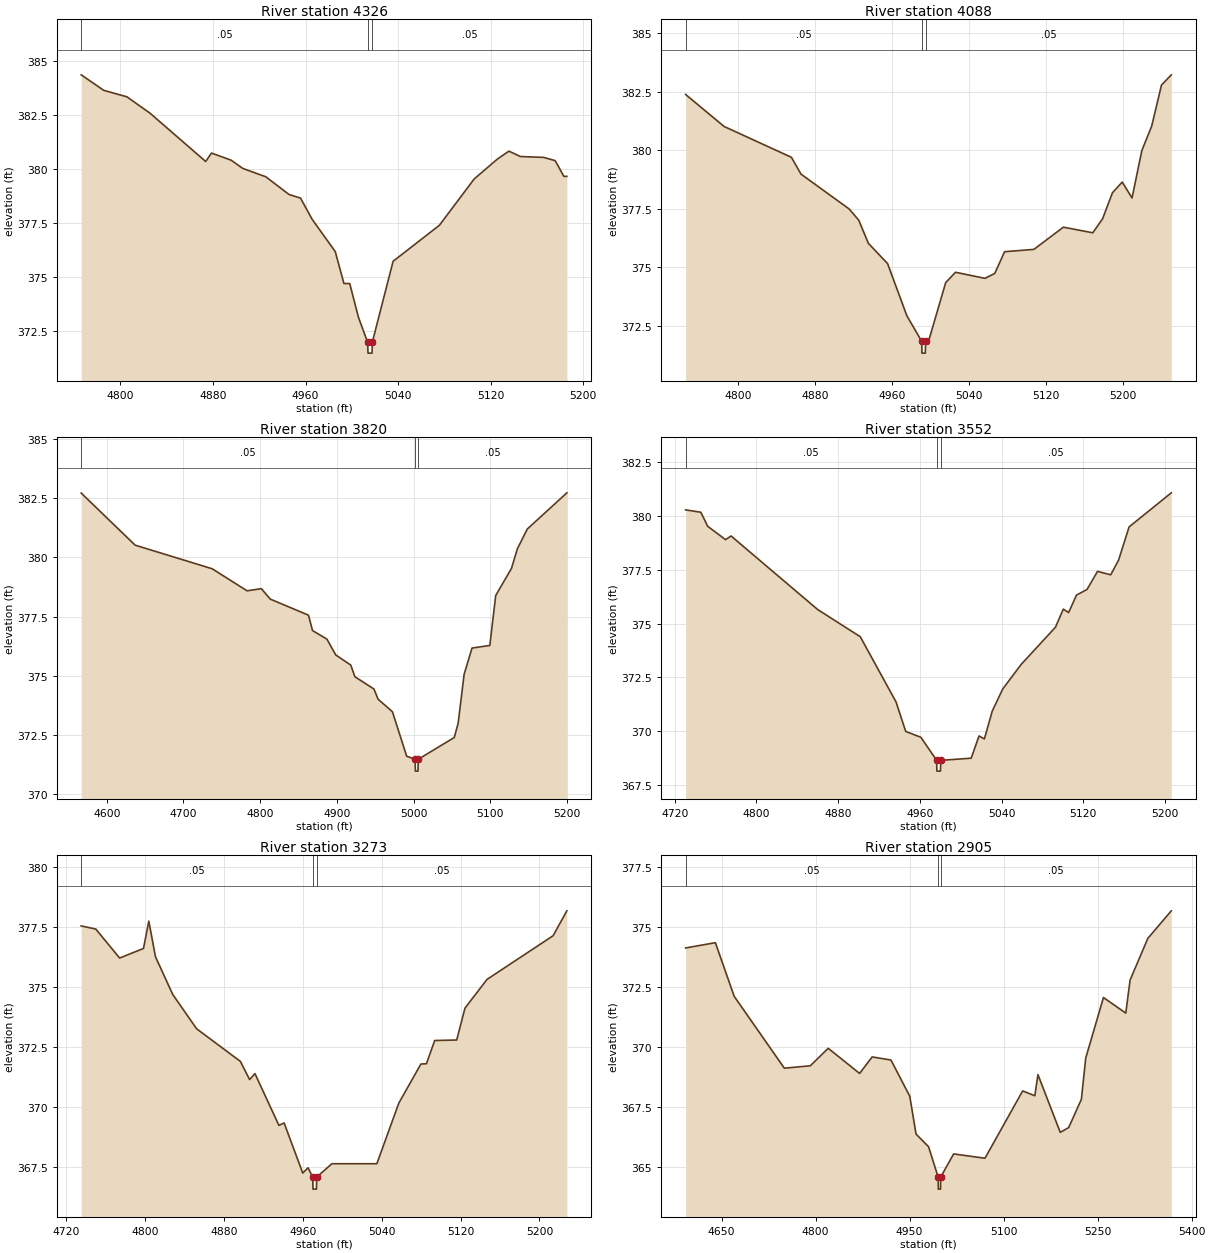
Type RM Length L Ch R = 1,4326,238,238,238
BEGIN DESCRIPTION:
Lynn Creek T 20 16.0
END DESCRIPTION:
XS GIS Cut Line= 3
      2720805.44      6793701.35      2720576.00      6793711.00
      2720385.86      6793713.27
#Sta/Elev= 30
  4766.1  384.38  4785.6  383.66  4805.6  383.36  4825.6  382.60  4873.7  380.36
  4878.7  380.75  4895.7  380.42  4905.7  380.04  4925.7  379.65  4945.7  378.83
  4955.7  378.66  4965.7  377.68  4985.7  376.18  4993.2  374.70  4998.2  374.70
  5005.7  373.14  5013.7  371.97  5014.0  371.47  5017.5  371.47  5017.7  371.97
  5035.7  375.73  5075.7  377.40  5105.8  379.55  5125.8  380.47  5135.8  380.84
  5145.8  380.59  5165.8  380.55  5175.8  380.40  5183.3  379.67  5185.9  379.67
#Mann=3,-1,0
  4766.1    0.05       0  5013.7    0.04       0  5017.7    0.05       0
Bank Sta=5013.7,5017.7
Exp/Cntr=0.3,0.1

Type RM Length L Ch R = 1,4088,268,268,268
BEGIN DESCRIPTION:
Lynn Creek T 20 15.0
END DESCRIPTION:
XS GIS Cut Line= 3
      2720725.97      6793511.00      2720476.00      6793511.00
      2720226.02      6793561.00
#Sta/Elev= 30
  4745.6  382.39  4785.6  381.02  4855.6  379.70  4865.6  378.98  4915.6  377.49
  4925.6  377.01  4935.6  376.02  4955.6  375.15  4975.6  372.92  4991.1  371.82
  4991.3  371.32  4994.8  371.32  4995.1  371.82  4998.1  371.82  5016.0  374.34
  5026.2  374.78  5056.8  374.52  5067.0  374.73  5077.2  375.66  5107.7  375.76
  5138.3  376.71  5168.9  376.47  5179.1  377.07  5189.3  378.18  5199.5  378.64
  5209.7  377.96  5219.9  379.99  5230.1  381.03  5240.3  382.79  5250.5  383.23
#Mann=3,-1,0
  4745.6    0.05       0  4991.1    0.04       0  4995.1    0.05       0
Bank Sta=4991.1,4995.1
Exp/Cntr=0.3,0.1

Type RM Length L Ch R = 1,3820,268,268,268
BEGIN DESCRIPTION:
Lynn Creek T 20 14.0
END DESCRIPTION:
XS GIS Cut Line= 3
      2720776.01      6793461.00      2720376.00      6793311.00
      2720175.97      6793361.01
#Sta/Elev= 30
  4566.6  382.72  4636.9  380.52  4737.5  379.52  4782.9  378.59  4801.6  378.68
  4813.1  378.24  4863.0  377.56  4868.3  376.91  4887.0  376.55  4898.6  375.88
  4918.2  375.45  4923.5  374.96  4948.4  374.44  4953.8  374.01  4972.5  373.48
  4991.1  371.60  5002.1  371.47  5002.4  370.97  5005.9  370.97  5006.1  371.47
  5053.1  372.39  5058.2  372.99  5066.0  375.06  5076.3  376.17  5099.5  376.28
  5107.2  378.39  5127.8  379.54  5135.5  380.37  5148.4  381.20  5200.0  382.73
#Mann=3,-1,0
  4566.6    0.05       0  5002.1    0.04       0  5006.1    0.05       0
Bank Sta=5002.1,5006.1
Exp/Cntr=0.3,0.1

Type RM Length L Ch R = 1,3552,279,279,279
BEGIN DESCRIPTION:
Lynn Creek T 20 13.0
END DESCRIPTION:
XS GIS Cut Line= 3
      2720676.05      6793161.02      2720426.00      6793061.00
      2720225.96      6793111.01
#Sta/Elev= 30
  4730.7  380.27  4745.6  380.16  4752.3  379.51  4769.8  378.89  4775.2  379.06
  4860.0  375.65  4901.7  374.39  4936.7  371.37  4946.2  370.00  4961.0  369.73
  4976.5  368.66  4976.7  368.16  4980.2  368.16  4980.5  368.66  5010.3  368.76
  5018.0  369.79  5023.2  369.65  5030.9  370.94  5041.2  371.97  5059.3  373.11
  5092.8  374.83  5100.5  375.67  5105.7  375.51  5113.4  376.32  5123.7  376.58
  5134.0  377.42  5146.9  377.26  5154.6  377.94  5164.9  379.48  5206.2  381.06
#Mann=3,-1,0
  4730.7    0.05       0  4976.5    0.04       0  4980.5    0.05       0
Bank Sta=4976.5,4980.5
Exp/Cntr=0.3,0.1

Type RM Length L Ch R = 1,3273,368,368,368
BEGIN DESCRIPTION:
Lynn Creek T 20 12.0
END DESCRIPTION:
XS GIS Cut Line= 3
      2720675.96      6792711.02      2720426.00      6792811.00
      2720226.02      6792910.99
#Sta/Elev= 30
  4735.0  377.54  4749.8  377.41  4774.0  376.20  4798.2  376.60  4803.6  377.74
  4810.4  376.25  4827.9  374.68  4852.1  373.25  4896.5  371.89  4905.9  371.13
  4911.3  371.38  4935.6  369.22  4940.9  369.32  4959.8  367.23  4965.2  367.45
  4969.9  367.06  4970.2  366.56  4973.7  366.56  4973.9  367.06  4989.4  367.62
  5035.0  367.62  5057.3  370.15  5079.7  371.78  5085.3  371.79  5093.7  372.76
  5116.0  372.78  5124.4  374.11  5146.8  375.31  5213.8  377.13  5227.8  378.17
#Mann=3,-1,0
  4735.0    0.05       0  4969.9    0.04       0  4973.9    0.05       0
Bank Sta=4969.9,4973.9
Exp/Cntr=0.3,0.1

Type RM Length L Ch R = 1,2905,130,130,130
BEGIN DESCRIPTION:
Lynn Creek T 20 11.0
END DESCRIPTION:
XS GIS Cut Line= 4
      2720405.53      6792133.52      2720396.08      6792540.71
      2720389.49      6792740.91      2720273.90      6792861.72
#Sta/Elev= 30
  4592.7  374.14  4640.2  374.36  4670.2  372.12  4750.2  369.12  4791.6  369.22
  4820.2  369.95  4870.3  368.90  4890.3  369.59  4920.3  369.46  4950.3  367.95
  4960.3  366.37  4980.3  365.84  4995.6  364.57  4995.9  364.07  4999.4  364.07
  4999.6  364.57  5020.3  365.54  5070.3  365.36  5130.4  368.17  5149.8  367.97
  5154.8  368.85  5190.4  366.44  5203.8  366.64  5224.1  367.82  5231.0  369.54
  5259.3  372.07  5294.9  371.42  5301.8  372.80  5330.1  374.54  5367.5  375.69
#Mann=3,-1,0
  4592.7    0.05       0  4995.6    0.04       0  4999.6    0.05       0
Bank Sta=4995.6,4999.6
Exp/Cntr=0.3,0.1

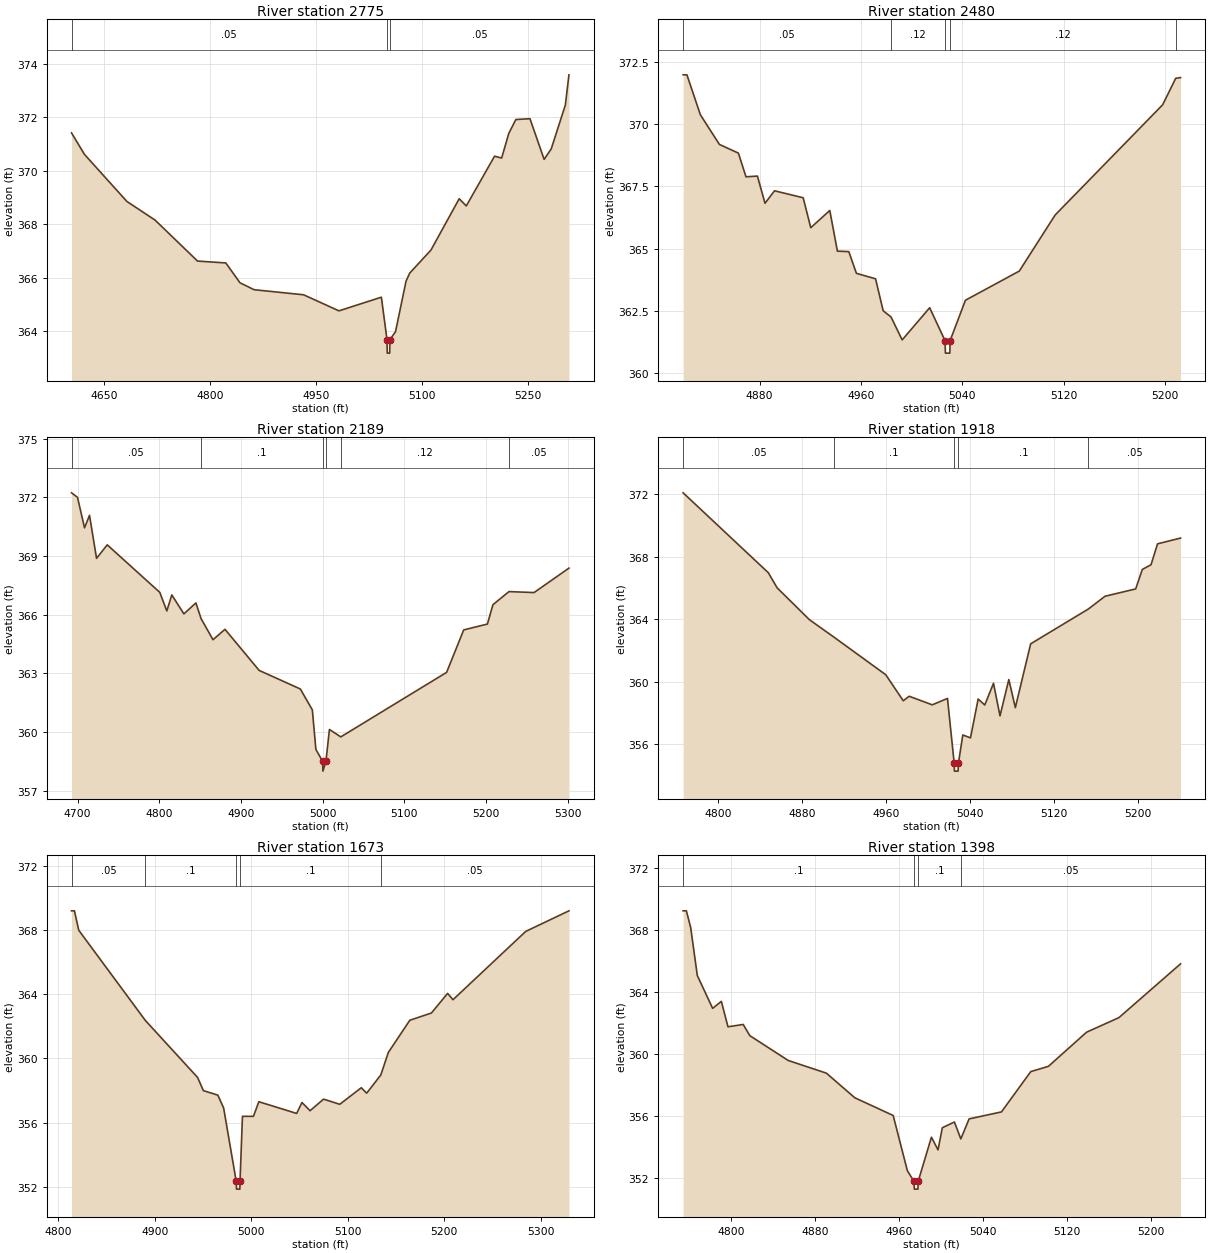
Type RM Length L Ch R = 1,2775,295,295,295
BEGIN DESCRIPTION:
Lynn Creek T 20 10.0
END DESCRIPTION:
XS GIS Cut Line= 3
      2720283.61      6792112.79      2720283.61      6792512.82
      2720272.76      6792816.09
#Sta/Elev= 30
  4603.9  371.41  4622.1  370.61  4682.1  368.85  4722.1  368.15  4782.1  366.62
  4822.1  366.55  4842.1  365.81  4862.1  365.55  4932.1  365.36  4982.1  364.76
  5042.1  365.27  5050.1  363.68  5050.4  363.18  5053.9  363.18  5054.1  363.68
  5062.1  363.98  5077.0  365.87  5082.2  366.17  5112.2  367.03  5152.2  368.95
  5162.2  368.68  5202.2  370.54  5212.2  370.47  5222.3  371.39  5232.3  371.91
  5252.3  371.94  5272.3  370.42  5282.3  370.81  5302.3  372.45  5307.4  373.58
#Mann=3,-1,0
  4603.9    0.05       0  5050.1    0.05       0  5054.1    0.05       0
Bank Sta=5050.1,5054.1
Exp/Cntr=0.3,0.1

Type RM Length L Ch R = 1,2480,291,291,291
BEGIN DESCRIPTION:
Lynn Creek T 20 9.0
END DESCRIPTION:
XS GIS Cut Line= 3
      2720276.02      6792110.97      2720176.00      6792261.00
      2720026.03      6792410.97
#Sta/Elev= 30
  4819.7  371.97  4822.7  371.97  4833.3  370.37  4848.3  369.18  4863.3  368.83
  4869.3  367.88  4878.3  367.91  4884.3  366.82  4891.8  367.32  4914.4  367.04
  4920.4  365.84  4935.4  366.53  4941.4  364.90  4950.4  364.88  4956.4  364.01
  4971.5  363.79  4977.5  362.51  4983.7  362.26  4992.5  361.34  5014.2  362.63
  5026.3  361.31  5026.6  360.81  5030.1  360.81  5030.3  361.31  5042.4  362.93
  5084.9  364.10  5113.2  366.35  5198.0  370.77  5208.3  371.83  5212.1  371.86
#Mann=5,-1,0
  4819.7    0.05       0  4983.7    0.12       0  5026.3    0.07       0
  5030.3    0.12       0  5208.3    0.05       0
Bank Sta=5026.3,5030.3
Exp/Cntr=0.3,0.1

Type RM Length L Ch R = 1,2189,271,271,271
BEGIN DESCRIPTION:
Lynn Creek T 20 8.0
END DESCRIPTION:
XS GIS Cut Line= 3
      2720321.56      6791835.09      2720076.00      6792011.00
      2719832.00      6792196.71
#Sta/Elev= 30
  4692.7  372.23  4700.0  372.00  4708.6  370.44  4714.7  371.08  4723.3  368.88
  4736.4  369.57  4800.7  367.14  4809.3  366.19  4815.4  367.01  4830.2  366.04
  4844.9  366.60  4851.2  365.80  4865.8  364.72  4880.5  365.25  4922.3  363.15
  4972.7  362.20  4987.4  361.13  4991.7  359.11  5000.0  358.50  5000.3  358.00
  5004.0  358.50  5008.3  360.13  5022.2  359.75  5151.7  363.05  5172.6  365.22
  5201.6  365.52  5208.4  366.51  5228.0  367.18  5258.7  367.13  5301.4  368.38
#Mann=6,-1,0
  4692.7    0.05       0  4851.2     0.1       0  5000.0    0.07       0
  5004.0     0.1       0  5022.2    0.12       0  5228.0    0.05       0
Bank Sta=5000,5004
Exp/Cntr=0.3,0.1

Type RM Length L Ch R = 1,1918,245,245,245
BEGIN DESCRIPTION:
Lynn Creek T 20 7.0
END DESCRIPTION:
XS GIS Cut Line= 3
      2720226.02      6791710.99      2720026.00      6791811.00
      2719826.02      6791960.99
#Sta/Elev= 30
  4766.7  372.10  4847.8  366.98  4856.2  366.01  4886.9  363.97  4910.5  362.84
  4959.6  360.44  4976.3  358.77  4981.9  359.06  5003.9  358.51  5018.4  358.92
  5024.8  354.76  5025.0  354.26  5028.5  354.26  5028.8  354.76  5033.0  356.58
  5040.3  356.39  5047.6  358.88  5053.9  358.50  5062.2  359.89  5068.4  357.80
  5076.8  360.13  5083.0  358.33  5097.6  362.42  5152.5  364.65  5168.4  365.47
  5197.6  365.94  5203.9  367.19  5212.2  367.49  5218.4  368.83  5240.3  369.20
#Mann=5,-1,0
  4766.7    0.05       0  4910.5     0.1       0  5024.8    0.07       0
  5028.8     0.1       0  5152.5    0.05       0
Bank Sta=5024.8,5028.8
Exp/Cntr=0.3,0.1

Type RM Length L Ch R = 1,1673,275,275,275
BEGIN DESCRIPTION:
Lynn Creek T 20 6.0
END DESCRIPTION:
XS GIS Cut Line= 3
      2720025.98      6791461.02      2719926.00      6791611.00
      2719625.96      6791761.02
#Sta/Elev= 30
  4813.8  369.19  4816.8  369.19  4821.3  367.98  4890.3  362.37  4944.5  358.82
  4950.5  358.00  4965.5  357.72  4971.5  356.92  4984.5  352.37  4984.8  351.87
  4988.3  351.87  4988.5  352.37  4991.0  356.40  5002.4  356.40  5008.0  357.31
  5047.2  356.58  5052.7  357.26  5061.1  356.75  5075.1  357.47  5091.9  357.15
  5114.2  358.18  5119.8  357.84  5134.5  358.98  5142.2  360.37  5164.5  362.38
  5186.9  362.83  5203.7  364.05  5209.3  363.66  5284.7  367.91  5329.5  369.19
#Mann=5,-1,0
  4813.8    0.05       0  4890.3     0.1       0  4984.5    0.07       0
  4988.5     0.1       0  5134.5    0.05       0
Bank Sta=4984.5,4988.5
Exp/Cntr=0.3,0.1

Type RM Length L Ch R = 1,1398,281,281,281
BEGIN DESCRIPTION:
Lynn Creek T 20 5.0
END DESCRIPTION:
XS GIS Cut Line= 3
      2719875.97      6791261.04      2719726.00      6791461.00
      2719625.98      6791661.04
#Sta/Elev= 30
  4754.6  369.26  4757.7  369.26  4761.8  368.18  4768.1  365.09  4782.7  362.97
  4791.0  363.42  4797.3  361.78  4811.8  361.93  4818.1  361.21  4854.6  359.61
  4891.0  358.79  4918.1  357.20  4954.6  356.06  4968.1  352.50  4974.4  351.81
  4974.7  351.31  4978.2  351.31  4978.4  351.81  4991.0  354.66  4997.3  353.84
  5001.4  355.27  5012.9  355.64  5019.0  354.55  5026.9  355.84  5057.7  356.29
  5085.6  358.89  5102.4  359.23  5138.7  361.43  5169.5  362.37  5228.2  365.84
#Mann=4,-1,0
  4754.6     0.1       0  4974.4    0.07       0  4978.4     0.1       0
  5019.0    0.05       0
Bank Sta=4974.4,4978.4
Exp/Cntr=0.3,0.1

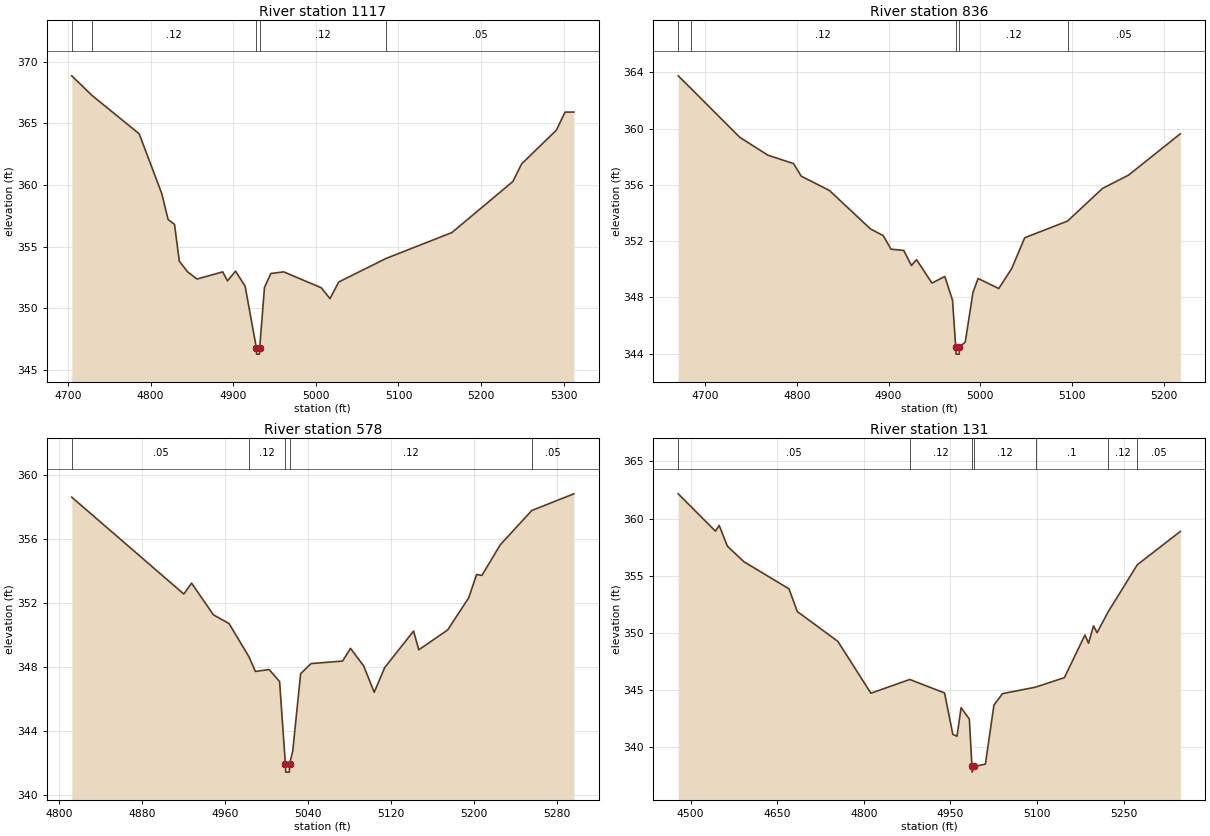
Type RM Length L Ch R = 1,1117,281,281,281
BEGIN DESCRIPTION:
Lynn Creek T 20 4.0
END DESCRIPTION:
XS GIS Cut Line= 3
      2719676.01      6791010.99      2719526.00      6791261.00
      2719426.00      6791561.01
#Sta/Elev= 30
  4704.5  368.85  4729.0  367.26  4786.1  364.15  4813.4  359.31  4821.1  357.20
  4828.9  356.80  4834.7  353.82  4844.5  352.97  4856.1  352.37  4887.2  352.95
  4893.0  352.22  4902.8  353.01  4914.4  351.78  4928.0  346.78  4928.2  346.28
  4931.7  346.28  4932.0  346.78  4937.8  351.69  4945.5  352.82  4961.1  352.95
  5006.6  351.66  5017.1  350.78  5027.7  352.13  5085.0  354.04  5164.7  356.14
  5238.5  360.28  5249.0  361.70  5291.2  364.45  5301.7  365.91  5312.3  365.91
#Mann=5,-1,0
  4704.5    0.05       0  4729.0    0.12       0  4928.0    0.07       0
  4932.0    0.12       0  5085.0    0.05       0
Bank Sta=4928,4932
Exp/Cntr=0.3,0.1

Type RM Length L Ch R = 1,836,258,258,258
BEGIN DESCRIPTION:
Lynn Creek T 20 3.0
END DESCRIPTION:
XS GIS Cut Line= 3
      2719575.98      6791011.01      2719276.00      6791161.00
      2719126.02      6791310.98
#Sta/Elev= 30
  4670.7  363.75  4684.6  362.85  4737.8  359.38  4768.5  358.11  4796.5  357.51
  4804.8  356.62  4835.6  355.60  4880.3  352.87  4894.3  352.39  4902.7  351.43
  4916.6  351.34  4925.0  350.27  4930.6  350.68  4947.4  349.02  4961.4  349.49
  4969.8  347.80  4973.3  344.47  4973.6  343.97  4977.1  343.97  4977.3  344.47
  4983.7  344.83  4992.1  348.35  4997.7  349.35  5020.2  348.63  5034.4  350.06
  5048.5  352.24  5095.3  353.43  5133.4  355.75  5161.7  356.69  5218.2  359.63
#Mann=5,-1,0
  4670.7    0.05       0  4684.6    0.12       0  4973.3    0.07       0
  4977.3    0.12       0  5095.3    0.05       0
Bank Sta=4973.3,4977.3
Exp/Cntr=0.3,0.1

Type RM Length L Ch R = 1,578,447,447,447
BEGIN DESCRIPTION:
Lynn Creek T 20 2.0
END DESCRIPTION:
XS GIS Cut Line= 3
      2719225.98      6790811.03      2719126.00      6790961.00
      2719076.00      6791261.02
#Sta/Elev= 30
  4812.2  358.59  4920.3  352.55  4927.8  353.23  4948.9  351.25  4963.9  350.71
  4983.2  348.63  4989.4  347.72  5002.6  347.84  5012.7  347.09  5018.3  341.94
  5018.6  341.44  5022.1  341.44  5022.3  341.94  5025.4  342.76  5033.0  347.58
  5043.1  348.21  5073.5  348.37  5081.1  349.16  5093.8  348.07  5104.0  346.42
  5114.1  347.96  5142.0  350.24  5147.0  349.07  5174.9  350.31  5195.2  352.32
  5202.8  353.77  5207.9  353.71  5225.6  355.62  5256.0  357.76  5296.6  358.80
#Mann=5,-1,0
  4812.2    0.05       0  4983.2    0.12       0  5018.3    0.07       0
  5022.3    0.12       0  5256.0    0.05       0
Bank Sta=5018.3,5022.3
Exp/Cntr=0.3,0.1

Type RM Length L Ch R = 1,131,0,0,0
BEGIN DESCRIPTION:
Lynn Creek T 20 1.0
END DESCRIPTION:
XS GIS Cut Line= 3
      2719076.02      6790660.98      2718741.19      6791060.53
      2719026.01      6791261.01
#Sta/Elev= 30
  4478.7  362.17  4543.1  358.91  4549.6  359.41  4563.9  357.59  4592.6  356.23
  4670.6  353.86  4684.9  351.88  4755.2  349.27  4812.4  344.74  4879.7  345.94
  4940.0  344.76  4954.3  341.14  4961.5  340.98  4968.6  343.47  4982.9  342.48
  4987.4  338.34  4987.7  337.84  4991.4  338.34  5010.7  338.54  5025.5  343.70
  5040.3  344.70  5097.7  345.27  5147.5  346.10  5183.2  349.83  5189.3  349.11
  5198.0  350.63  5204.1  350.03  5223.3  351.85  5273.8  355.97  5348.3  358.88
#Mann=7,-1,0
  4478.7    0.05       0  4879.7    0.12       0  4987.4    0.07       0
  4991.4    0.12       0  5097.7     0.1       0  5223.3    0.12       0
  5273.8    0.05       0
Bank Sta=4987.4,4991.4
Exp/Cntr=0.3,0.1

Chan Stop Cuts=-1