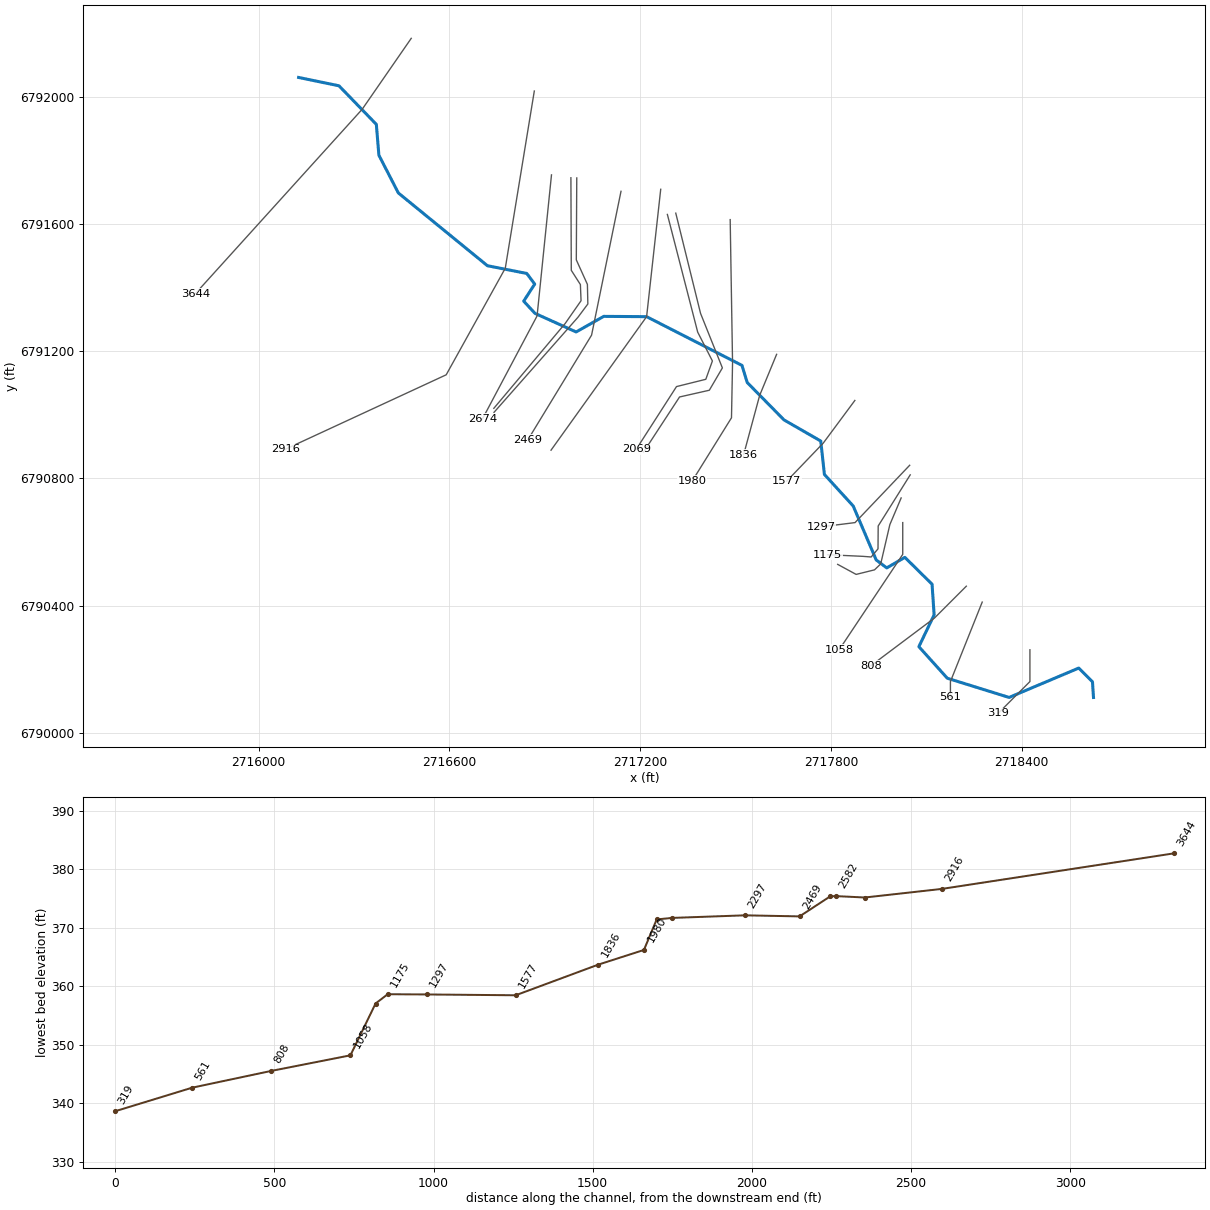
--- Lynn Creek T 21.prj (project) ---

Proj Title=Lynn Creek T 21 Base Level Engineering
Current Plan=p01
Default Exp/Contr=0.3,0.1
English Units
Geom File=g01
Flow File=f01
Plan File=p01
BEGIN DESCRIPTION:
Lynn Creek T 21
END DESCRIPTION:

--- Lynn Creek T 21.p01 (plan) ---

Plan Title=Multiple Run
Short Identifier=Multiple
Geom File=g01
Flow File=f01
Subcritical Flow
K Sum by GR= 0
Std Step Tol= 0.01
Critical Tol= 0.01
Num of Std Step Trials= 20
Max Error Tol= 0.3
Flow Tol Ratio= 0.001
Split Flow NTrial= 30
Split Flow Tol= 0.02
Split Flow Ratio= 0.02
Log Output Level= 0
Friction Slope Method= 1
Unsteady Friction Slope Method= 2
Unsteady Bridges Friction Slope Method= 1
Parabolic Critical Depth
Global Vel Dist=  1 , 1 , 1
Global Log Level= 0
CheckData=True
Encroach Param= -1, 0, 0, 0
BEGIN DESCRIPTION:
Multiple Run
END DESCRIPTION:

--- Lynn Creek T 21.f01 (steady flow) ---

Flow Title=Multiple
Number of Profiles=7
Profile Names=10-year,25-year,50-year,1pct_min,100-year,1pct_plu,500-year
River Rch & RM= Lynn Creek T 21,Reach-1,3644
     200     249     287     165     329     656     429
Boundary for River Rch & Prof#=Lynn Creek T 21,Reach-1,1
Up Type=0
Dn Type=3
Dn Slope=0.005
Boundary for River Rch & Prof#=Lynn Creek T 21,Reach-1,2
Up Type=0
Dn Type=3
Dn Slope=0.005
Boundary for River Rch & Prof#=Lynn Creek T 21,Reach-1,3
Up Type=0
Dn Type=3
Dn Slope=0.005
Boundary for River Rch & Prof#=Lynn Creek T 21,Reach-1,4
Up Type=0
Dn Type=3
Dn Slope=0.005
Boundary for River Rch & Prof#=Lynn Creek T 21,Reach-1,5
Up Type=0
Dn Type=3
Dn Slope=0.005
Boundary for River Rch & Prof#=Lynn Creek T 21,Reach-1,6
Up Type=0
Dn Type=3
Dn Slope=0.005
Boundary for River Rch & Prof#=Lynn Creek T 21,Reach-1,7
Up Type=0
Dn Type=3
Dn Slope=0.005

--- Lynn Creek T 21.g01 (geometry) ---

Geom Title=Existing Conditions

River Reach=Lynn Creek T 21,Reach-1
Reach XY= 30
      2716126.00      6792061.00      2716252.87      6792034.81
      2716370.48      6791913.43      2716378.45      6791816.56
      2716439.62      6791697.78      2716719.84      6791468.88
      2716843.61      6791444.54      2716868.53      6791411.23
      2716833.90      6791357.43      2716869.32      6791319.14
      2716998.80      6791260.61      2717085.66      6791309.61
      2717220.48      6791308.66      2717520.39      6791155.41
      2717536.89      6791101.58      2717652.54      6790984.02
      2717768.25      6790917.45      2717779.63      6790812.50
      2717870.15      6790713.29      2717942.64      6790543.47
      2717975.79      6790518.47      2718032.68      6790551.70
      2718118.24      6790467.21      2718124.71      6790370.70
      2718076.75      6790270.77      2718166.19      6790171.51
      2718360.61      6790111.09      2718579.62      6790203.50
      2718622.73      6790160.37      2718626.00      6790111.00

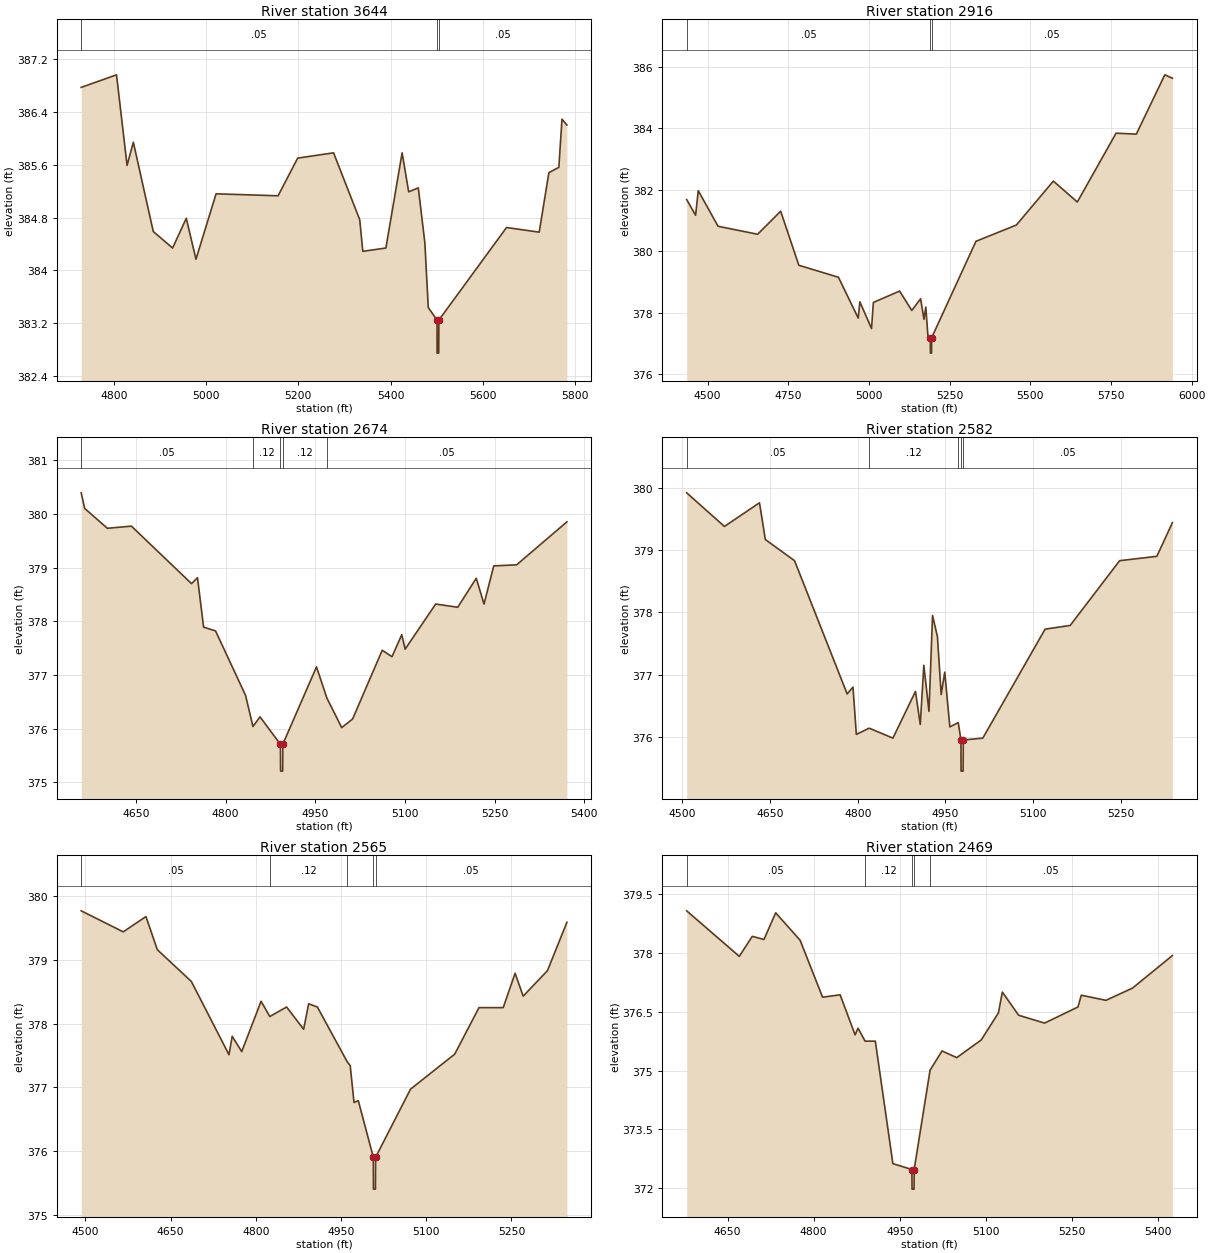
Type RM Length L Ch R = 1,3644,728,728,728
BEGIN DESCRIPTION:
Lynn Creek T 21 11.0
END DESCRIPTION:
XS GIS Cut Line= 3
      2716480.22      6792184.04      2716326.00      6791961.00
      2715801.15      6791380.98
#Sta/Elev= 30
  4729.1  386.77  4805.7  386.96  4828.6  385.59  4842.2  385.94  4885.4  384.59
  4927.3  384.34  4957.0  384.79  4978.0  384.17  5021.6  385.16  5156.1  385.13
  5198.6  385.70  5276.4  385.78  5333.1  384.77  5339.9  384.29  5389.9  384.34
  5425.1  385.78  5439.3  385.19  5460.2  385.25  5474.4  384.42  5481.8  383.44
  5500.8  383.25  5501.0  382.75  5504.5  382.75  5504.8  383.25  5651.5  384.65
  5722.4  384.58  5743.4  385.48  5765.0  385.56  5771.8  386.29  5782.5  386.20
#Mann=3,-1,0
  4729.1    0.05       0  5500.8    0.04       0  5504.8    0.05       0
Bank Sta=5500.8,5504.8
Exp/Cntr=0.3,0.1

Type RM Length L Ch R = 1,2916,242,242,242
BEGIN DESCRIPTION:
Lynn Creek T 21 10.0
END DESCRIPTION:
XS GIS Cut Line= 4
      2716867.30      6792018.36      2716776.00      6791461.00
      2716590.18      6791125.84      2716084.63      6790891.80
#Sta/Elev= 30
  4435.2  381.68  4462.9  381.17  4471.1  381.97  4532.4  380.81  4655.1  380.55
  4726.5  381.30  4782.8  379.54  4905.5  379.15  4966.8  377.82  4971.9  378.35
  5008.0  377.48  5013.7  378.33  5095.0  378.70  5132.8  378.07  5160.2  378.45
  5170.5  377.78  5176.2  378.18  5182.9  377.22  5190.3  377.18  5190.5  376.68
  5194.0  376.68  5194.3  377.18  5331.6  380.32  5456.8  380.85  5571.5  382.28
  5645.7  381.60  5765.8  383.84  5828.6  383.81  5916.8  385.74  5940.3  385.63
#Mann=3,-1,0
  4435.2    0.05       0  5190.3    0.04       0  5194.3    0.05       0
Bank Sta=5190.3,5194.3
Exp/Cntr=0.3,0.1

Type RM Length L Ch R = 1,2674,92,92,92
BEGIN DESCRIPTION:
Lynn Creek T 21 9.0
END DESCRIPTION:
XS GIS Cut Line= 3
      2716921.31      6791754.60      2716876.00      6791311.00
      2716704.14      6790986.96
#Sta/Elev= 30
  4558.4  380.39  4564.2  380.10  4602.2  379.73  4642.4  379.77  4743.0  378.70
  4753.0  378.81  4763.2  377.89  4783.2  377.82  4833.4  376.62  4845.8  376.04
  4857.6  376.22  4891.7  375.71  4892.0  375.21  4895.5  375.21  4895.7  375.71
  4952.1  377.15  4969.5  376.57  4994.3  376.02  5012.5  376.18  5062.1  377.46
  5078.4  377.34  5094.8  377.75  5100.4  377.48  5151.5  378.32  5188.4  378.26
  5219.4  378.80  5232.4  378.32  5248.7  379.03  5287.0  379.05  5371.1  379.85
#Mann=5,-1,0
  4558.4    0.05       0  4845.8    0.12       0  4891.7    0.04       0
  4895.7    0.12       0  4969.5    0.05       0
Bank Sta=4891.7,4895.7
Exp/Cntr=0.3,0.1

Type RM Length L Ch R = 1,2582,17,17,17
BEGIN DESCRIPTION:
Mapping XS 8904392b
END DESCRIPTION:
XS GIS Cut Line= 6
      2716982.39      6791745.55      2716983.58      6791454.47
      2717012.20      6791409.67      2717014.29      6791358.85
      2716964.45      6791287.34      2716739.94      6791020.37
#Sta/Elev= 30
  4507.2  379.92  4571.8  379.38  4631.8  379.76  4641.8  379.17  4691.8  378.83
  4781.8  376.69  4791.8  376.80  4797.5  376.04  4819.5  376.14  4860.1  375.98
  4898.7  376.73  4906.9  376.20  4913.0  377.15  4921.8  376.41  4927.9  377.95
  4936.3  377.61  4942.7  376.68  4948.8  377.04  4957.5  376.16  4971.9  376.23
  4976.5  375.95  4976.7  375.45  4980.2  375.45  4980.5  375.95  5013.9  375.98
  5120.5  377.73  5163.4  377.79  5248.0  378.83  5311.7  378.90  5338.3  379.44
#Mann=5,-1,0
  4507.2    0.05       0  4819.5    0.12       0  4971.9    0.05       0
  4976.5    0.04       0  4980.5    0.05       0
Bank Sta=4976.5,4980.5
Exp/Cntr=0.3,0.1

Type RM Length L Ch R = 1,2565,96,96,96
BEGIN DESCRIPTION:
Mapping XS 0a3713f9
END DESCRIPTION:
XS GIS Cut Line= 6
      2717000.79      6791744.95      2716999.38      6791487.30
      2717034.26      6791410.18      2717035.68      6791348.52
      2717004.46      6791306.67      2716740.52      6791007.73
#Sta/Elev= 30
  4492.6  379.77  4566.6  379.44  4606.6  379.68  4626.6  379.16  4686.6  378.66
  4752.8  377.51  4758.4  377.80  4775.2  377.56  4809.3  378.35  4824.6  378.11
  4854.2  378.26  4884.2  377.91  4893.0  378.31  4908.4  378.26  4960.9  377.40
  4966.2  377.34  4972.9  376.76  4980.4  376.79  5006.9  375.90  5007.1  375.40
  5010.6  375.40  5010.9  375.90  5072.4  376.97  5150.2  377.52  5192.9  378.25
  5235.6  378.25  5256.5  378.79  5270.7  378.43  5313.4  378.83  5347.7  379.59
#Mann=5,-1,0
  4492.6    0.05       0  4824.6    0.12       0  4960.9    0.05       0
  5006.9    0.04       0  5010.9    0.05       0
Bank Sta=5006.9,5010.9
Exp/Cntr=0.3,0.1

Type RM Length L Ch R = 1,2469,172,172,172
BEGIN DESCRIPTION:
Mapping XS d167e895
END DESCRIPTION:
XS GIS Cut Line= 3
      2717139.95      6791702.99      2717047.39      6791250.59
      2716847.49      6790922.10
#Sta/Elev= 30
  4578.8  379.07  4670.5  377.91  4693.1  378.42  4713.5  378.34  4733.9  379.02
  4776.5  378.32  4815.6  376.87  4846.2  376.93  4872.3  375.91  4877.4  376.08
  4889.7  375.75  4907.5  375.75  4938.1  372.63  4971.2  372.48  4971.5  371.98
  4975.0  371.98  4975.2  372.48  5002.9  375.01  5023.7  375.50  5049.4  375.33
  5092.0  375.78  5122.0  376.47  5128.8  377.00  5157.2  376.41  5202.4  376.21
  5260.6  376.62  5266.4  376.92  5309.3  376.79  5355.5  377.10  5425.1  377.93
#Mann=5,-1,0
  4578.8    0.05       0  4889.7    0.12       0  4971.2    0.07       0
  4975.2    0.12       0  5002.9    0.05       0
Bank Sta=4971.2,4975.2
Exp/Cntr=0.3,0.1

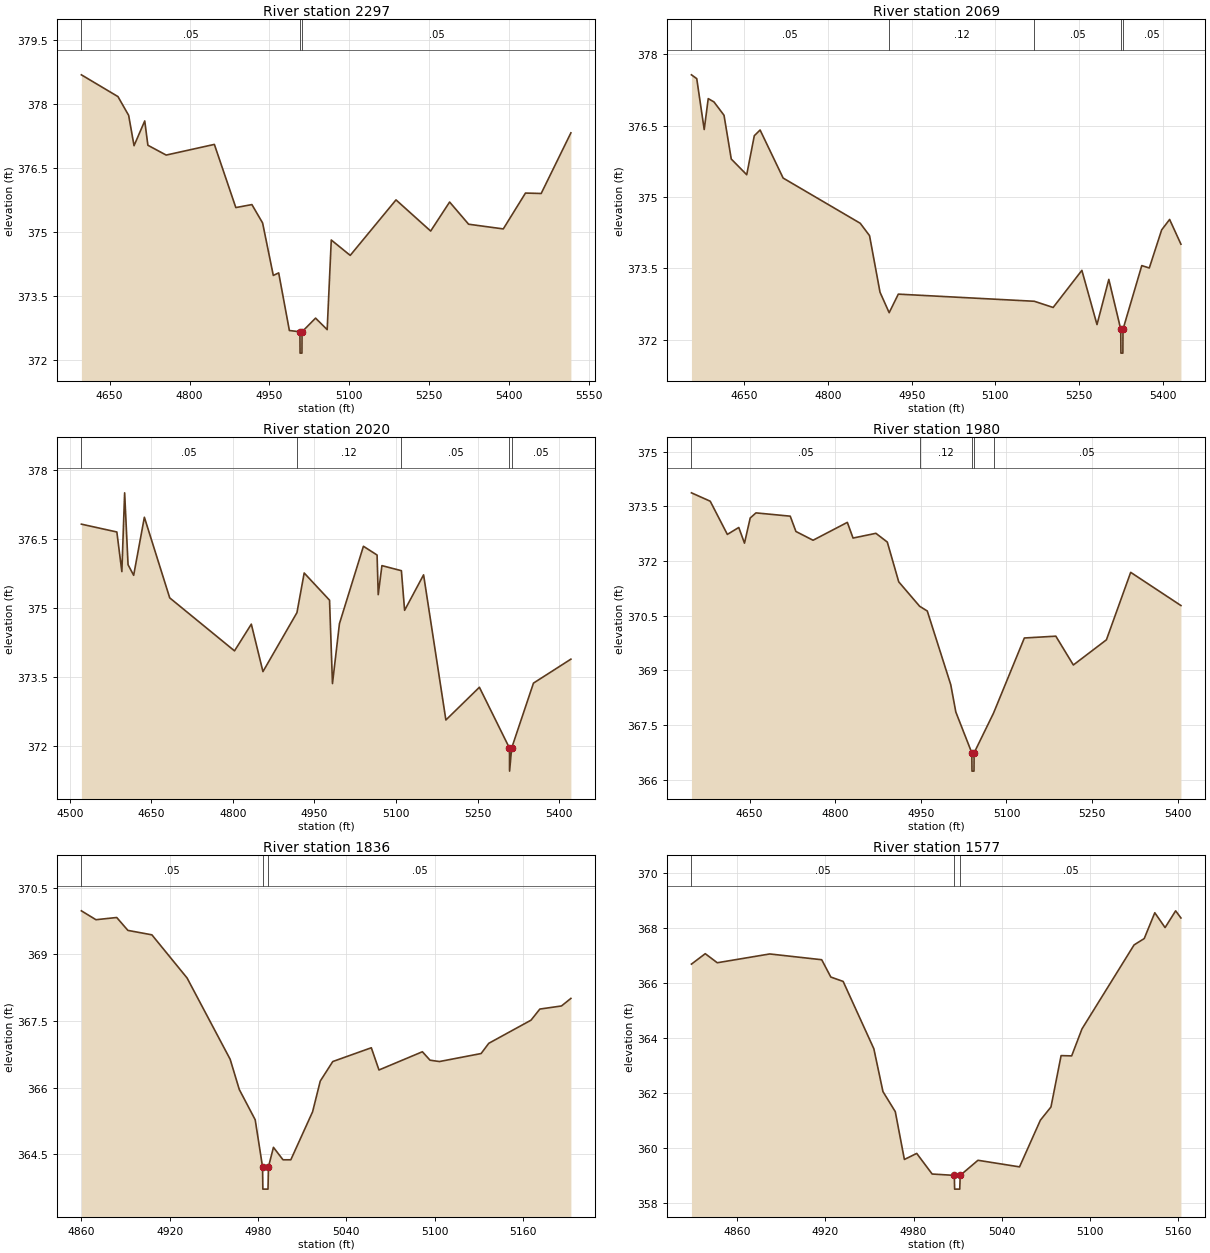
Type RM Length L Ch R = 1,2297,228,228,228
BEGIN DESCRIPTION:
Lynn Creek T 21 8.0
END DESCRIPTION:
XS GIS Cut Line= 3
      2717264.85      6791709.31      2717220.48      6791308.66
      2716919.88      6790888.77
#Sta/Elev= 30
  4596.9  378.68  4665.6  378.17  4685.7  377.73  4695.8  377.02  4715.9  377.60
  4721.8  377.03  4756.2  376.80  4846.7  377.05  4887.0  375.57  4917.2  375.64
  4937.3  375.21  4957.4  373.98  4967.5  374.04  4987.6  372.69  5007.4  372.66
  5007.7  372.16  5011.2  372.16  5011.4  372.66  5036.8  372.98  5058.6  372.71
  5066.3  374.81  5101.9  374.45  5187.9  375.75  5253.0  375.02  5288.6  375.70
  5324.3  375.18  5389.4  375.07  5431.1  375.91  5460.6  375.90  5516.4  377.32
#Mann=3,-1,0
  4596.9    0.05       0  5007.4    0.05       0  5011.4    0.05       0
Bank Sta=5007.4,5011.4
Exp/Cntr=0.3,0.1

Type RM Length L Ch R = 1,2069,49,49,49
BEGIN DESCRIPTION:
Mapping XS 49424180
END DESCRIPTION:
XS GIS Cut Line= 6
      2717285.81      6791630.16      2717381.15      6791260.02
      2717427.38      6791169.31      2717406.65      6791111.68
      2717314.48      6791088.77      2717188.07      6790891.89
#Sta/Elev= 30
  4555.2  377.57  4564.7  377.49  4578.1  376.42  4585.3  377.07  4595.6  377.00
  4613.6  376.72  4626.6  375.80  4654.3  375.47  4667.9  376.29  4678.3  376.41
  4719.6  375.40  4857.8  374.45  4874.5  374.19  4893.3  373.00  4909.7  372.57
  4926.1  372.96  5169.9  372.81  5203.7  372.68  5255.2  373.46  5282.3  372.32
  5303.5  373.27  5324.9  372.22  5325.2  371.72  5328.7  371.72  5328.9  372.22
  5362.6  373.56  5376.1  373.51  5398.2  374.31  5412.5  374.53  5432.8  374.01
#Mann=5,-1,0
  4555.2    0.05       0  4909.7    0.12       0  5169.9    0.05       0
  5324.9    0.07       0  5328.9    0.05       0
Bank Sta=5324.9,5328.9
Exp/Cntr=0.3,0.1

Type RM Length L Ch R = 1,2020,40,40,40
BEGIN DESCRIPTION:
Mapping XS 66993c6a
END DESCRIPTION:
XS GIS Cut Line= 6
      2717312.19      6791634.27      2717390.09      6791319.11
      2717458.78      6791147.52      2717417.74      6791077.30
      2717324.06      6791056.09      2717210.71      6790882.54
#Sta/Elev= 30
  4521.5  376.82  4586.7  376.65  4595.9  375.79  4601.0  377.50  4607.3  375.94
  4617.6  375.71  4637.3  376.97  4683.9  375.22  4803.0  374.07  4833.9  374.65
  4855.3  373.62  4917.8  374.90  4931.1  375.76  4977.7  375.17  4983.1  373.36
  4995.9  374.66  5040.0  376.34  5065.1  376.15  5067.2  375.29  5074.0  375.92
  5109.8  375.81  5115.7  374.95  5150.6  375.72  5191.6  372.57  5253.2  373.28
  5308.5  371.96  5308.7  371.46  5312.5  371.96  5352.6  373.37  5421.4  373.89
#Mann=5,-1,0
  4521.5    0.05       0  4917.8    0.12       0  5109.8    0.05       0
  5308.5    0.07       0  5312.5    0.05       0
Bank Sta=5308.5,5312.5
Exp/Cntr=0.3,0.1

Type RM Length L Ch R = 1,1980,144,144,144
BEGIN DESCRIPTION:
Mapping XS ba3d72c8
END DESCRIPTION:
XS GIS Cut Line= 4
      2717483.33      6791613.93      2717490.78      6791163.84
      2717487.42      6790990.59      2717364.00      6790792.06
#Sta/Elev= 30
  4548.3  373.87  4581.2  373.64  4611.2  372.73  4631.2  372.92  4641.2  372.49
  4651.2  373.18  4661.3  373.32  4721.3  373.23  4731.3  372.81  4761.3  372.57
  4821.3  373.06  4831.3  372.63  4871.3  372.76  4891.3  372.52  4911.3  371.43
  4947.9  370.76  4961.3  370.63  5002.4  368.61  5011.3  367.86  5039.3  366.74
  5039.6  366.24  5043.1  366.24  5043.3  366.74  5077.3  367.83  5131.3  369.89
  5186.4  369.94  5217.1  369.15  5275.0  369.84  5317.5  371.69  5405.5  370.78
#Mann=5,-1,0
  4548.3    0.05       0  4947.9    0.12       0  5039.3    0.07       0
  5043.3    0.12       0  5077.3    0.05       0
Bank Sta=5039.3,5043.3
Exp/Cntr=0.3,0.1

Type RM Length L Ch R = 1,1836,259,259,259
BEGIN DESCRIPTION:
Lynn Creek T 21 7.0
END DESCRIPTION:
XS GIS Cut Line= 3
      2717629.32      6791190.17      2717576.00      6791061.00
      2717525.72      6790874.81
#Sta/Elev= 30
  4860.0  369.98  4869.9  369.78  4884.0  369.83  4891.6  369.54  4907.9  369.44
  4931.8  368.47  4961.1  366.64  4967.3  365.96  4978.1  365.28  4983.1  364.22
  4983.3  363.72  4986.8  363.72  4987.1  364.22  4990.5  364.66  4997.0  364.38
  5002.3  364.38  5017.1  365.46  5022.3  366.15  5030.8  366.59  5057.0  366.90
  5062.2  366.40  5091.7  366.81  5096.9  366.62  5103.3  366.59  5131.6  366.77
  5136.8  367.00  5165.5  367.52  5171.5  367.77  5186.2  367.84  5192.6  368.01
#Mann=3,-1,0
  4860.0    0.05       0  4983.1    0.03       0  4987.1    0.05       0
Bank Sta=4983.1,4987.1
Exp/Cntr=0.3,0.1

Type RM Length L Ch R = 1,1577,280,280,280
BEGIN DESCRIPTION:
Lynn Creek T 21 6.0
END DESCRIPTION:
XS GIS Cut Line= 3
      2717875.41      6791045.14      2717776.00      6790911.00
      2717660.79      6790791.02
#Sta/Elev= 30
  4828.8  366.68  4838.2  367.06  4846.4  366.73  4882.1  367.05  4917.5  366.84
  4923.7  366.21  4932.1  366.05  4953.0  363.60  4959.2  362.04  4967.6  361.31
  4973.8  359.57  4982.2  359.79  4992.7  359.04  5007.8  358.99  5008.0  358.49
  5011.5  358.49  5011.8  358.99  5023.9  359.54  5052.2  359.30  5066.4  361.00
  5073.6  361.48  5080.5  363.35  5087.7  363.34  5094.7  364.32  5130.2  367.38
  5137.1  367.61  5144.3  368.55  5151.3  368.01  5158.5  368.62  5162.1  368.36
#Mann=3,-1,0
  4828.8    0.05       0  5007.8    0.04       0  5011.8    0.05       0
Bank Sta=5007.8,5011.8
Exp/Cntr=0.3,0.1

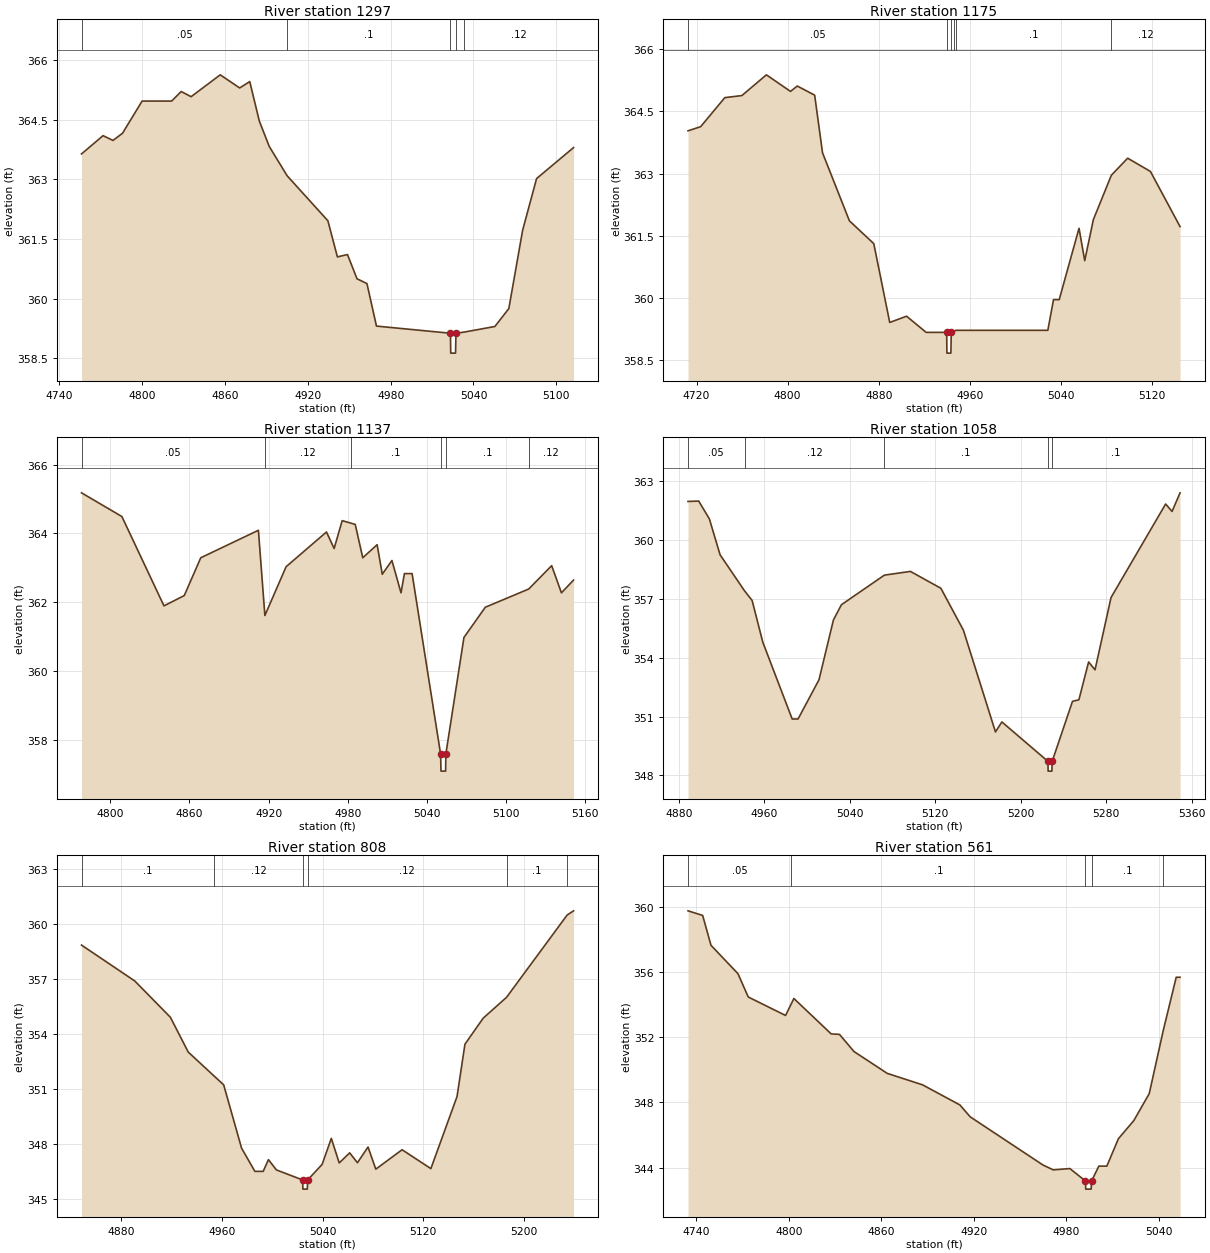
Type RM Length L Ch R = 1,1297,122,122,122
BEGIN DESCRIPTION:
Lynn Creek T 21 5.0
END DESCRIPTION:
XS GIS Cut Line= 3
      2718047.85      6790841.33      2717876.00      6790661.00
      2717769.43      6790647.68
#Sta/Elev= 30
  4756.0  363.64  4771.6  364.10  4778.8  363.98  4785.7  364.16  4799.9  364.97
  4821.3  364.97  4828.2  365.21  4835.4  365.08  4856.5  365.63  4870.6  365.30
  4877.9  365.46  4884.8  364.47  4892.0  363.83  4905.0  363.09  4934.5  361.96
  4941.4  361.05  4948.7  361.11  4955.6  360.50  4962.8  360.38  4969.7  359.31
  5023.3  359.13  5023.5  358.63  5027.0  358.63  5027.3  359.13  5033.4  359.16
  5055.5  359.30  5065.6  359.75  5075.6  361.72  5085.7  363.02  5112.5  363.80
#Mann=5,-1,0
  4756.0    0.05       0  4905.0     0.1       0  5023.3    0.07       0
  5027.3     0.1       0  5033.4    0.12       0
Bank Sta=5023.3,5027.3
Exp/Cntr=0.3,0.1

Type RM Length L Ch R = 1,1175,38,38,38
BEGIN DESCRIPTION:
Mapping XS ac557ec7
END DESCRIPTION:
XS GIS Cut Line= 6
      2718049.54      6790811.11      2717948.80      6790650.34
      2717948.25      6790578.45      2717926.77      6790552.85
      2717900.98      6790554.85      2717790.01      6790560.01
#Sta/Elev= 30
  4712.5  364.03  4723.6  364.13  4744.8  364.83  4759.8  364.88  4781.3  365.38
  4802.5  364.98  4808.4  365.11  4823.7  364.89  4830.6  363.50  4854.2  361.86
  4875.6  361.31  4889.6  359.41  4904.4  359.56  4921.6  359.17  4939.6  359.17
  4939.8  358.67  4943.3  358.67  4943.6  359.17  4946.3  359.20  4947.7  359.22
  5028.4  359.22  5033.4  359.96  5038.4  359.96  5055.8  361.68  5060.8  360.90
  5068.4  361.89  5084.2  362.96  5098.5  363.37  5118.5  363.05  5144.5  361.72
#Mann=6,-1,0
  4712.5    0.05       0  4939.6    0.07       0  4943.6    0.05       0
  4946.3    0.12       0  4947.7     0.1       0  5084.2    0.12       0
Bank Sta=4939.6,4943.6
Exp/Cntr=0.3,0.1

Type RM Length L Ch R = 1,1137,79,79,79
BEGIN DESCRIPTION:
Mapping XS e4d2175f
END DESCRIPTION:
XS GIS Cut Line= 6
      2718021.05      6790738.56      2717985.48      6790654.65
      2717956.70      6790531.03      2717937.27      6790512.39
      2717879.48      6790498.07      2717821.42      6790529.61
#Sta/Elev= 30
  4778.2  365.18  4808.8  364.49  4840.7  361.89  4856.1  362.19  4868.6  363.29
  4912.3  364.09  4917.2  361.61  4933.3  363.03  4963.9  364.04  4969.7  363.56
  4975.8  364.37  4982.2  364.30  4985.7  364.26  4991.4  363.29  5002.3  363.67
  5006.2  362.81  5013.5  363.21  5020.4  362.27  5023.0  362.83  5028.8  362.83
  5050.4  357.58  5050.7  357.08  5054.2  357.08  5054.4  357.58  5068.1  360.97
  5084.3  361.85  5117.2  362.38  5134.6  363.06  5142.0  362.27  5151.2  362.64
#Mann=6,-1,0
  4778.2    0.05       0  4917.2    0.12       0  4982.2     0.1       0
  5050.4    0.07       0  5054.4     0.1       0  5117.2    0.12       0
Bank Sta=5050.4,5054.4
Exp/Cntr=0.3,0.1

Type RM Length L Ch R = 1,1058,250,250,250
BEGIN DESCRIPTION:
Lynn Creek T 21 4.0
END DESCRIPTION:
XS GIS Cut Line= 3
      2718026.00      6790661.03      2718026.00      6790561.00
      2717825.99      6790260.99
#Sta/Elev= 30
  4888.6  361.98  4898.6  362.00  4908.6  361.09  4918.6  359.26  4941.5  357.42
  4948.6  356.93  4958.6  354.80  4986.1  350.88  4991.6  350.88  5011.2  352.88
  5024.7  355.93  5032.2  356.71  5072.4  358.22  5096.8  358.41  5125.3  357.55
  5146.4  355.41  5176.4  350.22  5182.4  350.73  5225.5  348.72  5225.7  348.22
  5229.2  348.22  5229.5  348.72  5248.5  351.78  5254.5  351.86  5263.6  353.79
  5269.6  353.39  5284.6  357.08  5335.7  361.85  5341.7  361.47  5349.2  362.42
#Mann=5,-1,0
  4888.6    0.05       0  4941.5    0.12       0  5072.4     0.1       0
  5225.5    0.07       0  5229.5     0.1       0
Bank Sta=5225.5,5229.5
Exp/Cntr=0.3,0.1

Type RM Length L Ch R = 1,808,247,247,247
BEGIN DESCRIPTION:
Lynn Creek T 21 3.0
END DESCRIPTION:
XS GIS Cut Line= 3
      2718226.00      6790461.00      2718126.00      6790361.00
      2717926.02      6790211.01
#Sta/Elev= 30
  4848.3  358.86  4890.7  356.90  4919.0  354.92  4933.2  353.02  4954.0  351.70
  4961.4  351.23  4975.6  347.78  4986.2  346.51  4992.8  346.51  4997.0  347.15
  5003.3  346.59  5024.2  346.04  5024.4  345.54  5027.9  345.54  5028.2  346.04
  5039.7  346.89  5047.0  348.31  5053.3  346.97  5061.6  347.52  5067.8  346.98
  5076.2  347.84  5082.4  346.63  5103.3  347.69  5126.2  346.66  5147.0  350.59
  5153.3  353.45  5167.8  354.87  5186.4  356.01  5234.6  360.50  5239.7  360.73
#Mann=6,-1,0
  4848.3     0.1       0  4954.0    0.12       0  5024.2    0.07       0
  5028.2    0.12       0  5186.4     0.1       0  5234.6    0.05       0
Bank Sta=5024.2,5028.2
Exp/Cntr=0.3,0.1

Type RM Length L Ch R = 1,561,242,242,242
BEGIN DESCRIPTION:
Lynn Creek T 21 2.0
END DESCRIPTION:
XS GIS Cut Line= 3
      2718276.02      6790411.04      2718176.00      6790161.00
      2718176.00      6790111.00
#Sta/Elev= 30
  4734.6  359.74  4744.1  359.46  4749.5  357.63  4767.0  355.89  4773.7  354.46
  4797.9  353.33  4801.7  354.06  4803.3  354.37  4827.5  352.20  4832.9  352.17
  4842.3  351.12  4863.9  349.78  4886.8  349.08  4911.0  347.85  4917.7  347.12
  4964.9  344.17  4971.6  343.87  4982.4  343.95  4992.5  343.19  4992.7  342.69
  4996.2  342.69  4996.5  343.19  5001.2  344.10  5006.4  344.10  5013.9  345.78
  5023.9  346.89  5033.9  348.54  5042.9  352.37  5051.4  355.67  5053.9  355.67
#Mann=5,-1,0
  4734.6    0.05       0  4801.7     0.1       0  4992.5    0.07       0
  4996.5     0.1       0  5042.9    0.05       0
Bank Sta=4992.5,4996.5
Exp/Cntr=0.3,0.1

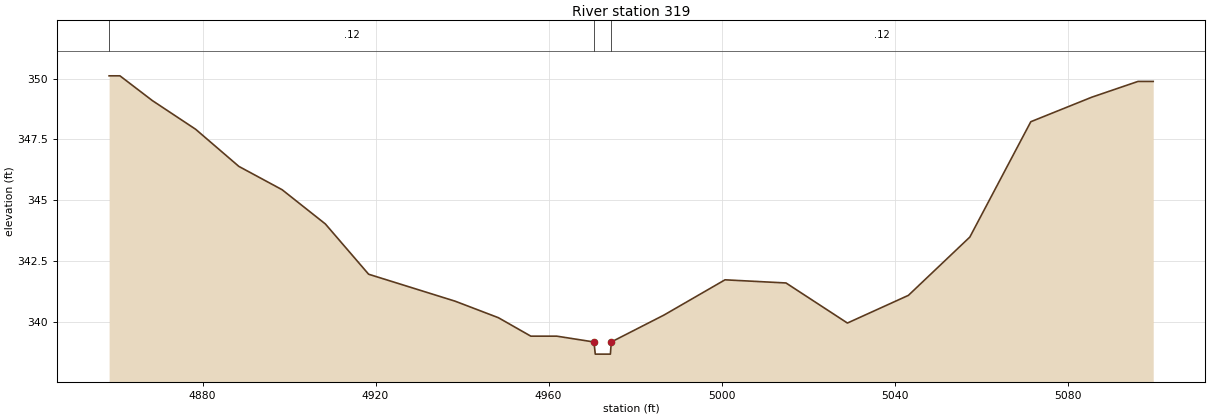
Type RM Length L Ch R = 1,319,0,0,0
BEGIN DESCRIPTION:
Lynn Creek T 21 1.0
END DESCRIPTION:
XS GIS Cut Line= 3
      2718426.00      6790260.97      2718426.00      6790161.00
      2718325.99      6790060.99
#Sta/Elev= 27
  4858.4  350.12  4860.9  350.12  4868.4  349.10  4878.4  347.92  4888.4  346.39
  4898.4  345.43  4908.4  344.02  4918.4  341.95  4938.4  340.84  4948.4  340.16
  4955.9  339.40  4958.4  339.40  4961.9  339.40  4970.5  339.16  4970.8  338.66
  4974.3  338.66  4974.5  339.16  4986.7  340.27  5000.8  341.72  5014.9  341.59
  5029.1  339.94  5043.2  341.08  5057.4  343.48  5071.5  348.23  5085.6  349.24
  5096.3  349.89  5099.8  349.89
#Mann=3,-1,0
  4858.4    0.12       0  4970.5    0.07       0  4974.5    0.12       0
Bank Sta=4970.5,4974.5
Exp/Cntr=0.3,0.1

Chan Stop Cuts=-1