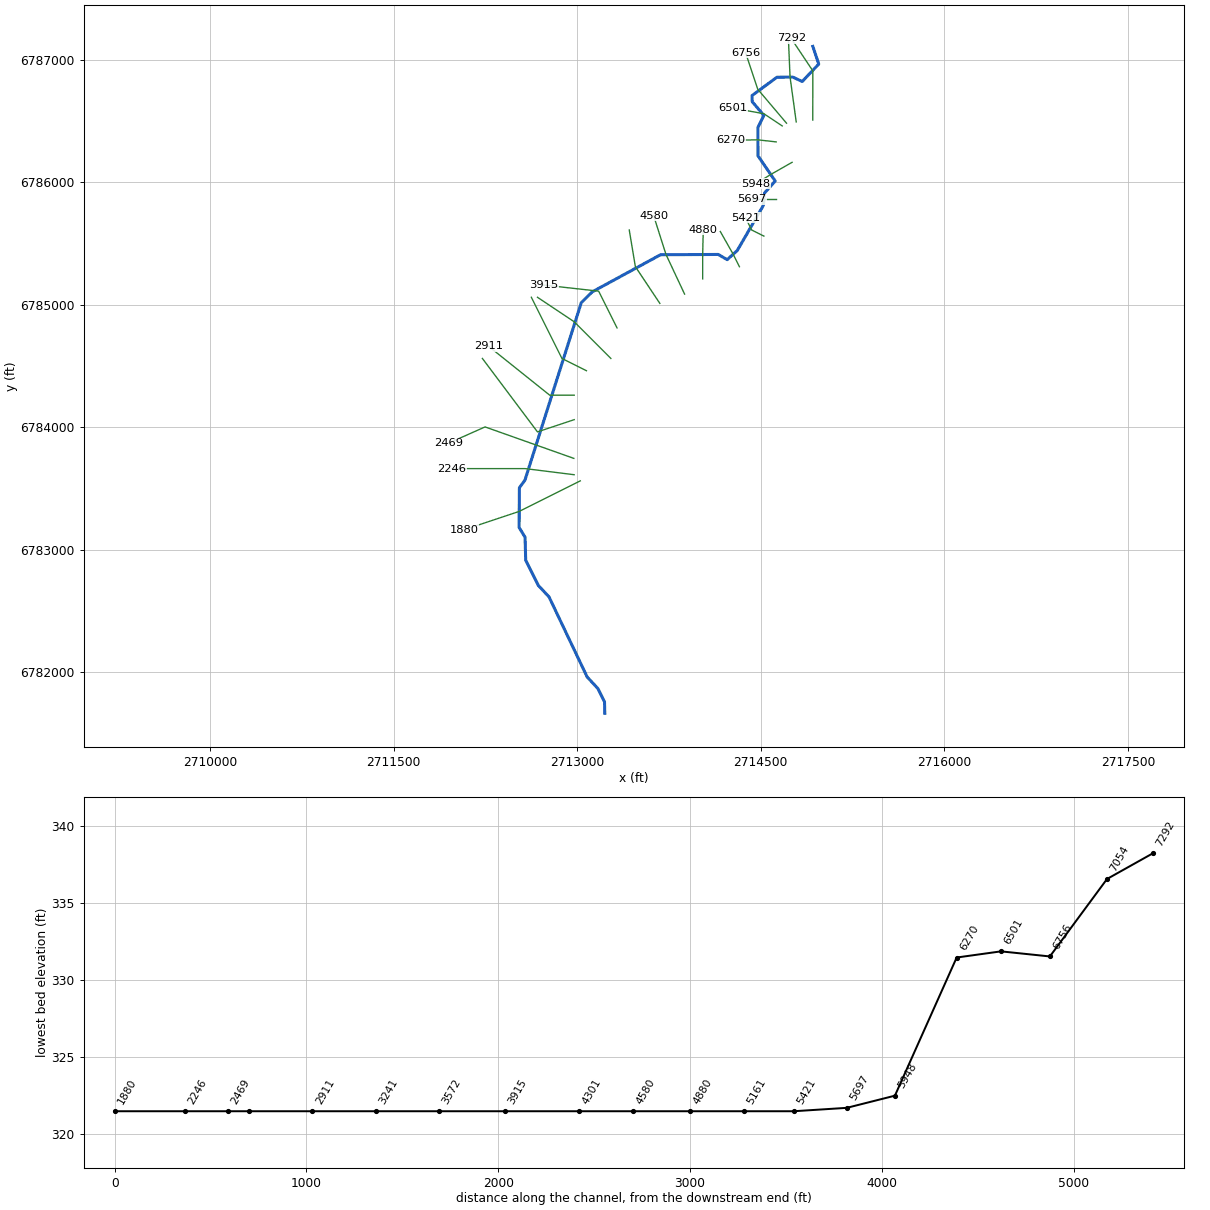
--- Lynn Creek T 22.prj (project) ---

Proj Title=Lynn Creek T 22 Base Level Engineering
Current Plan=p01
Default Exp/Contr=0.3,0.1
English Units
Geom File=g01
Flow File=f01
Plan File=p01
BEGIN DESCRIPTION:
Lynn Creek T 22
END DESCRIPTION:

--- Lynn Creek T 22.p01 (plan) ---

Plan Title=Multiple Run
Short Identifier=Multiple
Geom File=g01
Flow File=f01
Subcritical Flow
K Sum by GR= 0
Std Step Tol= 0.01
Critical Tol= 0.01
Num of Std Step Trials= 20
Max Error Tol= 0.3
Flow Tol Ratio= 0.001
Split Flow NTrial= 30
Split Flow Tol= 0.02
Split Flow Ratio= 0.02
Log Output Level= 0
Friction Slope Method= 1
Unsteady Friction Slope Method= 2
Unsteady Bridges Friction Slope Method= 1
Parabolic Critical Depth
Global Vel Dist=  1 , 1 , 1
Global Log Level= 0
CheckData=True
Encroach Param= -1, 0, 0, 0
BEGIN DESCRIPTION:
Multiple Run
END DESCRIPTION:

--- Lynn Creek T 22.f01 (steady flow) ---

Flow Title=Multiple
Number of Profiles=7
Profile Names=10-year,25-year,50-year,1pct_min,100-year,1pct_plu,500-year
River Rch & RM= Lynn Creek T 22,Reach-1,7292
     398     522     619     365     729    1454    1008
River Rch & RM= Lynn Creek T 22,Reach-1,3915
     669     901    1088     652    1301    2596    1858
Boundary for River Rch & Prof#=Lynn Creek T 22,Reach-1,1
Up Type=0
Dn Type=3
Dn Slope=0.005
Boundary for River Rch & Prof#=Lynn Creek T 22,Reach-1,2
Up Type=0
Dn Type=3
Dn Slope=0.005
Boundary for River Rch & Prof#=Lynn Creek T 22,Reach-1,3
Up Type=0
Dn Type=3
Dn Slope=0.005
Boundary for River Rch & Prof#=Lynn Creek T 22,Reach-1,4
Up Type=0
Dn Type=3
Dn Slope=0.005
Boundary for River Rch & Prof#=Lynn Creek T 22,Reach-1,5
Up Type=0
Dn Type=3
Dn Slope=0.005
Boundary for River Rch & Prof#=Lynn Creek T 22,Reach-1,6
Up Type=0
Dn Type=3
Dn Slope=0.005
Boundary for River Rch & Prof#=Lynn Creek T 22,Reach-1,7
Up Type=0
Dn Type=3
Dn Slope=0.005

--- Lynn Creek T 22.g01 (geometry) ---

Geom Title=Existing Conditions

River Reach=Lynn Creek T 22,Reach-1
Reach XY= 30
      2714926.00      6787111.00      2714974.29      6786966.62
      2714839.38      6786824.53      2714762.14      6786860.18
      2714631.93      6786858.77      2714429.09      6786709.36
      2714431.08      6786658.72      2714525.90      6786546.96
      2714476.70      6786447.09      2714478.18      6786216.45
      2714618.70      6786010.92      2714531.55      6785913.43
      2714522.17      6785812.59      2714309.35      6785444.26
      2714226.11      6785368.31      2714153.35      6785410.99
      2713681.52      6785408.65      2713123.64      6785105.29
      2713033.85      6785017.19      2712573.64      6783566.98
      2712528.26      6783505.06      2712526.21      6783179.27
      2712574.78      6783100.49      2712579.75      6782912.55
      2712684.16      6782704.95      2712770.15      6782613.29
      2713081.85      6781958.71      2713170.16      6781863.29
      2713223.81      6781755.55      2713226.00      6781661.00

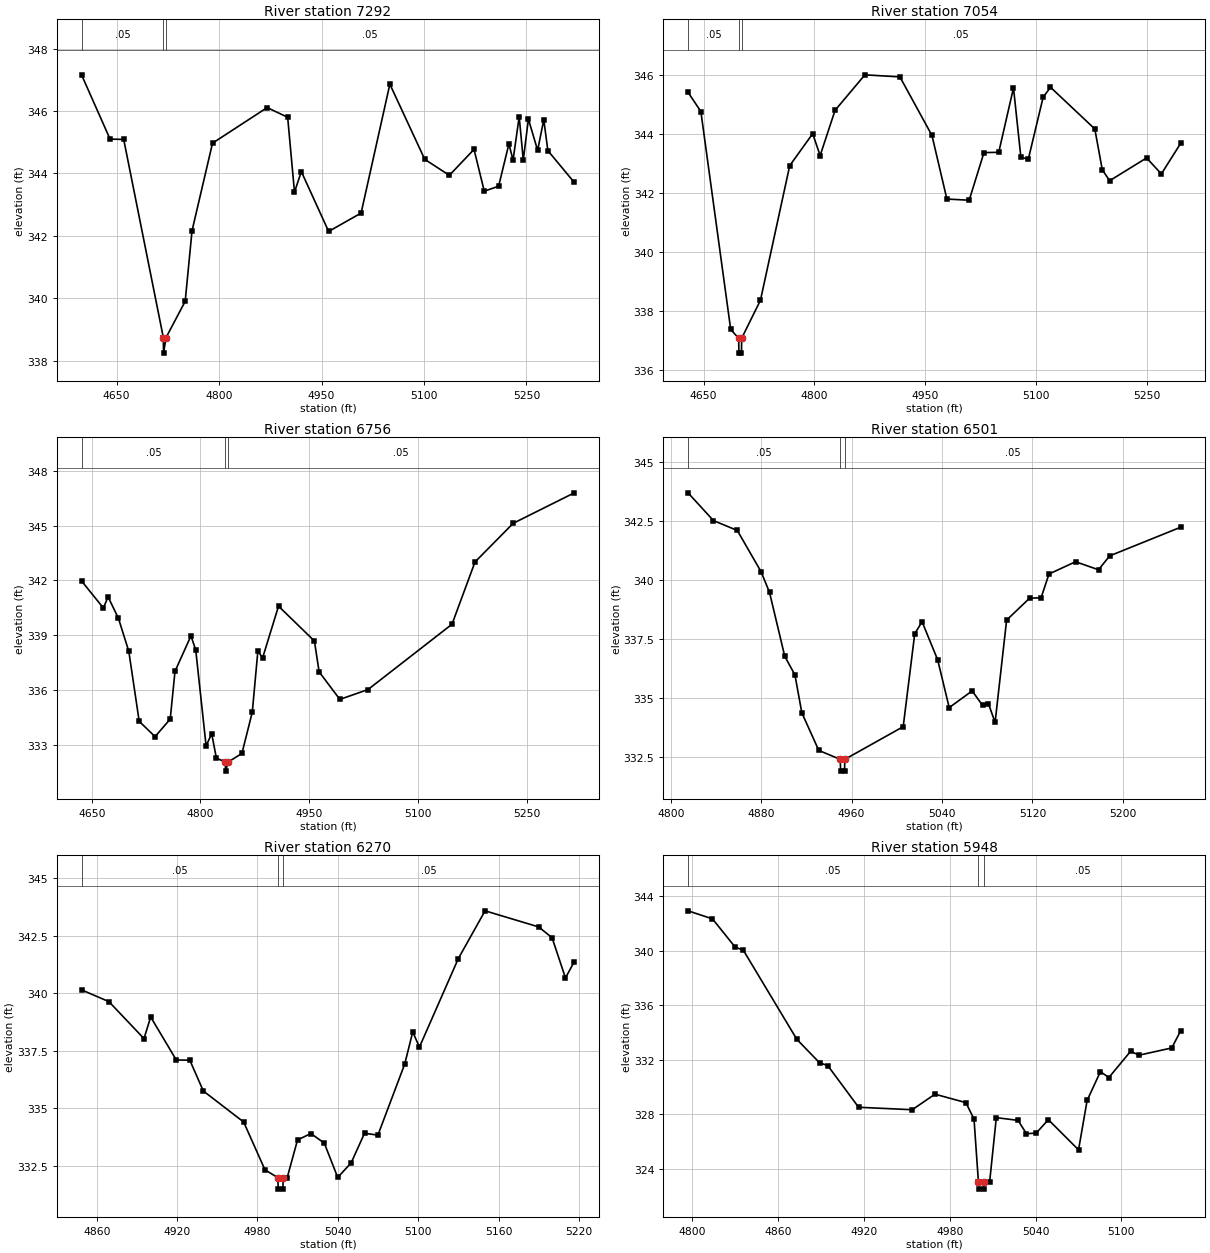
Type RM Length L Ch R = 1,7292,238,238,238
BEGIN DESCRIPTION:
Lynn Creek T 22 19.0
END DESCRIPTION:
XS GIS Cut Line= 3
      2714925.47      6786509.29      2714926.00      6786911.00
      2714748.73      6787176.93
#Sta/Elev= 30
  4598.7  347.16  4640.4  345.10  4660.4  345.09  4718.4  338.74  4718.7  338.24
  4722.4  338.74  4750.4  339.90  4760.4  342.16  4790.4  344.97  4870.4  346.11
  4900.4  345.80  4910.4  343.40  4920.4  344.06  4960.4  342.14  5007.9  342.73
  5050.0  346.86  5101.1  344.45  5137.1  343.94  5173.2  344.77  5188.2  343.43
  5209.2  343.59  5224.3  344.95  5230.3  344.42  5239.3  345.82  5245.3  344.43
  5252.8  345.74  5266.3  344.74  5275.3  345.72  5281.3  344.73  5320.0  343.71
#Mann=3,-1,0
  4598.7    0.05       0  4718.4    0.05       0  4722.4    0.05       0
Bank Sta=4718.4,4722.4
Exp/Cntr=0.3,0.1

Type RM Length L Ch R = 1,7054,298,298,298
BEGIN DESCRIPTION:
Lynn Creek T 22 18.0
END DESCRIPTION:
XS GIS Cut Line= 3
      2714790.29      6786493.77      2714739.83      6786861.42
      2714727.11      6787157.25
#Sta/Elev= 30
  4628.9  345.40  4646.3  344.75  4686.7  337.38  4697.5  337.08  4697.8  336.58
  4701.3  336.58  4701.5  337.08  4727.0  338.37  4766.6  342.92  4797.7  344.00
  4807.8  343.26  4828.0  344.79  4868.4  345.99  4915.8  345.92  4959.2  343.94
  4979.4  341.79  5009.6  341.75  5029.6  343.36  5049.6  343.37  5069.6  345.55
  5079.6  343.20  5089.7  343.14  5109.7  345.23  5119.7  345.57  5179.7  344.16
  5189.8  342.78  5199.8  342.41  5249.8  343.18  5269.8  342.64  5296.1  343.68
#Mann=3,-1,0
  4628.9    0.05       0  4697.5    0.05       0  4701.5    0.05       0
Bank Sta=4697.5,4701.5
Exp/Cntr=0.3,0.1

Type RM Length L Ch R = 1,6756,255,255,255
BEGIN DESCRIPTION:
Lynn Creek T 22 17.0
END DESCRIPTION:
XS GIS Cut Line= 3
      2714710.90      6786483.63      2714476.00      6786761.00
      2714376.00      6787061.00
#Sta/Elev= 30
  4636.0  341.97  4666.1  340.49  4672.6  341.10  4686.9  339.92  4701.2  338.11
  4715.5  334.28  4737.4  333.44  4758.3  334.40  4764.9  337.02  4786.9  338.96
  4793.5  338.19  4807.8  332.93  4815.5  333.60  4822.0  332.26  4834.3  332.05
  4834.6  331.55  4838.3  332.05  4857.2  332.52  4871.5  334.78  4879.2  338.13
  4885.8  337.76  4907.7  340.59  4957.2  338.68  4963.7  336.99  4992.3  335.48
  5031.1  336.02  5147.0  339.60  5178.7  343.01  5231.4  345.13  5315.7  346.80
#Mann=3,-1,0
  4636.0    0.05       0  4834.3    0.05       0  4838.3    0.05       0
Bank Sta=4834.3,4838.3
Exp/Cntr=0.3,0.1

Type RM Length L Ch R = 1,6501,231,231,231
BEGIN DESCRIPTION:
Lynn Creek T 22 16.0
END DESCRIPTION:
XS GIS Cut Line= 4
      2714676.00      6786461.00      2714609.21      6786505.53
      2714526.00      6786561.00      2714274.32      6786606.30
#Sta/Elev= 30
  4815.3  343.71  4837.8  342.53  4858.9  342.11  4879.9  340.36  4887.4  339.48
  4900.9  336.76  4909.9  335.97  4916.0  334.36  4931.0  332.76  4950.0  332.38
  4950.3  331.88  4953.8  331.88  4954.0  332.38  5005.7  333.77  5015.9  337.72
  5022.4  338.23  5036.2  336.61  5046.4  334.58  5066.7  335.29  5076.0  334.67
  5081.1  334.75  5087.0  333.95  5097.2  338.30  5117.5  339.23  5127.7  339.25
  5134.7  340.26  5158.2  340.78  5178.5  340.44  5188.4  341.03  5251.3  342.25
#Mann=3,-1,0
  4815.3    0.05       0  4950.0    0.03       0  4954.0    0.05       0
Bank Sta=4950,4954
Exp/Cntr=0.3,0.1

Type RM Length L Ch R = 1,6270,322,322,322
BEGIN DESCRIPTION:
Lynn Creek T 22 15.0
END DESCRIPTION:
XS GIS Cut Line= 3
      2714626.29      6786330.71      2714476.41      6786347.47
      2714259.45      6786344.20
#Sta/Elev= 30
  4848.7  340.15  4869.1  339.64  4895.3  338.03  4900.3  338.97  4919.4  337.10
  4929.5  337.09  4939.6  335.75  4969.7  334.40  4985.6  332.32  4995.2  331.98
  4995.5  331.48  4999.0  331.48  4999.2  331.98  5002.2  331.98  5009.9  333.62
  5019.9  333.90  5029.9  333.48  5039.9  331.99  5049.9  332.62  5059.9  333.91
  5069.9  333.83  5089.9  336.92  5095.9  338.32  5100.9  337.66  5129.9  341.51
  5149.9  343.59  5189.9  342.89  5199.9  342.42  5209.9  340.67  5216.5  341.38
#Mann=3,-1,0
  4848.7    0.05       0  4995.2    0.03       0  4999.2    0.05       0
Bank Sta=4995.2,4999.2
Exp/Cntr=0.3,0.1

Type RM Length L Ch R = 1,5948,251,251,251
BEGIN DESCRIPTION:
Lynn Creek T 22 14.0
END DESCRIPTION:
XS GIS Cut Line= 3
      2714756.65      6786163.99      2714576.00      6786061.00
      2714460.73      6785987.60
#Sta/Elev= 30
  4796.9  342.91  4814.0  342.32  4829.8  340.26  4835.6  340.02  4873.0  333.49
  4888.9  331.77  4894.6  331.57  4916.2  328.51  4953.7  328.33  4969.6  329.47
  4991.2  328.85  4996.9  327.65  5000.0  323.01  5000.2  322.51  5003.7  322.51
  5004.0  323.01  5007.8  323.01  5012.5  327.75  5027.7  327.55  5033.6  326.57
  5040.4  326.62  5048.9  327.60  5070.0  325.39  5076.0  329.01  5085.3  331.12
  5091.2  330.69  5106.4  332.61  5112.4  332.33  5135.2  332.86  5141.5  334.13
#Mann=3,-1,0
  4796.9    0.05       0  5000.0    0.03       0  5004.0    0.05       0
Bank Sta=5000,5004
Exp/Cntr=0.3,0.1

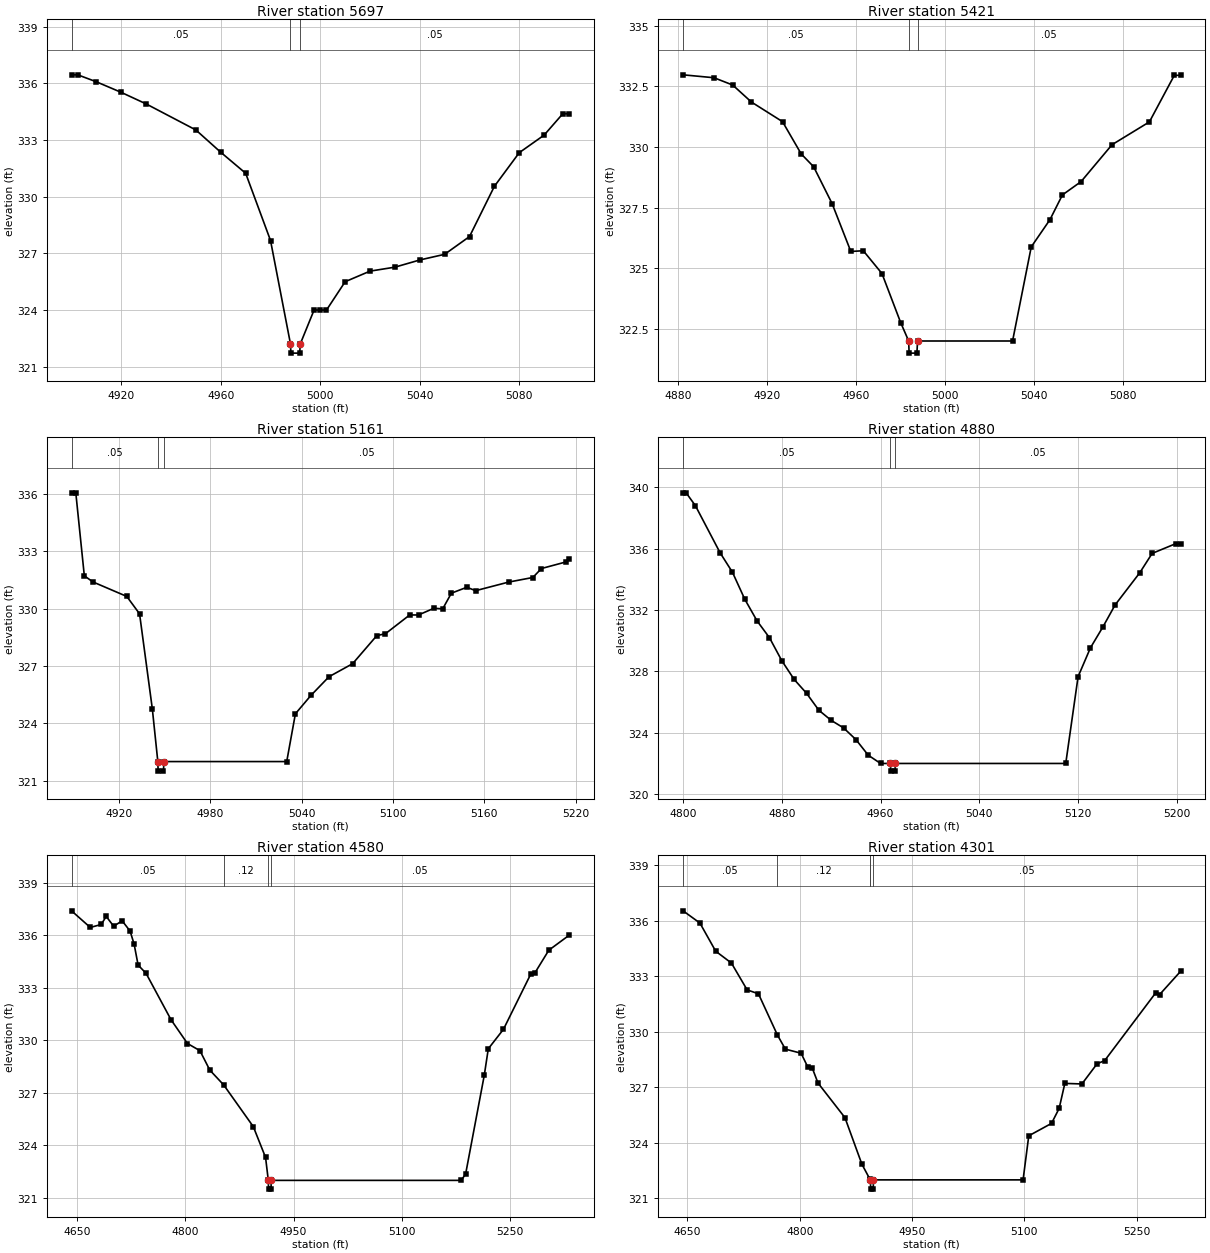
Type RM Length L Ch R = 1,5697,276,276,276
BEGIN DESCRIPTION:
Lynn Creek T 22 13.0
END DESCRIPTION:
XS GIS Cut Line= 3
      2714625.96      6785861.00      2714526.00      6785861.00
      2714425.96      6785861.00
#Sta/Elev= 27
  4900.0  336.45  4902.5  336.45  4910.0  336.08  4920.0  335.52  4930.0  334.91
  4950.0  333.53  4960.0  332.35  4970.0  331.24  4980.0  327.68  4988.0  322.22
  4988.2  321.72  4991.7  321.72  4992.0  322.22  4997.5  324.00  5000.0  324.00
  5002.5  324.00  5010.0  325.50  5020.0  326.06  5030.0  326.27  5040.0  326.65
  5050.0  326.95  5060.0  327.89  5070.0  330.55  5080.0  332.33  5090.0  333.26
  5097.5  334.39  5100.0  334.39
#Mann=3,-1,0
  4900.0    0.05       0  4988.0    0.03       0  4992.0    0.05       0
Bank Sta=4988,4992
Exp/Cntr=0.3,0.1

Type RM Length L Ch R = 1,5421,260,260,260
BEGIN DESCRIPTION:
Lynn Creek T 22 12.0
END DESCRIPTION:
XS GIS Cut Line= 3
      2714525.97      6785561.02      2714426.00      6785611.00
      2714375.99      6785711.02
#Sta/Elev= 25
  4882.2  332.97  4896.1  332.85  4904.5  332.55  4912.9  331.85  4926.9  331.04
  4935.3  329.71  4940.9  329.18  4949.2  327.66  4957.6  325.69  4963.2  325.72
  4971.6  324.78  4980.0  322.76  4983.6  322.00  4983.8  321.50  4987.3  321.50
  4987.6  322.00  5030.3  322.00  5038.7  325.88  5047.1  327.00  5052.7  328.02
  5061.1  328.57  5075.0  330.09  5091.8  331.03  5103.0  332.95  5105.8  332.95
#Mann=3,-1,0
  4882.2    0.05       0  4983.6    0.05       0  4987.6    0.05       0
Bank Sta=4983.6,4987.6
Exp/Cntr=0.3,0.1

Type RM Length L Ch R = 1,5161,281,281,281
BEGIN DESCRIPTION:
Lynn Creek T 22 11.0
END DESCRIPTION:
XS GIS Cut Line= 3
      2714325.99      6785311.02      2714276.00      6785411.00
      2714170.12      6785598.25
#Sta/Elev= 30
  4888.8  336.06  4891.6  336.06  4897.2  331.72  4902.8  331.40  4925.1  330.64
  4933.5  329.73  4941.9  324.75  4945.5  322.00  4945.7  321.50  4949.2  321.50
  4949.5  322.00  5030.2  322.00  5035.9  324.50  5046.1  325.46  5058.0  326.44
  5073.5  327.12  5089.4  328.59  5095.1  328.69  5111.0  329.67  5116.8  329.67
  5126.9  330.02  5132.7  329.99  5138.4  330.81  5148.6  331.12  5154.3  330.94
  5176.0  331.39  5191.9  331.63  5197.6  332.10  5213.5  332.44  5215.7  332.62
#Mann=3,-1,0
  4888.8    0.05       0  4945.5    0.05       0  4949.5    0.05       0
Bank Sta=4945.5,4949.5
Exp/Cntr=0.3,0.1

Type RM Length L Ch R = 1,4880,300,300,300
BEGIN DESCRIPTION:
Lynn Creek T 22 10.0
END DESCRIPTION:
XS GIS Cut Line= 3
      2714026.00      6785211.03      2714026.00      6785411.00
      2714030.60      6785613.98
#Sta/Elev= 30
  4800.0  339.65  4802.5  339.65  4810.0  338.81  4830.0  335.74  4840.0  334.47
  4850.0  332.71  4860.0  331.29  4870.0  330.20  4880.0  328.70  4890.0  327.48
  4900.0  326.58  4910.0  325.47  4920.0  324.81  4930.0  324.32  4940.0  323.56
  4950.0  322.54  4960.0  322.00  4968.0  322.00  4968.2  321.50  4971.7  321.50
  4972.0  322.00  5110.0  322.00  5120.0  327.66  5130.0  329.54  5140.0  330.89
  5150.0  332.34  5170.0  334.44  5180.0  335.70  5199.0  336.33  5203.0  336.33
#Mann=3,-1,0
  4800.0    0.05       0  4968.0    0.05       0  4972.0    0.05       0
Bank Sta=4968,4972
Exp/Cntr=0.3,0.1

Type RM Length L Ch R = 1,4580,279,279,279
BEGIN DESCRIPTION:
Lynn Creek T 22 9.0
END DESCRIPTION:
XS GIS Cut Line= 3
      2713877.86      6785087.45      2713726.00      6785411.00
      2713625.28      6785727.65
#Sta/Elev= 30
  4642.2  337.40  4668.2  336.45  4683.3  336.62  4690.3  337.08  4700.6  336.52
  4712.4  336.83  4723.4  336.24  4729.0  335.49  4734.5  334.30  4745.5  333.83
  4780.1  331.18  4802.9  329.82  4820.2  329.41  4833.9  328.30  4853.2  327.45
  4894.2  325.07  4911.2  323.31  4915.0  322.00  4915.3  321.50  4918.8  321.50
  4919.0  322.00  5182.2  322.00  5188.5  322.35  5214.4  328.00  5220.0  329.52
  5241.0  330.63  5278.9  333.79  5284.1  333.82  5303.9  335.15  5331.9  336.00
#Mann=4,-1,0
  4642.2    0.05       0  4853.2    0.12       0  4915.0    0.05       0
  4919.0    0.05       0
Bank Sta=4915,4919
Exp/Cntr=0.3,0.1

Type RM Length L Ch R = 1,4301,386,386,386
BEGIN DESCRIPTION:
Lynn Creek T 22 8.0
END DESCRIPTION:
XS GIS Cut Line= 3
      2713676.00      6785011.00      2713476.00      6785311.00
      2713426.00      6785611.01
#Sta/Elev= 30
  4644.1  336.53  4666.6  335.87  4687.7  334.35  4708.7  333.71  4729.7  332.26
  4744.8  332.05  4770.2  329.82  4780.8  329.06  4801.8  328.84  4810.9  328.08
  4816.9  328.02  4824.4  327.23  4860.4  325.36  4883.0  322.85  4893.7  322.04
  4894.5  322.00  4894.7  321.50  4898.2  321.50  4898.5  322.00  5098.4  322.00
  5106.0  324.38  5136.4  325.05  5146.6  325.86  5154.2  327.21  5177.0  327.18
  5197.3  328.27  5207.4  328.44  5275.8  332.11  5280.9  332.01  5308.8  333.26
#Mann=5,-1,0
  4644.1    0.05       0  4770.2    0.12       0  4893.7    0.05       0
  4894.5    0.03       0  4898.5    0.05       0
Bank Sta=4894.5,4898.5
Exp/Cntr=0.3,0.1

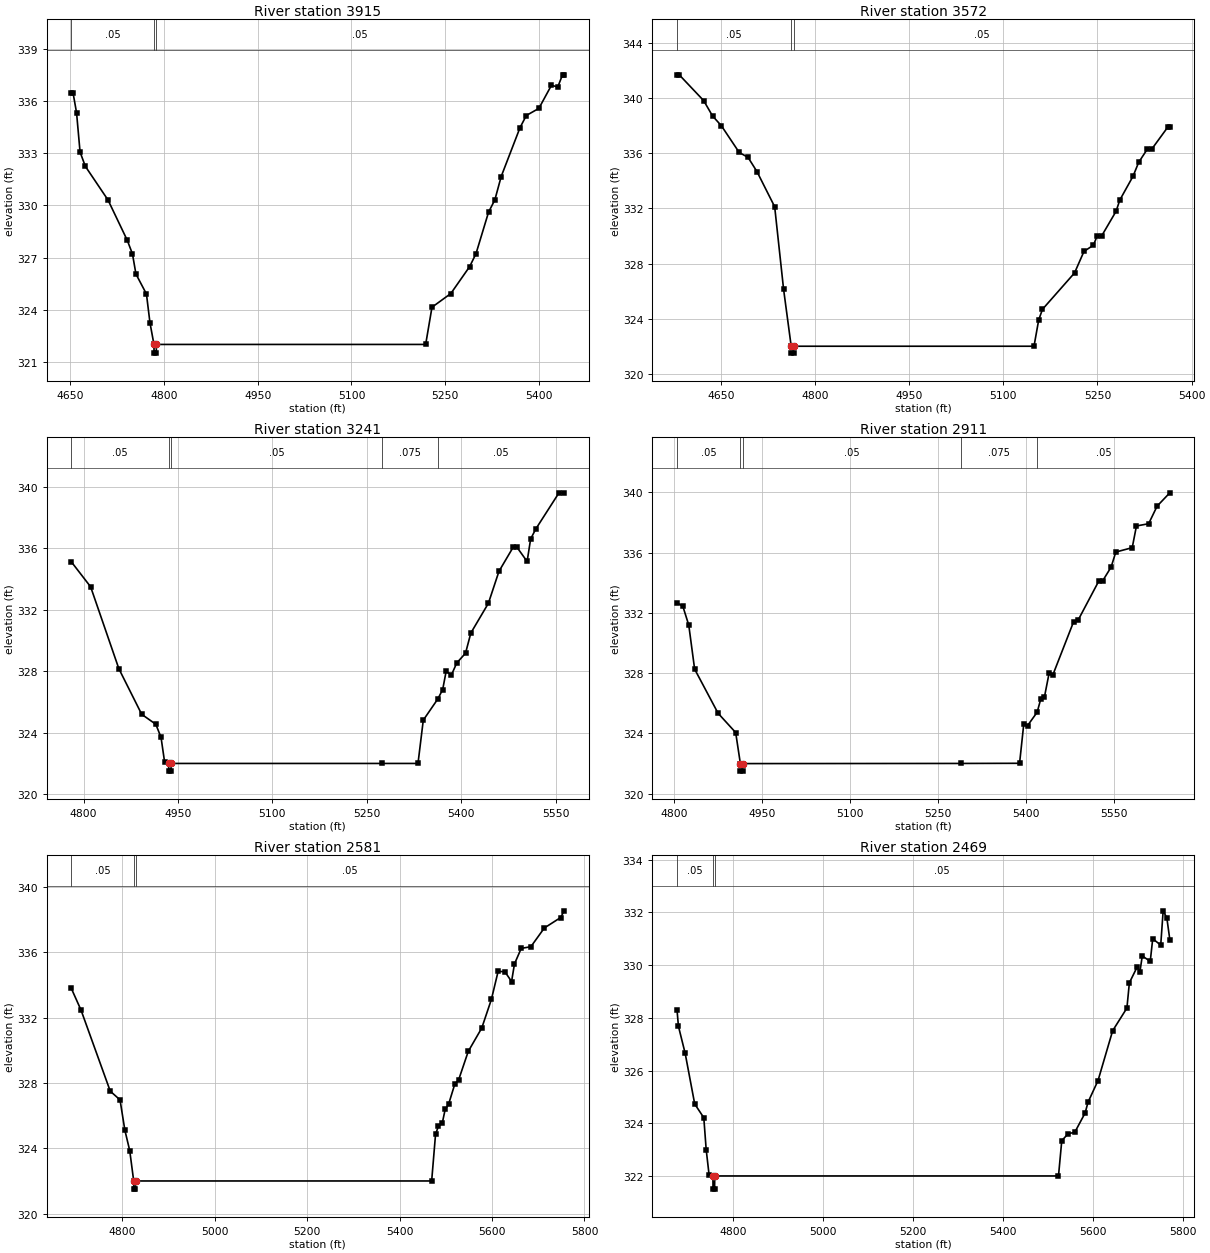
Type RM Length L Ch R = 1,3915,343,343,343
BEGIN DESCRIPTION:
Lynn Creek T 22 7.0
END DESCRIPTION:
XS GIS Cut Line= 3
      2713326.00      6784811.01      2713176.00      6785111.00
      2712725.97      6785161.00
#Sta/Elev= 30
  4651.9  336.47  4654.7  336.47  4660.3  335.33  4665.9  333.07  4674.3  332.25
  4710.6  330.31  4741.3  328.00  4749.7  327.21  4755.3  326.05  4772.1  324.90
  4777.7  323.25  4784.1  322.00  4784.3  321.50  4787.8  321.50  4788.1  322.00
  5218.7  322.00  5228.8  324.14  5259.0  324.93  5289.1  326.48  5299.2  327.22
  5319.3  329.61  5329.4  330.32  5339.5  331.66  5369.6  334.47  5379.7  335.17
  5399.8  335.58  5419.9  336.91  5430.0  336.81  5437.6  337.51  5440.1  337.51
#Mann=3,-1,0
  4651.9    0.05       0  4784.1    0.03       0  4788.1    0.05       0
Bank Sta=4784.1,4788.1
Exp/Cntr=0.3,0.1

Type RM Length L Ch R = 1,3572,331,331,331
BEGIN DESCRIPTION:
Lynn Creek T 22 6.0
END DESCRIPTION:
XS GIS Cut Line= 3
      2713275.98      6784561.02      2712976.00      6784861.00
      2712675.99      6785061.01
#Sta/Elev= 30
  4580.4  341.69  4583.9  341.69  4622.8  339.82  4636.9  338.71  4651.1  337.99
  4679.4  336.06  4693.5  335.70  4707.7  334.67  4735.9  332.12  4750.1  326.13
  4762.2  322.00  4762.5  321.50  4766.0  321.50  4766.2  322.00  5148.9  322.00
  5156.4  323.91  5162.4  324.68  5213.5  327.32  5228.5  328.88  5243.5  329.33
  5249.5  330.00  5257.0  330.03  5279.6  331.79  5285.6  332.61  5306.6  334.33
  5315.6  335.34  5329.1  336.28  5336.6  336.31  5362.2  337.91  5365.2  337.91
#Mann=3,-1,0
  4580.4    0.05       0  4762.2    0.03       0  4766.2    0.05       0
Bank Sta=4762.2,4766.2
Exp/Cntr=0.3,0.1

Type RM Length L Ch R = 1,3241,330,330,330
BEGIN DESCRIPTION:
Lynn Creek T 22 5.0
END DESCRIPTION:
XS GIS Cut Line= 3
      2713075.99      6784461.00      2712876.00      6784561.00
      2712626.01      6785060.98
#Sta/Elev= 30
  4780.6  335.13  4811.3  333.50  4856.1  328.17  4892.4  325.20  4914.8  324.55
  4923.1  323.70  4928.7  322.11  4935.1  322.00  4935.4  321.50  4938.9  321.50
  4939.1  322.00  5273.4  322.00  5331.2  322.00  5339.6  324.82  5362.7  326.20
  5370.4  326.81  5375.9  328.00  5384.3  327.76  5392.7  328.54  5406.7  329.18
  5415.1  330.49  5443.0  332.43  5459.8  334.51  5482.2  336.07  5487.8  336.11
  5504.5  335.15  5510.1  336.62  5518.5  337.28  5554.8  339.60  5563.2  339.62
#Mann=5,-1,0
  4780.6    0.05       0  4935.1    0.03       0  4939.1    0.05       0
  5273.4   0.075       0  5362.7    0.05       0
Bank Sta=4935.1,4939.1
Exp/Cntr=0.3,0.1

Type RM Length L Ch R = 1,2911,330,330,330
BEGIN DESCRIPTION:
Lynn Creek T 22 4.0
END DESCRIPTION:
XS GIS Cut Line= 3
      2712975.95      6784261.00      2712776.00      6784261.00
      2712275.97      6784661.02
#Sta/Elev= 30
  4804.7  332.68  4814.7  332.43  4824.7  331.19  4834.7  328.27  4874.7  325.34
  4904.7  324.06  4912.7  322.00  4912.9  321.50  4916.4  321.50  4916.7  322.00
  5289.6  322.01  5388.8  322.02  5396.0  324.64  5402.4  324.52  5418.8  325.41
  5424.9  326.28  5431.3  326.44  5439.3  328.03  5445.7  327.90  5480.9  331.41
  5488.9  331.54  5524.1  334.13  5530.5  334.13  5544.9  335.04  5552.9  336.04
  5580.9  336.33  5588.1  337.77  5608.9  337.92  5623.4  339.09  5645.0  339.97
#Mann=5,-1,0
  4804.7    0.05       0  4912.7    0.05       0  4916.7    0.05       0
  5289.6   0.075       0  5418.8    0.05       0
Bank Sta=4912.7,4916.7
Exp/Cntr=0.3,0.1

Type RM Length L Ch R = 1,2581,112,112,112
BEGIN DESCRIPTION:
Lynn Creek T 22 3.0
END DESCRIPTION:
XS GIS Cut Line= 3
      2712975.96      6784060.99      2712676.00      6783961.00
      2712225.99      6784561.01
#Sta/Elev= 30
  4689.7  333.80  4710.7  332.47  4774.0  327.50  4795.1  326.97  4805.6  325.11
  4816.1  323.86  4824.7  322.00  4824.9  321.50  4828.4  321.50  4828.7  322.00
  5469.4  322.00  5477.8  324.86  5484.0  325.35  5492.3  325.54  5498.6  326.38
  5505.9  326.69  5519.4  327.93  5527.8  328.20  5548.6  329.94  5577.8  331.37
  5598.6  333.12  5613.2  334.84  5627.8  334.82  5642.3  334.22  5648.6  335.30
  5663.2  336.25  5684.0  336.35  5713.2  337.50  5748.6  338.14  5755.9  338.55
#Mann=3,-1,0
  4689.7    0.05       0  4824.7    0.03       0  4828.7    0.05       0
Bank Sta=4824.7,4828.7
Exp/Cntr=0.3,0.1

Type RM Length L Ch R = 1,2469,223,223,223
BEGIN DESCRIPTION:
Mapping XS b1fd205a
END DESCRIPTION:
XS GIS Cut Line= 3
      2712973.08      6783744.69      2712247.53      6784001.70
      2711949.94      6783868.90
#Sta/Elev= 30
  4674.8  328.29  4677.9  327.68  4692.9  326.65  4714.1  324.73  4734.3  324.21
  4739.6  323.00  4746.0  322.05  4754.6  322.00  4754.8  321.50  4758.3  321.50
  4758.6  322.00  5522.9  322.00  5530.2  323.34  5544.8  323.61  5558.9  323.65
  5582.1  324.39  5588.6  324.80  5610.8  325.62  5643.3  327.51  5675.0  328.37
  5680.5  329.33  5698.1  329.94  5703.7  329.72  5709.2  330.35  5726.9  330.14
  5732.4  331.00  5750.2  330.76  5755.6  332.06  5763.8  331.79  5770.4  330.97
#Mann=3,-1,0
  4674.8    0.05       0  4754.6    0.03       0  4758.6    0.05       0
Bank Sta=4754.6,4758.6
Exp/Cntr=0.3,0.1

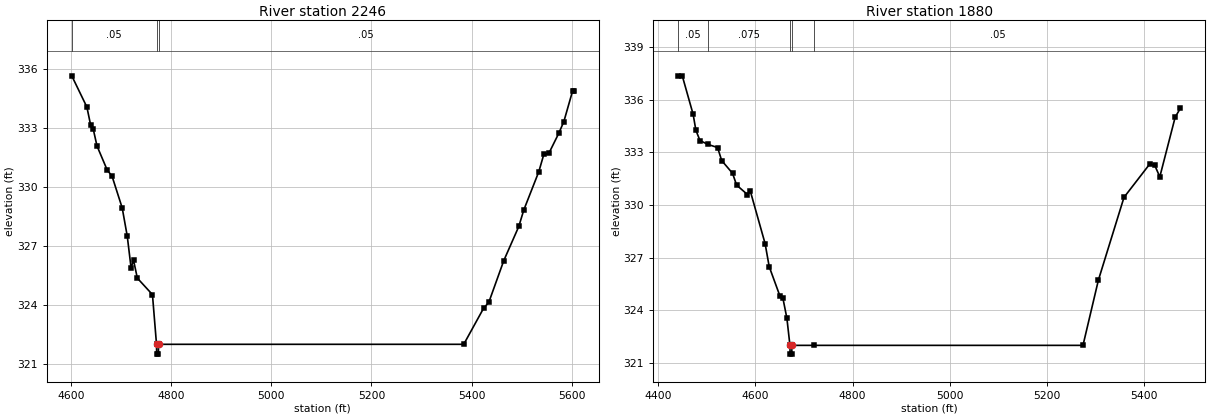
Type RM Length L Ch R = 1,2246,366,366,366
BEGIN DESCRIPTION:
Lynn Creek T 22 2.0
END DESCRIPTION:
XS GIS Cut Line= 3
      2712976.00      6783611.00      2712576.00      6783661.00
      2711976.01      6783661.00
#Sta/Elev= 30
  4601.3  335.67  4631.5  334.08  4639.1  333.15  4644.1  332.97  4651.7  332.10
  4671.8  330.89  4681.9  330.55  4702.1  328.94  4712.2  327.50  4719.7  325.91
  4724.8  326.27  4732.3  325.37  4762.5  324.53  4770.6  322.00  4770.9  321.50
  4774.4  321.50  4774.6  322.00  5384.4  322.00  5424.4  323.85  5434.4  324.13
  5464.4  326.26  5494.4  328.00  5504.4  328.84  5534.4  330.79  5544.4  331.67
  5554.4  331.72  5574.4  332.75  5584.4  333.34  5601.9  334.90  5604.4  334.90
#Mann=3,-1,0
  4601.3    0.05       0  4770.6    0.03       0  4774.6    0.05       0
Bank Sta=4770.6,4774.6
Exp/Cntr=0.3,0.1

Type RM Length L Ch R = 1,1880,0,0,0
BEGIN DESCRIPTION:
Lynn Creek T 22 1.0
END DESCRIPTION:
XS GIS Cut Line= 3
      2713025.96      6783560.98      2712526.00      6783311.00
      2712076.01      6783161.00
#Sta/Elev= 30
  4441.0  337.34  4449.3  337.37  4471.7  335.17  4477.3  334.27  4485.7  333.68
  4502.0  333.46  4522.0  333.28  4530.4  332.54  4552.8  331.81  4561.1  331.14
  4583.5  330.60  4589.1  330.82  4619.8  327.80  4628.2  326.49  4650.6  324.79
  4656.2  324.72  4664.6  323.55  4670.9  322.00  4671.2  321.50  4674.7  321.50
  4674.9  322.00  4721.1  322.00  5274.0  322.00  5305.7  325.72  5358.4  330.44
  5411.1  332.33  5421.6  332.27  5432.1  331.61  5463.8  335.02  5474.3  335.51
#Mann=5,-1,0
  4441.0    0.05       0  4502.0   0.075       0  4670.9    0.03       0
  4674.9   0.075       0  4721.1    0.05       0
Bank Sta=4670.9,4674.9
Exp/Cntr=0.3,0.1

Chan Stop Cuts=-1