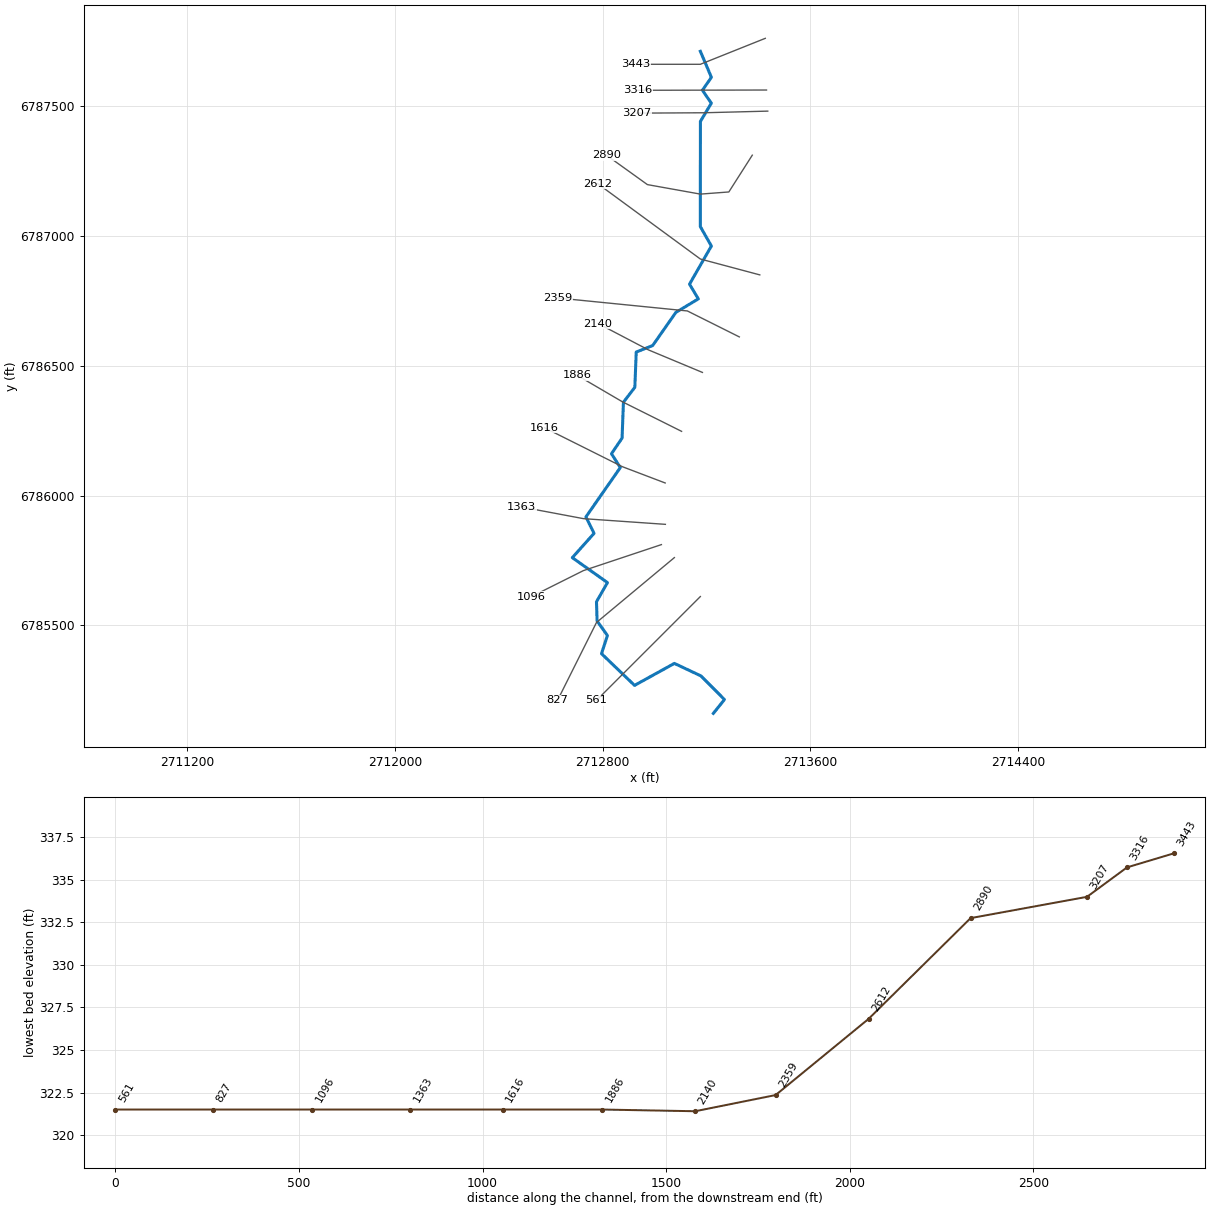
--- Lynn Creek T 23.prj (project) ---

Proj Title=Lynn Creek T 23 Base Level Engineering
Current Plan=p01
Default Exp/Contr=0.3,0.1
English Units
Geom File=g01
Flow File=f01
Plan File=p01
BEGIN DESCRIPTION:
Lynn Creek T 23
END DESCRIPTION:

--- Lynn Creek T 23.p01 (plan) ---

Plan Title=Multiple Run
Short Identifier=Multiple
Geom File=g01
Flow File=f01
Subcritical Flow
K Sum by GR= 0
Std Step Tol= 0.01
Critical Tol= 0.01
Num of Std Step Trials= 20
Max Error Tol= 0.3
Flow Tol Ratio= 0.001
Split Flow NTrial= 30
Split Flow Tol= 0.02
Split Flow Ratio= 0.02
Log Output Level= 0
Friction Slope Method= 1
Unsteady Friction Slope Method= 2
Unsteady Bridges Friction Slope Method= 1
Parabolic Critical Depth
Global Vel Dist=  1 , 1 , 1
Global Log Level= 0
CheckData=True
Encroach Param= -1, 0, 0, 0
BEGIN DESCRIPTION:
Multiple Run
END DESCRIPTION:

--- Lynn Creek T 23.f01 (steady flow) ---

Flow Title=Multiple
Number of Profiles=7
Profile Names=10-year,25-year,50-year,1pct_min,100-year,1pct_plu,500-year
River Rch & RM= Lynn Creek T 23,Reach-1,3443
     342     442     520     304     607    1212     826
Boundary for River Rch & Prof#=Lynn Creek T 23,Reach-1,1
Up Type=0
Dn Type=3
Dn Slope=0.005
Boundary for River Rch & Prof#=Lynn Creek T 23,Reach-1,2
Up Type=0
Dn Type=3
Dn Slope=0.005
Boundary for River Rch & Prof#=Lynn Creek T 23,Reach-1,3
Up Type=0
Dn Type=3
Dn Slope=0.005
Boundary for River Rch & Prof#=Lynn Creek T 23,Reach-1,4
Up Type=0
Dn Type=3
Dn Slope=0.005
Boundary for River Rch & Prof#=Lynn Creek T 23,Reach-1,5
Up Type=0
Dn Type=3
Dn Slope=0.005
Boundary for River Rch & Prof#=Lynn Creek T 23,Reach-1,6
Up Type=0
Dn Type=3
Dn Slope=0.005
Boundary for River Rch & Prof#=Lynn Creek T 23,Reach-1,7
Up Type=0
Dn Type=3
Dn Slope=0.005

--- Lynn Creek T 23.g01 (geometry) ---

Geom Title=Existing Conditions

River Reach=Lynn Creek T 23,Reach-1
Reach XY= 30
      2713176.00      6787711.00      2713218.44      6787610.93
      2713184.01      6787561.00      2713218.22      6787511.10
      2713176.18      6787441.02      2713175.89      6787035.88
      2713218.47      6786960.99      2713134.26      6786814.22
      2713168.07      6786757.43      2713081.68      6786705.38
      2712992.48      6786577.73      2712929.08      6786552.69
      2712923.72      6786416.95      2712879.79      6786359.43
      2712874.61      6786221.44      2712833.80      6786160.90
      2712867.76      6786107.77      2712735.32      6785917.66
      2712766.66      6785854.33      2712683.01      6785760.79
      2712818.30      6785664.67      2712776.03      6785590.95
      2712778.36      6785516.89      2712818.19      6785460.90
      2712795.37      6785391.00      2712922.59      6785268.77
      2713076.00      6785353.50      2713178.32      6785305.20
      2713268.76      6785214.35      2713226.00      6785161.00

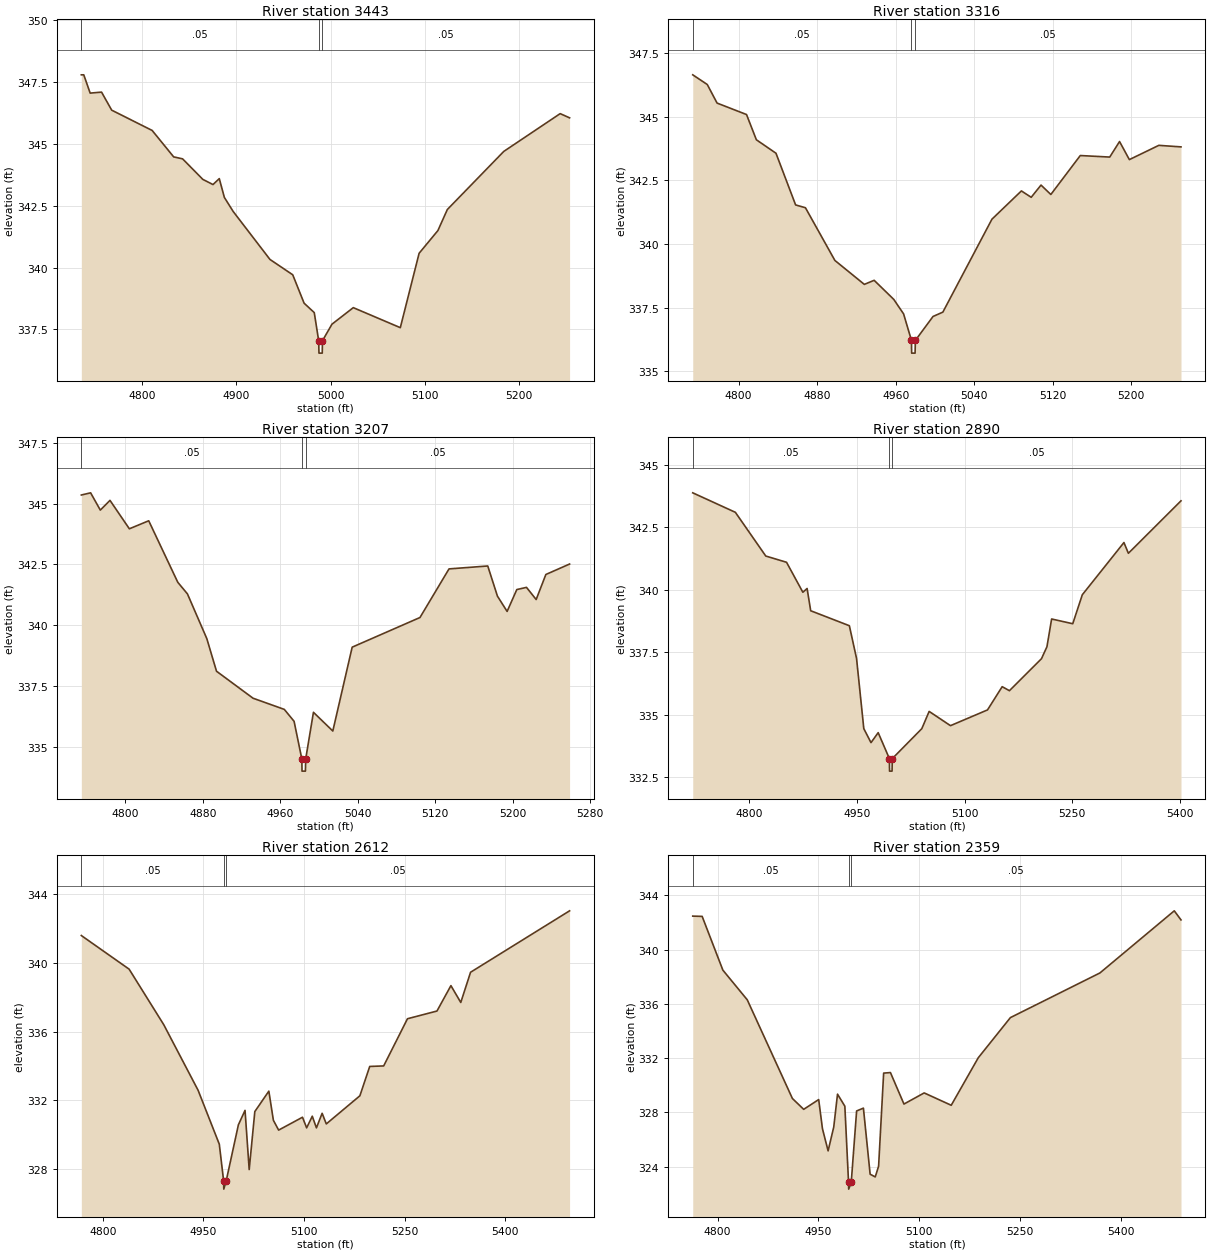
Type RM Length L Ch R = 1,3443,127,127,127
BEGIN DESCRIPTION:
Lynn Creek T 23 12.0
END DESCRIPTION:
XS GIS Cut Line= 3
      2713425.96      6787760.98      2713176.00      6787661.00
      2712926.01      6787661.00
#Sta/Elev= 30
  4735.0  347.80  4737.6  347.80  4744.4  347.06  4756.5  347.10  4767.3  346.37
  4810.3  345.55  4833.2  344.48  4842.7  344.40  4864.2  343.57  4875.0  343.36
  4881.7  343.60  4887.1  342.84  4896.5  342.27  4935.6  340.33  4959.8  339.71
  4971.9  338.56  4982.7  338.18  4987.4  337.04  4987.7  336.54  4991.2  336.54
  4991.4  337.04  5001.5  337.71  5024.2  338.38  5074.2  337.57  5094.2  340.58
  5114.2  341.50  5124.2  342.35  5184.2  344.70  5244.2  346.23  5254.2  346.06
#Mann=3,-1,0
  4735.0    0.05       0  4987.4    0.03       0  4991.4    0.05       0
Bank Sta=4987.4,4991.4
Exp/Cntr=0.3,0.1

Type RM Length L Ch R = 1,3316,109,109,109
BEGIN DESCRIPTION:
Mapping XS 6f4e547c
END DESCRIPTION:
XS GIS Cut Line= 2
      2713430.77      6787561.90      2712933.37      6787560.88
#Sta/Elev= 30
  4753.3  346.65  4768.1  346.27  4778.1  345.54  4808.1  345.09  4818.1  344.10
  4838.1  343.57  4858.1  341.54  4868.1  341.43  4898.1  339.36  4928.1  338.42
  4938.1  338.58  4958.1  337.83  4968.1  337.26  4976.1  336.22  4976.3  335.72
  4979.8  335.72  4980.1  336.22  4998.1  337.16  5008.1  337.33  5058.1  340.98
  5088.1  342.09  5098.1  341.84  5108.1  342.32  5118.1  341.95  5148.1  343.48
  5178.1  343.42  5188.1  344.03  5198.1  343.32  5228.1  343.88  5250.7  343.82
#Mann=3,-1,0
  4753.3    0.05       0  4976.1    0.05       0  4980.1    0.05       0
Bank Sta=4976.1,4980.1
Exp/Cntr=0.3,0.1

Type RM Length L Ch R = 1,3207,317,317,317
BEGIN DESCRIPTION:
Lynn Creek T 23 11.0
END DESCRIPTION:
XS GIS Cut Line= 3
      2713435.58      6787480.62      2713190.16      6787474.32
      2712931.46      6787472.87
#Sta/Elev= 30
  4754.5  345.35  4764.1  345.44  4774.1  344.73  4784.1  345.13  4804.1  343.96
  4824.1  344.29  4854.1  341.76  4864.1  341.28  4884.1  339.44  4894.1  338.10
  4931.8  336.99  4964.1  336.53  4974.2  336.04  4982.2  334.49  4982.4  333.99
  4985.9  333.99  4986.2  334.49  4994.2  336.41  5014.2  335.64  5034.2  339.09
  5104.2  340.31  5134.2  342.31  5174.2  342.43  5184.2  341.19  5194.2  340.56
  5204.2  341.46  5214.2  341.55  5224.2  341.05  5234.2  342.08  5258.7  342.51
#Mann=3,-1,0
  4754.5    0.05       0  4982.2    0.05       0  4986.2    0.05       0
Bank Sta=4982.2,4986.2
Exp/Cntr=0.3,0.1

Type RM Length L Ch R = 1,2890,278,278,278
BEGIN DESCRIPTION:
Lynn Creek T 23 10.0
END DESCRIPTION:
XS GIS Cut Line= 5
      2713376.02      6787311.03      2713285.64      6787169.28
      2713176.00      6787161.00      2712972.15      6787197.58
      2712814.50      6787310.85
#Sta/Elev= 30
  4721.9  343.88  4781.2  343.10  4823.5  341.35  4852.4  341.10  4875.1  339.90
  4881.0  340.05  4886.0  339.16  4939.8  338.56  4949.8  337.25  4959.9  334.44
  4969.9  333.88  4979.9  334.28  4995.5  333.24  4995.7  332.74  4999.2  332.74
  4999.5  333.24  5040.6  334.44  5050.8  335.13  5080.5  334.56  5132.0  335.19
  5152.4  336.12  5162.5  335.96  5207.1  337.24  5214.7  337.72  5221.2  338.83
  5250.6  338.64  5263.9  339.80  5321.8  341.89  5328.0  341.46  5401.2  343.56
#Mann=3,-1,0
  4721.9    0.05       0  4995.5    0.03       0  4999.5    0.05       0
Bank Sta=4995.5,4999.5
Exp/Cntr=0.3,0.1

Type RM Length L Ch R = 1,2612,253,253,253
BEGIN DESCRIPTION:
Lynn Creek T 23 9.0
END DESCRIPTION:
XS GIS Cut Line= 3
      2713404.85      6786849.89      2713176.00      6786911.00
      2712779.86      6787201.82
#Sta/Elev= 30
  4767.9  341.60  4839.2  339.64  4890.9  336.40  4942.1  332.58  4973.7  329.44
  4980.1  327.32  4980.4  326.82  4984.1  327.32  5002.2  330.57  5012.1  331.41
  5018.3  327.96  5026.7  331.34  5047.6  332.53  5054.4  330.83  5062.2  330.26
  5097.8  331.01  5104.0  330.39  5112.4  331.07  5118.6  330.39  5127.1  331.24
  5133.3  330.62  5183.4  332.26  5198.1  333.97  5218.9  334.00  5254.4  336.75
  5298.4  337.20  5319.2  338.68  5333.9  337.70  5348.5  339.46  5496.2  343.04
#Mann=3,-1,0
  4767.9    0.05       0  4980.1    0.05       0  4984.1    0.05       0
Bank Sta=4980.1,4984.1
Exp/Cntr=0.3,0.1

Type RM Length L Ch R = 1,2359,219,219,219
BEGIN DESCRIPTION:
Lynn Creek T 23 8.0
END DESCRIPTION:
XS GIS Cut Line= 3
      2713326.04      6786610.98      2713126.00      6786711.00
      2712626.04      6786761.00
#Sta/Elev= 30
  4763.0  342.47  4777.0  342.45  4807.8  338.49  4844.1  336.30  4911.2  329.03
  4928.0  328.23  4950.3  328.95  4955.9  326.80  4964.3  325.17  4972.7  326.93
  4978.3  329.35  4989.2  328.46  4994.7  322.85  4994.9  322.35  4998.7  322.85
  5006.7  328.11  5016.8  328.32  5026.8  323.45  5034.4  323.25  5039.4  324.04
  5046.9  330.90  5057.0  330.94  5077.1  328.62  5107.2  329.44  5147.4  328.53
  5187.6  332.03  5235.4  334.99  5368.5  338.28  5479.1  342.86  5489.1  342.19
#Mann=3,-1,0
  4763.0    0.05       0  4994.7    0.03       0  4998.7    0.05       0
Bank Sta=4994.7,4998.7
Exp/Cntr=0.3,0.1

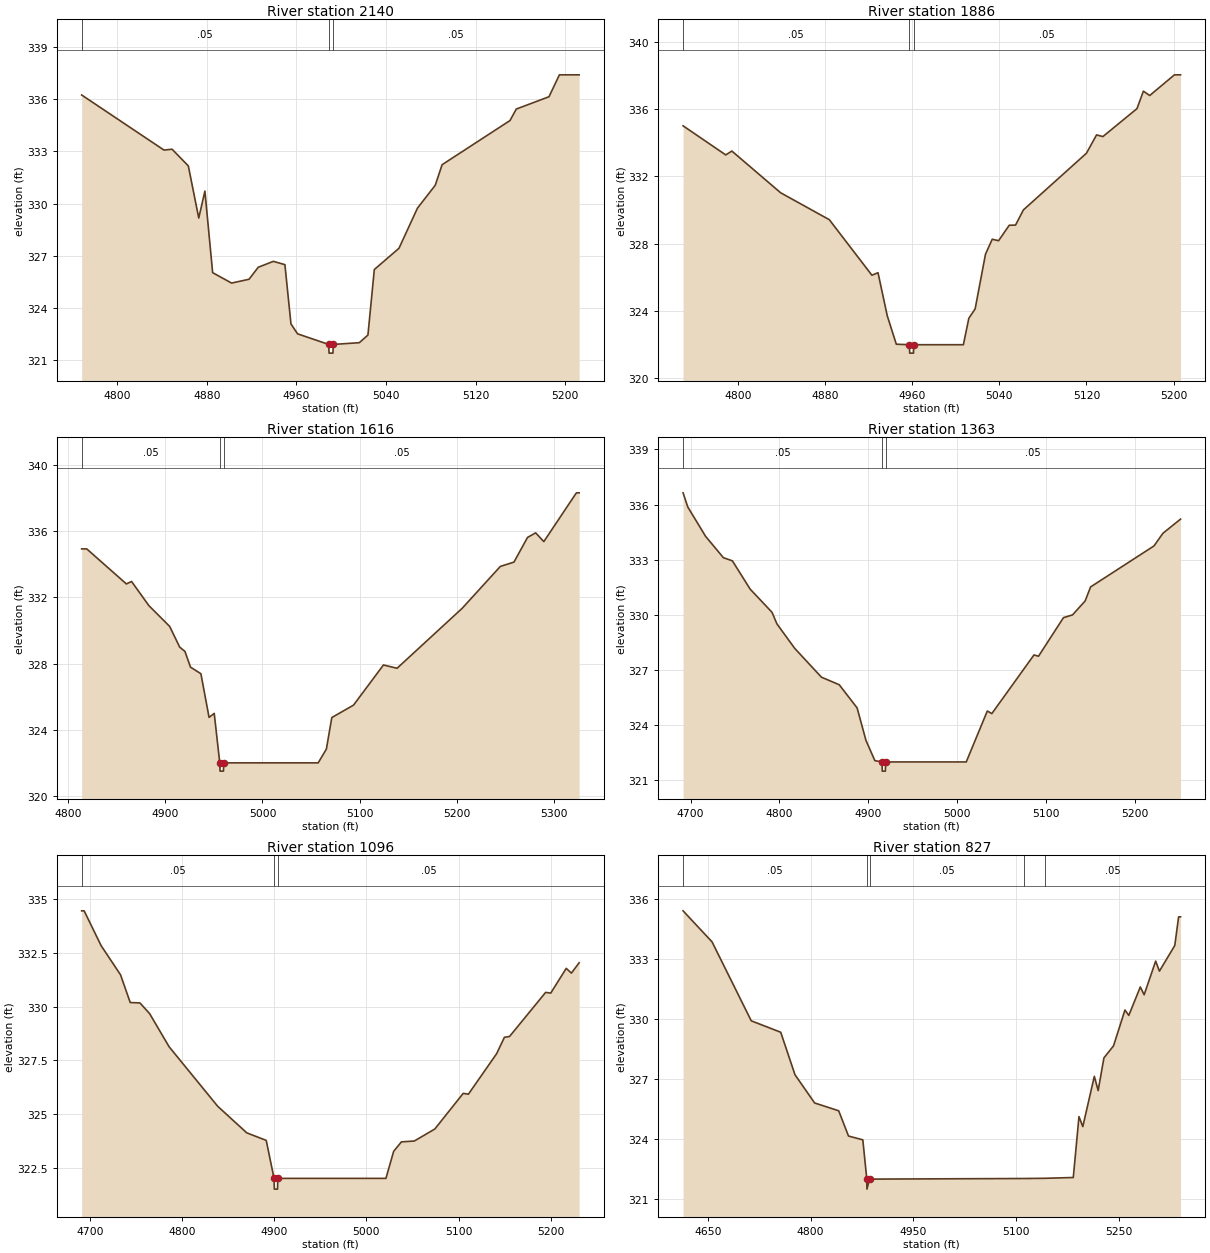
Type RM Length L Ch R = 1,2140,254,254,254
BEGIN DESCRIPTION:
Lynn Creek T 23 7.0
END DESCRIPTION:
XS GIS Cut Line= 3
      2713183.87      6786474.23      2712976.00      6786561.00
      2712782.21      6786662.47
#Sta/Elev= 30
  4768.3  336.25  4841.8  333.08  4849.0  333.13  4863.5  332.17  4872.8  329.17
  4878.3  330.72  4885.2  326.03  4902.1  325.43  4917.7  325.65  4925.9  326.34
  4939.4  326.68  4949.7  326.49  4955.1  323.08  4961.0  322.51  4988.8  321.90
  4989.1  321.40  4992.6  321.40  4992.8  321.90  5016.1  322.00  5023.8  322.44
  5029.5  326.21  5051.5  327.43  5068.0  329.74  5083.9  331.06  5090.0  332.24
  5150.6  334.78  5156.2  335.44  5185.4  336.15  5194.7  337.41  5212.3  337.41
#Mann=3,-1,0
  4768.3    0.05       0  4988.8    0.05       0  4992.8    0.05       0
Bank Sta=4988.8,4992.8
Exp/Cntr=0.3,0.1

Type RM Length L Ch R = 1,1886,270,270,270
BEGIN DESCRIPTION:
Lynn Creek T 23 6.0
END DESCRIPTION:
XS GIS Cut Line= 3
      2713103.71      6786247.28      2712876.00      6786361.00
      2712701.44      6786463.19
#Sta/Elev= 30
  4749.6  335.01  4788.8  333.28  4794.4  333.51  4839.2  331.03  4883.9  329.43
  4923.0  326.13  4928.6  326.28  4937.1  323.72  4945.4  322.03  4957.4  322.00
  4957.7  321.50  4961.2  321.50  4961.4  322.00  5007.0  322.00  5012.0  323.57
  5017.8  324.13  5027.3  327.38  5033.5  328.27  5039.3  328.18  5049.1  329.10
  5054.9  329.11  5062.1  330.01  5120.0  333.38  5129.3  334.47  5135.1  334.37
  5166.4  336.03  5172.3  337.07  5178.1  336.81  5200.8  338.04  5206.4  338.04
#Mann=3,-1,0
  4749.6    0.05       0  4957.4    0.05       0  4961.4    0.05       0
Bank Sta=4957.4,4961.4
Exp/Cntr=0.3,0.1

Type RM Length L Ch R = 1,1616,253,253,253
BEGIN DESCRIPTION:
Lynn Creek T 23 5.0
END DESCRIPTION:
XS GIS Cut Line= 3
      2713040.62      6786048.39      2712876.00      6786111.00
      2712576.03      6786260.98
#Sta/Elev= 30
  4814.1  334.94  4819.3  334.94  4860.1  332.82  4865.4  332.97  4883.2  331.51
  4904.6  330.25  4914.9  329.00  4920.3  328.74  4926.0  327.79  4936.7  327.39
  4945.1  324.75  4950.4  324.99  4956.1  322.00  4956.4  321.50  4959.9  321.50
  4960.1  322.00  5057.3  322.00  5065.7  322.83  5071.3  324.74  5093.6  325.49
  5124.4  327.92  5138.4  327.72  5205.4  331.35  5244.6  333.88  5258.6  334.14
  5272.5  335.63  5280.9  335.91  5289.3  335.38  5322.8  338.33  5325.6  338.33
#Mann=3,-1,0
  4814.1    0.05       0  4956.1    0.05       0  4960.1    0.05       0
Bank Sta=4956.1,4960.1
Exp/Cntr=0.3,0.1

Type RM Length L Ch R = 1,1363,267,267,267
BEGIN DESCRIPTION:
Lynn Creek T 23 4.0
END DESCRIPTION:
XS GIS Cut Line= 3
      2713041.32      6785889.09      2712726.00      6785911.00
      2712486.58      6785956.01
#Sta/Elev= 30
  4691.6  336.64  4696.9  335.87  4717.0  334.27  4737.0  333.11  4747.1  332.94
  4767.1  331.40  4791.7  330.14  4797.2  329.51  4817.2  328.18  4847.3  326.61
  4867.3  326.20  4887.4  324.94  4897.4  323.17  4907.4  322.07  4915.5  322.00
  4915.7  321.50  4919.2  321.50  4919.5  322.00  5010.2  322.00  5033.9  324.77
  5039.0  324.63  5086.4  327.82  5091.5  327.75  5119.6  329.85  5129.8  330.00
  5144.0  330.76  5150.1  331.52  5221.4  333.75  5231.5  334.44  5251.3  335.21
#Mann=3,-1,0
  4691.6    0.05       0  4915.5    0.05       0  4919.5    0.05       0
Bank Sta=4915.5,4919.5
Exp/Cntr=0.3,0.1

Type RM Length L Ch R = 1,1096,269,269,269
BEGIN DESCRIPTION:
Lynn Creek T 23 3.0
END DESCRIPTION:
XS GIS Cut Line= 3
      2713026.02      6785811.01      2712726.00      6785711.00
      2712525.96      6785610.98
#Sta/Elev= 30
  4691.0  334.46  4693.7  334.46  4712.1  332.84  4733.2  331.48  4743.7  330.19
  4754.3  330.17  4764.8  329.67  4785.9  328.13  4838.6  325.36  4870.2  324.12
  4891.3  323.77  4899.8  322.00  4900.1  321.50  4903.6  321.50  4903.8  322.00
  5021.2  322.00  5029.6  323.26  5038.0  323.70  5052.0  323.74  5074.3  324.30
  5105.1  325.96  5110.7  325.92  5141.4  327.81  5149.8  328.57  5155.4  328.61
  5194.5  330.66  5200.1  330.63  5216.9  331.78  5222.5  331.56  5230.9  332.04
#Mann=3,-1,0
  4691.0    0.05       0  4899.8    0.05       0  4903.8    0.05       0
Bank Sta=4899.8,4903.8
Exp/Cntr=0.3,0.1

Type RM Length L Ch R = 1,827,266,266,266
BEGIN DESCRIPTION:
Lynn Creek T 23 2.0
END DESCRIPTION:
XS GIS Cut Line= 3
      2713075.97      6785760.98      2712776.00      6785511.00
      2712625.99      6785210.99
#Sta/Elev= 30
  4614.0  335.39  4656.3  333.84  4713.5  329.90  4756.5  329.33  4777.3  327.21
  4806.0  325.80  4841.1  325.41  4855.4  324.15  4876.3  323.96  4882.1  322.00
  4882.3  321.50  4886.1  322.00  5111.6  322.03  5141.5  322.04  5183.4  322.08
  5191.7  325.12  5197.3  324.62  5214.1  327.13  5219.7  326.42  5228.1  328.05
  5242.1  328.65  5258.8  330.44  5264.4  330.17  5281.2  331.59  5286.8  331.20
  5303.6  332.88  5309.1  332.38  5331.5  333.66  5337.1  335.09  5339.9  335.09
#Mann=5,-1,0
  4614.0    0.05       0  4882.1    0.05       0  4886.1    0.05       0
  5111.6     0.1       0  5141.5    0.05       0
Bank Sta=4882.1,4886.1
Exp/Cntr=0.3,0.1

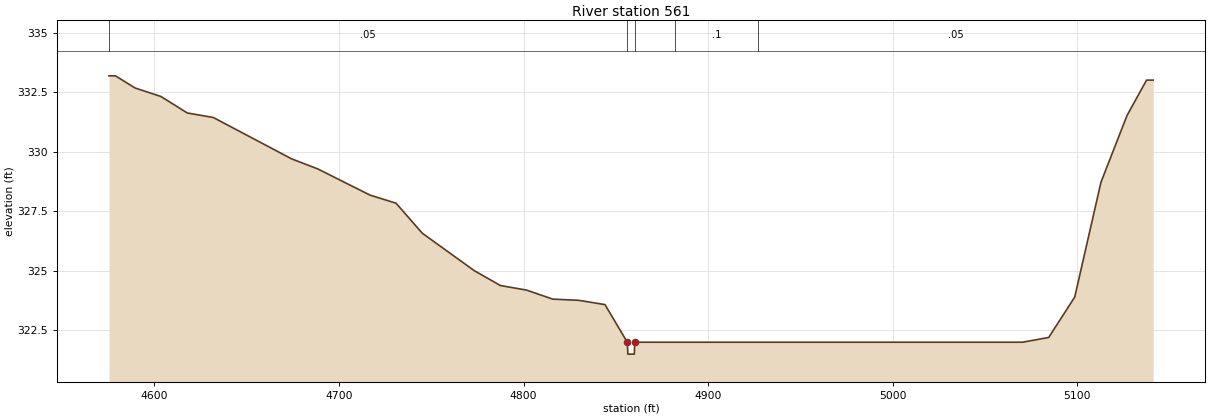
Type RM Length L Ch R = 1,561,0,0,0
BEGIN DESCRIPTION:
Lynn Creek T 23 1.0
END DESCRIPTION:
XS GIS Cut Line= 3
      2713175.98      6785610.98      2712876.00      6785311.00
      2712775.97      6785210.97
#Sta/Elev= 30
  4575.4  333.19  4578.9  333.19  4589.5  332.68  4603.6  332.32  4617.8  331.63
  4631.9  331.44  4674.4  329.70  4688.5  329.28  4716.8  328.18  4730.9  327.84
  4745.1  326.58  4773.4  325.00  4787.5  324.38  4801.6  324.19  4815.8  323.81
  4829.9  323.76  4844.1  323.58  4856.2  322.00  4856.5  321.50  4860.0  321.50
  4860.2  322.00  4881.8  322.00  4927.1  322.00  5070.3  322.00  5084.5  322.20
  5098.6  323.90  5112.8  328.72  5126.9  331.52  5137.5  333.01  5141.1  333.01
#Mann=5,-1,0
  4575.4    0.05       0  4856.2    0.05       0  4860.2    0.05       0
  4881.8     0.1       0  4927.1    0.05       0
Bank Sta=4856.2,4860.2
Exp/Cntr=0.3,0.1

Chan Stop Cuts=-1