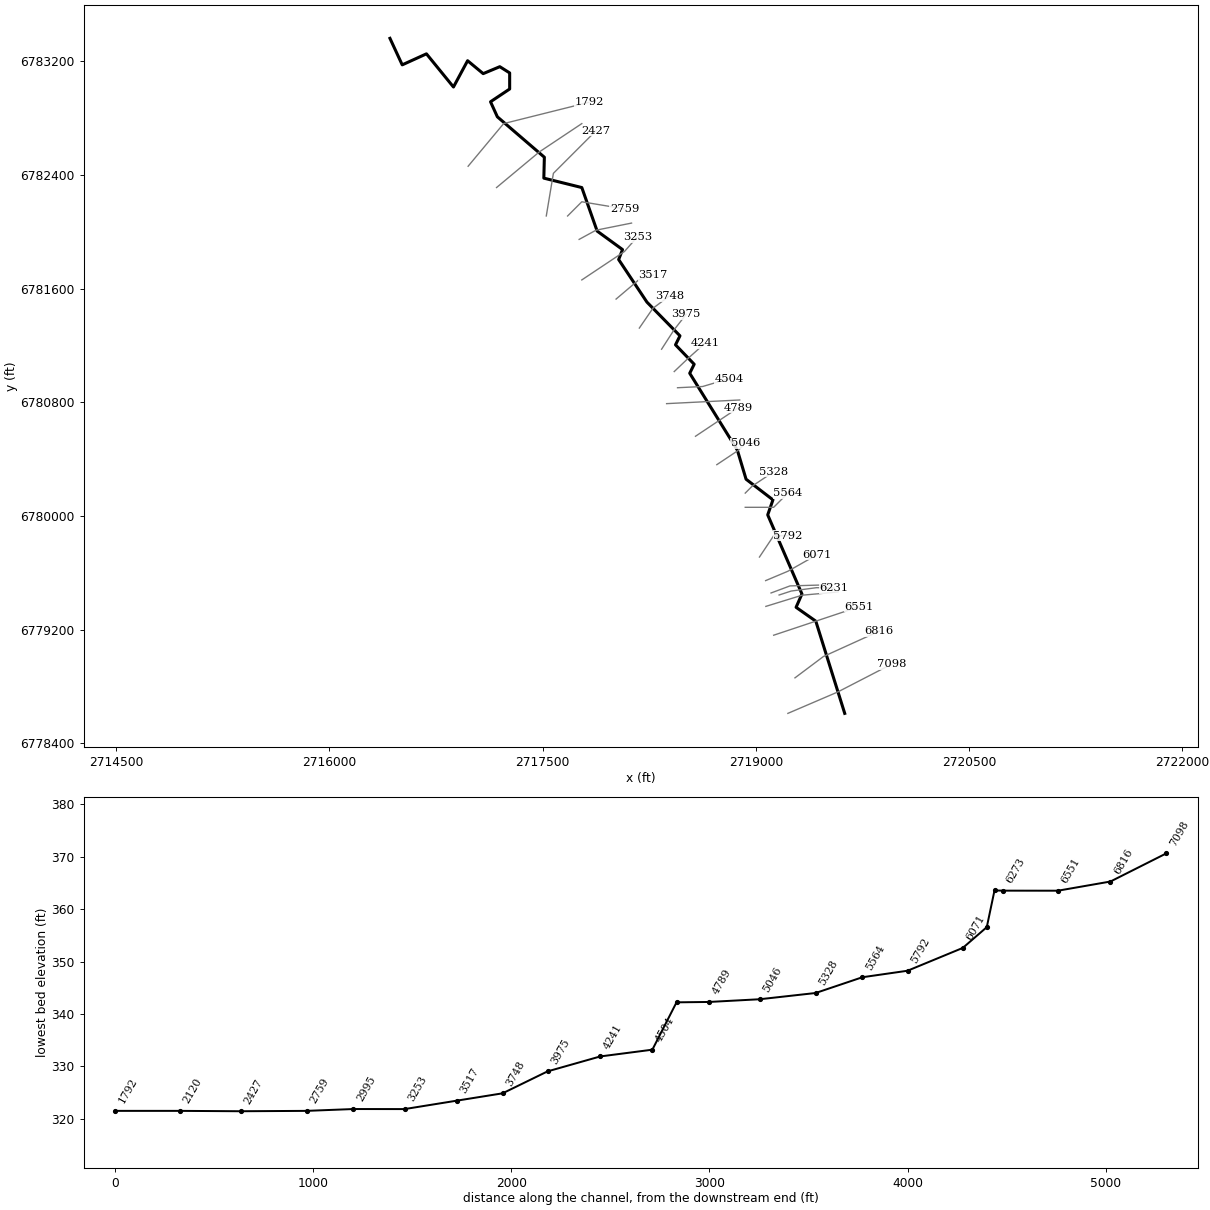
--- Lynn Creek T3.prj (project) ---

Proj Title=Lynn Creek T3 Base Level Engineering
Current Plan=p01
Default Exp/Contr=0.3,0.1
English Units
Geom File=g01
Flow File=f01
Plan File=p01
BEGIN DESCRIPTION:
Lynn Creek T3
END DESCRIPTION:

--- Lynn Creek T3.p01 (plan) ---

Plan Title=Multiple Run
Short Identifier=Multiple
Geom File=g01
Flow File=f01
Subcritical Flow
K Sum by GR= 0
Std Step Tol= 0.01
Critical Tol= 0.01
Num of Std Step Trials= 20
Max Error Tol= 0.3
Flow Tol Ratio= 0.001
Split Flow NTrial= 30
Split Flow Tol= 0.02
Split Flow Ratio= 0.02
Log Output Level= 0
Friction Slope Method= 1
Unsteady Friction Slope Method= 2
Unsteady Bridges Friction Slope Method= 1
Parabolic Critical Depth
Global Vel Dist=  1 , 1 , 1
Global Log Level= 0
CheckData=True
Encroach Param= -1, 0, 0, 0
BEGIN DESCRIPTION:
Multiple Run
END DESCRIPTION:

--- Lynn Creek T3.f01 (steady flow) ---

Flow Title=Multiple
Number of Profiles=7
Profile Names=10-year,25-year,50-year,1pct_min,100-year,1pct_plu,500-year
River Rch & RM= Lynn Creek T3,Reach-1,7098
     208     262     303     175     350     697     462
River Rch & RM= Lynn Creek T3,Reach-1,5046
     337     438     519     306     610    1217     841
River Rch & RM= Lynn Creek T3,Reach-1,2427
     533     710     853     508    1014    2024    1433
Boundary for River Rch & Prof#=Lynn Creek T3,Reach-1,1
Up Type=0
Dn Type=3
Dn Slope=0.005
Boundary for River Rch & Prof#=Lynn Creek T3,Reach-1,2
Up Type=0
Dn Type=3
Dn Slope=0.005
Boundary for River Rch & Prof#=Lynn Creek T3,Reach-1,3
Up Type=0
Dn Type=3
Dn Slope=0.005
Boundary for River Rch & Prof#=Lynn Creek T3,Reach-1,4
Up Type=0
Dn Type=3
Dn Slope=0.005
Boundary for River Rch & Prof#=Lynn Creek T3,Reach-1,5
Up Type=0
Dn Type=3
Dn Slope=0.005
Boundary for River Rch & Prof#=Lynn Creek T3,Reach-1,6
Up Type=0
Dn Type=3
Dn Slope=0.005
Boundary for River Rch & Prof#=Lynn Creek T3,Reach-1,7
Up Type=0
Dn Type=3
Dn Slope=0.005

--- Lynn Creek T3.g01 (geometry) ---

Geom Title=Existing Conditions

River Reach=Lynn Creek T3,Reach-1
Reach XY= 30
      2719626.00      6778611.00      2719422.54      6779259.75
      2719283.72      6779357.34      2719325.04      6779451.14
      2719084.10      6780007.71      2719120.99      6780113.54
      2718931.82      6780258.69      2718870.46      6780463.42
      2718535.32      6781004.34      2718566.70      6781067.67
      2718435.30      6781204.33      2718466.70      6781267.68
      2718234.16      6781504.95      2718035.31      6781804.34
      2718062.50      6781874.68      2717883.86      6782004.81
      2717776.00      6782311.00      2717508.79      6782377.23
      2717512.47      6782524.40      2717181.80      6782808.71
      2717133.67      6782914.66      2717268.36      6783004.55
      2717268.36      6783117.55      2717198.92      6783161.49
      2717082.03      6783112.64      2716972.38      6783203.52
      2716872.86      6783018.50      2716682.75      6783251.90
      2716512.27      6783174.37      2716426.00      6783361.00

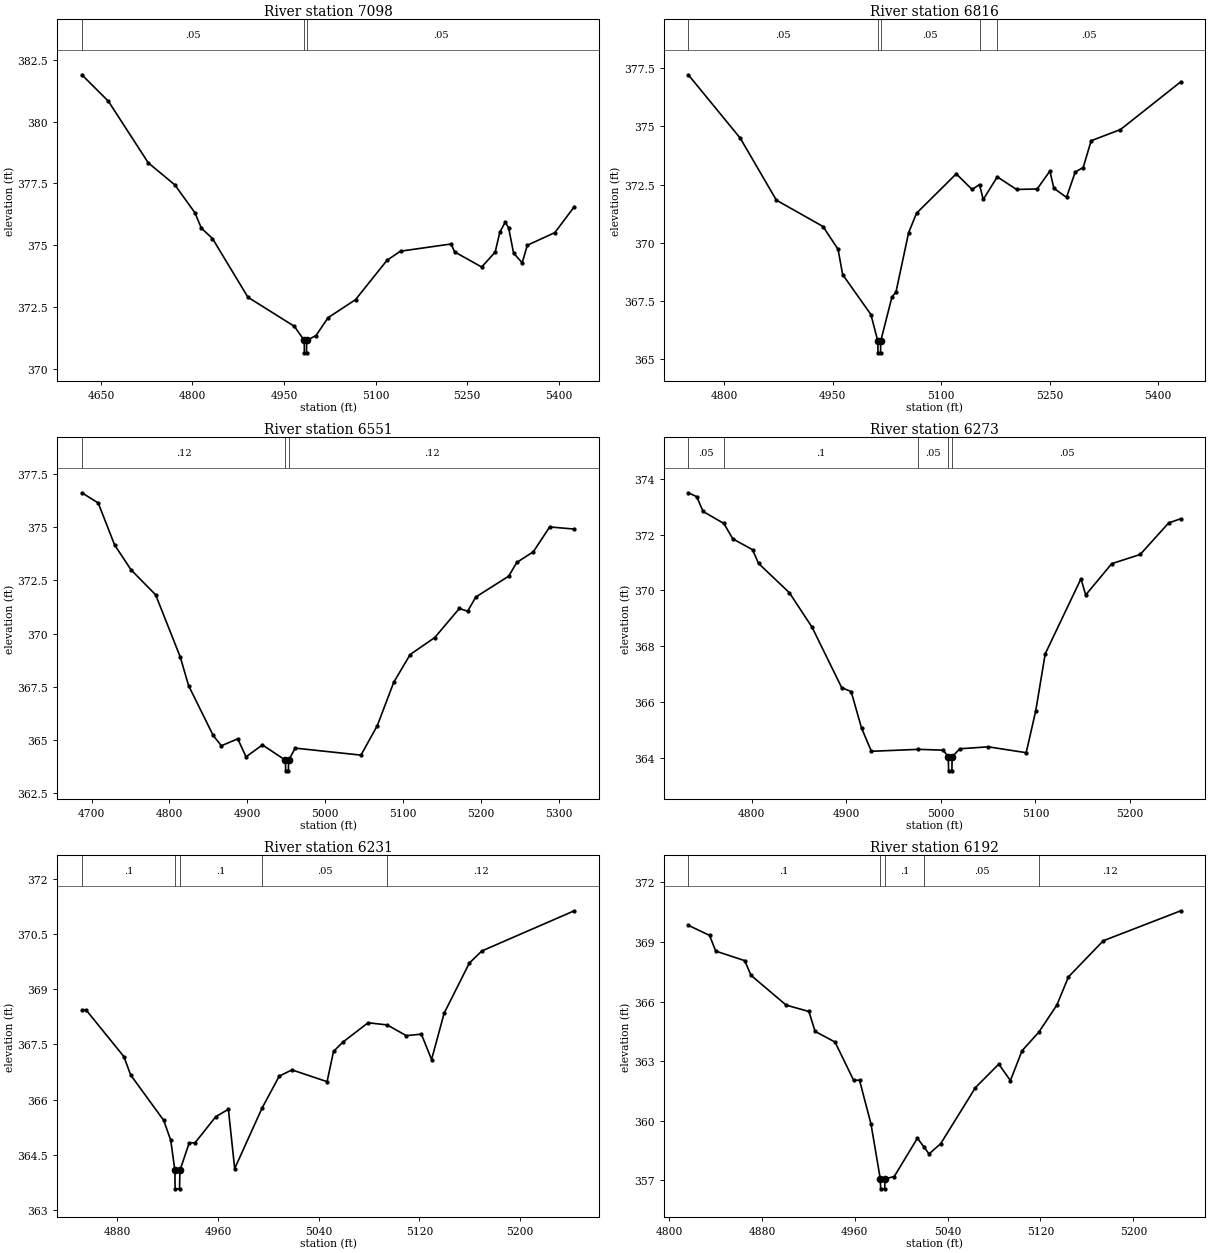
Type RM Length L Ch R = 1,7098,282,282,282
BEGIN DESCRIPTION:
Lynn Creek T3 21.0
END DESCRIPTION:
XS GIS Cut Line= 3
      2719225.99      6778610.99      2719576.00      6778761.00
      2719954.38      6778956.49
#Sta/Elev= 30
  4618.8  381.89  4662.3  380.82  4727.6  378.33  4771.1  377.44  4803.8  376.32
  4814.6  375.69  4832.8  375.27  4890.8  372.90  4967.0  371.72  4983.1  371.15
  4983.3  370.65  4986.8  370.65  4987.1  371.15  5002.4  371.35  5022.1  372.07
  5067.1  372.80  5118.6  374.39  5140.8  374.76  5223.7  375.05  5229.4  374.73
  5273.7  374.12  5295.8  374.72  5303.5  375.53  5312.3  375.93  5317.9  375.70
  5326.0  374.68  5340.1  374.29  5348.5  375.00  5393.6  375.51  5425.5  376.56
#Mann=3,-1,0
  4618.8    0.05       0  4983.1    0.04       0  4987.1    0.05       0
Bank Sta=4983.1,4987.1
Exp/Cntr=0.3,0.1

Type RM Length L Ch R = 1,6816,265,265,265
BEGIN DESCRIPTION:
Lynn Creek T3 20.0
END DESCRIPTION:
XS GIS Cut Line= 3
      2719275.98      6778860.98      2719476.00      6779011.00
      2719868.98      6779189.63
#Sta/Elev= 30
  4750.0  377.21  4821.9  374.49  4871.9  371.83  4936.5  370.70  4957.3  369.72
  4963.6  368.64  5002.8  366.92  5012.3  365.78  5012.6  365.28  5016.1  365.28
  5016.3  365.78  5031.9  367.68  5037.4  367.88  5054.9  370.43  5065.9  371.27
  5120.9  372.96  5142.8  372.29  5153.1  372.50  5158.2  371.86  5177.7  372.83
  5204.3  372.29  5232.9  372.31  5250.5  373.08  5256.0  372.34  5273.5  371.95
  5285.6  373.04  5296.6  373.23  5307.6  374.38  5348.2  374.86  5431.7  376.91
#Mann=5,-1,0
  4750.0    0.05       0  5012.3    0.04       0  5016.3    0.05       0
  5153.1    0.12       0  5177.7    0.05       0
Bank Sta=5012.3,5016.3
Exp/Cntr=0.3,0.1

Type RM Length L Ch R = 1,6551,278,278,278
BEGIN DESCRIPTION:
Lynn Creek T3 19.0
END DESCRIPTION:
XS GIS Cut Line= 3
      2719126.04      6779161.01      2719426.00      6779261.00
      2719725.98      6779360.99
#Sta/Elev= 30
  4687.5  376.63  4708.5  376.15  4729.6  374.17  4750.7  373.00  4782.3  371.82
  4814.0  368.88  4824.5  367.55  4856.1  365.20  4866.7  364.71  4887.7  365.04
  4898.3  364.19  4919.4  364.75  4949.0  364.03  4949.2  363.53  4952.7  363.53
  4953.0  364.03  4961.5  364.60  5045.9  364.27  5066.9  365.66  5088.0  367.70
  5109.1  369.01  5140.7  369.81  5172.3  371.18  5182.9  371.05  5193.4  371.72
  5235.6  372.70  5246.1  373.35  5267.2  373.85  5288.3  375.02  5319.9  374.92
#Mann=3,-1,0
  4687.5    0.12       0  4949.0    0.07       0  4953.0    0.12       0
Bank Sta=4949,4953
Exp/Cntr=0.3,0.1

Type RM Length L Ch R = 1,6273,42,42,42
BEGIN DESCRIPTION:
Lynn Creek T3 18.0
END DESCRIPTION:
XS GIS Cut Line= 3
      2719071.09      6779363.83      2719326.12      6779442.54
      2719578.71      6779465.19
#Sta/Elev= 30
  4733.1  373.50  4742.0  373.36  4748.7  372.83  4770.7  372.40  4780.1  371.85
  4801.0  371.46  4807.3  370.97  4839.9  369.92  4863.8  368.69  4895.2  366.52
  4905.2  366.38  4916.2  365.07  4926.6  364.24  4976.3  364.31  5002.5  364.28
  5007.9  364.04  5008.2  363.54  5011.7  363.54  5011.9  364.04  5020.0  364.33
  5050.1  364.40  5090.2  364.19  5100.3  365.69  5110.3  367.73  5148.1  370.42
  5153.1  369.84  5180.6  370.96  5210.7  371.29  5240.8  372.42  5253.6  372.57
#Mann=5,-1,0
  4733.1    0.05       0  4770.7     0.1       0  4976.3    0.05       0
  5007.9    0.05       0  5011.9    0.05       0
Bank Sta=5007.9,5011.9
Exp/Cntr=0.3,0.1

Type RM Length L Ch R = 1,6231,39,39,39
BEGIN DESCRIPTION:
Mapping XS 1ca22f7c
END DESCRIPTION:
XS GIS Cut Line= 4
      2719164.22      6779443.93      2719249.64      6779471.87
      2719427.92      6779495.47      2719549.39      6779493.09
#Sta/Elev= 30
  4851.8  368.44  4855.1  368.44  4885.2  367.17  4890.6  366.67  4916.8  365.44
  4922.4  364.90  4925.7  364.08  4925.9  363.58  4929.4  363.58  4929.7  364.08
  4937.1  364.83  4941.7  364.83  4958.2  365.54  4968.2  365.74  4973.2  364.13
  4994.9  365.77  5008.6  366.64  5018.7  366.81  5046.6  366.49  5051.7  367.31
  5059.0  367.56  5079.2  368.09  5094.4  368.03  5109.5  367.74  5121.5  367.78
  5129.6  367.09  5139.6  368.35  5159.6  369.71  5169.6  370.04  5243.0  371.13
#Mann=5,-1,0
  4851.8     0.1       0  4925.7    0.05       0  4929.7     0.1       0
  4994.9    0.05       0  5094.4    0.12       0
Bank Sta=4925.7,4929.7
Exp/Cntr=0.3,0.1

Type RM Length L Ch R = 1,6192,121,121,121
BEGIN DESCRIPTION:
Mapping XS 06eea1bf
END DESCRIPTION:
XS GIS Cut Line= 3
      2719107.59      6779458.20      2719241.08      6779508.04
      2719522.78      6779515.84
#Sta/Elev= 30
  4816.6  369.84  4834.9  369.33  4840.2  368.54  4865.2  368.06  4870.6  367.32
  4900.9  365.82  4920.5  365.50  4925.8  364.50  4943.0  363.96  4959.0  362.04
  4964.1  362.04  4974.0  359.83  4982.0  357.07  4982.3  356.57  4985.8  356.57
  4986.0  357.07  4994.0  357.19  5014.0  359.12  5019.7  358.67  5024.0  358.33
  5034.0  358.84  5064.0  361.67  5084.1  362.85  5094.1  362.02  5104.1  363.52
  5118.6  364.46  5134.1  365.82  5144.1  367.24  5174.1  369.06  5240.9  370.57
#Mann=5,-1,0
  4816.6     0.1       0  4982.0    0.07       0  4986.0     0.1       0
  5019.7    0.05       0  5118.6    0.12       0
Bank Sta=4982,4986
Exp/Cntr=0.3,0.1

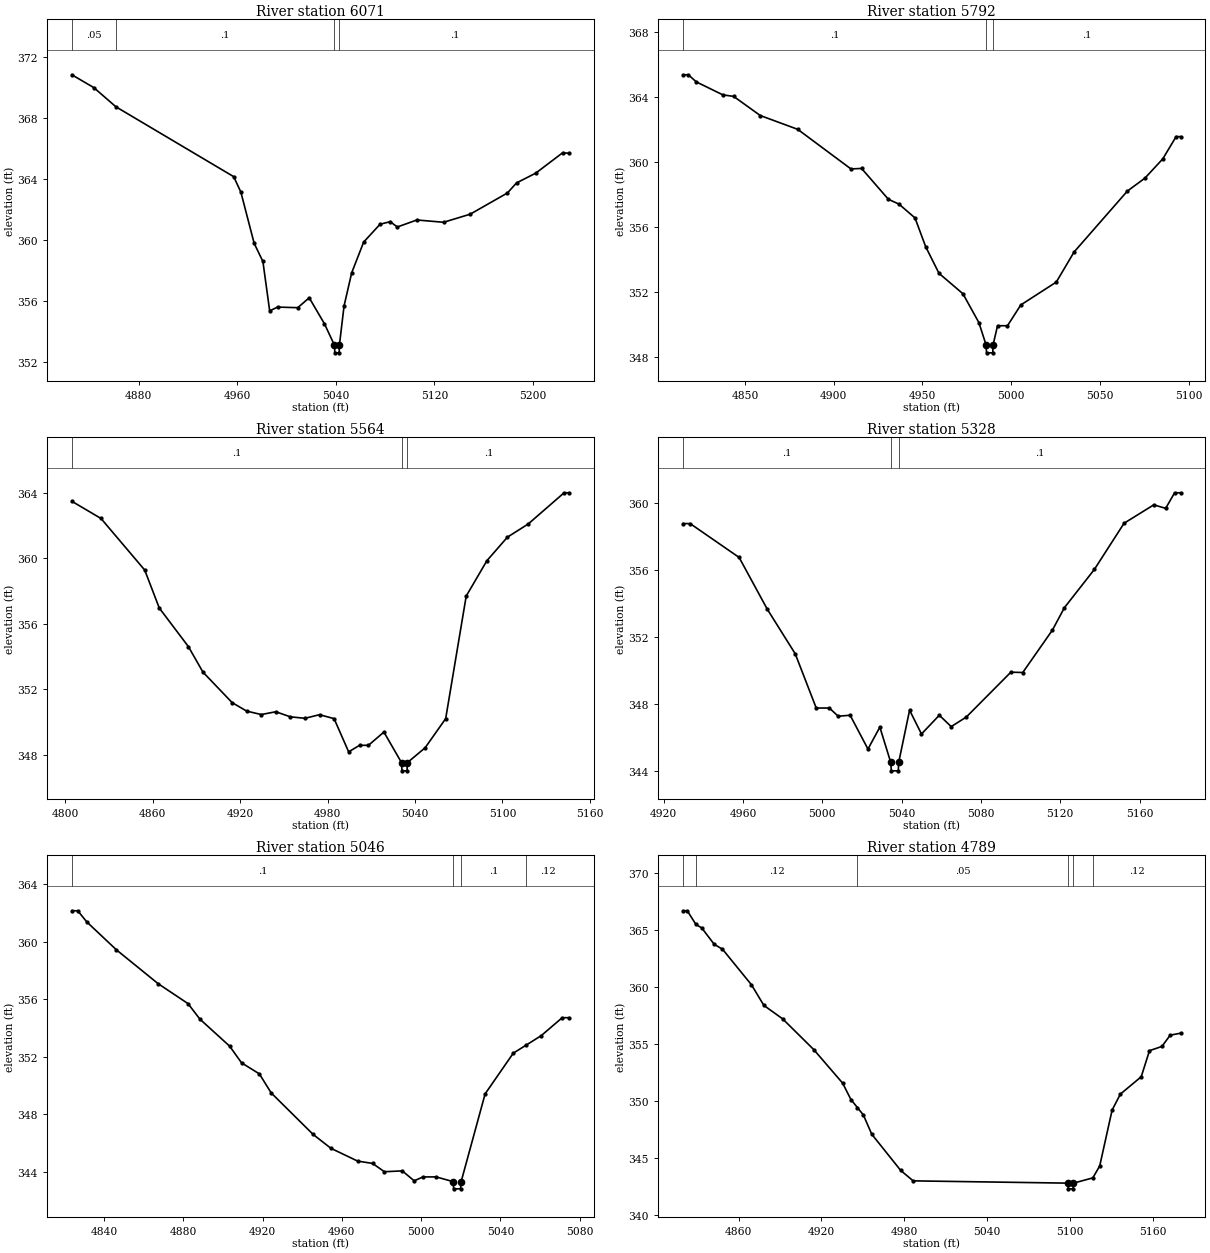
Type RM Length L Ch R = 1,6071,279,279,279
BEGIN DESCRIPTION:
Lynn Creek T3 17.0
END DESCRIPTION:
XS GIS Cut Line= 3
      2719069.56      6779545.16      2719226.00      6779611.00
      2719429.79      6779726.35
#Sta/Elev= 30
  4825.7  370.84  4843.5  370.00  4861.5  368.74  4957.1  364.16  4962.9  363.15
  4973.7  359.79  4980.8  358.60  4986.3  355.36  4992.7  355.61  5009.1  355.57
  5018.4  356.22  5030.8  354.51  5038.9  353.11  5039.2  352.61  5042.7  352.61
  5042.9  353.11  5046.7  355.69  5052.9  357.86  5062.6  359.87  5075.9  361.04
  5084.2  361.21  5089.9  360.86  5105.8  361.32  5127.5  361.17  5149.1  361.70
  5179.3  363.09  5186.7  363.75  5202.3  364.39  5224.2  365.73  5229.6  365.69
#Mann=4,-1,0
  4825.7    0.05       0  4861.5     0.1       0  5038.9    0.07       0
  5042.9     0.1       0
Bank Sta=5038.9,5042.9
Exp/Cntr=0.3,0.1

Type RM Length L Ch R = 1,5792,228,228,228
BEGIN DESCRIPTION:
Lynn Creek T3 16.0
END DESCRIPTION:
XS GIS Cut Line= 3
      2719026.01      6779711.02      2719126.00      6779861.00
      2719226.05      6779861.00
#Sta/Elev= 30
  4815.1  365.38  4818.1  365.38  4822.6  364.94  4837.6  364.14  4843.6  364.05
  4858.6  362.87  4879.7  362.02  4909.7  359.58  4915.7  359.61  4930.8  357.71
  4936.8  357.41  4945.8  356.56  4951.8  354.79  4959.3  353.15  4972.8  351.89
  4981.8  350.11  4985.8  348.75  4986.1  348.25  4989.6  348.25  4989.8  348.75
  4992.3  349.92  4997.9  349.92  5005.4  351.20  5025.4  352.61  5035.4  354.46
  5065.4  358.21  5075.4  359.02  5085.4  360.20  5092.9  361.57  5095.4  361.57
#Mann=3,-1,0
  4815.1     0.1       0  4985.8    0.07       0  4989.8     0.1       0
Bank Sta=4985.8,4989.8
Exp/Cntr=0.3,0.1

Type RM Length L Ch R = 1,5564,236,236,236
BEGIN DESCRIPTION:
Lynn Creek T3 15.0
END DESCRIPTION:
XS GIS Cut Line= 3
      2718925.96      6780061.00      2719126.00      6780061.00
      2719226.03      6780161.03
#Sta/Elev= 30
  4804.4  363.48  4824.4  362.43  4854.4  359.28  4864.4  356.96  4884.4  354.60
  4894.4  353.04  4914.4  351.18  4924.4  350.66  4934.4  350.45  4944.4  350.62
  4954.4  350.31  4964.4  350.22  4974.4  350.44  4984.4  350.20  4994.4  348.17
  5001.9  348.57  5008.0  348.57  5018.6  349.38  5030.7  347.51  5031.0  347.01
  5034.5  347.01  5034.7  347.51  5046.9  348.42  5061.0  350.20  5075.1  357.69
  5089.3  359.85  5103.4  361.29  5117.6  362.09  5142.3  364.00  5145.9  364.00
#Mann=3,-1,0
  4804.4     0.1       0  5030.7    0.07       0  5034.7     0.1       0
Bank Sta=5030.7,5034.7
Exp/Cntr=0.3,0.1

Type RM Length L Ch R = 1,5328,282,282,282
BEGIN DESCRIPTION:
Lynn Creek T3 14.0
END DESCRIPTION:
XS GIS Cut Line= 3
      2718925.97      6780160.97      2718976.00      6780211.00
      2719125.98      6780310.98
#Sta/Elev= 30
  4929.7  358.76  4933.3  358.76  4958.0  356.74  4972.2  353.65  4986.3  350.99
  4996.9  347.75  5003.5  347.75  5008.0  347.26  5014.0  347.32  5023.0  345.30
  5029.0  346.61  5034.5  344.50  5034.8  344.00  5038.3  344.00  5038.5  344.50
  5044.0  347.62  5050.0  346.20  5059.0  347.32  5065.0  346.64  5072.6  347.21
  5095.1  349.89  5101.1  349.87  5116.1  352.41  5122.1  353.74  5137.2  356.02
  5152.2  358.78  5167.2  359.88  5173.2  359.67  5177.7  360.60  5180.7  360.60
#Mann=3,-1,0
  4929.7     0.1       0  5034.5    0.07       0  5038.5     0.1       0
Bank Sta=5034.5,5038.5
Exp/Cntr=0.3,0.1

Type RM Length L Ch R = 1,5046,257,257,257
BEGIN DESCRIPTION:
Lynn Creek T3 13.0
END DESCRIPTION:
XS GIS Cut Line= 3
      2718726.02      6780361.02      2718876.00      6780461.00
      2718926.03      6780511.03
#Sta/Elev= 30
  4823.8  362.16  4826.8  362.16  4831.3  361.39  4846.3  359.44  4867.3  357.09
  4882.4  355.70  4888.4  354.62  4903.4  352.74  4909.4  351.58  4918.4  350.81
  4924.4  349.48  4945.5  346.60  4954.5  345.63  4968.0  344.74  4975.5  344.58
  4981.5  344.00  4990.5  344.06  4996.5  343.37  5001.0  343.64  5007.6  343.64
  5016.2  343.31  5016.4  342.81  5019.9  342.81  5020.2  343.31  5032.3  349.42
  5046.5  352.25  5053.1  352.82  5060.6  353.47  5071.2  354.72  5074.8  354.72
#Mann=4,-1,0
  4823.8     0.1       0  5016.2    0.07       0  5020.2     0.1       0
  5053.1    0.12       0
Bank Sta=5016.2,5020.2
Exp/Cntr=0.3,0.1

Type RM Length L Ch R = 1,4789,163,163,163
BEGIN DESCRIPTION:
Lynn Creek T3 12.0
END DESCRIPTION:
XS GIS Cut Line= 3
      2718575.96      6780560.97      2718726.00      6780661.00
      2718876.00      6780761.00
#Sta/Elev= 30
  4819.7  366.68  4822.8  366.68  4829.0  365.49  4833.3  365.17  4842.3  363.74
  4848.3  363.31  4869.3  360.19  4878.3  358.38  4891.9  357.20  4914.4  354.51
  4935.4  351.56  4941.4  350.12  4946.1  349.42  4950.4  348.77  4956.5  347.08
  4977.5  343.90  4986.5  342.99  5098.7  342.79  5098.9  342.29  5102.4  342.29
  5102.7  342.79  5116.7  343.25  5121.7  344.29  5130.7  349.20  5136.7  350.60
  5151.8  352.12  5157.8  354.41  5166.8  354.78  5172.8  355.77  5180.3  355.94
#Mann=6,-1,0
  4819.7    0.05       0  4829.0    0.12       0  4946.1    0.05       0
  5098.7    0.03       0  5102.7    0.05       0  5116.7    0.12       0
Bank Sta=5098.7,5102.7
Exp/Cntr=0.3,0.1

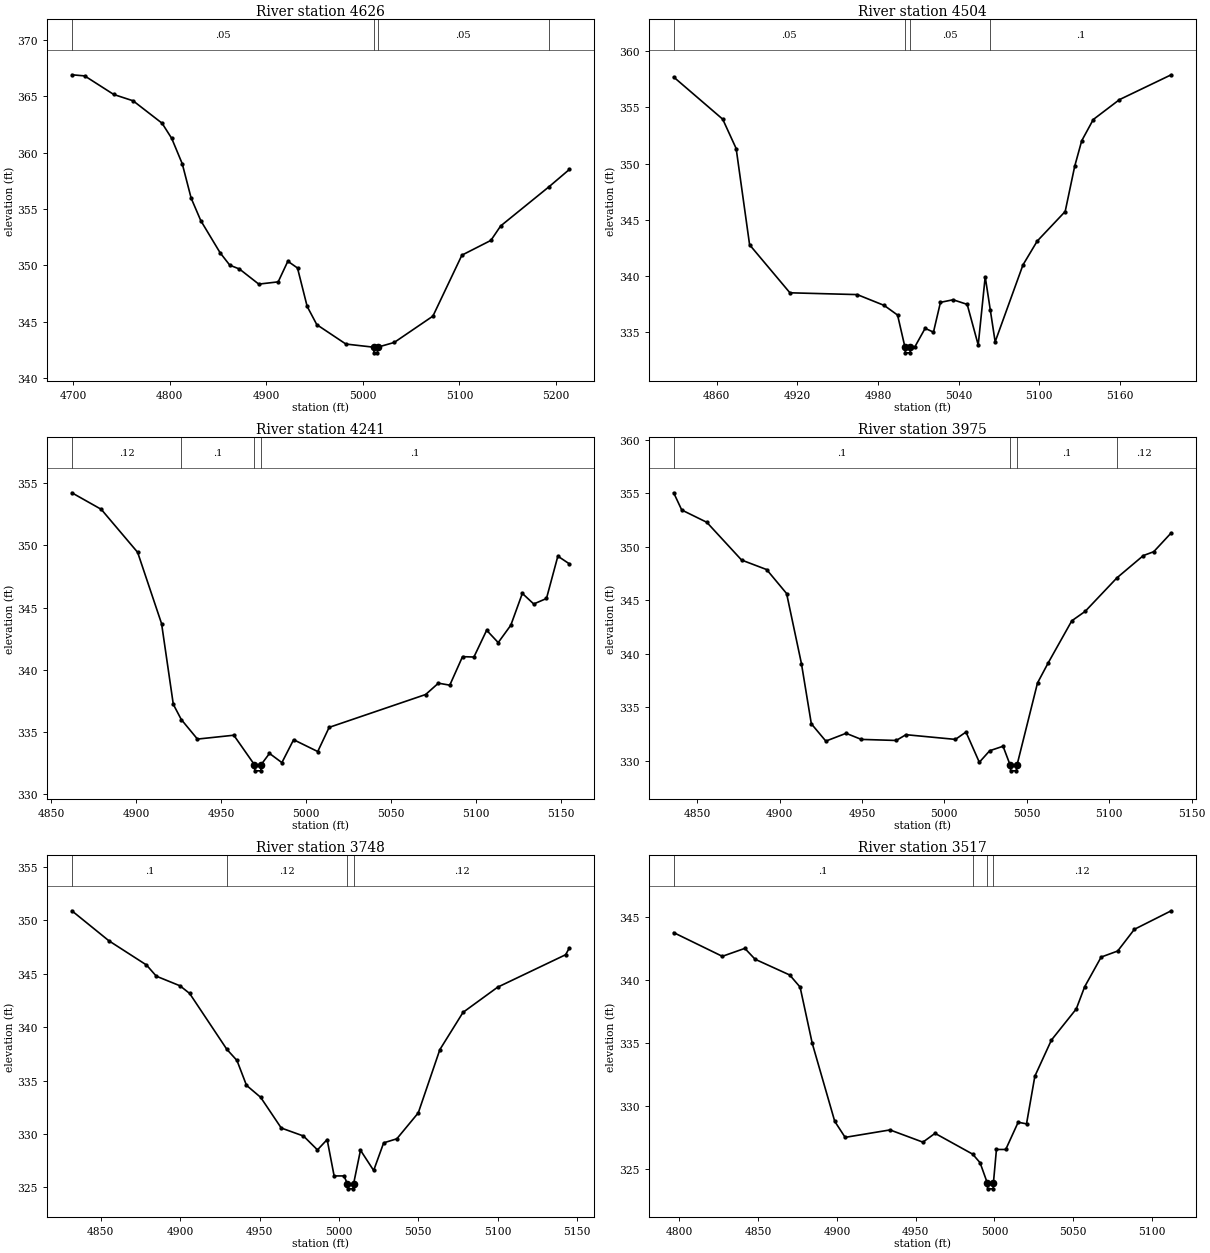
Type RM Length L Ch R = 1,4626,122,122,122
BEGIN DESCRIPTION:
Mapping XS fd49085a
END DESCRIPTION:
XS GIS Cut Line= 2
      2718372.69      6780790.49      2718887.15      6780816.23
#Sta/Elev= 30
  4698.8  366.90  4712.1  366.80  4742.2  365.15  4762.2  364.59  4792.2  362.60
  4802.2  361.25  4813.1  359.00  4822.3  355.95  4832.3  353.95  4852.3  351.10
  4862.3  350.00  4872.3  349.66  4892.3  348.32  4912.4  348.52  4922.4  350.35
  4932.4  349.75  4942.4  346.34  4952.4  344.72  4982.5  343.00  5011.3  342.72
  5011.6  342.22  5015.1  342.22  5015.3  342.72  5032.5  343.14  5072.6  345.48
  5102.6  350.89  5132.6  352.20  5142.7  353.48  5192.9  356.97  5213.9  358.50
#Mann=4,-1,0
  4698.8    0.05       0  5011.3    0.05       0  5015.3    0.05       0
  5192.9    0.12       0
Bank Sta=5011.3,5015.3
Exp/Cntr=0.3,0.1

Type RM Length L Ch R = 1,4504,263,263,263
BEGIN DESCRIPTION:
Lynn Creek T3 11.0
END DESCRIPTION:
XS GIS Cut Line= 3
      2718449.56      6780902.42      2718626.00      6780911.00
      2718811.62      6780965.82
#Sta/Elev= 30
  4828.0  357.71  4864.5  353.96  4874.5  351.35  4884.5  342.79  4914.5  338.52
  4964.6  338.36  4984.6  337.40  4994.6  336.54  5000.1  333.68  5000.4  333.18
  5003.9  333.18  5004.1  333.68  5007.3  333.68  5015.1  335.36  5021.3  335.02
  5026.5  337.67  5035.9  337.90  5046.4  337.49  5054.6  333.88  5059.8  339.95
  5063.6  336.98  5067.2  334.16  5087.9  341.00  5098.5  343.12  5119.3  345.75
  5126.4  349.78  5131.6  352.04  5140.2  353.93  5159.7  355.70  5198.2  357.91
#Mann=4,-1,0
  4828.0    0.05       0  5000.1    0.03       0  5004.1    0.05       0
  5063.6     0.1       0
Bank Sta=5000.1,5004.1
Exp/Cntr=0.3,0.1

Type RM Length L Ch R = 1,4241,266,266,266
BEGIN DESCRIPTION:
Lynn Creek T3 10.0
END DESCRIPTION:
XS GIS Cut Line= 3
      2718426.30      6781016.19      2718526.00      6781111.00
      2718641.71      6781214.46
#Sta/Elev= 30
  4862.1  354.22  4879.4  352.89  4900.8  349.44  4914.9  343.71  4921.8  337.23
  4926.5  336.01  4936.0  334.44  4957.4  334.75  4969.5  332.39  4969.8  331.89
  4973.3  331.89  4973.5  332.39  4978.4  333.29  4985.7  332.55  4992.6  334.39
  5006.8  333.44  5013.5  335.38  5070.3  338.02  5077.8  338.93  5084.5  338.77
  5092.0  341.06  5098.7  341.03  5106.2  343.18  5113.0  342.19  5120.4  343.58
  5127.2  346.14  5133.9  345.29  5141.4  345.73  5148.1  349.13  5154.9  348.51
#Mann=4,-1,0
  4862.1    0.12       0  4926.5     0.1       0  4969.5    0.07       0
  4973.5     0.1       0
Bank Sta=4969.5,4973.5
Exp/Cntr=0.3,0.1

Type RM Length L Ch R = 1,3975,227,227,227
BEGIN DESCRIPTION:
Lynn Creek T3 9.0
END DESCRIPTION:
XS GIS Cut Line= 3
      2718337.29      6781173.44      2718426.00      6781311.00
      2718511.07      6781419.81
#Sta/Elev= 30
  4835.8  355.04  4840.7  353.43  4855.9  352.28  4877.0  348.75  4892.2  347.86
  4904.3  345.62  4913.3  339.07  4919.3  333.44  4928.1  331.82  4940.4  332.55
  4949.6  331.98  4970.8  331.88  4976.7  332.42  5006.7  331.98  5013.1  332.67
  5021.2  329.84  5027.5  330.92  5035.6  331.34  5040.0  329.54  5040.2  329.04
  5043.7  329.04  5044.0  329.54  5056.5  337.26  5063.0  339.14  5077.3  343.07
  5085.4  343.95  5104.7  347.09  5120.7  349.17  5127.0  349.53  5137.6  351.29
#Mann=4,-1,0
  4835.8     0.1       0  5040.0    0.07       0  5044.0     0.1       0
  5104.7    0.12       0
Bank Sta=5040,5044
Exp/Cntr=0.3,0.1

Type RM Length L Ch R = 1,3748,231,231,231
BEGIN DESCRIPTION:
Lynn Creek T3 8.0
END DESCRIPTION:
XS GIS Cut Line= 3
      2718180.82      6781322.26      2718276.00      6781461.00
      2718392.23      6781547.95
#Sta/Elev= 30
  4831.8  350.91  4855.2  348.09  4878.8  345.83  4885.0  344.78  4899.9  343.88
  4906.0  343.16  4929.4  337.93  4935.8  336.88  4941.8  334.55  4950.7  333.43
  4963.7  330.55  4977.7  329.80  4986.5  328.50  4992.6  329.47  4997.0  326.06
  5003.2  326.06  5005.3  325.35  5005.6  324.85  5009.1  324.85  5009.3  325.35
  5013.6  328.47  5021.9  326.57  5028.2  329.16  5036.5  329.54  5050.0  331.97
  5063.6  337.90  5078.2  341.39  5100.0  343.75  5142.8  346.79  5145.2  347.44
#Mann=4,-1,0
  4831.8     0.1       0  4929.4    0.12       0  5005.3    0.07       0
  5009.3    0.12       0
Bank Sta=5005.3,5009.3
Exp/Cntr=0.3,0.1

Type RM Length L Ch R = 1,3517,264,264,264
BEGIN DESCRIPTION:
Lynn Creek T3 7.0
END DESCRIPTION:
XS GIS Cut Line= 3
      2718017.15      6781526.27      2718176.00      6781661.00
      2718278.17      6781695.09
#Sta/Elev= 30
  4796.3  343.76  4827.2  341.88  4841.5  342.51  4848.0  341.65  4870.0  340.40
  4876.6  339.44  4884.3  334.99  4898.6  328.80  4905.2  327.53  4933.7  328.12
  4954.6  327.15  4962.3  327.85  4986.2  326.20  4990.9  325.52  4995.4  323.95
  4995.7  323.45  4999.2  323.45  4999.4  323.95  5001.3  326.57  5007.2  326.57
  5015.1  328.73  5020.4  328.60  5025.7  332.38  5036.2  335.24  5052.0  337.71
  5057.3  339.46  5067.8  341.82  5078.3  342.30  5088.9  344.02  5112.3  345.49
#Mann=4,-1,0
  4796.3     0.1       0  4986.2    0.12       0  4995.4    0.07       0
  4999.4    0.12       0
Bank Sta=4995.4,4999.4
Exp/Cntr=0.3,0.1

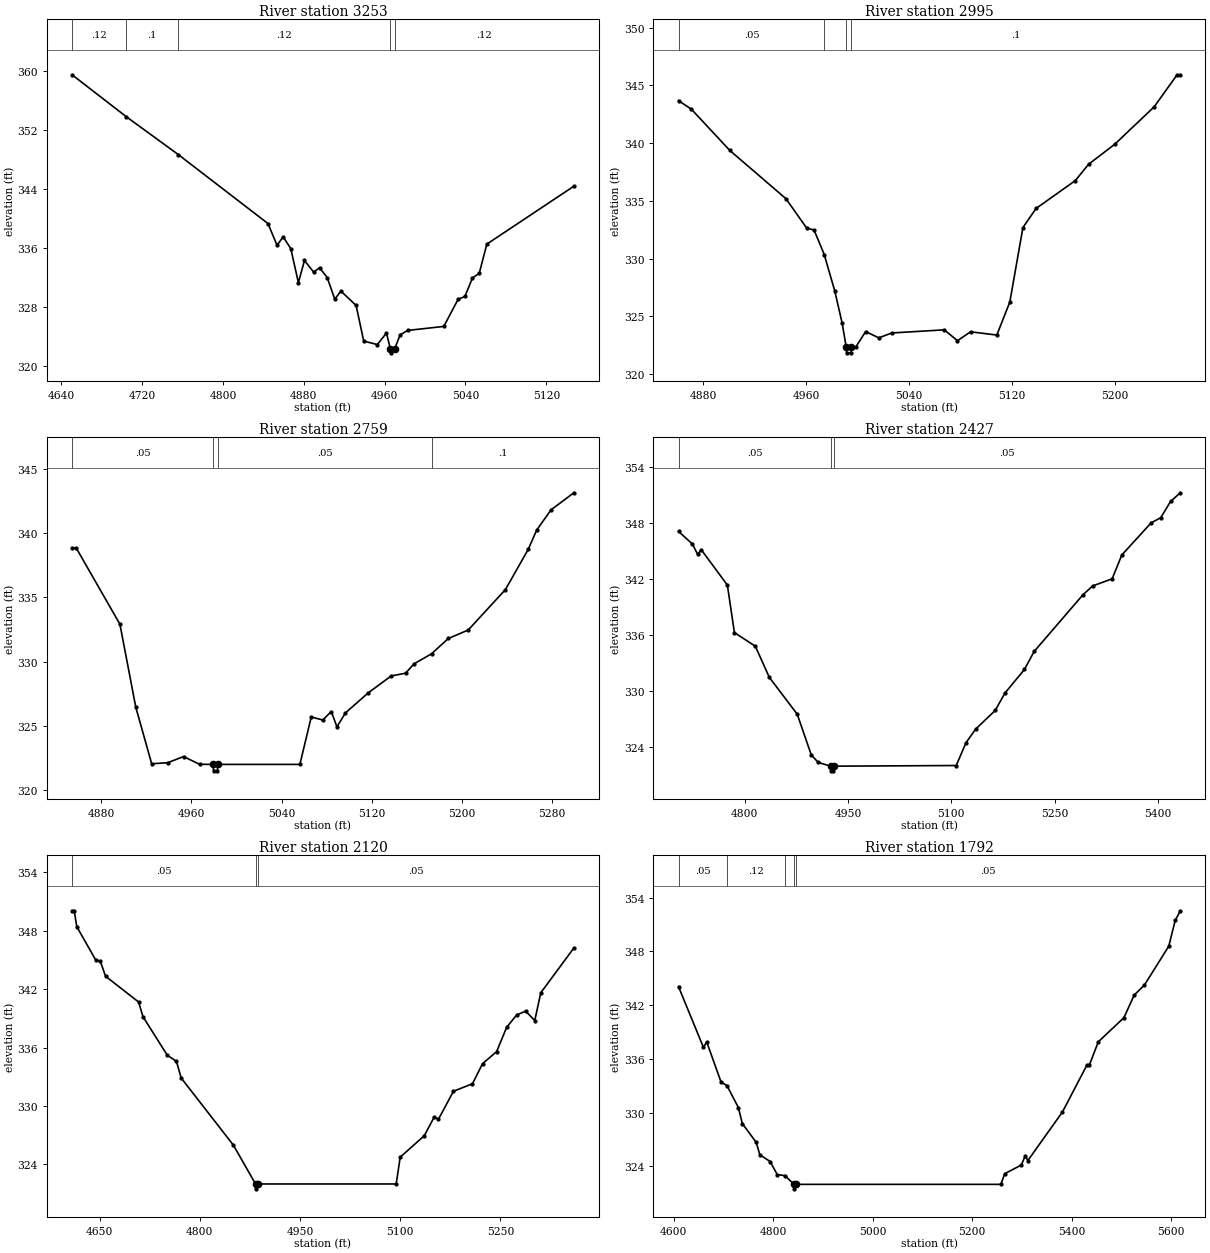
Type RM Length L Ch R = 1,3253,258,258,258
BEGIN DESCRIPTION:
Lynn Creek T3 6.0
END DESCRIPTION:
XS GIS Cut Line= 3
      2717775.98      6781660.99      2718076.00      6781861.00
      2718166.05      6781962.69
#Sta/Elev= 30
  4650.8  359.54  4704.3  353.87  4755.9  348.72  4844.6  339.37  4853.6  336.42
  4859.6  337.57  4867.2  335.96  4874.7  331.35  4880.7  334.36  4889.7  332.80
  4895.7  333.37  4903.2  332.05  4910.7  329.11  4916.7  330.21  4931.8  328.26
  4939.3  323.44  4952.8  322.96  4961.8  324.53  4965.8  322.34  4966.1  321.84
  4969.8  322.34  4975.3  324.27  4982.8  324.88  5018.5  325.42  5032.7  329.10
  5039.4  329.48  5046.9  332.00  5053.6  332.62  5061.1  336.58  5147.2  344.43
#Mann=5,-1,0
  4650.8    0.12       0  4704.3     0.1       0  4755.9    0.12       0
  4965.8    0.07       0  4969.8    0.12       0
Bank Sta=4965.8,4969.8
Exp/Cntr=0.3,0.1

Type RM Length L Ch R = 1,2995,236,236,236
BEGIN DESCRIPTION:
Lynn Creek T3 5.0
END DESCRIPTION:
XS GIS Cut Line= 3
      2717757.22      6781946.27      2717876.00      6782011.00
      2718125.98      6782061.00
#Sta/Elev= 30
  4860.7  343.67  4870.7  342.93  4900.6  339.36  4944.2  335.19  4960.4  332.64
  4966.1  332.48  4974.0  330.35  4982.2  327.20  4987.9  324.43  4991.1  322.35
  4991.4  321.85  4994.9  321.85  4995.1  322.35  4998.5  322.35  5006.2  323.69
  5016.4  323.15  5026.6  323.57  5067.4  323.84  5077.6  322.90  5087.8  323.67
  5108.2  323.39  5118.3  326.24  5128.5  332.69  5138.7  334.34  5169.3  336.76
  5179.5  338.16  5199.9  339.90  5230.5  343.13  5248.4  345.91  5250.9  345.91
#Mann=4,-1,0
  4860.7    0.05       0  4974.0     0.1       0  4991.1    0.07       0
  4995.1     0.1       0
Bank Sta=4991.1,4995.1
Exp/Cntr=0.3,0.1

Type RM Length L Ch R = 1,2759,332,332,332
BEGIN DESCRIPTION:
Lynn Creek T3 4.0
END DESCRIPTION:
XS GIS Cut Line= 3
      2717675.98      6782110.98      2717776.00      6782211.00
      2718076.01      6782161.00
#Sta/Elev= 30
  4854.0  338.84  4857.6  338.84  4896.5  332.90  4910.6  326.44  4924.7  322.05
  4938.9  322.13  4953.0  322.61  4967.2  322.01  4979.3  322.00  4979.6  321.50
  4983.1  321.50  4983.3  322.00  5056.3  322.00  5066.4  325.69  5076.6  325.45
  5084.2  326.11  5089.2  324.92  5096.8  326.01  5117.1  327.57  5137.4  328.88
  5150.1  329.09  5157.7  329.82  5173.2  330.60  5188.1  331.79  5205.8  332.45
  5238.8  335.59  5259.0  338.71  5266.6  340.22  5279.3  341.79  5299.6  343.12
#Mann=4,-1,0
  4854.0    0.05       0  4979.3    0.05       0  4983.3    0.05       0
  5173.2     0.1       0
Bank Sta=4979.3,4983.3
Exp/Cntr=0.3,0.1

Type RM Length L Ch R = 1,2427,307,307,307
BEGIN DESCRIPTION:
Lynn Creek T3 3.0
END DESCRIPTION:
XS GIS Cut Line= 3
      2717526.01      6782111.04      2717576.00      6782411.00
      2717876.03      6782711.03
#Sta/Elev= 30
  4704.0  347.08  4724.2  345.73  4731.8  344.61  4736.9  345.13  4774.9  341.33
  4785.1  336.24  4815.5  334.78  4835.8  331.44  4876.3  327.50  4896.6  323.15
  4906.7  322.33  4925.0  321.93  4925.2  321.43  4928.7  321.43  4929.0  321.93
  5107.1  322.00  5121.2  324.43  5135.4  325.91  5163.7  327.90  5177.8  329.76
  5206.1  332.29  5220.2  334.22  5290.9  340.28  5305.1  341.24  5333.4  342.00
  5347.5  344.56  5389.9  347.99  5404.1  348.56  5418.2  350.29  5432.4  351.22
#Mann=3,-1,0
  4704.0    0.05       0  4925.0    0.05       0  4929.0    0.05       0
Bank Sta=4925,4929
Exp/Cntr=0.3,0.1

Type RM Length L Ch R = 1,2120,328,328,328
BEGIN DESCRIPTION:
Lynn Creek T3 2.0
END DESCRIPTION:
XS GIS Cut Line= 3
      2717176.02      6782311.02      2717476.00      6782561.00
      2717775.97      6782760.98
#Sta/Elev= 30
  4608.9  350.05  4612.1  350.05  4616.0  348.41  4644.7  344.95  4651.2  344.87
  4659.0  343.33  4708.5  340.68  4715.0  339.18  4751.4  335.22  4765.1  334.59
  4772.2  332.88  4850.3  325.99  4883.5  322.00  4883.7  321.50  4887.5  322.00
  5094.0  322.00  5100.0  324.75  5136.1  326.96  5151.1  328.90  5157.1  328.63
  5179.7  331.52  5208.2  332.29  5223.2  334.35  5244.3  335.59  5259.3  338.08
  5274.3  339.36  5287.8  339.74  5301.4  338.78  5310.4  341.63  5359.9  346.23
#Mann=3,-1,0
  4608.9    0.05       0  4883.5    0.05       0  4887.5    0.05       0
Bank Sta=4883.5,4887.5
Exp/Cntr=0.3,0.1

Type RM Length L Ch R = 1,1792,0,0,0
BEGIN DESCRIPTION:
Lynn Creek T3 1.0
END DESCRIPTION:
XS GIS Cut Line= 3
      2716976.00      6782461.00      2717226.00      6782761.00
      2717826.02      6782911.01
#Sta/Elev= 30
  4609.7  344.06  4659.8  337.28  4666.3  337.90  4695.0  333.45  4707.3  333.00
  4730.1  330.56  4737.9  328.79  4765.9  326.69  4773.1  325.31  4793.9  324.55
  4808.2  323.09  4823.6  322.97  4842.0  322.00  4842.3  321.50  4846.0  322.00
  5257.9  322.00  5265.6  323.19  5299.1  324.16  5306.9  325.20  5312.0  324.65
  5381.6  330.07  5430.6  335.28  5435.7  335.30  5453.8  337.91  5505.3  340.60
  5525.9  343.12  5546.5  344.24  5595.5  348.58  5608.4  351.46  5618.7  352.53
#Mann=5,-1,0
  4609.7    0.05       0  4707.3    0.12       0  4823.6    0.05       0
  4842.0    0.03       0  4846.0    0.05       0
Bank Sta=4842,4846
Exp/Cntr=0.3,0.1

Chan Stop Cuts=-1