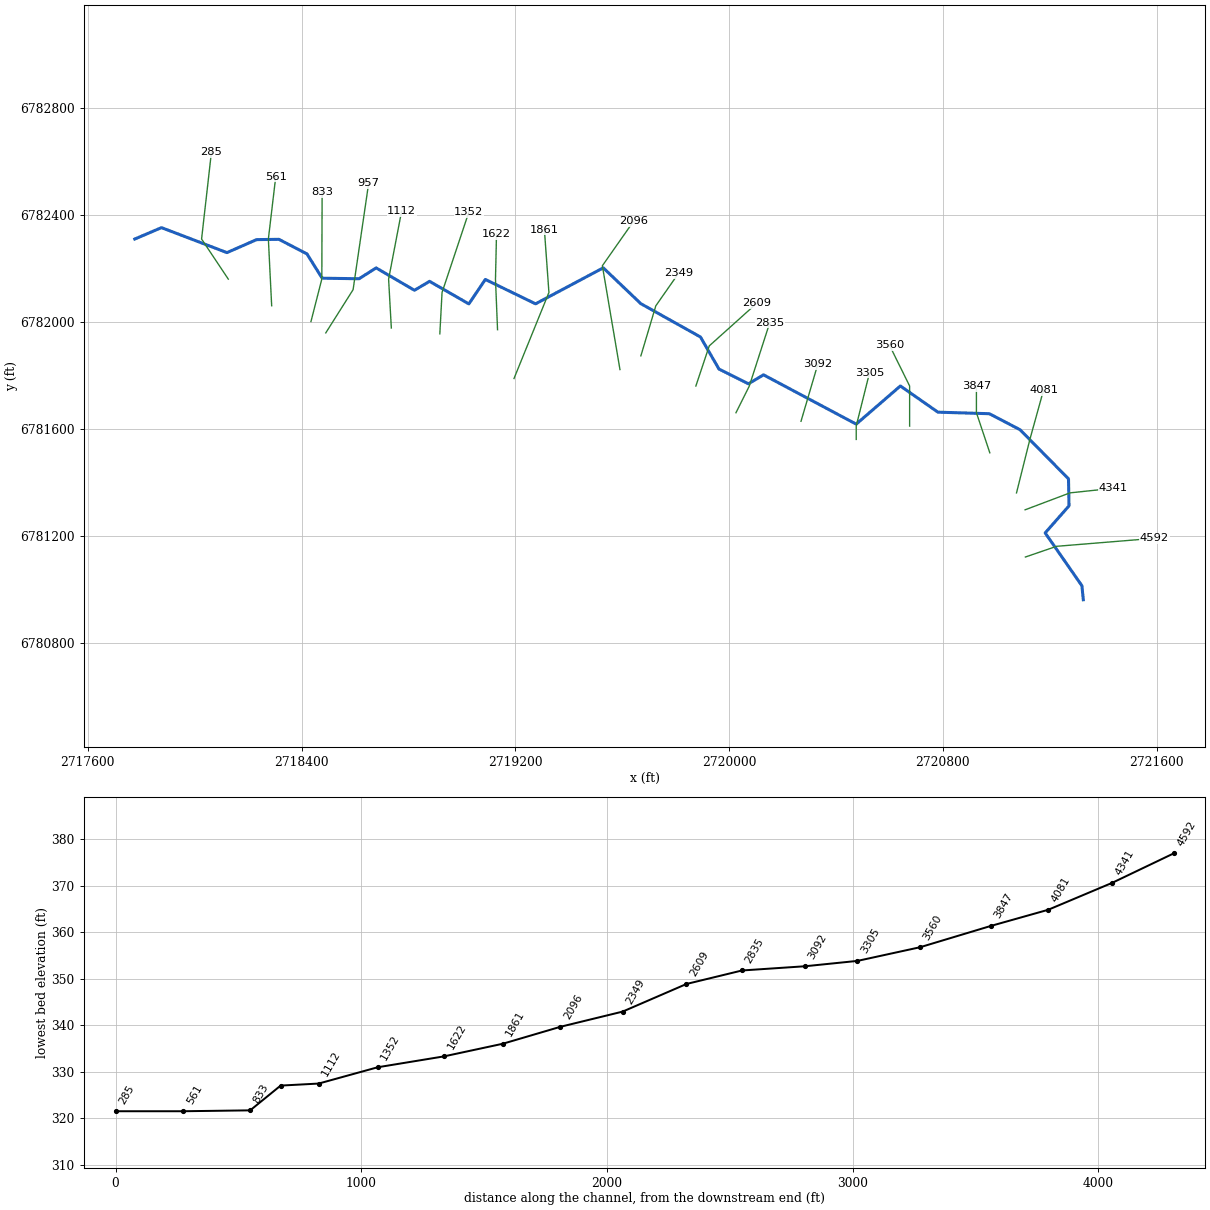
--- Lynn Creek T4.prj (project) ---

Proj Title=Lynn Creek T4 Base Level Engineering
Current Plan=p01
Default Exp/Contr=0.3,0.1
English Units
Geom File=g01
Flow File=f01
Plan File=p01
BEGIN DESCRIPTION:
Lynn Creek T4
END DESCRIPTION:

--- Lynn Creek T4.p01 (plan) ---

Plan Title=Multiple Run
Short Identifier=Multiple
Geom File=g01
Flow File=f01
Subcritical Flow
K Sum by GR= 0
Std Step Tol= 0.01
Critical Tol= 0.01
Num of Std Step Trials= 20
Max Error Tol= 0.3
Flow Tol Ratio= 0.001
Split Flow NTrial= 30
Split Flow Tol= 0.02
Split Flow Ratio= 0.02
Log Output Level= 0
Friction Slope Method= 1
Unsteady Friction Slope Method= 2
Unsteady Bridges Friction Slope Method= 1
Parabolic Critical Depth
Global Vel Dist=  1 , 1 , 1
Global Log Level= 0
CheckData=True
Encroach Param= -1, 0, 0, 0
BEGIN DESCRIPTION:
Multiple Run
END DESCRIPTION:

--- Lynn Creek T4.f01 (steady flow) ---

Flow Title=Multiple
Number of Profiles=7
Profile Names=10-year,25-year,50-year,1pct_min,100-year,1pct_plu,500-year
River Rch & RM= Lynn Creek T4,Reach-1,4592
     159     196     222     126     252     502     321
River Rch & RM= Lynn Creek T4,Reach-1,1861
     251     319     371     216     430     858     575
Boundary for River Rch & Prof#=Lynn Creek T4,Reach-1,1
Up Type=0
Dn Type=3
Dn Slope=0.005
Boundary for River Rch & Prof#=Lynn Creek T4,Reach-1,2
Up Type=0
Dn Type=3
Dn Slope=0.005
Boundary for River Rch & Prof#=Lynn Creek T4,Reach-1,3
Up Type=0
Dn Type=3
Dn Slope=0.005
Boundary for River Rch & Prof#=Lynn Creek T4,Reach-1,4
Up Type=0
Dn Type=3
Dn Slope=0.005
Boundary for River Rch & Prof#=Lynn Creek T4,Reach-1,5
Up Type=0
Dn Type=3
Dn Slope=0.005
Boundary for River Rch & Prof#=Lynn Creek T4,Reach-1,6
Up Type=0
Dn Type=3
Dn Slope=0.005
Boundary for River Rch & Prof#=Lynn Creek T4,Reach-1,7
Up Type=0
Dn Type=3
Dn Slope=0.005

--- Lynn Creek T4.g01 (geometry) ---

Geom Title=Existing Conditions

River Reach=Lynn Creek T4,Reach-1
Reach XY= 30
      2721326.00      6780961.00      2721320.67      6781013.51
      2721183.30      6781211.08      2721272.52      6781312.50
      2721270.60      6781413.43      2721089.22      6781597.38
      2720974.45      6781657.25      2720781.86      6781663.07
      2720641.36      6781761.11      2720476.09      6781618.29
      2720129.23      6781802.76      2720072.76      6781769.24
      2719962.44      6781824.46      2719893.05      6781944.50
      2719669.95      6782069.16      2719529.41      6782203.23
      2719276.00      6782068.50      2719088.01      6782159.79
      2719026.29      6782068.23      2718879.23      6782152.76
      2718822.77      6782119.24      2718679.32      6782202.96
      2718615.56      6782162.37      2718477.27      6782164.47
      2718420.38      6782255.38      2718315.47      6782309.92
      2718231.98      6782308.83      2718120.97      6782260.19
      2717875.96      6782353.69      2717776.00      6782311.00

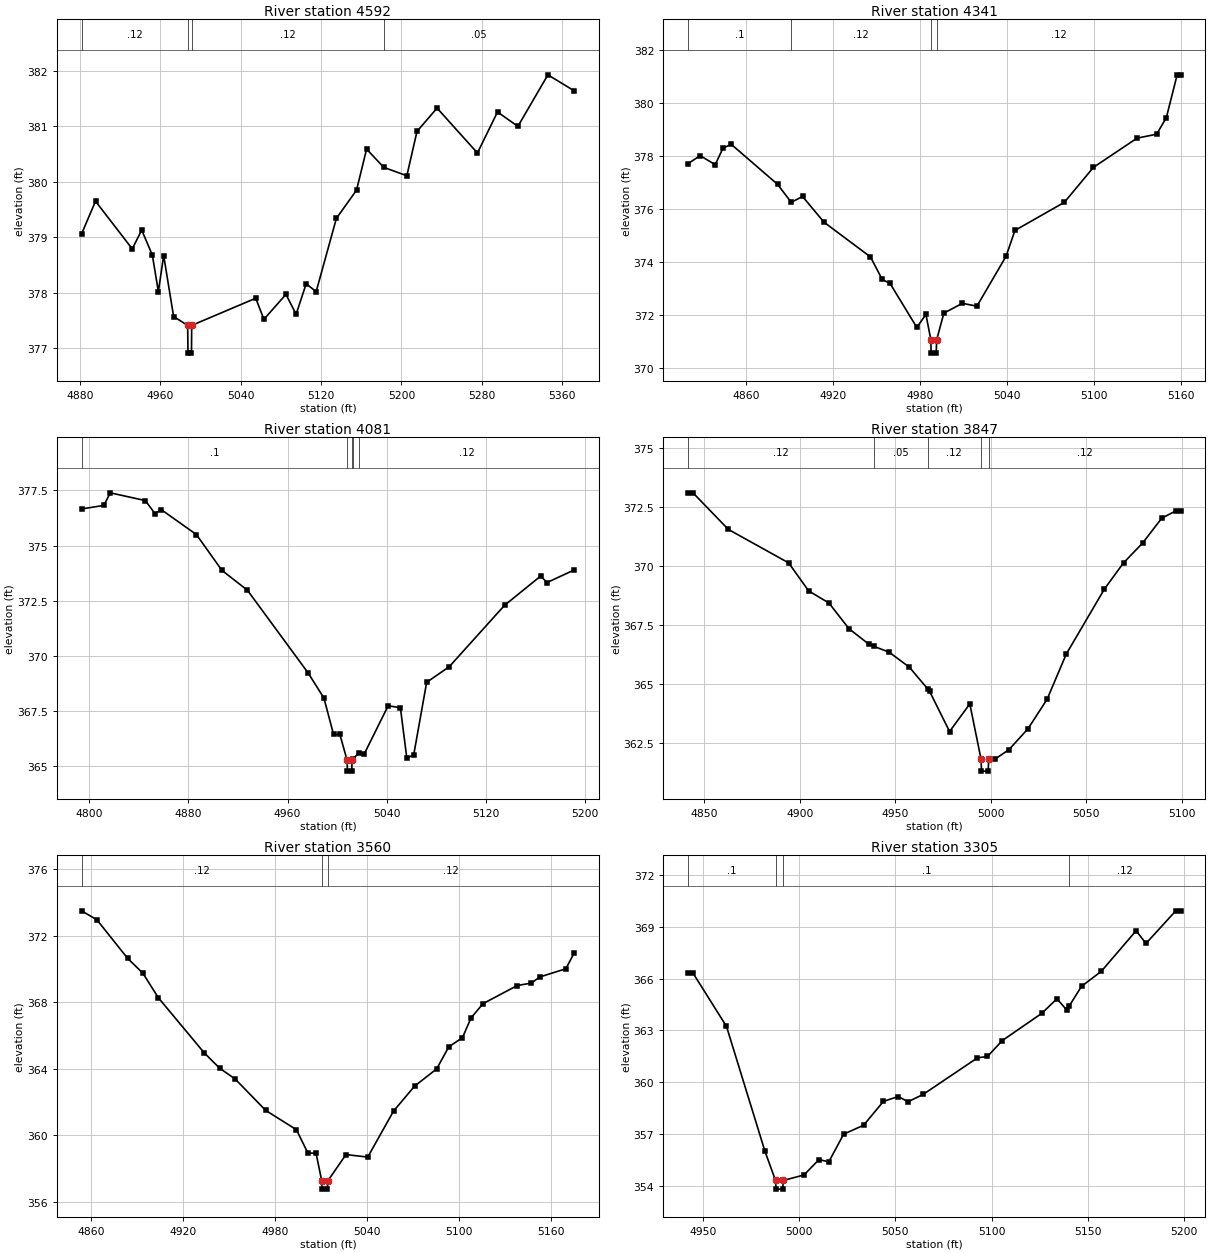
Type RM Length L Ch R = 1,4592,251,251,251
BEGIN DESCRIPTION:
Lynn Creek T4 18.0
END DESCRIPTION:
XS GIS Cut Line= 3
      2721109.30      6781120.97      2721226.00      6781161.00
      2721592.20      6781190.98
#Sta/Elev= 30
  4881.4  379.06  4895.3  379.65  4931.9  378.79  4941.3  379.13  4951.9  378.68
  4957.9  378.02  4963.2  378.67  4973.1  377.57  4987.1  377.41  4987.4  376.91
  4990.9  376.91  4991.1  377.41  5054.9  377.90  5063.0  377.52  5085.0  377.97
  5095.1  377.61  5105.1  378.16  5115.1  378.02  5135.2  379.34  5155.3  379.85
  5165.3  380.59  5182.5  380.26  5205.4  380.11  5215.5  380.91  5235.5  381.33
  5275.7  380.52  5295.7  381.26  5316.0  381.00  5345.9  381.93  5372.2  381.64
#Mann=4,-1,0
  4881.4    0.12       0  4987.1    0.07       0  4991.1    0.12       0
  5182.5    0.05       0
Bank Sta=4987.1,4991.1
Exp/Cntr=0.3,0.1

Type RM Length L Ch R = 1,4341,260,260,260
BEGIN DESCRIPTION:
Lynn Creek T4 17.0
END DESCRIPTION:
XS GIS Cut Line= 3
      2721108.16      6781297.59      2721276.00      6781361.00
      2721435.99      6781377.93
#Sta/Elev= 30
  4819.7  377.72  4828.1  378.02  4838.5  377.68  4843.8  378.30  4849.5  378.45
  4881.5  376.94  4891.0  376.26  4898.8  376.48  4913.6  375.51  4945.7  374.20
  4953.8  373.35  4959.2  373.20  4977.7  371.54  4984.0  372.03  4987.4  371.07
  4987.6  370.57  4991.1  370.57  4991.4  371.07  4996.4  372.08  5009.2  372.45
  5019.2  372.34  5039.3  374.22  5045.5  375.20  5079.6  376.26  5099.7  377.58
  5129.8  378.68  5143.3  378.83  5150.0  379.45  5157.5  381.07  5160.0  381.07
#Mann=4,-1,0
  4819.7     0.1       0  4891.0    0.12       0  4987.4    0.07       0
  4991.4    0.12       0
Bank Sta=4987.4,4991.4
Exp/Cntr=0.3,0.1

Type RM Length L Ch R = 1,4081,234,234,234
BEGIN DESCRIPTION:
Lynn Creek T4 16.0
END DESCRIPTION:
XS GIS Cut Line= 3
      2721076.00      6781361.00      2721126.00      6781561.00
      2721177.24      6781745.98
#Sta/Elev= 30
  4793.6  376.66  4811.6  376.82  4816.8  377.39  4845.1  377.04  4852.9  376.45
  4858.0  376.63  4886.4  375.50  4907.0  373.88  4927.6  372.98  4976.6  369.24
  4989.4  368.10  4997.2  366.45  5002.3  366.45  5008.1  365.29  5008.4  364.79
  5011.9  364.79  5012.1  365.29  5013.0  365.35  5017.6  365.61  5022.1  365.58
  5041.3  367.75  5051.2  367.66  5056.4  365.37  5062.0  365.54  5072.4  368.81
  5090.7  369.52  5135.4  372.30  5164.5  373.62  5169.7  373.33  5191.7  373.90
#Mann=5,-1,0
  4793.6     0.1       0  5008.1    0.07       0  5012.1     0.1       0
  5013.0    0.05       0  5017.6    0.12       0
Bank Sta=5008.1,5012.1
Exp/Cntr=0.3,0.1

Type RM Length L Ch R = 1,3847,287,287,287
BEGIN DESCRIPTION:
Lynn Creek T4 15.0
END DESCRIPTION:
XS GIS Cut Line= 3
      2720976.00      6781511.01      2720926.00      6781661.00
      2720926.00      6781760.99
#Sta/Elev= 30
  4841.5  373.11  4844.1  373.11  4862.6  371.56  4894.2  370.14  4904.7  368.95
  4915.3  368.44  4925.8  367.35  4936.4  366.68  4938.9  366.60  4946.9  366.35
  4957.4  365.72  4967.0  364.80  4968.0  364.70  4978.5  362.99  4989.1  364.16
  4995.0  361.81  4995.2  361.31  4998.7  361.31  4999.0  361.81  5002.1  361.81
  5009.6  362.22  5019.6  363.11  5029.6  364.36  5039.6  366.27  5059.6  369.03
  5069.6  370.14  5079.6  370.98  5089.6  372.03  5097.1  372.35  5099.6  372.35
#Mann=5,-1,0
  4841.5    0.12       0  4938.9    0.05       0  4967.0    0.12       0
  4995.0    0.07       0  4999.0    0.12       0
Bank Sta=4995,4999
Exp/Cntr=0.3,0.1

Type RM Length L Ch R = 1,3560,255,255,255
BEGIN DESCRIPTION:
Lynn Creek T4 14.0
END DESCRIPTION:
XS GIS Cut Line= 3
      2720676.00      6781610.96      2720676.00      6781761.00
      2720600.22      6781914.36
#Sta/Elev= 30
  4853.9  373.51  4863.9  372.97  4883.9  370.65  4893.9  369.75  4903.9  368.28
  4933.9  364.95  4943.9  364.03  4953.9  363.39  4973.9  361.49  4993.9  360.33
  5001.4  358.92  5006.7  358.92  5010.4  357.25  5010.6  356.75  5014.1  356.75
  5014.4  357.25  5026.2  358.83  5040.4  358.68  5057.2  361.45  5070.9  362.95
  5085.3  363.99  5093.2  365.32  5102.1  365.87  5107.7  367.06  5115.5  367.92
  5137.8  369.01  5147.0  369.16  5152.6  369.53  5169.5  370.02  5175.0  370.99
#Mann=3,-1,0
  4853.9    0.12       0  5010.4    0.07       0  5014.4    0.12       0
Bank Sta=5010.4,5014.4
Exp/Cntr=0.3,0.1

Type RM Length L Ch R = 1,3305,213,213,213
BEGIN DESCRIPTION:
Lynn Creek T4 13.0
END DESCRIPTION:
XS GIS Cut Line= 3
      2720476.00      6781560.98      2720476.00      6781611.00
      2720526.01      6781811.02
#Sta/Elev= 30
  4942.2  366.33  4944.7  366.33  4962.2  363.23  4982.2  356.00  4987.7  354.31
  4988.0  353.81  4991.5  353.81  4991.7  354.31  5002.5  354.63  5010.3  355.52
  5015.4  355.39  5023.1  356.99  5033.5  357.51  5043.8  358.89  5051.5  359.17
  5056.6  358.87  5064.4  359.29  5092.7  361.41  5097.9  361.49  5105.6  362.41
  5126.2  363.99  5134.0  364.83  5139.1  364.18  5140.5  364.43  5146.8  365.55
  5157.1  366.42  5175.2  368.77  5180.3  368.03  5195.8  369.92  5198.4  369.92
#Mann=4,-1,0
  4942.2     0.1       0  4987.7    0.07       0  4991.7     0.1       0
  5140.5    0.12       0
Bank Sta=4987.7,4991.7
Exp/Cntr=0.3,0.1

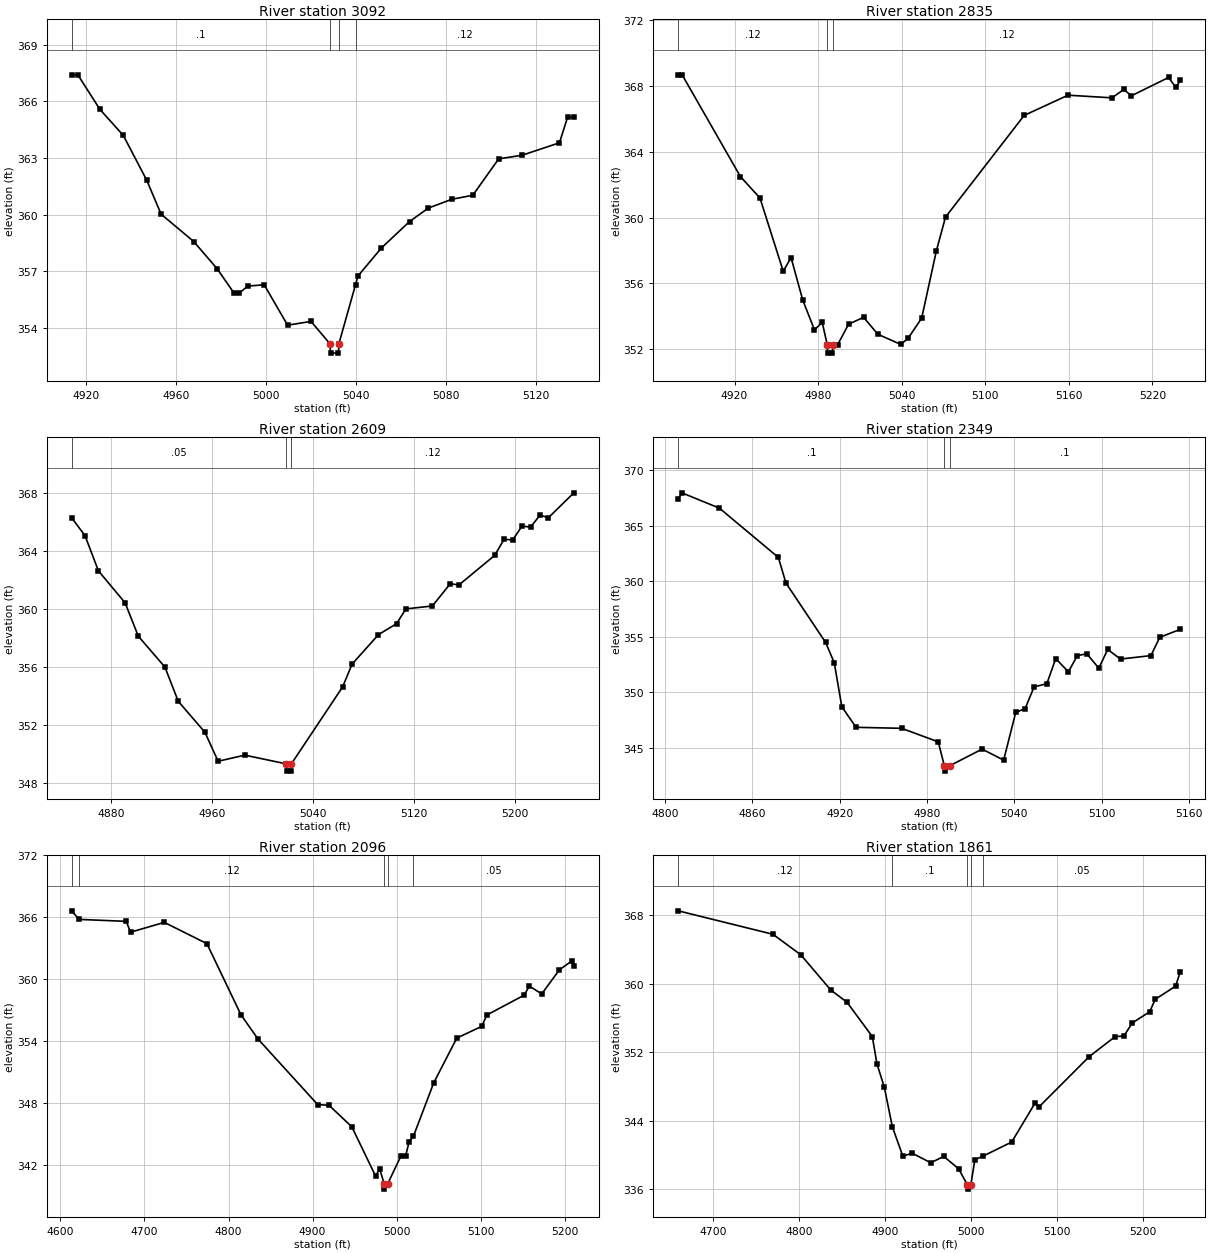
Type RM Length L Ch R = 1,3092,257,257,257
BEGIN DESCRIPTION:
Lynn Creek T4 12.0
END DESCRIPTION:
XS GIS Cut Line= 3
      2720269.46      6781629.02      2720290.49      6781700.34
      2720332.55      6781843.02
#Sta/Elev= 30
  4913.8  367.40  4916.5  367.40  4926.3  365.57  4936.7  364.19  4947.1  361.82
  4953.5  360.02  4968.0  358.57  4978.4  357.13  4985.9  355.84  4988.2  355.84
  4992.0  356.21  4999.3  356.28  5009.7  354.14  5020.1  354.34  5028.5  353.16
  5028.8  352.66  5032.3  352.66  5032.5  353.16  5039.9  356.29  5041.0  356.75
  5051.4  358.23  5063.9  359.63  5072.2  360.34  5082.7  360.81  5092.0  361.02
  5103.5  362.95  5113.9  363.14  5130.5  363.80  5134.1  365.15  5136.9  365.15
#Mann=4,-1,0
  4913.8     0.1       0  5028.5    0.07       0  5032.5     0.1       0
  5039.9    0.12       0
Bank Sta=5028.5,5032.5
Exp/Cntr=0.3,0.1

Type RM Length L Ch R = 1,2835,226,226,226
BEGIN DESCRIPTION:
Lynn Creek T4 11.0
END DESCRIPTION:
XS GIS Cut Line= 3
      2720026.01      6781661.02      2720076.00      6781761.00
      2720152.41      6781997.69
#Sta/Elev= 30
  4879.6  368.69  4882.4  368.69  4924.3  362.49  4938.3  361.19  4955.0  356.73
  4960.6  357.57  4969.0  354.98  4977.4  353.17  4983.0  353.62  4986.6  352.25
  4986.8  351.75  4990.3  351.75  4990.6  352.25  4994.0  352.25  5001.9  353.51
  5012.7  353.93  5022.9  352.90  5039.4  352.28  5044.7  352.66  5054.4  353.88
  5064.9  357.96  5071.5  360.03  5128.0  366.22  5159.5  367.45  5191.0  367.29
  5199.6  367.80  5204.9  367.41  5231.7  368.53  5236.9  367.92  5240.1  368.35
#Mann=3,-1,0
  4879.6    0.12       0  4986.6    0.07       0  4990.6    0.12       0
Bank Sta=4986.6,4990.6
Exp/Cntr=0.3,0.1

Type RM Length L Ch R = 1,2609,260,260,260
BEGIN DESCRIPTION:
Lynn Creek T4 10.0
END DESCRIPTION:
XS GIS Cut Line= 3
      2719876.00      6781761.01      2719926.00      6781911.00
      2720104.22      6782070.98
#Sta/Elev= 30
  4849.1  366.28  4859.6  365.06  4870.2  362.64  4891.3  360.44  4901.8  358.14
  4922.9  356.01  4933.4  353.66  4954.5  351.53  4965.0  349.53  4986.1  349.95
  5019.0  349.35  5019.3  348.85  5022.8  348.85  5023.0  349.35  5063.6  354.65
  5071.1  356.22  5092.0  358.25  5106.3  359.00  5113.7  360.02  5134.7  360.22
  5148.9  361.76  5155.6  361.66  5184.0  363.70  5191.5  364.82  5198.2  364.76
  5205.7  365.72  5212.4  365.65  5219.9  366.47  5226.6  366.30  5246.7  368.01
#Mann=3,-1,0
  4849.1    0.05       0  5019.0    0.03       0  5023.0    0.12       0
Bank Sta=5019,5023
Exp/Cntr=0.3,0.1

Type RM Length L Ch R = 1,2349,253,253,253
BEGIN DESCRIPTION:
Lynn Creek T4 9.0
END DESCRIPTION:
XS GIS Cut Line= 3
      2719670.19      6781873.88      2719726.00      6782061.00
      2719811.75      6782183.75
#Sta/Elev= 30
  4809.1  367.38  4811.6  367.94  4837.4  366.56  4877.9  362.13  4883.1  359.83
  4910.4  354.48  4916.3  352.66  4921.5  348.70  4931.3  346.85  4962.6  346.76
  4987.8  345.54  4991.9  343.41  4992.2  342.91  4995.9  343.41  5017.9  344.89
  5032.7  343.90  5041.0  348.19  5047.5  348.54  5053.6  350.48  5062.4  350.78
  5068.5  353.03  5077.2  351.84  5083.3  353.29  5089.8  353.47  5098.1  352.17
  5104.2  353.85  5113.0  352.99  5133.9  353.30  5140.0  354.95  5154.1  355.66
#Mann=3,-1,0
  4809.1     0.1       0  4991.9    0.07       0  4995.9     0.1       0
Bank Sta=4991.9,4995.9
Exp/Cntr=0.3,0.1

Type RM Length L Ch R = 1,2096,235,235,235
BEGIN DESCRIPTION:
Lynn Creek T4 8.0
END DESCRIPTION:
XS GIS Cut Line= 3
      2719591.92      6781822.49      2719526.00      6782211.00
      2719642.75      6782377.48
#Sta/Elev= 30
  4613.5  366.61  4622.0  365.78  4678.3  365.59  4683.4  364.54  4723.6  365.49
  4774.3  363.43  4814.8  356.54  4835.1  354.19  4906.1  347.84  4919.6  347.77
  4946.7  345.69  4974.9  340.93  4979.9  341.59  4985.3  340.15  4985.5  339.65
  4989.3  340.15  5005.0  342.83  5010.6  342.83  5015.0  344.26  5020.1  344.79
  5044.2  349.95  5071.6  354.28  5101.3  355.42  5107.4  356.52  5151.8  358.44
  5157.9  359.32  5172.7  358.56  5193.7  360.90  5208.5  361.75  5210.9  361.31
#Mann=5,-1,0
  4613.5    0.05       0  4622.0    0.12       0  4985.3    0.07       0
  4989.3    0.12       0  5020.1    0.05       0
Bank Sta=4985.3,4989.3
Exp/Cntr=0.3,0.1

Type RM Length L Ch R = 1,1861,239,239,239
BEGIN DESCRIPTION:
Lynn Creek T4 7.0
END DESCRIPTION:
XS GIS Cut Line= 3
      2719195.33      6781789.03      2719326.00      6782111.00
      2719309.01      6782346.51
#Sta/Elev= 30
  4659.7  368.51  4769.8  365.77  4802.1  363.38  4837.1  359.25  4855.8  357.84
  4885.3  353.82  4890.7  350.62  4899.3  347.89  4908.5  343.31  4920.8  339.84
  4931.6  340.20  4953.2  339.08  4968.3  339.82  4985.6  338.38  4995.8  336.50
  4996.1  336.00  4999.8  336.50  5004.5  339.44  5014.5  339.88  5047.3  341.50
  5074.5  346.06  5079.5  345.65  5137.5  351.49  5167.6  353.82  5177.6  353.88
  5187.6  355.42  5207.7  356.72  5214.2  358.18  5237.8  359.71  5243.3  361.40
#Mann=5,-1,0
  4659.7    0.12       0  4908.5     0.1       0  4995.8    0.07       0
  4999.8     0.1       0  5014.5    0.05       0
Bank Sta=4995.8,4999.8
Exp/Cntr=0.3,0.1

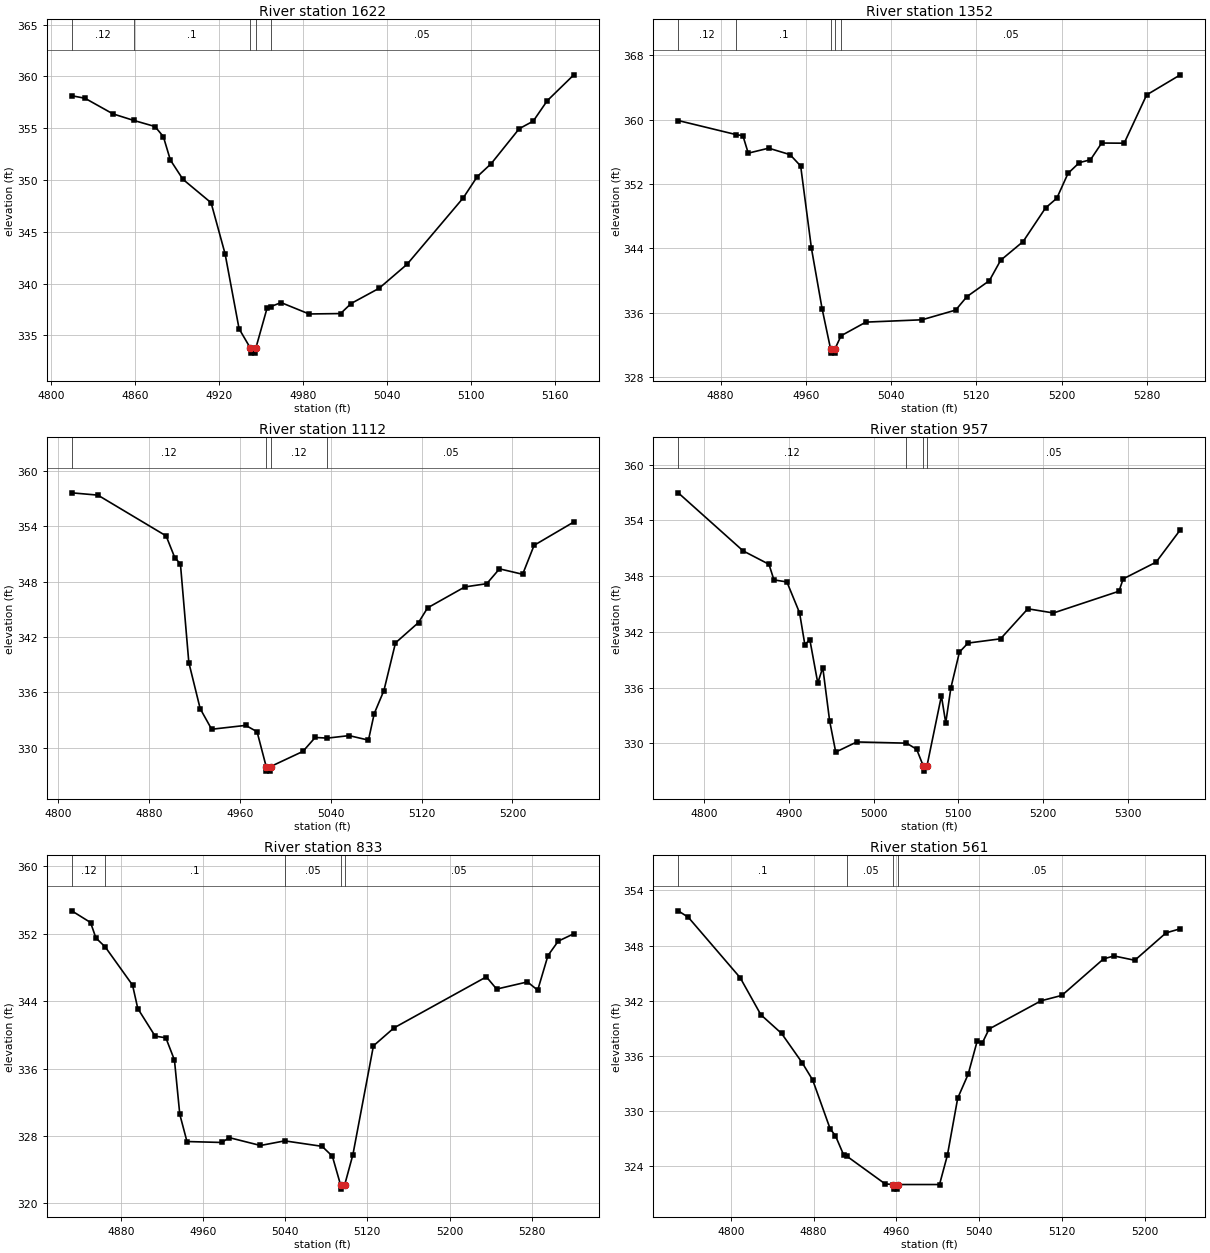
Type RM Length L Ch R = 1,1622,270,270,270
BEGIN DESCRIPTION:
Lynn Creek T4 6.0
END DESCRIPTION:
XS GIS Cut Line= 3
      2719133.70      6781971.63      2719126.00      6782161.00
      2719129.83      6782330.03
#Sta/Elev= 30
  4814.8  358.14  4824.2  357.90  4844.2  356.39  4859.0  355.76  4874.2  355.17
  4880.2  354.20  4885.2  351.94  4894.2  350.07  4914.3  347.81  4924.3  342.88
  4934.3  335.64  4942.3  333.79  4942.5  333.29  4946.0  333.29  4946.3  333.79
  4954.3  337.64  4956.9  337.78  4964.3  338.17  4984.3  337.07  5006.8  337.11
  5014.3  338.08  5034.3  339.55  5054.3  341.87  5094.4  348.28  5104.4  350.33
  5114.4  351.59  5134.4  354.96  5144.4  355.69  5154.4  357.66  5173.4  360.16
#Mann=5,-1,0
  4814.8    0.12       0  4859.0     0.1       0  4942.3    0.03       0
  4946.3     0.1       0  4956.9    0.05       0
Bank Sta=4942.3,4946.3
Exp/Cntr=0.3,0.1

Type RM Length L Ch R = 1,1352,240,240,240
BEGIN DESCRIPTION:
Lynn Creek T4 5.0
END DESCRIPTION:
XS GIS Cut Line= 3
      2718917.71      6781956.22      2718926.00      6782111.00
      2719025.99      6782410.97
#Sta/Elev= 30
  4840.3  359.90  4894.9  358.14  4901.0  358.01  4906.0  355.84  4925.2  356.46
  4945.2  355.66  4955.2  354.24  4965.3  344.01  4975.3  336.49  4983.3  331.45
  4983.5  330.95  4987.0  330.95  4987.3  331.45  4993.1  333.11  5016.4  334.81
  5069.1  335.10  5100.7  336.31  5111.2  337.98  5132.3  339.97  5142.9  342.51
  5164.0  344.84  5185.0  349.02  5195.6  350.23  5206.1  353.32  5216.7  354.66
  5227.2  355.02  5237.7  357.10  5258.8  357.08  5279.9  363.09  5311.5  365.59
#Mann=5,-1,0
  4840.3    0.12       0  4894.9     0.1       0  4983.3    0.03       0
  4987.3     0.1       0  4993.1    0.05       0
Bank Sta=4983.3,4987.3
Exp/Cntr=0.3,0.1

Type RM Length L Ch R = 1,1112,155,155,155
BEGIN DESCRIPTION:
Lynn Creek T4 4.0
END DESCRIPTION:
XS GIS Cut Line= 3
      2718736.19      6781978.03      2718726.00      6782161.00
      2718774.66      6782415.34
#Sta/Elev= 30
  4811.9  357.62  4834.9  357.37  4895.0  352.95  4902.6  350.60  4907.6  349.91
  4915.0  339.22  4925.0  334.22  4935.1  331.99  4965.1  332.41  4975.1  331.72
  4983.1  327.95  4983.4  327.45  4986.9  327.45  4987.1  327.95  5015.5  329.59
  5026.3  331.10  5037.1  331.03  5056.2  331.30  5073.2  330.81  5078.3  333.69
  5086.8  336.18  5097.0  341.35  5117.3  343.56  5125.3  345.15  5158.1  347.42
  5177.4  347.77  5188.6  349.38  5209.0  348.79  5219.1  351.93  5254.1  354.46
#Mann=4,-1,0
  4811.9    0.12       0  4983.1    0.07       0  4987.1    0.12       0
  5037.1    0.05       0
Bank Sta=4983.1,4987.1
Exp/Cntr=0.3,0.1

Type RM Length L Ch R = 1,957,124,124,124
BEGIN DESCRIPTION:
Mapping XS edd7cb26
END DESCRIPTION:
XS GIS Cut Line= 3
      2718490.88      6781959.82      2718593.09      6782121.47
      2718651.28      6782519.28
#Sta/Elev= 30
  4769.0  356.96  4845.7  350.71  4876.2  349.27  4882.1  347.59  4897.4  347.37
  4912.4  344.04  4918.6  340.63  4924.5  341.16  4933.9  336.49  4939.8  338.16
  4947.9  332.42  4955.1  329.06  4980.0  330.15  5038.7  330.02  5050.7  329.37
  5058.8  327.51  5059.1  327.01  5062.8  327.51  5080.0  335.11  5085.1  332.20
  5091.2  335.98  5101.3  339.82  5111.4  340.79  5149.9  341.25  5182.1  344.48
  5212.4  344.03  5289.8  346.37  5294.8  347.70  5333.7  349.50  5362.3  352.98
#Mann=4,-1,0
  4769.0    0.12       0  5038.7    0.05       0  5058.8    0.07       0
  5062.8    0.05       0
Bank Sta=5058.8,5062.8
Exp/Cntr=0.3,0.1

Type RM Length L Ch R = 1,833,272,272,272
BEGIN DESCRIPTION:
Lynn Creek T4 3.0
END DESCRIPTION:
XS GIS Cut Line= 3
      2718435.42      6782002.28      2718476.00      6782161.00
      2718477.20      6782486.17
#Sta/Elev= 30
  4832.1  354.73  4850.4  353.34  4855.6  351.51  4864.7  350.44  4891.3  345.91
  4896.4  343.13  4913.3  339.85  4923.7  339.66  4932.1  337.02  4937.3  330.57
  4944.3  327.34  4978.1  327.23  4985.6  327.80  5015.9  326.87  5039.5  327.42
  5075.9  326.77  5085.9  325.60  5093.9  322.19  5094.2  321.69  5097.9  322.19
  5105.9  325.78  5125.9  338.70  5145.9  340.83  5235.9  346.89  5245.9  345.44
  5275.9  346.29  5285.9  345.31  5295.9  349.42  5305.9  351.13  5321.1  352.01
#Mann=5,-1,0
  4832.1    0.12       0  4864.7     0.1       0  5039.5    0.05       0
  5093.9    0.07       0  5097.9    0.05       0
Bank Sta=5093.9,5097.9
Exp/Cntr=0.3,0.1

Type RM Length L Ch R = 1,561,276,276,276
BEGIN DESCRIPTION:
Lynn Creek T4 2.0
END DESCRIPTION:
XS GIS Cut Line= 3
      2718288.34      6782061.20      2718276.00      6782311.00
      2718303.66      6782544.66
#Sta/Elev= 30
  4749.1  351.78  4758.9  351.07  4809.0  344.50  4829.0  340.47  4849.0  338.44
  4869.0  335.24  4879.1  333.37  4896.0  328.05  4901.0  327.33  4909.1  325.20
  4912.4  325.06  4949.1  322.07  4957.2  322.00  4957.4  321.50  4960.9  321.50
  4961.2  322.00  5001.7  322.00  5009.3  325.18  5019.3  331.40  5029.4  334.00
  5038.1  337.60  5043.1  337.41  5049.6  338.92  5099.9  341.99  5120.0  342.58
  5160.3  346.55  5170.4  346.87  5190.5  346.40  5220.7  349.38  5234.5  349.83
#Mann=4,-1,0
  4749.1     0.1       0  4912.4    0.05       0  4957.2    0.03       0
  4961.2    0.05       0
Bank Sta=4957.2,4961.2
Exp/Cntr=0.3,0.1

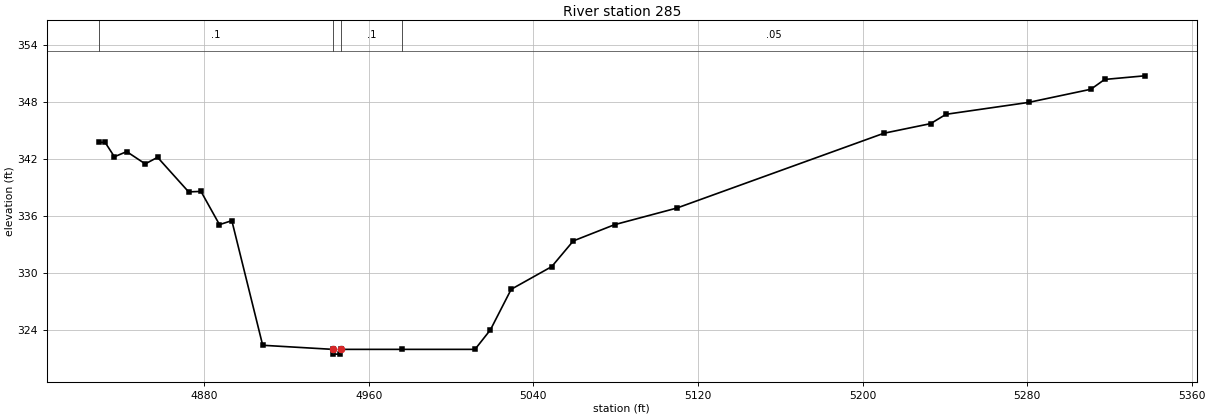
Type RM Length L Ch R = 1,285,0,0,0
BEGIN DESCRIPTION:
Lynn Creek T4 1.0
END DESCRIPTION:
XS GIS Cut Line= 3
      2718126.00      6782161.00      2718026.00      6782311.00
      2718063.00      6782636.92
#Sta/Elev= 30
  4828.8  343.74  4831.8  343.74  4836.3  342.23  4842.3  342.77  4851.3  341.48
  4857.3  342.17  4872.4  338.54  4878.4  338.59  4887.4  335.10  4893.4  335.52
  4908.4  322.43  4942.5  322.00  4942.7  321.50  4946.2  321.50  4946.5  322.00
  4976.2  322.00  5011.6  322.00  5019.1  324.05  5029.2  328.31  5048.9  330.69
  5059.4  333.39  5079.5  335.10  5109.7  336.84  5210.4  344.70  5233.1  345.71
  5240.6  346.69  5280.8  347.94  5311.0  349.32  5317.7  350.35  5337.1  350.73
#Mann=4,-1,0
  4828.8     0.1       0  4942.5    0.05       0  4946.5     0.1       0
  4976.2    0.05       0
Bank Sta=4942.5,4946.5
Exp/Cntr=0.3,0.1

Chan Stop Cuts=-1