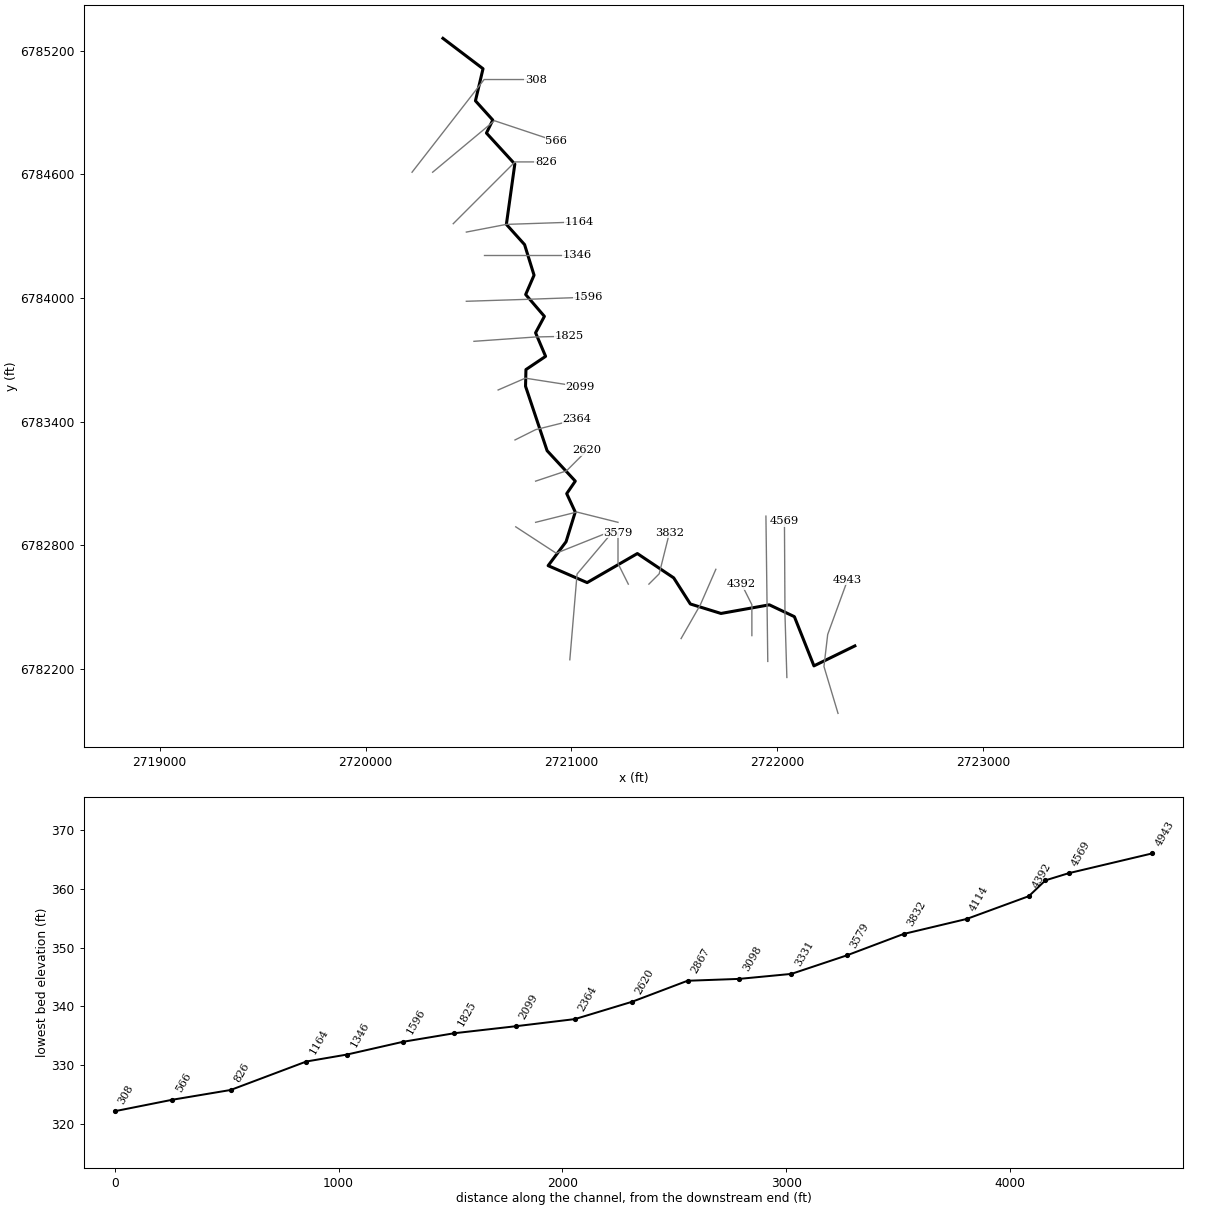
--- Lynn Creek T5.prj (project) ---

Proj Title=Lynn Creek T5 Base Level Engineering
Current Plan=p01
Default Exp/Contr=0.3,0.1
English Units
Geom File=g01
Flow File=f01
Plan File=p01
BEGIN DESCRIPTION:
Lynn Creek T5
END DESCRIPTION:

--- Lynn Creek T5.p01 (plan) ---

Plan Title=Multiple Run
Short Identifier=Multiple
Geom File=g01
Flow File=f01
Subcritical Flow
K Sum by GR= 0
Std Step Tol= 0.01
Critical Tol= 0.01
Num of Std Step Trials= 20
Max Error Tol= 0.3
Flow Tol Ratio= 0.001
Split Flow NTrial= 30
Split Flow Tol= 0.02
Split Flow Ratio= 0.02
Log Output Level= 0
Friction Slope Method= 1
Unsteady Friction Slope Method= 2
Unsteady Bridges Friction Slope Method= 1
Parabolic Critical Depth
Global Vel Dist=  1 , 1 , 1
Global Log Level= 0
CheckData=True
Encroach Param= -1, 0, 0, 0
BEGIN DESCRIPTION:
Multiple Run
END DESCRIPTION:

--- Lynn Creek T5.f01 (steady flow) ---

Flow Title=Multiple
Number of Profiles=7
Profile Names=10-year,25-year,50-year,1pct_min,100-year,1pct_plu,500-year
River Rch & RM= Lynn Creek T5,Reach-1,4943
     281     360     421     245     489     975     657
Boundary for River Rch & Prof#=Lynn Creek T5,Reach-1,1
Up Type=0
Dn Type=3
Dn Slope=0.005
Boundary for River Rch & Prof#=Lynn Creek T5,Reach-1,2
Up Type=0
Dn Type=3
Dn Slope=0.005
Boundary for River Rch & Prof#=Lynn Creek T5,Reach-1,3
Up Type=0
Dn Type=3
Dn Slope=0.005
Boundary for River Rch & Prof#=Lynn Creek T5,Reach-1,4
Up Type=0
Dn Type=3
Dn Slope=0.005
Boundary for River Rch & Prof#=Lynn Creek T5,Reach-1,5
Up Type=0
Dn Type=3
Dn Slope=0.005
Boundary for River Rch & Prof#=Lynn Creek T5,Reach-1,6
Up Type=0
Dn Type=3
Dn Slope=0.005
Boundary for River Rch & Prof#=Lynn Creek T5,Reach-1,7
Up Type=0
Dn Type=3
Dn Slope=0.005

--- Lynn Creek T5.g01 (geometry) ---

Geom Title=Existing Conditions

River Reach=Lynn Creek T5,Reach-1
Reach XY= 30
      2722376.00      6782311.00      2722177.39      6782214.02
      2722082.39      6782453.00      2721960.79      6782510.50
      2721726.00      6782468.56      2721577.28      6782514.52
      2721496.47      6782641.36      2721319.96      6782759.38
      2721076.10      6782618.32      2720886.80      6782700.63
      2720973.83      6782816.89      2721018.41      6782961.01
      2720976.99      6783050.36      2721018.65      6783111.09
      2720881.83      6783258.70      2720777.06      6783571.66
      2720779.00      6783652.65      2720874.43      6783716.86
      2720825.81      6783831.20      2720868.64      6783911.08
      2720777.67      6784017.05      2720818.41      6784110.99
      2720772.37      6784259.50      2720684.00      6784357.67
      2720724.96      6784650.56      2720587.24      6784801.00
      2720617.97      6784864.33      2720533.83      6784957.58
      2720570.60      6785113.43      2720376.00      6785261.00

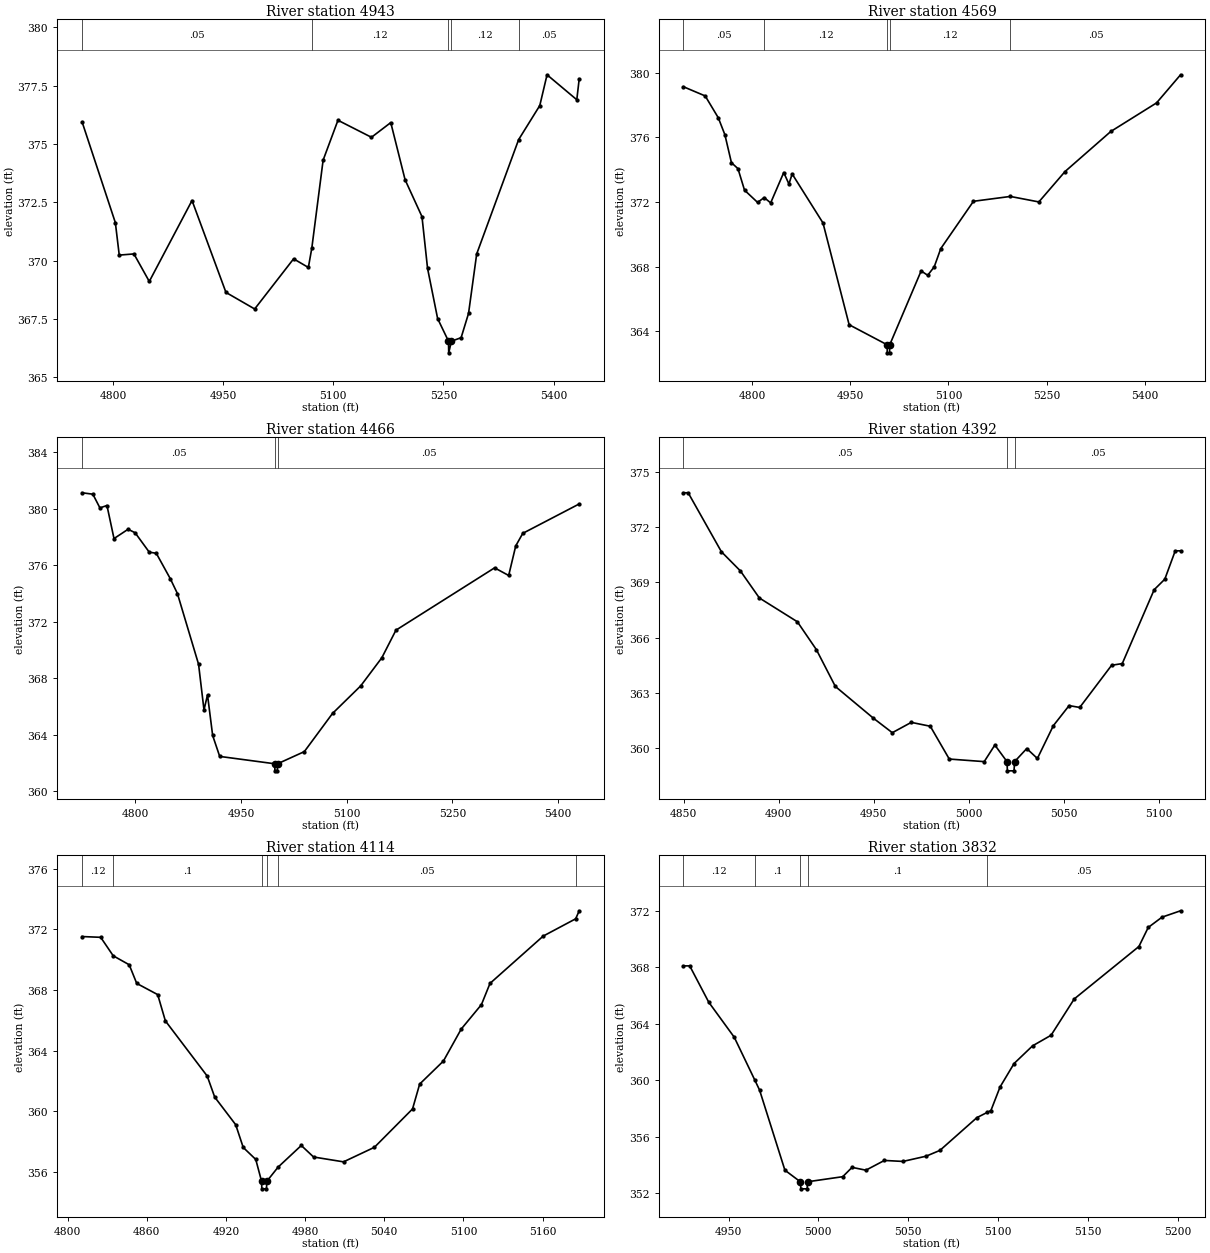
Type RM Length L Ch R = 1,4943,374,374,374
BEGIN DESCRIPTION:
Lynn Creek T5 18.0
END DESCRIPTION:
XS GIS Cut Line= 4
      2722294.27      6781983.39      2722226.00      6782211.00
      2722244.17      6782366.65      2722341.02      6782632.10
#Sta/Elev= 30
  4757.9  375.95  4803.2  371.63  4808.5  370.24  4828.5  370.29  4849.4  369.11
  4907.6  372.58  4953.8  368.64  4992.9  367.93  5045.9  370.08  5066.0  369.71
  5070.7  370.54  5086.1  374.31  5106.3  376.02  5151.9  375.29  5178.2  375.92
  5197.7  373.47  5220.7  371.89  5228.3  369.67  5242.0  367.52  5256.8  366.55
  5257.1  366.05  5260.8  366.55  5274.0  366.70  5284.1  367.74  5295.2  370.29
  5352.3  375.19  5381.1  376.65  5391.0  377.97  5431.5  376.90  5434.8  377.80
#Mann=5,-1,0
  4757.9    0.05       0  5070.7    0.12       0  5256.8    0.05       0
  5260.8    0.12       0  5352.3    0.05       0
Bank Sta=5256.8,5260.8
Exp/Cntr=0.3,0.1

Type RM Length L Ch R = 1,4569,103,103,103
BEGIN DESCRIPTION:
Lynn Creek T5 17.0
END DESCRIPTION:
XS GIS Cut Line= 3
      2722045.93      6782157.68      2722036.76      6782462.74
      2722034.15      6782917.73
#Sta/Elev= 30
  4694.8  379.14  4728.1  378.57  4748.1  377.22  4758.2  376.17  4768.2  374.44
  4778.2  374.07  4788.2  372.74  4808.2  371.98  4818.3  372.28  4828.2  371.95
  4848.2  373.83  4856.1  373.12  4861.1  373.74  4908.2  370.71  4948.2  364.41
  5006.3  363.17  5006.5  362.67  5010.0  362.67  5010.3  363.17  5058.3  367.74
  5068.3  367.47  5078.3  367.99  5088.3  369.12  5138.3  372.05  5194.7  372.35
  5238.3  372.01  5278.3  373.89  5348.3  376.37  5418.3  378.14  5455.0  379.88
#Mann=5,-1,0
  4694.8    0.05       0  4818.3    0.12       0  5006.3    0.07       0
  5010.3    0.12       0  5194.7    0.05       0
Bank Sta=5006.3,5010.3
Exp/Cntr=0.3,0.1

Type RM Length L Ch R = 1,4466,74,74,74
BEGIN DESCRIPTION:
Mapping XS e4c9a6de
END DESCRIPTION:
XS GIS Cut Line= 2
      2721953.24      6782235.67      2721944.23      6782941.11
#Sta/Elev= 30
  4724.4  381.13  4739.7  381.03  4749.7  380.06  4759.7  380.23  4769.7  377.89
  4789.7  378.55  4799.7  378.30  4819.7  376.93  4829.7  376.85  4849.7  375.04
  4859.7  374.00  4889.7  369.00  4897.4  365.77  4902.4  366.83  4909.7  363.96
  4919.7  362.48  4997.8  361.96  4998.0  361.46  5001.5  361.46  5001.8  361.96
  5039.8  362.82  5079.8  365.52  5119.8  367.47  5149.8  369.46  5169.8  371.41
  5309.8  375.82  5329.8  375.28  5339.8  377.37  5349.8  378.26  5429.9  380.34
#Mann=3,-1,0
  4724.4    0.05       0  4997.8    0.05       0  5001.8    0.05       0
Bank Sta=4997.8,5001.8
Exp/Cntr=0.3,0.1

Type RM Length L Ch R = 1,4392,278,278,278
BEGIN DESCRIPTION:
Lynn Creek T5 16.0
END DESCRIPTION:
XS GIS Cut Line= 3
      2721876.00      6782360.97      2721876.00      6782511.00
      2721826.02      6782610.97
#Sta/Elev= 30
  4849.8  373.86  4852.3  373.86  4869.8  370.66  4879.8  369.62  4889.8  368.15
  4909.8  366.86  4919.8  365.35  4929.8  363.35  4949.8  361.63  4959.8  360.84
  4969.8  361.40  4979.8  361.19  4989.8  359.41  5008.2  359.27  5013.8  360.17
  5020.2  359.27  5020.4  358.77  5023.9  358.77  5024.2  359.27  5030.6  359.98
  5036.2  359.44  5044.6  361.22  5052.9  362.31  5058.5  362.21  5075.3  364.50
  5080.9  364.59  5097.7  368.60  5103.3  369.17  5108.8  370.71  5111.6  370.71
#Mann=3,-1,0
  4849.8    0.05       0  5020.2    0.05       0  5024.2    0.05       0
Bank Sta=5020.2,5024.2
Exp/Cntr=0.3,0.1

Type RM Length L Ch R = 1,4114,282,282,282
BEGIN DESCRIPTION:
Lynn Creek T5 15.0
END DESCRIPTION:
XS GIS Cut Line= 3
      2721532.36      6782346.70      2721626.00      6782511.00
      2721701.06      6782682.91
#Sta/Elev= 30
  4811.0  371.52  4825.1  371.47  4834.6  370.25  4846.7  369.66  4852.4  368.43
  4868.3  367.69  4874.1  365.96  4905.8  362.32  4911.5  360.93  4927.4  359.11
  4933.1  357.61  4942.6  356.82  4947.0  355.38  4947.2  354.88  4950.7  354.88
  4951.0  355.38  4959.5  356.31  4977.1  357.74  4986.4  356.98  5009.1  356.66
  5032.5  357.62  5061.4  360.15  5066.8  361.79  5084.8  363.31  5098.3  365.42
  5113.6  367.03  5120.1  368.43  5160.4  371.55  5185.0  372.69  5187.7  373.22
#Mann=6,-1,0
  4811.0    0.12       0  4834.6     0.1       0  4947.0    0.05       0
  4951.0     0.1       0  4959.5    0.05       0  5185.0     0.1       0
Bank Sta=4947,4951
Exp/Cntr=0.3,0.1

Type RM Length L Ch R = 1,3832,253,253,253
BEGIN DESCRIPTION:
Lynn Creek T5 14.0
END DESCRIPTION:
XS GIS Cut Line= 3
      2721376.02      6782611.02      2721426.00      6782661.00
      2721475.99      6782860.97
#Sta/Elev= 30
  4924.9  368.10  4928.4  368.10  4939.0  365.53  4953.2  363.05  4964.6  360.03
  4967.3  359.31  4981.4  353.64  4990.0  352.82  4990.3  352.32  4993.8  352.32
  4994.0  352.82  5013.6  353.18  5018.8  353.84  5026.5  353.64  5036.8  354.33
  5047.1  354.26  5060.0  354.63  5067.7  355.04  5088.3  357.36  5094.2  357.74
  5096.1  357.86  5101.2  359.53  5109.0  361.19  5119.3  362.44  5129.6  363.19
  5142.5  365.76  5178.5  369.47  5183.7  370.82  5191.4  371.55  5201.7  372.00
#Mann=5,-1,0
  4924.9    0.12       0  4964.6     0.1       0  4990.0    0.07       0
  4994.0     0.1       0  5094.2    0.05       0
Bank Sta=4990,4994
Exp/Cntr=0.3,0.1

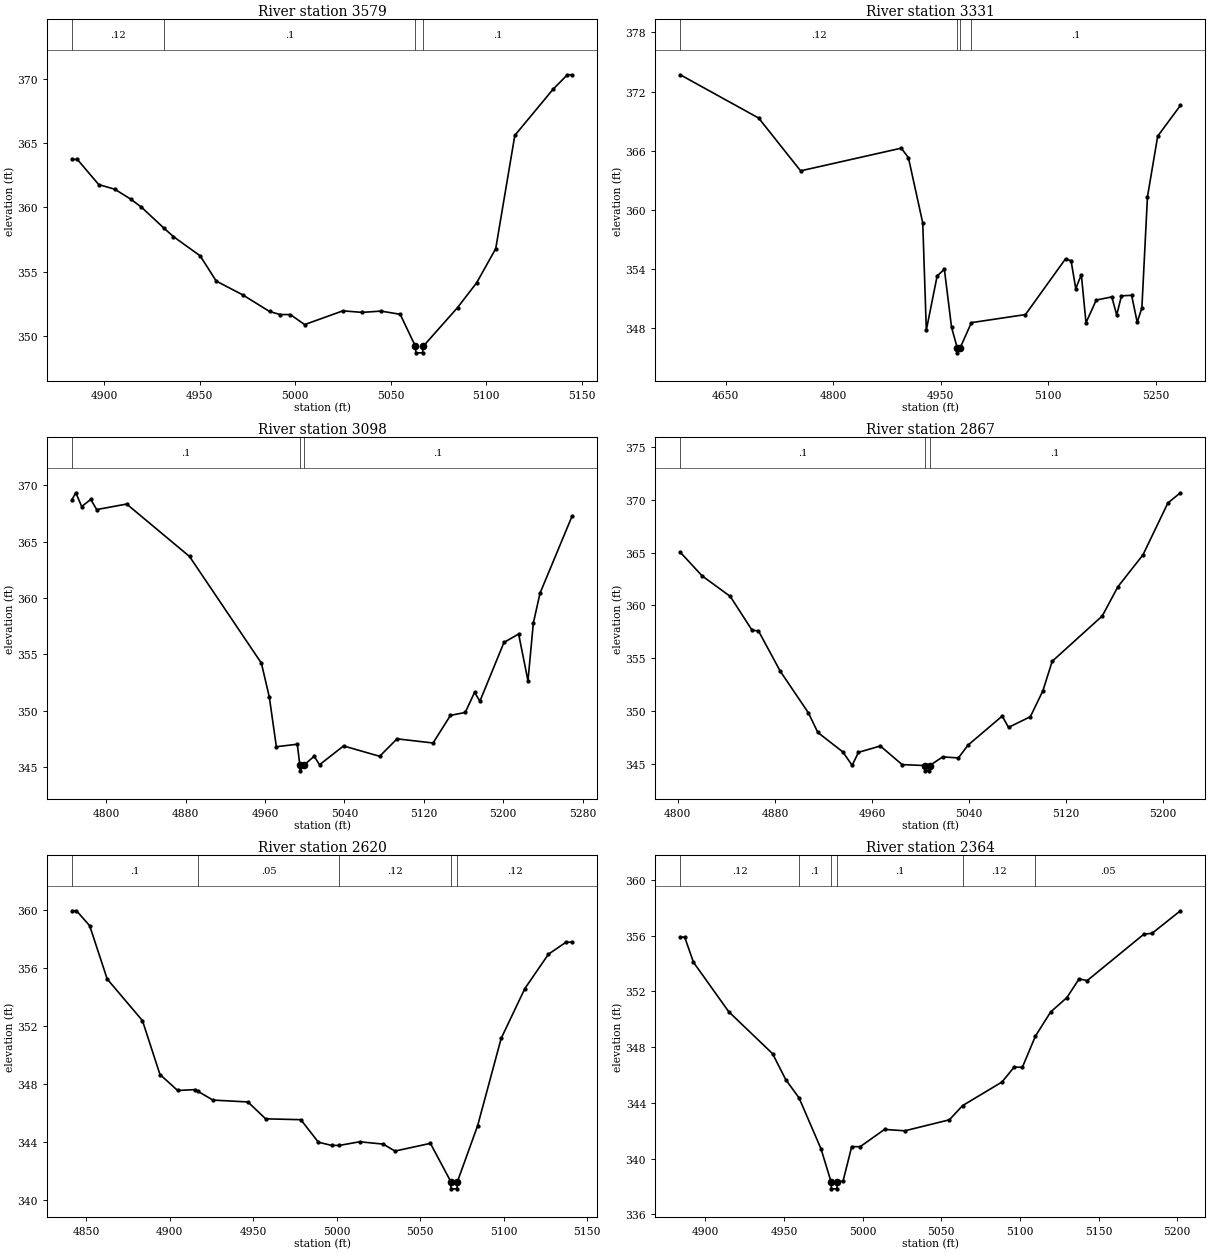
Type RM Length L Ch R = 1,3579,248,248,248
BEGIN DESCRIPTION:
Lynn Creek T5 13.0
END DESCRIPTION:
XS GIS Cut Line= 3
      2721276.00      6782611.01      2721226.00      6782711.00
      2721226.00      6782861.00
#Sta/Elev= 30
  4883.1  363.74  4885.9  363.74  4897.1  361.78  4905.5  361.42  4913.8  360.65
  4919.4  360.03  4931.3  358.38  4936.2  357.73  4950.2  356.23  4958.6  354.27
  4972.5  353.19  4986.5  351.90  4992.1  351.66  4997.4  351.66  5004.9  350.88
  5024.9  351.95  5034.9  351.83  5044.9  351.93  5054.9  351.68  5062.9  349.18
  5063.1  348.68  5066.6  348.68  5066.9  349.18  5084.9  352.20  5094.9  354.13
  5104.9  356.79  5114.9  365.61  5134.9  369.20  5142.4  370.33  5144.9  370.33
#Mann=4,-1,0
  4883.1    0.12       0  4931.3     0.1       0  5062.9    0.07       0
  5066.9     0.1       0
Bank Sta=5062.9,5066.9
Exp/Cntr=0.3,0.1

Type RM Length L Ch R = 1,3331,233,233,233
BEGIN DESCRIPTION:
Mapping XS f9605e3b
END DESCRIPTION:
XS GIS Cut Line= 3
      2720992.04      6782243.65      2721027.28      6782660.10
      2721208.08      6782874.24
#Sta/Elev= 30
  4586.5  373.71  4696.0  369.32  4754.5  363.97  4895.0  366.27  4905.0  365.31
  4925.0  358.69  4930.0  347.83  4945.1  353.31  4955.2  354.00  4965.2  348.11
  4973.2  346.02  4973.5  345.52  4977.2  346.02  4992.9  348.58  5068.4  349.40
  5124.3  355.05  5132.1  354.85  5138.6  352.03  5146.4  353.45  5152.9  348.57
  5167.2  350.87  5188.9  351.19  5195.8  349.36  5202.4  351.30  5216.6  351.35
  5224.4  348.62  5230.9  350.07  5238.7  361.34  5253.0  367.49  5284.7  370.60
#Mann=4,-1,0
  4586.5    0.12       0  4973.2    0.07       0  4977.2    0.12       0
  4992.9     0.1       0
Bank Sta=4973.2,4977.2
Exp/Cntr=0.3,0.1

Type RM Length L Ch R = 1,3098,231,231,231
BEGIN DESCRIPTION:
Lynn Creek T5 12.0
END DESCRIPTION:
XS GIS Cut Line= 3
      2720729.49      6782889.15      2720926.00      6782761.00
      2721176.04      6782861.02
#Sta/Elev= 30
  4765.5  368.73  4769.3  369.34  4775.3  368.12  4784.4  368.75  4790.4  367.85
  4820.6  368.34  4883.9  363.69  4956.3  354.23  4964.3  351.22  4971.4  346.81
  4992.5  347.03  4995.1  345.17  4995.4  344.67  4999.1  345.17  5009.5  345.96
  5014.9  345.21  5039.1  346.88  5075.5  345.96  5093.0  347.51  5129.3  347.14
  5146.8  349.59  5161.7  349.85  5171.1  351.63  5176.5  350.85  5200.7  356.06
  5215.5  356.81  5224.9  352.66  5230.3  357.77  5237.0  360.42  5269.4  367.28
#Mann=3,-1,0
  4765.5     0.1       0  4995.1    0.07       0  4999.1     0.1       0
Bank Sta=4995.1,4999.1
Exp/Cntr=0.3,0.1

Type RM Length L Ch R = 1,2867,247,247,247
BEGIN DESCRIPTION:
Lynn Creek T5 11.0
END DESCRIPTION:
XS GIS Cut Line= 3
      2720826.01      6782911.00      2721026.00      6782961.00
      2721226.00      6782911.00
#Sta/Elev= 30
  4802.0  365.03  4820.0  362.79  4843.2  360.85  4861.3  357.63  4866.4  357.60
  4884.4  353.78  4907.6  349.84  4915.4  347.98  4936.0  346.14  4943.7  344.87
  4948.9  346.10  4966.9  346.70  4984.9  344.94  5003.6  344.85  5003.8  344.35
  5007.3  344.35  5007.6  344.85  5018.4  345.67  5031.3  345.57  5039.1  346.77
  5067.4  349.53  5072.6  348.46  5090.6  349.47  5100.9  351.91  5108.6  354.71
  5149.9  359.00  5162.8  361.77  5183.4  364.77  5204.0  369.69  5214.3  370.65
#Mann=3,-1,0
  4802.0     0.1       0  5003.6    0.07       0  5007.6     0.1       0
Bank Sta=5003.6,5007.6
Exp/Cntr=0.3,0.1

Type RM Length L Ch R = 1,2620,256,256,256
BEGIN DESCRIPTION:
Lynn Creek T5 10.0
END DESCRIPTION:
XS GIS Cut Line= 3
      2720825.97      6783110.99      2720976.00      6783161.00
      2721076.03      6783261.03
#Sta/Elev= 30
  4841.5  359.92  4844.2  359.92  4852.1  358.89  4862.6  355.22  4883.7  352.36
  4894.2  348.65  4904.8  347.55  4915.3  347.61  4917.0  347.49  4925.9  346.89
  4946.9  346.76  4957.5  345.60  4978.6  345.54  4989.1  343.99  4997.0  343.77
  5001.7  343.77  5013.8  344.02  5027.9  343.86  5035.0  343.38  5056.2  343.91
  5068.4  341.28  5068.6  340.78  5072.1  340.78  5072.4  341.28  5084.5  345.13
  5098.6  351.14  5112.8  354.57  5126.9  356.93  5137.5  357.76  5141.1  357.76
#Mann=5,-1,0
  4841.5     0.1       0  4917.0    0.05       0  5001.7    0.12       0
  5068.4    0.05       0  5072.4    0.12       0
Bank Sta=5068.4,5072.4
Exp/Cntr=0.3,0.1

Type RM Length L Ch R = 1,2364,265,265,265
BEGIN DESCRIPTION:
Lynn Creek T5 9.0
END DESCRIPTION:
XS GIS Cut Line= 3
      2720725.96      6783310.98      2720826.00      6783361.00
      2721026.00      6783411.00
#Sta/Elev= 30
  4884.0  355.91  4886.8  355.91  4892.4  354.10  4914.8  350.55  4942.7  347.53
  4951.1  345.66  4959.5  344.36  4973.5  340.69  4979.9  338.32  4980.1  337.82
  4983.6  337.82  4983.9  338.32  4987.5  338.38  4993.0  340.85  4998.4  340.85
  5013.9  342.09  5026.8  341.99  5055.1  342.78  5063.5  343.80  5088.6  345.50
  5096.3  346.57  5101.5  346.55  5109.8  348.79  5119.5  350.53  5129.8  351.56
  5137.6  352.91  5142.7  352.78  5178.8  356.12  5184.0  356.18  5202.0  357.80
#Mann=6,-1,0
  4884.0    0.12       0  4959.5     0.1       0  4979.9    0.07       0
  4983.9     0.1       0  5063.5    0.12       0  5109.8    0.05       0
Bank Sta=4979.9,4983.9
Exp/Cntr=0.3,0.1

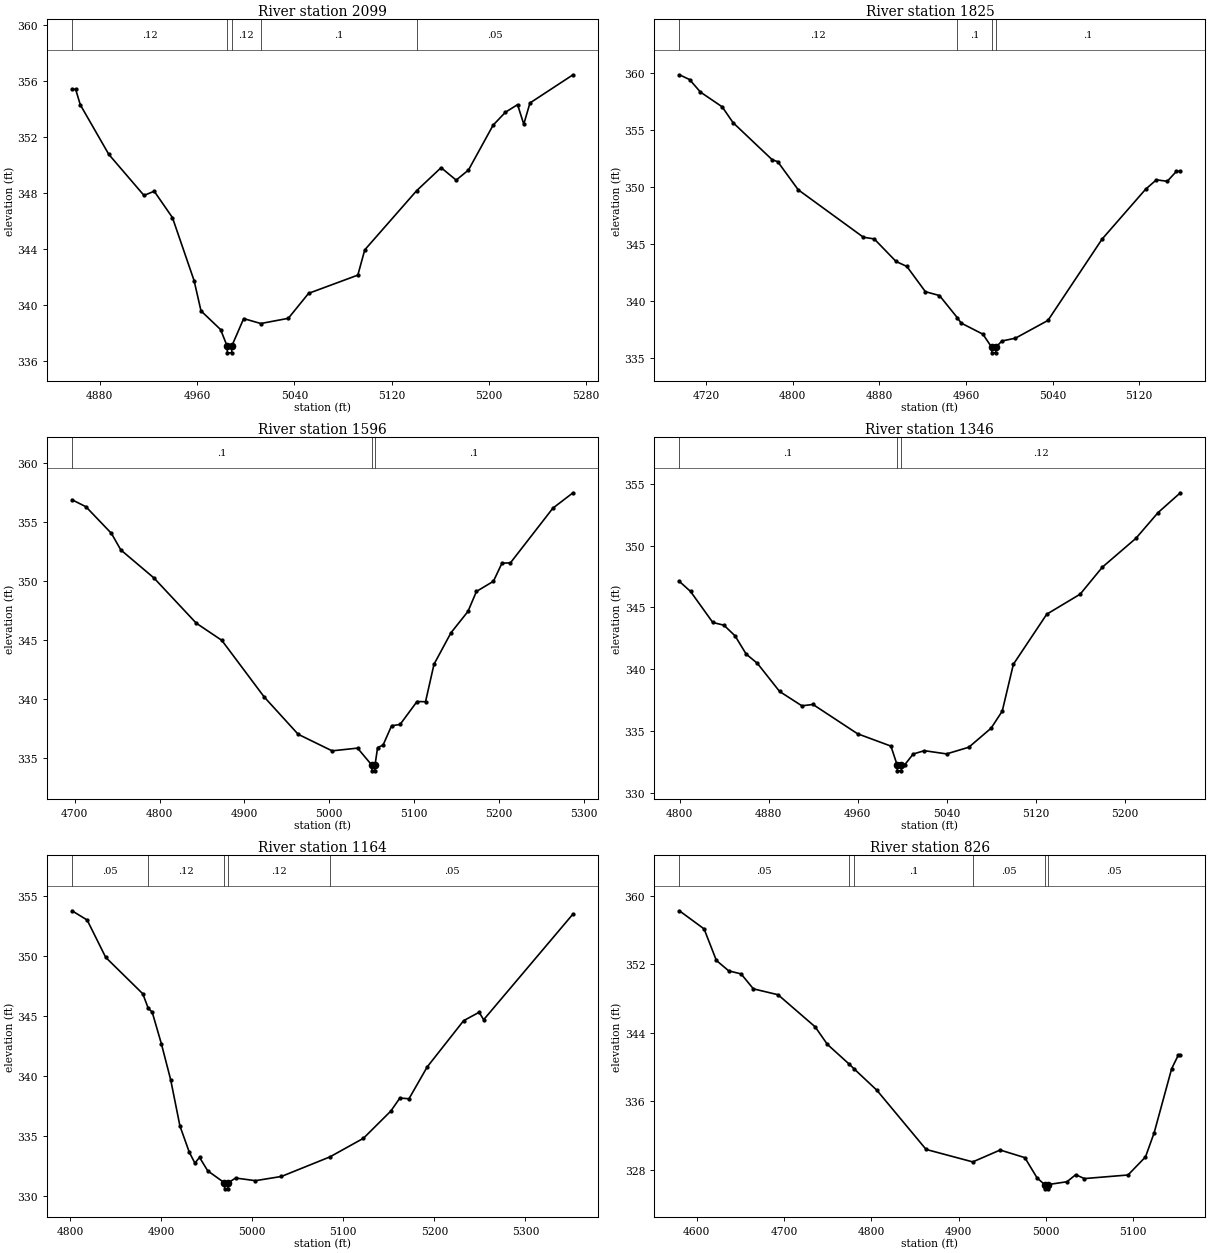
Type RM Length L Ch R = 1,2099,274,274,274
BEGIN DESCRIPTION:
Lynn Creek T5 8.0
END DESCRIPTION:
XS GIS Cut Line= 3
      2720643.96      6783553.63      2720776.00      6783611.00
      2721040.94      6783569.74
#Sta/Elev= 30
  4857.1  355.38  4860.1  355.38  4863.9  354.28  4887.4  350.74  4916.3  347.82
  4924.7  348.12  4939.7  346.24  4957.5  341.75  4963.2  339.59  4979.3  338.26
  4984.6  337.10  4984.9  336.60  4988.4  336.60  4988.6  337.10  4998.3  339.04
  5012.4  338.69  5035.0  339.06  5051.7  340.84  5092.2  342.14  5097.9  343.94
  5140.6  348.16  5160.7  349.80  5173.1  348.91  5183.2  349.63  5203.5  352.83
  5213.6  353.75  5223.6  354.29  5228.7  352.90  5233.8  354.41  5269.2  356.42
#Mann=5,-1,0
  4857.1    0.12       0  4984.6    0.07       0  4988.6    0.12       0
  5012.4     0.1       0  5140.6    0.05       0
Bank Sta=4984.6,4988.6
Exp/Cntr=0.3,0.1

Type RM Length L Ch R = 1,1825,229,229,229
BEGIN DESCRIPTION:
Lynn Creek T5 7.0
END DESCRIPTION:
XS GIS Cut Line= 3
      2720526.62      6783789.89      2720826.00      6783811.00
      2720988.14      6783814.44
#Sta/Elev= 30
  4695.6  359.87  4705.0  359.45  4715.0  358.35  4735.1  357.05  4745.1  355.66
  4781.3  352.39  4786.3  352.23  4805.3  349.75  4865.4  345.58  4875.4  345.43
  4895.5  343.45  4905.5  343.01  4922.6  340.79  4935.6  340.45  4952.0  338.51
  4955.6  338.03  4975.7  337.05  4983.7  335.91  4983.9  335.41  4987.4  335.41
  4987.7  335.91  4993.2  336.45  5005.7  336.70  5035.7  338.26  5085.7  345.42
  5125.8  349.80  5135.8  350.63  5145.8  350.50  5154.3  351.38  5157.9  351.38
#Mann=4,-1,0
  4695.6    0.12       0  4952.0     0.1       0  4983.7    0.07       0
  4987.7     0.1       0
Bank Sta=4983.7,4987.7
Exp/Cntr=0.3,0.1

Type RM Length L Ch R = 1,1596,250,250,250
BEGIN DESCRIPTION:
Lynn Creek T5 6.0
END DESCRIPTION:
XS GIS Cut Line= 3
      2720489.63      6783984.29      2720776.61      6783993.48
      2721079.70      6784004.16
#Sta/Elev= 30
  4696.9  356.86  4713.3  356.27  4743.3  354.02  4754.4  352.62  4793.3  350.26
  4843.3  346.43  4873.4  344.98  4923.4  340.19  4963.4  337.04  5003.4  335.64
  5033.4  335.87  5050.0  334.45  5050.3  333.95  5053.8  333.95  5054.0  334.45
  5057.0  335.91  5063.5  336.13  5073.5  337.76  5083.5  337.87  5103.5  339.81
  5113.5  339.79  5123.5  342.96  5143.5  345.62  5163.5  347.42  5173.5  349.11
  5193.5  349.97  5203.6  351.50  5213.6  351.53  5263.6  356.15  5287.3  357.45
#Mann=3,-1,0
  4696.9     0.1       0  5050.0    0.07       0  5054.0     0.1       0
Bank Sta=5050,5054
Exp/Cntr=0.3,0.1

Type RM Length L Ch R = 1,1346,182,182,182
BEGIN DESCRIPTION:
Lynn Creek T5 5.0
END DESCRIPTION:
XS GIS Cut Line= 3
      2720575.95      6784211.00      2720776.00      6784211.00
      2721025.95      6784211.00
#Sta/Elev= 30
  4799.9  347.10  4809.9  346.29  4829.9  343.78  4839.9  343.56  4849.9  342.70
  4859.9  341.22  4869.9  340.48  4889.9  338.20  4909.9  337.04  4919.9  337.15
  4959.9  334.78  4989.9  333.78  4995.4  332.28  4995.7  331.78  4999.2  331.78
  4999.4  332.28  5002.4  332.28  5009.9  333.14  5019.9  333.41  5039.9  333.15
  5059.9  333.69  5079.9  335.23  5089.9  336.61  5099.9  340.40  5129.9  344.45
  5159.9  346.07  5179.9  348.26  5209.9  350.58  5229.9  352.67  5249.9  354.27
#Mann=3,-1,0
  4799.9     0.1       0  4995.4    0.07       0  4999.4    0.12       0
Bank Sta=4995.4,4999.4
Exp/Cntr=0.3,0.1

Type RM Length L Ch R = 1,1164,338,338,338
BEGIN DESCRIPTION:
Lynn Creek T5 4.0
END DESCRIPTION:
XS GIS Cut Line= 3
      2720489.66      6784320.32      2720684.00      6784357.67
      2721036.00      6784369.36
#Sta/Elev= 30
  4802.1  353.74  4818.7  352.97  4839.1  349.86  4879.8  346.83  4885.8  345.62
  4890.1  345.31  4900.2  342.67  4910.4  339.68  4920.6  335.82  4930.8  333.65
  4937.0  332.73  4942.1  333.21  4951.1  332.09  4969.5  331.09  4969.7  330.59
  4973.2  330.59  4973.5  331.09  4981.7  331.49  5003.5  331.27  5032.0  331.62
  5085.3  333.25  5122.1  334.80  5152.1  337.06  5162.1  338.15  5172.1  338.09
  5192.1  340.74  5232.1  344.59  5249.1  345.29  5254.1  344.67  5352.2  353.47
#Mann=5,-1,0
  4802.1    0.05       0  4885.8    0.12       0  4969.5    0.07       0
  4973.5    0.12       0  5085.3    0.05       0
Bank Sta=4969.5,4973.5
Exp/Cntr=0.3,0.1

Type RM Length L Ch R = 1,826,260,260,260
BEGIN DESCRIPTION:
Lynn Creek T5 3.0
END DESCRIPTION:
XS GIS Cut Line= 3
      2720426.01      6784361.01      2720726.00      6784661.00
      2720876.05      6784661.00
#Sta/Elev= 30
  4580.0  358.26  4608.3  356.14  4622.4  352.45  4636.6  351.23  4650.7  350.88
  4664.8  349.13  4693.1  348.44  4735.6  344.69  4749.7  342.63  4774.4  340.35
  4780.7  339.73  4806.3  337.28  4862.8  330.35  4916.3  328.89  4947.7  330.28
  4976.0  329.39  4990.1  327.01  4998.7  326.24  4999.0  325.74  5002.5  325.74
  5002.7  326.24  5024.3  326.57  5034.3  327.39  5044.3  326.94  5094.3  327.36
  5114.3  329.47  5124.3  332.31  5144.3  339.79  5151.8  341.35  5154.3  341.35
#Mann=6,-1,0
  4580.0    0.05       0  4774.4    0.12       0  4780.7     0.1       0
  4916.3    0.05       0  4998.7    0.03       0  5002.7    0.05       0
Bank Sta=4998.7,5002.7
Exp/Cntr=0.3,0.1

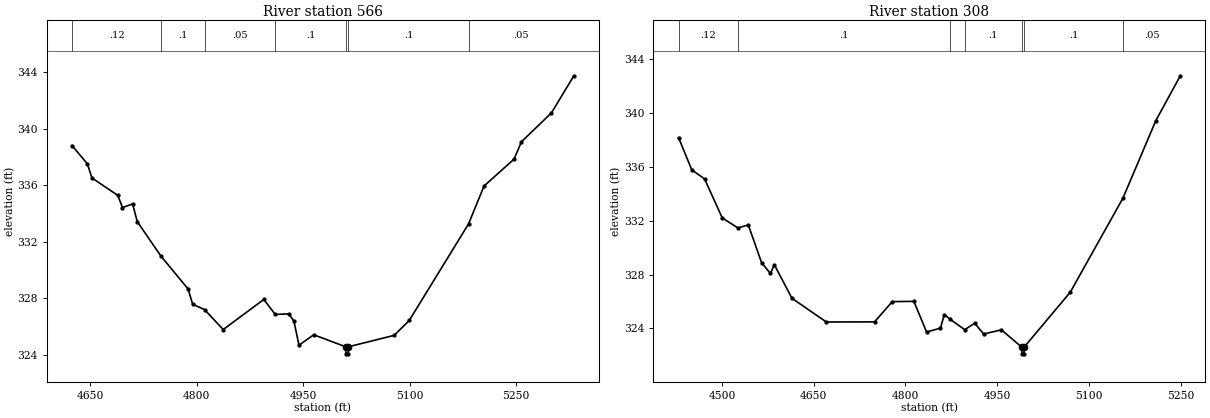
Type RM Length L Ch R = 1,566,258,258,258
BEGIN DESCRIPTION:
Lynn Creek T5 2.0
END DESCRIPTION:
XS GIS Cut Line= 3
      2720325.97      6784610.97      2720626.00      6784861.00
      2720926.02      6784760.99
#Sta/Elev= 30
  4624.3  338.82  4645.8  337.53  4652.3  336.53  4688.8  335.29  4695.3  334.43
  4709.6  334.69  4716.1  333.44  4749.3  331.01  4787.7  328.67  4794.2  327.59
  4810.9  327.21  4837.2  325.80  4894.4  327.93  4910.4  326.87  4929.6  326.91
  4936.8  326.40  4943.9  324.69  4964.7  325.43  5009.6  324.58  5009.9  324.08
  5013.4  324.08  5013.6  324.58  5078.1  325.39  5099.2  326.44  5182.7  333.27
  5204.6  335.96  5246.8  337.86  5257.3  339.09  5299.5  341.13  5331.1  343.76
#Mann=7,-1,0
  4624.3    0.12       0  4749.3     0.1       0  4810.9    0.05       0
  4910.4     0.1       0  5009.6    0.07       0  5013.6     0.1       0
  5182.7    0.05       0
Bank Sta=5009.6,5013.6
Exp/Cntr=0.3,0.1

Type RM Length L Ch R = 1,308,0,0,0
BEGIN DESCRIPTION:
Lynn Creek T5 1.0
END DESCRIPTION:
XS GIS Cut Line= 3
      2720225.99      6784610.99      2720576.00      6785061.00
      2720826.00      6785061.00
#Sta/Elev= 30
  4429.1  338.15  4450.8  335.75  4471.6  335.09  4500.6  332.19  4526.3  331.45
  4543.1  331.68  4564.9  328.87  4579.3  328.08  4585.7  328.72  4614.6  326.23
  4670.7  324.48  4749.5  324.49  4778.4  325.99  4813.7  326.01  4834.5  323.74
  4857.1  324.02  4863.5  325.03  4873.1  324.68  4896.8  323.91  4913.2  324.39
  4927.7  323.59  4956.7  323.90  4990.0  322.62  4990.2  322.12  4993.7  322.12
  4994.0  322.62  5069.2  326.68  5155.4  333.66  5209.2  339.41  5249.2  342.73
#Mann=7,-1,0
  4429.1    0.12       0  4526.3     0.1       0  4873.1    0.05       0
  4896.8     0.1       0  4990.0    0.07       0  4994.0     0.1       0
  5155.4    0.05       0
Bank Sta=4990,4994
Exp/Cntr=0.3,0.1

Chan Stop Cuts=-1