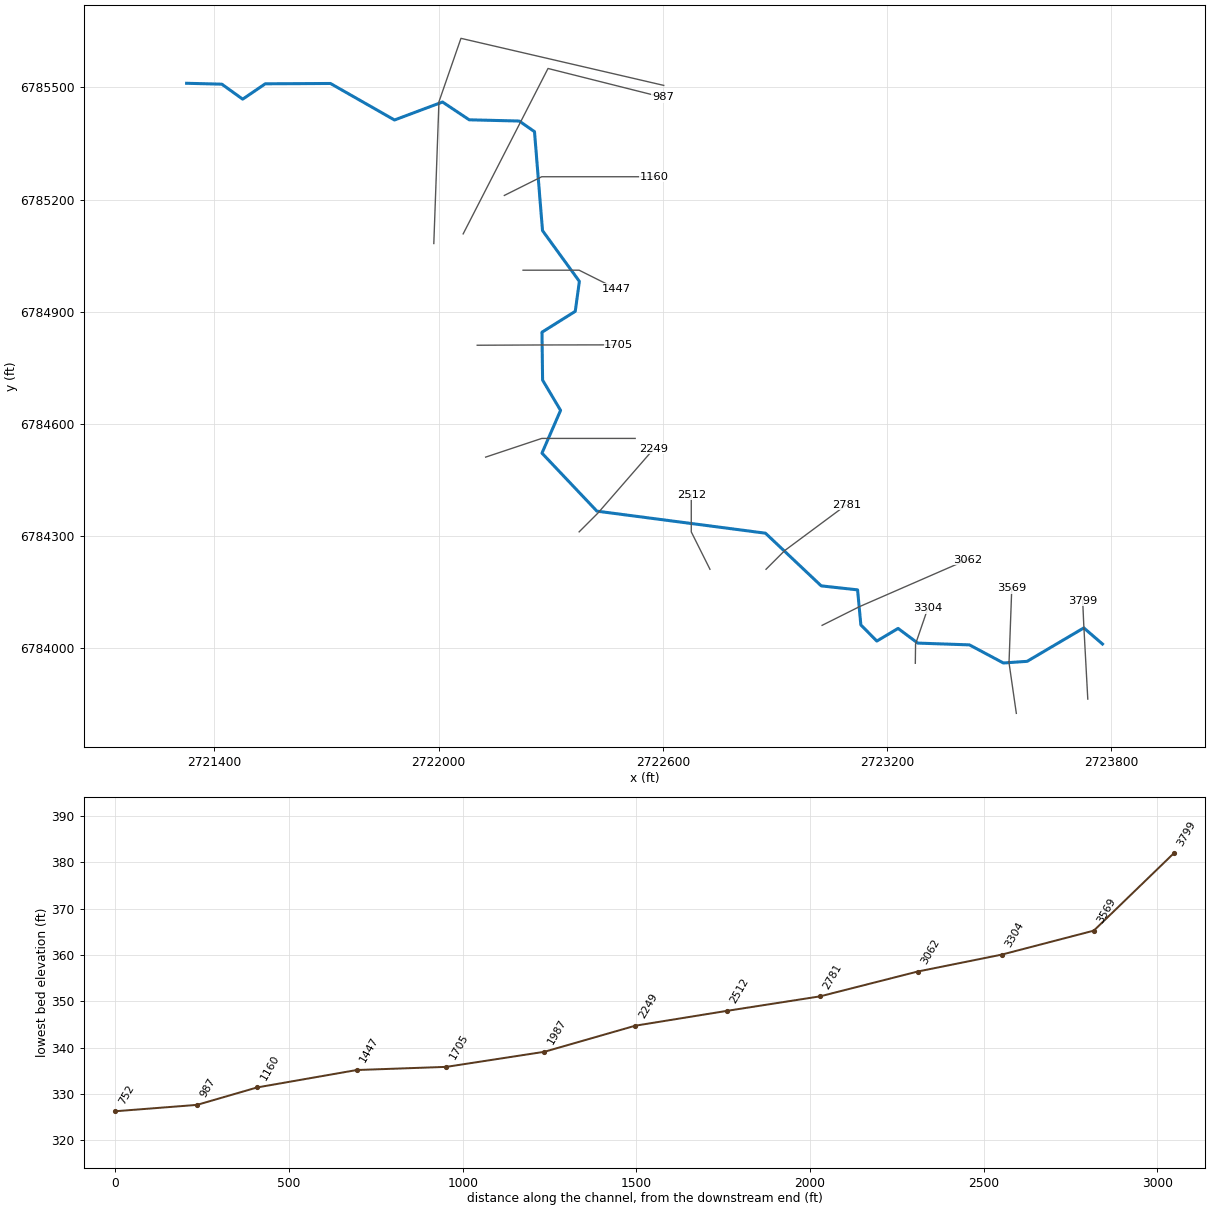
--- Lynn Creek T6.prj (project) ---

Proj Title=Lynn Creek T6 Base Level Engineering
Current Plan=p01
Default Exp/Contr=0.3,0.1
English Units
Geom File=g01
Flow File=f01
Plan File=p01
BEGIN DESCRIPTION:
Lynn Creek T6
END DESCRIPTION:

--- Lynn Creek T6.p01 (plan) ---

Plan Title=Multiple Run
Short Identifier=Multiple
Geom File=g01
Flow File=f01
Subcritical Flow
K Sum by GR= 0
Std Step Tol= 0.01
Critical Tol= 0.01
Num of Std Step Trials= 20
Max Error Tol= 0.3
Flow Tol Ratio= 0.001
Split Flow NTrial= 30
Split Flow Tol= 0.02
Split Flow Ratio= 0.02
Log Output Level= 0
Friction Slope Method= 1
Unsteady Friction Slope Method= 2
Unsteady Bridges Friction Slope Method= 1
Parabolic Critical Depth
Global Vel Dist=  1 , 1 , 1
Global Log Level= 0
CheckData=True
Encroach Param= -1, 0, 0, 0
BEGIN DESCRIPTION:
Multiple Run
END DESCRIPTION:

--- Lynn Creek T6.f01 (steady flow) ---

Flow Title=Multiple
Number of Profiles=7
Profile Names=10-year,25-year,50-year,1pct_min,100-year,1pct_plu,500-year
River Rch & RM= Lynn Creek T6,Reach-1,3799
     227     287     334     193     386     769     512
Boundary for River Rch & Prof#=Lynn Creek T6,Reach-1,1
Up Type=0
Dn Type=3
Dn Slope=0.005
Boundary for River Rch & Prof#=Lynn Creek T6,Reach-1,2
Up Type=0
Dn Type=3
Dn Slope=0.005
Boundary for River Rch & Prof#=Lynn Creek T6,Reach-1,3
Up Type=0
Dn Type=3
Dn Slope=0.005
Boundary for River Rch & Prof#=Lynn Creek T6,Reach-1,4
Up Type=0
Dn Type=3
Dn Slope=0.005
Boundary for River Rch & Prof#=Lynn Creek T6,Reach-1,5
Up Type=0
Dn Type=3
Dn Slope=0.005
Boundary for River Rch & Prof#=Lynn Creek T6,Reach-1,6
Up Type=0
Dn Type=3
Dn Slope=0.005
Boundary for River Rch & Prof#=Lynn Creek T6,Reach-1,7
Up Type=0
Dn Type=3
Dn Slope=0.005

--- Lynn Creek T6.g01 (geometry) ---

Geom Title=Existing Conditions

River Reach=Lynn Creek T6,Reach-1
Reach XY= 30
      2723776.00      6784011.00      2723726.12      6784054.13
      2723574.42      6783964.67      2723510.94      6783960.29
      2723420.06      6784008.73      2723281.86      6784013.46
      2723229.21      6784052.71      2723172.38      6784018.88
      2723129.65      6784062.11      2723120.89      6784155.88
      2723023.64      6784166.55      2722874.54      6784307.46
      2722423.55      6784366.46      2722276.60      6784521.62
      2722326.39      6784636.00      2722278.27      6784716.94
      2722276.66      6784845.15      2722365.64      6784900.92
      2722376.68      6784981.06      2722278.07      6785116.86
      2722256.60      6785381.66      2722215.73      6785410.01
      2722081.93      6785413.30      2722010.60      6785460.90
      2721882.11      6785412.80      2721710.79      6785510.49
      2721536.44      6785509.62      2721475.99      6785468.51
      2721420.23      6785508.66      2721326.00      6785511.00

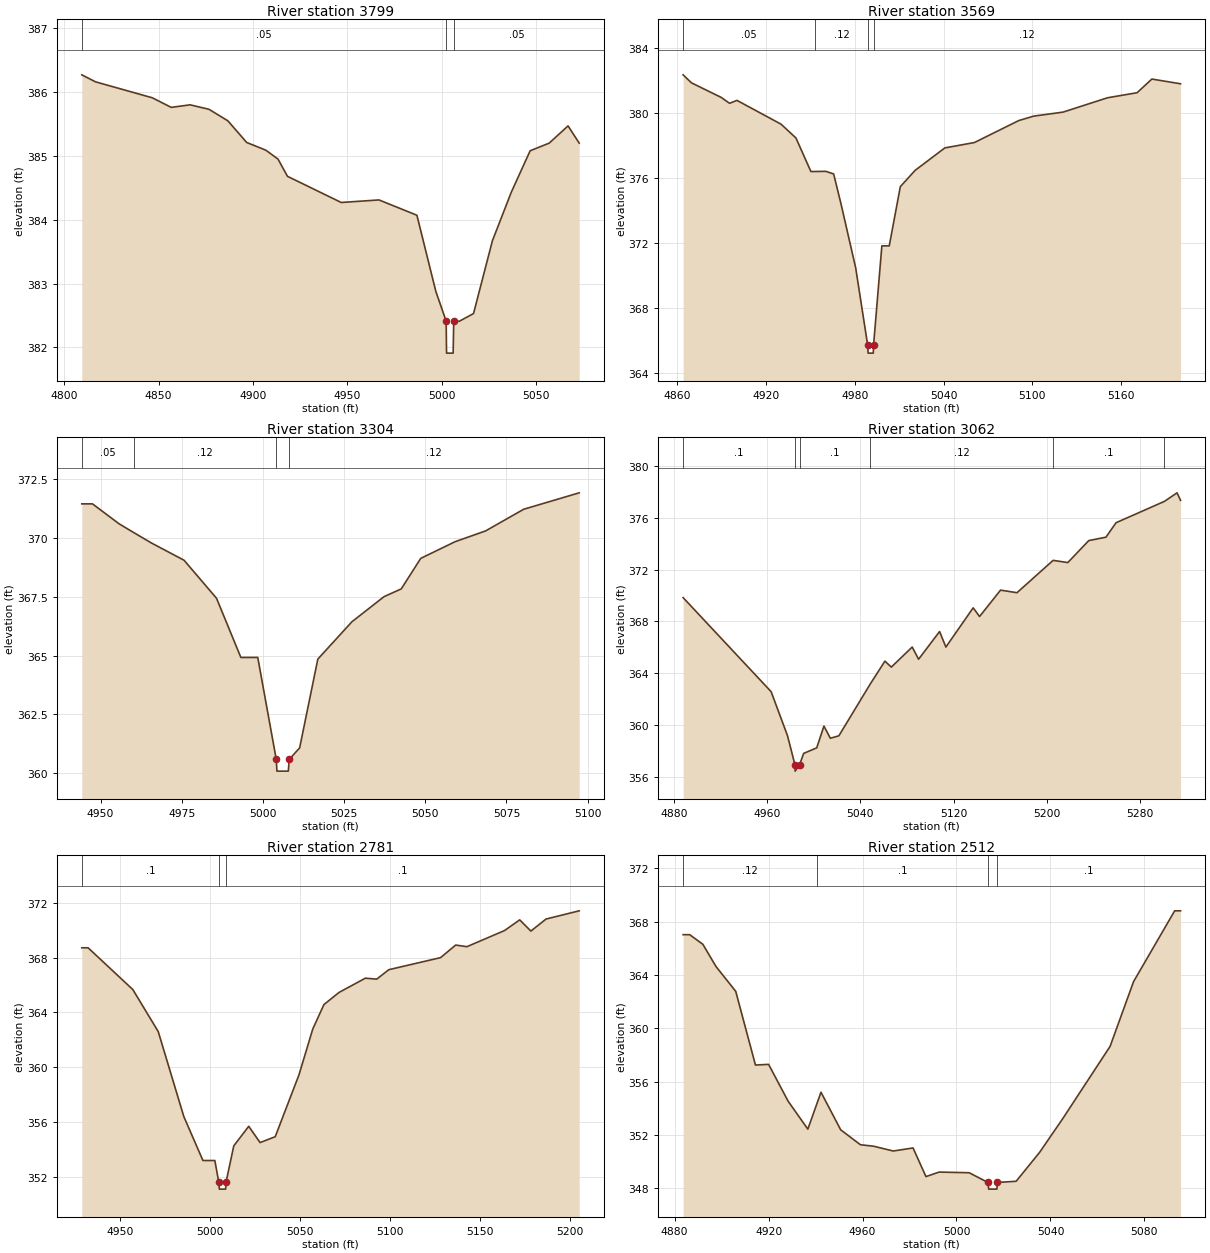
Type RM Length L Ch R = 1,3799,230,230,230
BEGIN DESCRIPTION:
Lynn Creek T6 12.0
END DESCRIPTION:
XS GIS Cut Line= 3
      2723736.72      6783863.69      2723726.00      6784061.00
      2723723.04      6784126.93
#Sta/Elev= 27
  4809.3  386.27  4816.6  386.16  4846.7  385.91  4856.7  385.76  4866.7  385.80
  4876.7  385.73  4886.7  385.55  4896.7  385.21  4906.8  385.09  4913.3  384.95
  4918.3  384.68  4946.8  384.27  4966.8  384.31  4986.9  384.07  4996.9  382.88
  5002.4  382.41  5002.6  381.91  5006.1  381.91  5006.4  382.41  5009.4  382.41
  5016.9  382.53  5026.9  383.67  5036.9  384.43  5046.9  385.08  5057.0  385.20
  5067.0  385.47  5072.9  385.20
#Mann=3,-1,0
  4809.3    0.05       0  5002.4    0.04       0  5006.4    0.05       0
Bank Sta=5002.4,5006.4
Exp/Cntr=0.3,0.1

Type RM Length L Ch R = 1,3569,265,265,265
BEGIN DESCRIPTION:
Lynn Creek T6 11.0
END DESCRIPTION:
XS GIS Cut Line= 3
      2723545.57      6783825.48      2723526.00      6783961.00
      2723533.37      6784160.34
#Sta/Elev= 30
  4863.9  382.35  4869.5  381.86  4889.7  380.96  4895.3  380.60  4900.3  380.78
  4930.1  379.32  4940.2  378.47  4950.3  376.41  4953.3  376.41  4960.4  376.42
  4965.7  376.26  4970.7  374.41  4980.6  370.49  4988.7  365.75  4989.0  365.25
  4992.5  365.25  4992.7  365.75  4998.3  371.84  5003.3  371.84  5010.8  375.48
  5020.8  376.48  5040.9  377.86  5060.9  378.19  5090.9  379.54  5100.9  379.81
  5120.9  380.06  5150.9  380.94  5170.9  381.25  5180.9  382.09  5200.3  381.80
#Mann=4,-1,0
  4863.9    0.05       0  4953.3    0.12       0  4988.7    0.07       0
  4992.7    0.12       0
Bank Sta=4988.7,4992.7
Exp/Cntr=0.3,0.1

Type RM Length L Ch R = 1,3304,242,242,242
BEGIN DESCRIPTION:
Lynn Creek T6 10.0
END DESCRIPTION:
XS GIS Cut Line= 3
      2723275.35      6783959.49      2723276.00      6784011.00
      2723309.01      6784107.17
#Sta/Elev= 24
  4944.2  371.46  4947.5  371.46  4955.7  370.61  4960.3  370.23  4965.7  369.79
  4975.7  369.06  4985.7  367.44  4993.2  364.92  4995.7  364.92  4998.4  364.92
  5004.1  360.58  5004.3  360.08  5007.8  360.08  5008.1  360.58  5011.3  361.07
  5016.9  364.85  5027.4  366.44  5037.3  367.51  5042.6  367.84  5048.6  369.14
  5059.2  369.85  5068.6  370.31  5080.3  371.23  5097.4  371.93
#Mann=4,-1,0
  4944.2    0.05       0  4960.3    0.12       0  5004.1    0.07       0
  5008.1    0.12       0
Bank Sta=5004.1,5008.1
Exp/Cntr=0.3,0.1

Type RM Length L Ch R = 1,3062,281,281,281
BEGIN DESCRIPTION:
Lynn Creek T6 9.0
END DESCRIPTION:
XS GIS Cut Line= 3
      2723025.98      6784060.99      2723126.00      6784111.00
      2723414.65      6784236.80
#Sta/Elev= 30
  4888.0  369.84  4963.5  362.57  4977.5  359.18  4983.9  356.93  4984.1  356.43
  4987.9  356.93  4991.4  357.80  5002.6  358.23  5008.8  359.91  5014.3  358.97
  5021.6  359.16  5048.5  363.16  5061.1  364.93  5066.6  364.47  5084.5  366.02
  5090.0  365.08  5108.0  367.22  5113.4  366.02  5136.8  369.05  5142.3  368.38
  5160.3  370.42  5174.4  370.22  5205.4  372.72  5218.0  372.55  5236.0  374.25
  5250.7  374.51  5259.4  375.63  5300.9  377.28  5311.7  377.94  5314.7  377.36
#Mann=6,-1,0
  4888.0     0.1       0  4983.9    0.07       0  4987.9     0.1       0
  5048.5    0.12       0  5205.4     0.1       0  5300.9    0.12       0
Bank Sta=4983.9,4987.9
Exp/Cntr=0.3,0.1

Type RM Length L Ch R = 1,2781,269,269,269
BEGIN DESCRIPTION:
Lynn Creek T6 8.0
END DESCRIPTION:
XS GIS Cut Line= 3
      2722875.99      6784210.99      2722926.00      6784261.00
      2723090.76      6784383.27
#Sta/Elev= 30
  4929.0  368.71  4932.5  368.71  4957.3  365.66  4971.4  362.59  4985.6  356.38
  4996.2  353.17  5002.8  353.17  5005.0  351.58  5005.3  351.08  5008.8  351.08
  5009.0  351.58  5013.3  354.24  5021.6  355.67  5027.9  354.48  5036.3  354.91
  5049.5  359.44  5057.1  362.77  5063.3  364.56  5071.7  365.45  5086.3  366.49
  5092.6  366.42  5099.3  367.11  5128.0  367.99  5136.4  368.91  5142.6  368.79
  5163.5  369.97  5171.9  370.75  5178.1  369.93  5186.5  370.81  5204.9  371.41
#Mann=3,-1,0
  4929.0     0.1       0  5005.0    0.07       0  5009.0     0.1       0
Bank Sta=5005,5009
Exp/Cntr=0.3,0.1

Type RM Length L Ch R = 1,2512,263,263,263
BEGIN DESCRIPTION:
Lynn Creek T6 7.0
END DESCRIPTION:
XS GIS Cut Line= 3
      2722726.01      6784210.98      2722676.00      6784311.00
      2722676.00      6784410.97
#Sta/Elev= 30
  4883.6  367.03  4886.4  367.03  4892.0  366.31  4897.6  364.64  4906.0  362.78
  4914.4  357.25  4920.0  357.30  4928.3  354.54  4936.7  352.44  4940.6  354.37
  4942.3  355.21  4950.7  352.39  4959.1  351.27  4964.7  351.16  4973.1  350.80
  4981.5  351.03  4987.0  348.88  4992.6  349.22  5005.4  349.17  5013.4  348.44
  5013.7  347.94  5017.2  347.94  5017.4  348.44  5025.4  348.53  5035.4  350.70
  5045.4  353.27  5065.4  358.65  5075.4  363.51  5092.9  368.82  5095.4  368.82
#Mann=4,-1,0
  4883.6    0.12       0  4940.6     0.1       0  5013.4    0.07       0
  5017.4     0.1       0
Bank Sta=5013.4,5017.4
Exp/Cntr=0.3,0.1

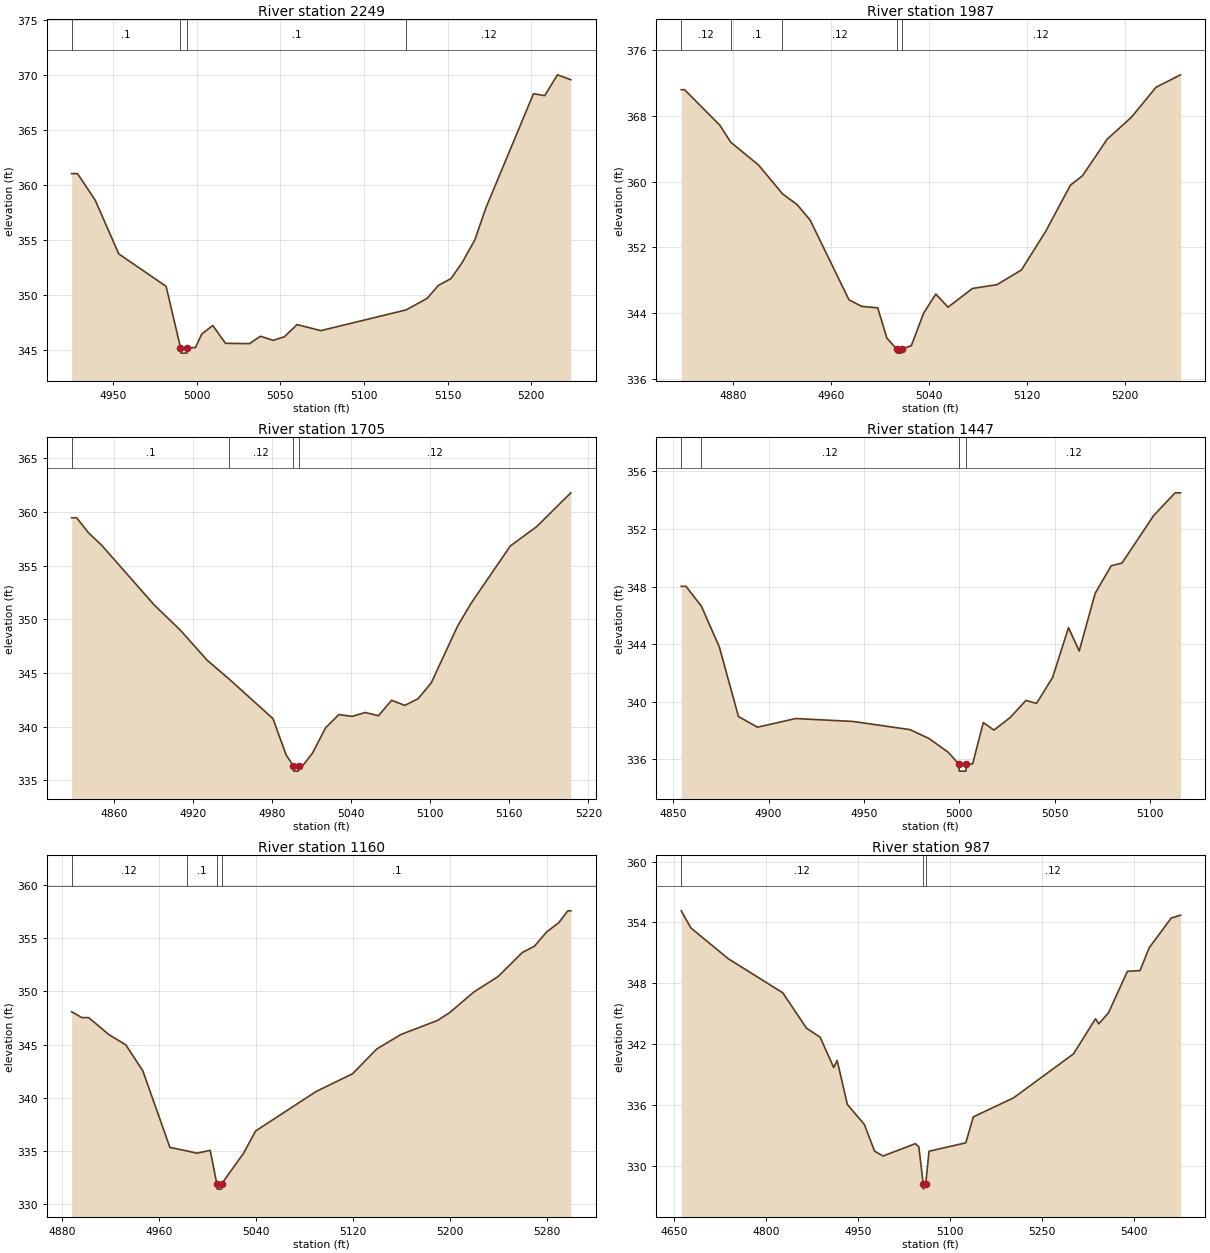
Type RM Length L Ch R = 1,2249,262,262,262
BEGIN DESCRIPTION:
Lynn Creek T6 6.0
END DESCRIPTION:
XS GIS Cut Line= 3
      2722376.03      6784311.03      2722426.00      6784361.00
      2722575.53      6784532.90
#Sta/Elev= 30
  4925.2  361.04  4928.7  361.04  4939.3  358.63  4953.4  353.75  4981.7  350.81
  4990.3  345.25  4990.6  344.75  4994.1  344.75  4994.3  345.25  4999.2  345.25
  5003.0  346.48  5009.6  347.26  5017.2  345.64  5031.5  345.61  5038.1  346.28
  5045.7  345.91  5052.4  346.23  5060.0  347.34  5074.2  346.79  5125.2  348.67
  5137.8  349.72  5144.5  350.89  5152.1  351.52  5158.7  352.96  5166.3  355.02
  5172.9  357.92  5201.4  368.29  5208.1  368.11  5215.7  370.00  5223.7  369.56
#Mann=4,-1,0
  4925.2     0.1       0  4990.3    0.07       0  4994.3     0.1       0
  5125.2    0.12       0
Bank Sta=4990.3,4994.3
Exp/Cntr=0.3,0.1

Type RM Length L Ch R = 1,1987,282,282,282
BEGIN DESCRIPTION:
Lynn Creek T6 5.0
END DESCRIPTION:
XS GIS Cut Line= 3
      2722125.98      6784510.99      2722276.00      6784561.00
      2722525.96      6784561.00
#Sta/Elev= 30
  4837.6  371.22  4840.3  371.22  4869.2  366.88  4878.0  364.83  4900.9  362.02
  4920.2  358.56  4932.5  357.19  4943.0  355.32  4974.7  345.62  4985.2  344.81
  4998.2  344.64  5005.7  340.95  5013.7  339.62  5014.0  339.12  5017.5  339.12
  5017.7  339.62  5025.7  340.03  5035.7  343.98  5045.7  346.32  5055.7  344.72
  5075.7  347.00  5095.7  347.46  5115.7  349.25  5135.7  354.00  5155.7  359.58
  5165.7  360.75  5185.7  365.17  5205.7  367.88  5225.7  371.51  5245.7  373.03
#Mann=5,-1,0
  4837.6    0.12       0  4878.0     0.1       0  4920.2    0.12       0
  5013.7    0.07       0  5017.7    0.12       0
Bank Sta=5013.7,5017.7
Exp/Cntr=0.3,0.1

Type RM Length L Ch R = 1,1705,258,258,258
BEGIN DESCRIPTION:
Lynn Creek T6 4.0
END DESCRIPTION:
XS GIS Cut Line= 3
      2722103.35      6784810.27      2722276.00      6784811.00
      2722481.94      6784811.29
#Sta/Elev= 30
  4828.0  359.47  4831.8  359.47  4840.7  358.08  4850.7  356.92  4890.7  351.34
  4910.7  348.97  4930.7  346.21  4947.6  344.43  4980.7  340.76  4990.7  337.37
  4996.2  336.37  4996.4  335.87  4999.9  335.87  5000.2  336.37  5003.2  336.37
  5010.7  337.55  5020.7  339.92  5030.7  341.14  5040.7  340.97  5050.7  341.33
  5060.7  341.03  5070.7  342.47  5080.7  341.99  5090.7  342.61  5100.7  344.08
  5120.7  349.37  5130.7  351.45  5160.7  356.84  5180.7  358.64  5206.6  361.79
#Mann=4,-1,0
  4828.0     0.1       0  4947.6    0.12       0  4996.2    0.07       0
  5000.2    0.12       0
Bank Sta=4996.2,5000.2
Exp/Cntr=0.3,0.1

Type RM Length L Ch R = 1,1447,287,287,287
BEGIN DESCRIPTION:
Lynn Creek T6 3.0
END DESCRIPTION:
XS GIS Cut Line= 3
      2722225.99      6785011.00      2722376.00      6785011.00
      2722475.99      6784961.01
#Sta/Elev= 30
  4854.2  348.02  4856.7  348.02  4864.8  346.63  4874.2  343.80  4884.2  338.98
  4894.2  338.24  4914.2  338.84  4944.2  338.64  4974.2  338.07  4984.2  337.45
  4994.2  336.50  4999.7  335.69  5000.0  335.19  5003.5  335.19  5003.7  335.69
  5007.0  335.69  5012.6  338.56  5018.2  338.04  5026.6  338.90  5035.0  340.10
  5040.5  339.89  5048.9  341.68  5057.3  345.15  5062.9  343.53  5071.3  347.54
  5079.7  349.45  5085.3  349.63  5102.0  352.94  5113.2  354.51  5116.0  354.51
#Mann=4,-1,0
  4854.2     0.1       0  4864.8    0.12       0  4999.7    0.07       0
  5003.7    0.12       0
Bank Sta=4999.7,5003.7
Exp/Cntr=0.3,0.1

Type RM Length L Ch R = 1,1160,173,173,173
BEGIN DESCRIPTION:
Lynn Creek T6 2.0
END DESCRIPTION:
XS GIS Cut Line= 3
      2722176.00      6785211.00      2722276.00      6785261.00
      2722575.99      6785261.00
#Sta/Elev= 30
  4888.1  348.08  4896.5  347.53  4902.1  347.53  4918.9  345.93  4932.8  344.97
  4946.8  342.54  4969.2  335.34  4983.1  335.02  4991.5  334.80  5002.4  335.07
  5007.9  331.93  5008.2  331.43  5011.7  331.43  5011.9  331.93  5029.9  334.79
  5039.9  336.89  5089.9  340.60  5119.9  342.26  5139.9  344.59  5159.9  345.95
  5189.9  347.26  5199.9  347.99  5219.9  349.93  5239.9  351.38  5259.9  353.64
  5269.9  354.23  5279.9  355.56  5289.9  356.43  5297.4  357.55  5299.9  357.55
#Mann=4,-1,0
  4888.1    0.12       0  4983.1     0.1       0  5007.9    0.07       0
  5011.9     0.1       0
Bank Sta=5007.9,5011.9
Exp/Cntr=0.3,0.1

Type RM Length L Ch R = 1,987,235,235,235
BEGIN DESCRIPTION:
Mapping XS 1ffcd190
END DESCRIPTION:
XS GIS Cut Line= 3
      2722065.80      6785108.14      2722292.79      6785550.64
      2722599.89      6785473.36
#Sta/Elev= 30
  4661.8  355.14  4677.5  353.45  4738.5  350.41  4827.3  347.05  4866.0  343.56
  4888.2  342.67  4910.4  339.67  4916.0  340.37  4932.6  336.03  4960.4  334.05
  4977.0  331.42  4990.9  330.94  5043.6  332.16  5049.2  331.84  5056.4  328.17
  5056.6  327.67  5060.4  328.17  5065.8  331.41  5125.8  332.24  5138.0  334.80
  5203.7  336.68  5301.4  341.02  5337.3  344.49  5342.5  343.98  5358.4  345.07
  5389.3  349.17  5409.9  349.24  5424.7  351.48  5460.7  354.42  5475.8  354.71
#Mann=3,-1,0
  4661.8    0.12       0  5056.4    0.07       0  5060.4    0.12       0
Bank Sta=5056.4,5060.4
Exp/Cntr=0.3,0.1

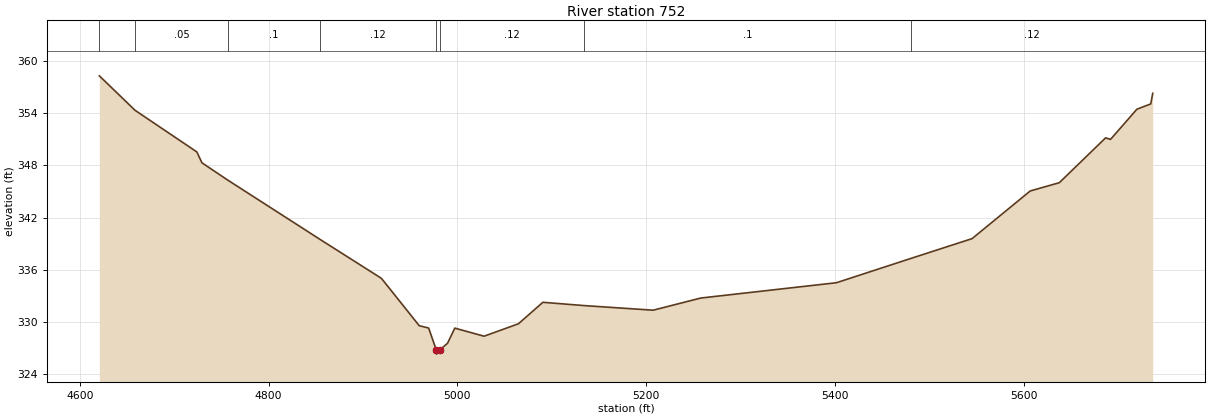
Type RM Length L Ch R = 1,752,0,0,0
BEGIN DESCRIPTION:
Lynn Creek T6 1.0
END DESCRIPTION:
XS GIS Cut Line= 4
      2721987.28      6785082.34      2722001.00      6785461.39
      2722059.89      6785631.25      2722602.40      6785505.38
#Sta/Elev= 30
  4620.7  358.30  4658.5  354.34  4724.0  349.55  4729.4  348.30  4756.6  346.32
  4854.7  339.48  4919.6  335.01  4959.6  329.57  4969.6  329.30  4977.6  326.80
  4977.8  326.30  4981.6  326.80  4989.6  327.55  4997.3  329.29  5028.3  328.36
  5064.7  329.79  5090.6  332.26  5134.4  331.88  5207.4  331.35  5257.9  332.75
  5401.6  334.51  5480.1  337.29  5545.3  339.58  5606.9  345.06  5637.7  346.01
  5686.8  351.17  5692.0  350.99  5719.9  354.46  5734.6  355.07  5736.7  356.29
#Mann=8,-1,0
  4620.7     0.1       0  4658.5    0.05       0  4756.6     0.1       0
  4854.7    0.12       0  4977.6    0.07       0  4981.6    0.12       0
  5134.4     0.1       0  5480.1    0.12       0
Bank Sta=4977.6,4981.6
Exp/Cntr=0.3,0.1

Chan Stop Cuts=-1