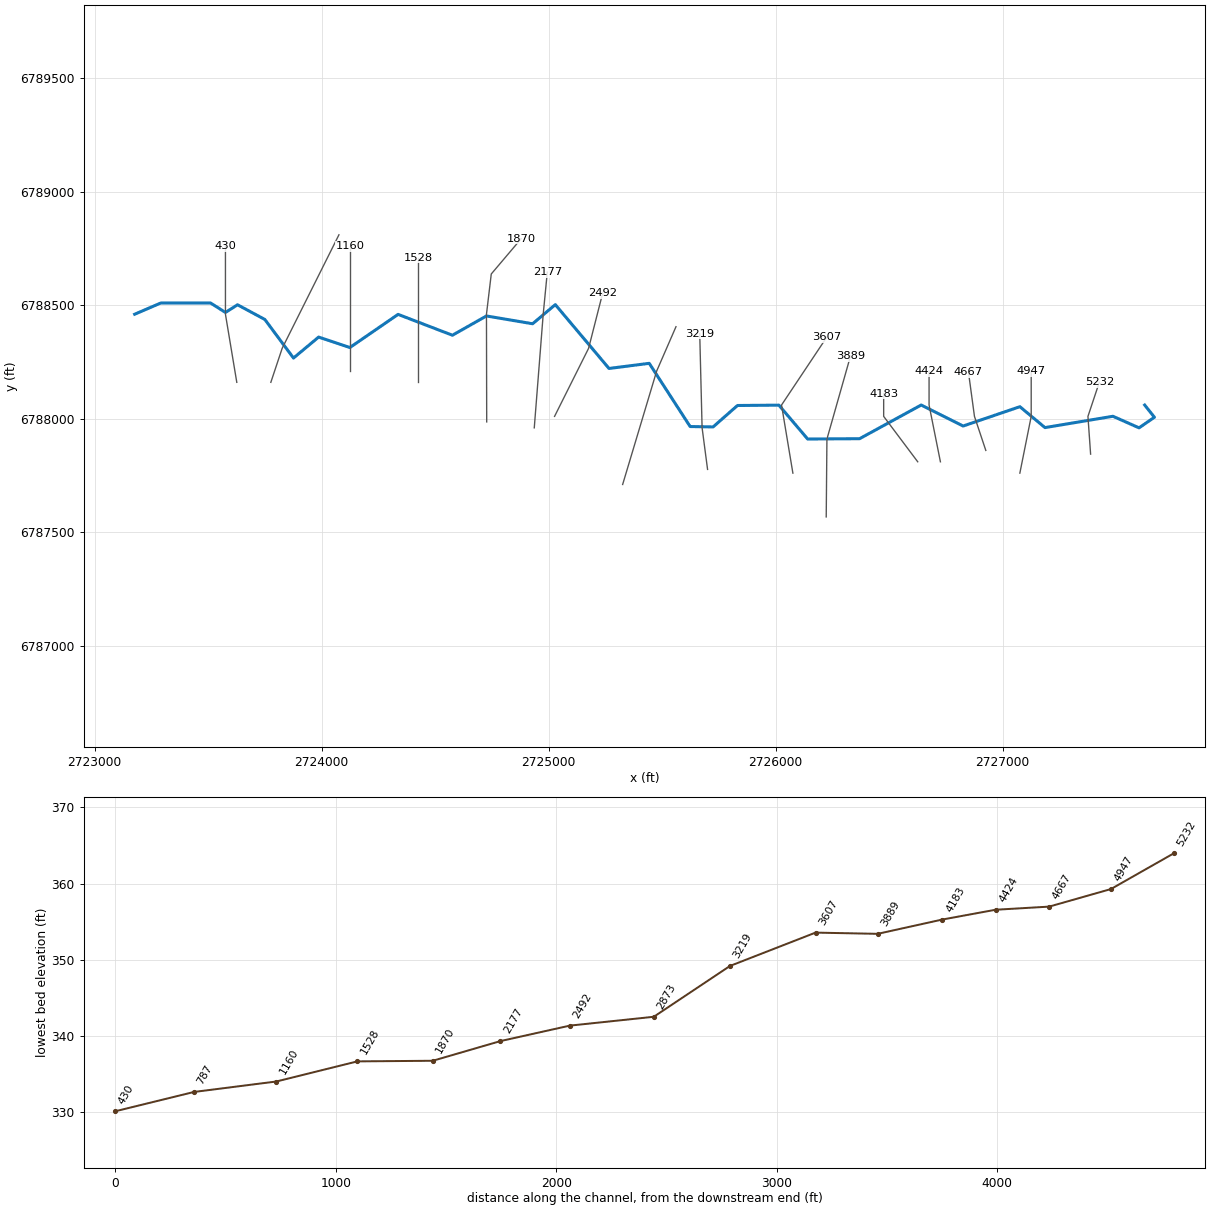
--- Lynn Creek T7.prj (project) ---

Proj Title=Lynn Creek T7 Base Level Engineering
Current Plan=p01
Default Exp/Contr=0.3,0.1
English Units
Geom File=g01
Flow File=f01
Plan File=p01
BEGIN DESCRIPTION:
Lynn Creek T7
END DESCRIPTION:

--- Lynn Creek T7.p01 (plan) ---

Plan Title=Multiple Run
Short Identifier=Multiple
Geom File=g01
Flow File=f01
Subcritical Flow
K Sum by GR= 0
Std Step Tol= 0.01
Critical Tol= 0.01
Num of Std Step Trials= 20
Max Error Tol= 0.3
Flow Tol Ratio= 0.001
Split Flow NTrial= 30
Split Flow Tol= 0.02
Split Flow Ratio= 0.02
Log Output Level= 0
Friction Slope Method= 1
Unsteady Friction Slope Method= 2
Unsteady Bridges Friction Slope Method= 1
Parabolic Critical Depth
Global Vel Dist=  1 , 1 , 1
Global Log Level= 0
CheckData=True
Encroach Param= -1, 0, 0, 0
BEGIN DESCRIPTION:
Multiple Run
END DESCRIPTION:

--- Lynn Creek T7.f01 (steady flow) ---

Flow Title=Multiple
Number of Profiles=7
Profile Names=10-year,25-year,50-year,1pct_min,100-year,1pct_plu,500-year
River Rch & RM= Lynn Creek T7,Reach-1,5232
     268     339     394     227     454     905     600
River Rch & RM= Lynn Creek T7,Reach-1,3889
     360     465     547     319     637    1272     865
River Rch & RM= Lynn Creek T7,Reach-1,3219
     621     833    1003     600    1197    2387    1701
Boundary for River Rch & Prof#=Lynn Creek T7,Reach-1,1
Up Type=0
Dn Type=3
Dn Slope=0.005
Boundary for River Rch & Prof#=Lynn Creek T7,Reach-1,2
Up Type=0
Dn Type=3
Dn Slope=0.005
Boundary for River Rch & Prof#=Lynn Creek T7,Reach-1,3
Up Type=0
Dn Type=3
Dn Slope=0.005
Boundary for River Rch & Prof#=Lynn Creek T7,Reach-1,4
Up Type=0
Dn Type=3
Dn Slope=0.005
Boundary for River Rch & Prof#=Lynn Creek T7,Reach-1,5
Up Type=0
Dn Type=3
Dn Slope=0.005
Boundary for River Rch & Prof#=Lynn Creek T7,Reach-1,6
Up Type=0
Dn Type=3
Dn Slope=0.005
Boundary for River Rch & Prof#=Lynn Creek T7,Reach-1,7
Up Type=0
Dn Type=3
Dn Slope=0.005

--- Lynn Creek T7.g01 (geometry) ---

Geom Title=Existing Conditions

River Reach=Lynn Creek T7,Reach-1
Reach XY= 30
      2727626.00      6788061.00      2727668.89      6788007.24
      2727601.19      6787960.48      2727486.19      6788011.45
      2727186.62      6787961.61      2727076.10      6788053.67
      2726825.99      6787968.53      2726641.34      6788061.04
      2726369.86      6787912.70      2726141.03      6787911.32
      2726014.38      6788060.50      2725831.84      6788058.98
      2725724.50      6787964.47      2725623.33      6787966.29
      2725443.13      6788244.75      2725265.92      6788222.09
      2725029.33      6788503.39      2724929.34      6788419.02
      2724726.00      6788453.44      2724576.01      6788368.53
      2724336.62      6788460.40      2724124.28      6788314.34
      2723986.62      6788360.38      2723875.78      6788268.00
      2723749.51      6788438.02      2723629.23      6788502.76
      2723576.10      6788468.80      2723510.84      6788510.35
      2723291.19      6788510.55      2723176.00      6788461.00

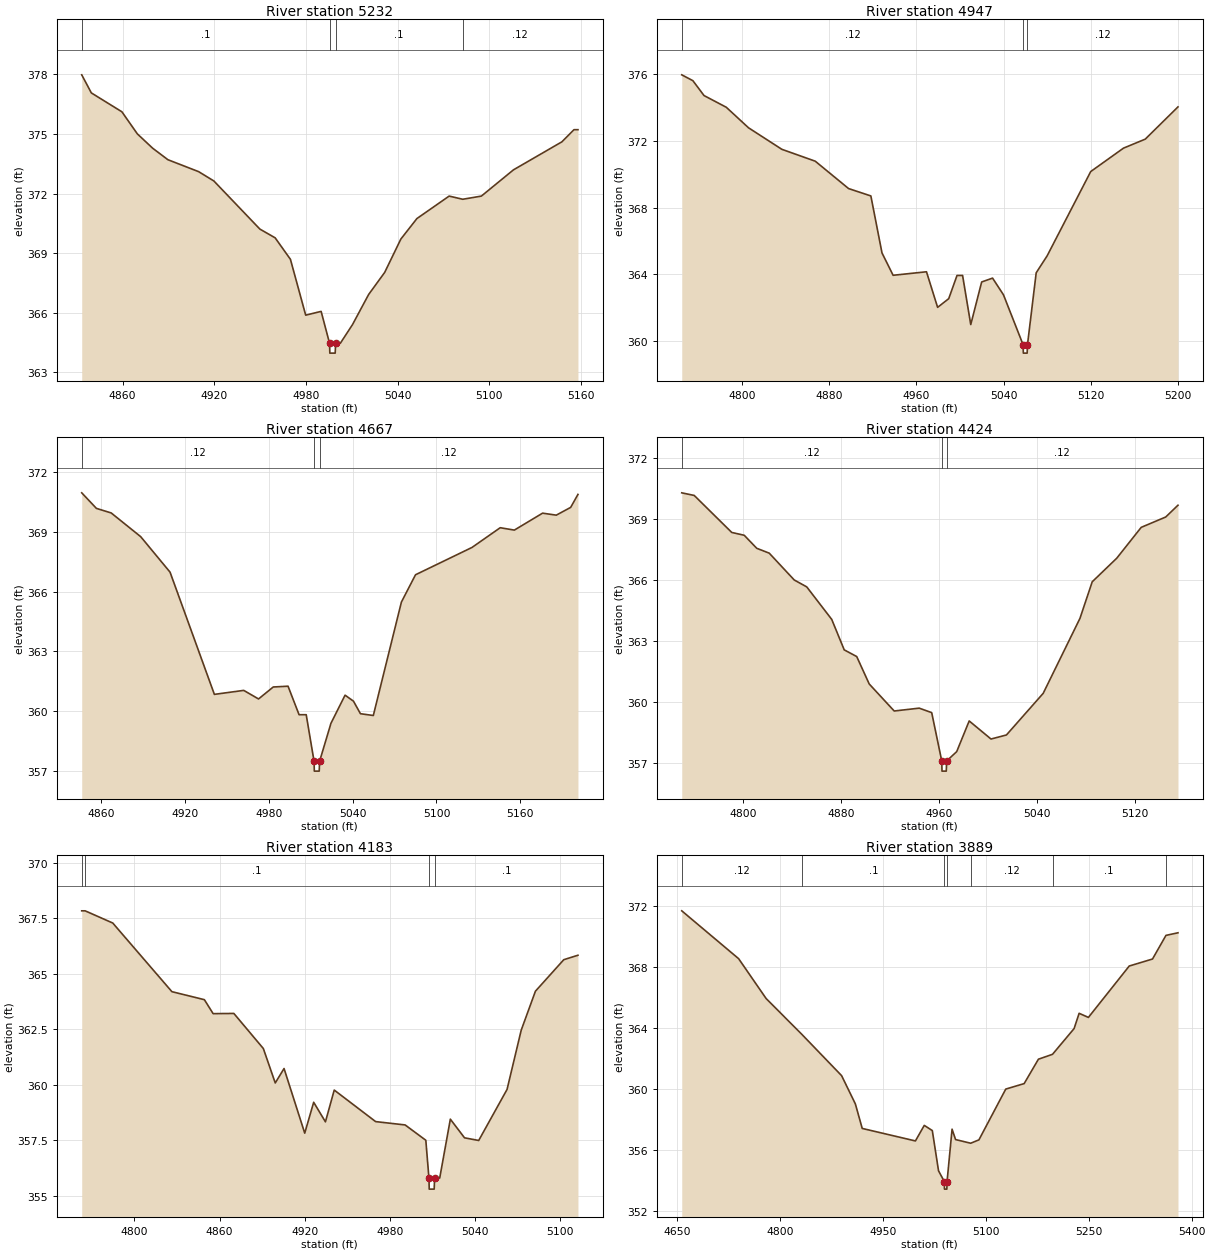
Type RM Length L Ch R = 1,5232,285,285,285
BEGIN DESCRIPTION:
Lynn Creek T7 16.0
END DESCRIPTION:
XS GIS Cut Line= 3
      2727387.71      6787844.72      2727376.00      6788011.00
      2727426.00      6788160.99
#Sta/Elev= 30
  4833.2  377.97  4839.5  377.06  4859.5  376.11  4869.6  375.00  4879.6  374.28
  4889.6  373.70  4909.7  373.10  4919.7  372.63  4949.8  370.21  4959.8  369.77
  4969.8  368.69  4979.8  365.88  4989.9  366.07  4995.4  364.47  4995.6  363.97
  4999.1  363.97  4999.4  364.47  5002.5  364.47  5010.4  365.40  5021.0  366.92
  5031.5  368.03  5042.1  369.71  5052.6  370.74  5073.7  371.87  5082.6  371.71
  5094.8  371.87  5115.8  373.19  5147.5  374.60  5155.4  375.21  5158.0  375.21
#Mann=4,-1,0
  4833.2     0.1       0  4995.4    0.07       0  4999.4     0.1       0
  5082.6    0.12       0
Bank Sta=4995.4,4999.4
Exp/Cntr=0.3,0.1

Type RM Length L Ch R = 1,4947,280,280,280
BEGIN DESCRIPTION:
Lynn Creek T7 15.0
END DESCRIPTION:
XS GIS Cut Line= 3
      2727075.99      6787760.96      2727126.00      6788011.00
      2727126.00      6788211.01
#Sta/Elev= 30
  4744.9  375.95  4755.1  375.60  4765.3  374.71  4785.7  374.01  4806.1  372.78
  4836.7  371.49  4867.3  370.78  4897.9  369.14  4918.3  368.70  4928.5  365.29
  4938.7  363.95  4969.3  364.16  4979.5  362.03  4989.7  362.55  4997.3  363.94
  5002.4  363.94  5009.9  361.00  5019.9  363.55  5029.9  363.78  5039.9  362.78
  5057.9  359.79  5058.1  359.29  5061.6  359.29  5061.9  359.79  5069.9  364.10
  5079.9  365.11  5119.9  370.16  5149.9  371.56  5169.9  372.10  5199.9  374.03
#Mann=3,-1,0
  4744.9    0.12       0  5057.9    0.07       0  5061.9    0.12       0
Bank Sta=5057.9,5061.9
Exp/Cntr=0.3,0.1

Type RM Length L Ch R = 1,4667,243,243,243
BEGIN DESCRIPTION:
Lynn Creek T7 14.0
END DESCRIPTION:
XS GIS Cut Line= 3
      2726926.00      6787861.01      2726876.00      6788011.00
      2726849.55      6788206.11
#Sta/Elev= 30
  4846.2  370.95  4856.7  370.17  4867.3  369.94  4888.4  368.75  4909.4  366.97
  4941.1  360.84  4962.1  361.04  4972.7  360.61  4983.2  361.21  4993.8  361.25
  5001.7  359.82  5006.8  359.82  5012.4  357.49  5012.6  356.99  5016.1  356.99
  5016.4  357.49  5024.5  359.39  5034.6  360.80  5040.6  360.50  5045.6  359.87
  5054.8  359.78  5074.9  365.47  5085.0  366.84  5125.4  368.21  5145.6  369.20
  5155.7  369.08  5175.9  369.93  5185.7  369.83  5196.0  370.22  5201.2  370.87
#Mann=3,-1,0
  4846.2    0.12       0  5012.4    0.07       0  5016.4    0.12       0
Bank Sta=5012.4,5016.4
Exp/Cntr=0.3,0.1

Type RM Length L Ch R = 1,4424,241,241,241
BEGIN DESCRIPTION:
Lynn Creek T7 13.0
END DESCRIPTION:
XS GIS Cut Line= 3
      2726726.00      6787810.98      2726676.00      6788061.00
      2726676.00      6788211.03
#Sta/Elev= 30
  4749.8  370.28  4760.0  370.15  4790.6  368.33  4800.8  368.19  4811.0  367.55
  4821.2  367.31  4841.6  365.99  4851.8  365.65  4872.2  364.05  4882.4  362.55
  4892.6  362.22  4902.8  360.87  4923.2  359.54  4943.6  359.68  4953.8  359.46
  4962.0  357.08  4962.2  356.58  4965.7  356.58  4966.0  357.08  4974.2  357.54
  4984.4  359.05  5002.2  358.16  5014.8  358.36  5044.8  360.41  5074.8  364.10
  5084.8  365.90  5104.8  367.06  5124.8  368.58  5144.8  369.09  5154.8  369.67
#Mann=3,-1,0
  4749.8    0.12       0  4962.0    0.07       0  4966.0    0.12       0
Bank Sta=4962,4966
Exp/Cntr=0.3,0.1

Type RM Length L Ch R = 1,4183,294,294,294
BEGIN DESCRIPTION:
Lynn Creek T7 12.0
END DESCRIPTION:
XS GIS Cut Line= 3
      2726626.01      6787810.98      2726476.00      6788011.00
      2726476.00      6788110.98
#Sta/Elev= 30
  4762.8  367.83  4765.2  367.83  4784.7  367.28  4826.4  364.19  4849.3  363.83
  4855.5  363.20  4870.1  363.21  4890.9  361.63  4899.3  360.08  4905.5  360.73
  4920.1  357.82  4926.4  359.21  4934.7  358.33  4940.9  359.76  4970.1  358.34
  4990.9  358.19  5005.5  357.50  5007.7  355.80  5007.9  355.30  5011.4  355.30
  5011.7  355.80  5015.3  355.80  5022.8  358.45  5032.8  357.61  5042.8  357.49
  5062.8  359.79  5072.8  362.46  5082.8  364.21  5102.8  365.63  5112.8  365.83
#Mann=4,-1,0
  4762.8    0.12       0  4765.2     0.1       0  5007.7    0.07       0
  5011.7     0.1       0
Bank Sta=5007.7,5011.7
Exp/Cntr=0.3,0.1

Type RM Length L Ch R = 1,3889,282,282,282
BEGIN DESCRIPTION:
Lynn Creek T7 11.0
END DESCRIPTION:
XS GIS Cut Line= 3
      2726222.89      6787568.11      2726226.00      6787911.00
      2726329.77      6788276.56
#Sta/Elev= 30
  4657.2  371.67  4740.1  368.53  4780.1  365.92  4833.0  363.53  4890.1  360.86
  4910.1  359.01  4920.1  357.40  4997.6  356.58  5010.5  357.60  5022.2  357.26
  5031.3  354.62  5039.7  353.92  5039.9  353.42  5043.4  353.42  5043.7  353.92
  5051.0  357.35  5056.1  356.67  5078.1  356.43  5090.1  356.65  5129.2  359.98
  5156.0  360.34  5176.8  361.94  5197.3  362.26  5228.8  363.95  5236.1  364.95
  5249.6  364.68  5309.1  368.05  5343.0  368.51  5362.6  370.06  5380.1  370.23
#Mann=7,-1,0
  4657.2    0.12       0  4833.0     0.1       0  5039.7    0.07       0
  5043.7     0.1       0  5078.1    0.12       0  5197.3     0.1       0
  5362.6    0.05       0
Bank Sta=5039.7,5043.7
Exp/Cntr=0.3,0.1

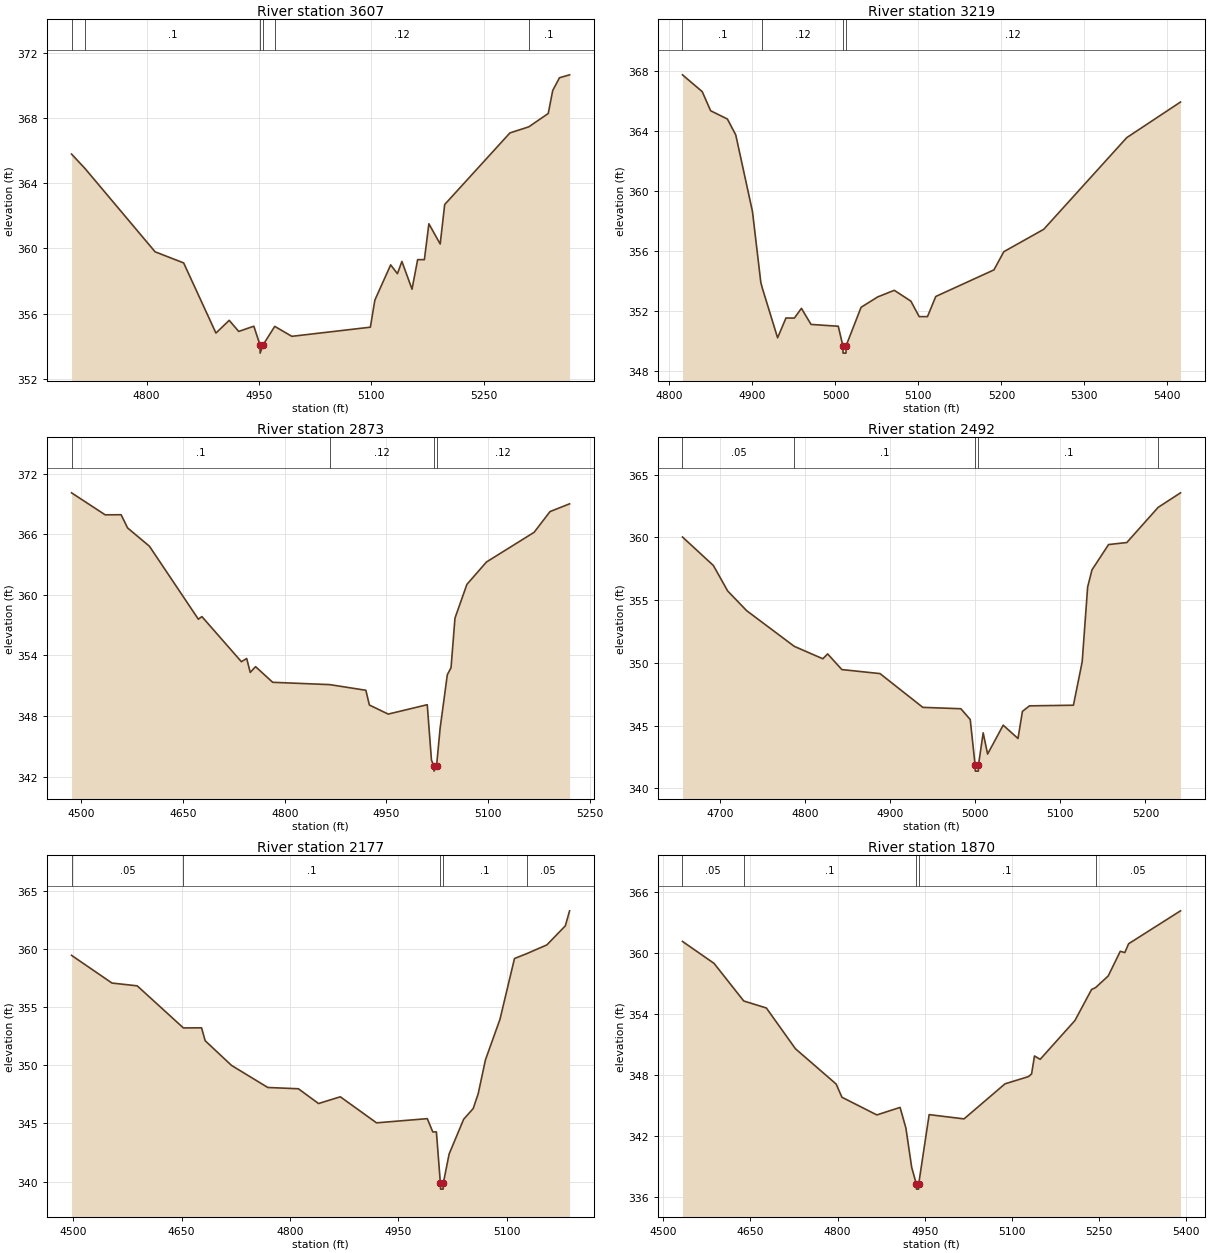
Type RM Length L Ch R = 1,3607,388,388,388
BEGIN DESCRIPTION:
Lynn Creek T7 10.0
END DESCRIPTION:
XS GIS Cut Line= 3
      2726076.01      6787760.97      2726026.00      6788061.00
      2726225.99      6788360.98
#Sta/Elev= 30
  4699.9  365.78  4717.8  364.90  4811.4  359.79  4849.5  359.11  4892.6  354.81
  4910.3  355.59  4923.0  354.91  4943.2  355.23  4951.4  354.08  4951.6  353.58
  4955.4  354.08  4971.1  355.22  4993.9  354.61  5098.7  355.17  5104.7  356.83
  5125.8  358.99  5134.8  358.45  5140.8  359.20  5154.3  357.50  5161.8  359.31
  5170.8  359.31  5176.8  361.51  5191.9  360.27  5197.9  362.69  5285.0  367.08
  5310.1  367.45  5336.1  368.27  5342.1  369.68  5351.1  370.46  5364.6  370.64
#Mann=6,-1,0
  4699.9    0.12       0  4717.8     0.1       0  4951.4    0.07       0
  4955.4     0.1       0  4971.1    0.12       0  5310.1     0.1       0
Bank Sta=4951.4,4955.4
Exp/Cntr=0.3,0.1

Type RM Length L Ch R = 1,3219,346,346,346
BEGIN DESCRIPTION:
Lynn Creek T7 9.0
END DESCRIPTION:
XS GIS Cut Line= 3
      2725700.13      6787777.38      2725676.00      6787961.00
      2725665.57      6788375.77
#Sta/Elev= 30
  4815.7  367.73  4839.5  366.61  4849.6  365.34  4869.8  364.79  4879.9  363.73
  4900.0  358.64  4910.1  353.91  4912.1  353.50  4930.3  350.23  4940.4  351.55
  4950.5  351.54  4959.0  352.19  4970.6  351.12  5003.4  351.00  5008.9  349.71
  5009.2  349.21  5012.7  349.21  5012.9  349.71  5030.9  352.26  5050.9  352.95
  5070.9  353.39  5090.9  352.67  5100.9  351.64  5110.9  351.64  5120.9  352.98
  5191.0  354.75  5202.9  355.96  5251.0  357.45  5351.0  363.55  5415.8  365.92
#Mann=4,-1,0
  4815.7     0.1       0  4912.1    0.12       0  5008.9    0.07       0
  5012.9    0.12       0
Bank Sta=5008.9,5012.9
Exp/Cntr=0.3,0.1

Type RM Length L Ch R = 1,2873,381,381,381
BEGIN DESCRIPTION:
Lynn Creek T7 8.0
END DESCRIPTION:
XS GIS Cut Line= 3
      2725326.00      6787710.99      2725476.00      6788211.00
      2725560.98      6788406.07
#Sta/Elev= 30
  4485.5  370.11  4535.1  367.93  4558.6  367.94  4568.2  366.63  4600.4  364.82
  4672.6  357.59  4677.8  357.85  4736.1  353.38  4743.9  353.70  4749.1  352.32
  4757.0  352.89  4782.2  351.34  4866.4  351.11  4919.7  350.55  4924.9  349.09
  4952.7  348.19  5010.3  349.12  5016.5  343.64  5020.0  343.04  5020.2  342.54
  5024.0  343.04  5029.3  346.80  5039.9  352.09  5045.4  352.79  5051.2  357.70
  5068.8  361.04  5097.7  363.26  5168.0  366.20  5191.4  368.25  5220.3  369.02
#Mann=4,-1,0
  4485.5     0.1       0  4866.4    0.12       0  5020.0    0.07       0
  5024.0    0.12       0
Bank Sta=5020,5024
Exp/Cntr=0.3,0.1

Type RM Length L Ch R = 1,2492,315,315,315
BEGIN DESCRIPTION:
Lynn Creek T7 7.0
END DESCRIPTION:
XS GIS Cut Line= 3
      2725026.01      6788011.02      2725176.00      6788311.00
      2725237.69      6788552.87
#Sta/Elev= 30
  4656.2  360.03  4692.5  357.76  4709.3  355.73  4731.6  354.16  4787.5  351.32
  4821.1  350.33  4826.7  350.72  4843.4  349.47  4888.2  349.15  4938.5  346.46
  4983.2  346.35  4994.2  345.49  4999.9  341.88  5000.2  341.38  5003.7  341.38
  5003.9  341.88  5009.4  344.43  5014.6  342.74  5032.9  345.04  5050.3  343.98
  5055.5  346.14  5063.8  346.58  5115.4  346.63  5125.7  350.09  5132.1  356.04
  5137.2  357.41  5156.7  359.43  5178.1  359.59  5214.9  362.39  5241.2  363.55
#Mann=5,-1,0
  4656.2    0.05       0  4787.5     0.1       0  4999.9    0.07       0
  5003.9     0.1       0  5214.9    0.12       0
Bank Sta=4999.9,5003.9
Exp/Cntr=0.3,0.1

Type RM Length L Ch R = 1,2177,307,307,307
BEGIN DESCRIPTION:
Lynn Creek T7 6.0
END DESCRIPTION:
XS GIS Cut Line= 3
      2724936.59      6787960.47      2724976.00      6788461.00
      2724994.08      6788646.84
#Sta/Elev= 30
  4497.9  359.45  4553.8  357.07  4588.7  356.83  4652.6  353.21  4677.7  353.22
  4682.7  352.11  4719.1  349.99  4769.3  348.09  4811.6  347.98  4839.5  346.71
  4869.6  347.29  4919.7  345.05  4989.9  345.41  4997.5  344.27  5002.5  344.27
  5008.0  339.85  5008.3  339.35  5011.8  339.35  5012.0  339.85  5020.1  342.37
  5040.2  345.36  5053.4  346.28  5060.3  347.55  5070.3  350.46  5090.4  353.95
  5110.5  359.18  5127.5  359.60  5155.3  360.35  5180.8  361.99  5186.7  363.28
#Mann=5,-1,0
  4497.9    0.05       0  4652.6     0.1       0  5008.0    0.07       0
  5012.0     0.1       0  5127.5    0.05       0
Bank Sta=5008,5012
Exp/Cntr=0.3,0.1

Type RM Length L Ch R = 1,1870,342,342,342
BEGIN DESCRIPTION:
Lynn Creek T7 5.0
END DESCRIPTION:
XS GIS Cut Line= 4
      2724727.04      6787986.74      2724726.00      6788461.00
      2724747.17      6788638.38      2724878.93      6788793.86
#Sta/Elev= 30
  4533.3  361.14  4587.6  358.98  4638.7  355.28  4677.6  354.59  4727.6  350.58
  4797.6  347.11  4807.6  345.81  4867.6  344.07  4907.6  344.81  4917.6  342.78
  4927.6  338.90  4935.6  337.27  4935.8  336.77  4939.3  336.77  4939.6  337.27
  4957.6  344.10  5017.6  343.68  5088.1  347.13  5128.4  347.84  5133.8  348.10
  5138.8  349.87  5148.6  349.54  5208.4  353.36  5237.0  356.41  5244.0  356.60
  5265.6  357.74  5286.4  360.17  5294.2  360.04  5300.7  360.91  5390.0  364.15
#Mann=5,-1,0
  4533.3    0.05       0  4638.7     0.1       0  4935.6    0.07       0
  4939.6     0.1       0  5244.0    0.05       0
Bank Sta=4935.6,4939.6
Exp/Cntr=0.3,0.1

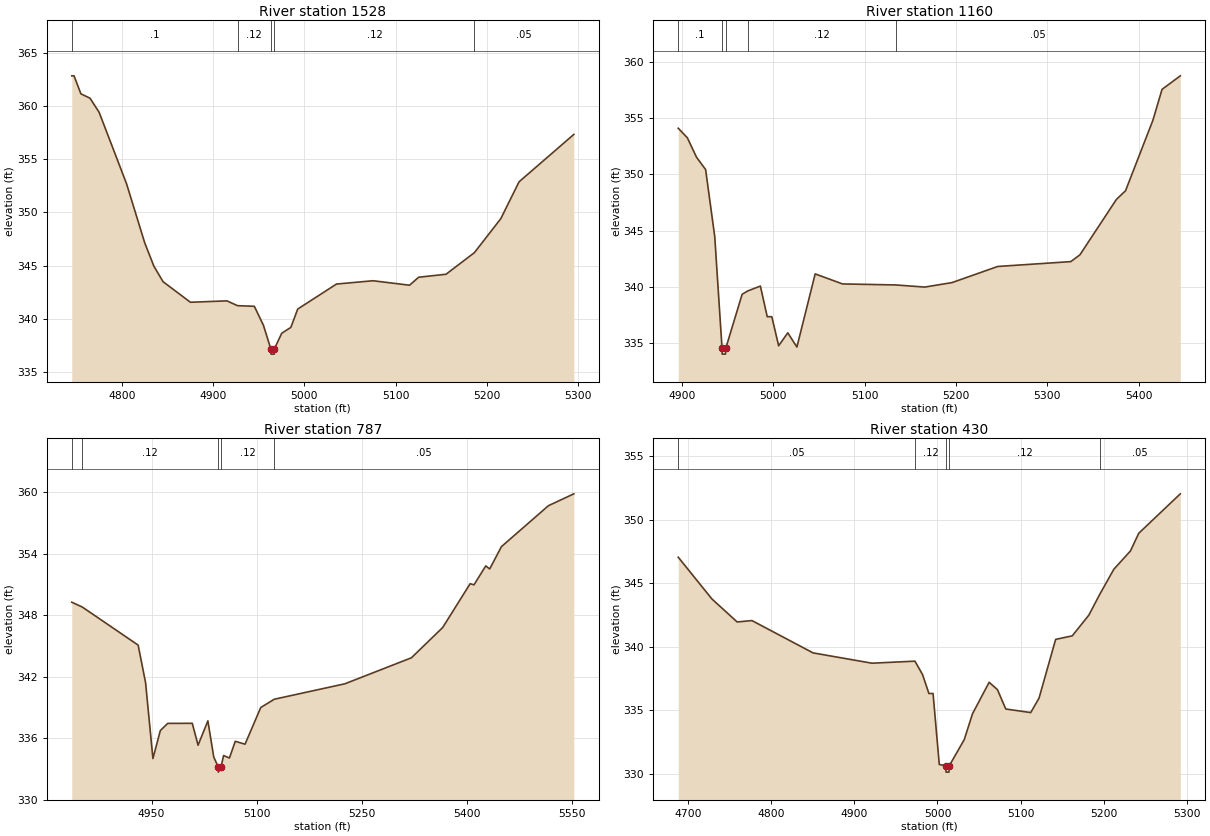
Type RM Length L Ch R = 1,1528,368,368,368
BEGIN DESCRIPTION:
Lynn Creek T7 4.0
END DESCRIPTION:
XS GIS Cut Line= 3
      2724426.00      6788160.98      2724426.00      6788411.00
      2724426.00      6788710.98
#Sta/Elev= 30
  4745.3  362.82  4747.8  362.82  4755.3  361.13  4765.3  360.72  4775.3  359.39
  4805.3  352.69  4825.3  347.12  4835.3  344.94  4845.3  343.49  4875.3  341.56
  4915.3  341.69  4926.9  341.24  4945.3  341.18  4955.3  339.39  4963.3  337.19
  4963.6  336.69  4967.1  336.69  4967.3  337.19  4975.3  338.65  4985.3  339.20
  4992.8  340.92  5035.3  343.27  5075.3  343.58  5115.3  343.16  5125.3  343.91
  5155.3  344.19  5186.4  346.22  5215.3  349.41  5235.3  352.87  5295.3  357.32
#Mann=5,-1,0
  4745.3     0.1       0  4926.9    0.12       0  4963.3    0.07       0
  4967.3    0.12       0  5186.4    0.05       0
Bank Sta=4963.3,4967.3
Exp/Cntr=0.3,0.1

Type RM Length L Ch R = 1,1160,373,373,373
BEGIN DESCRIPTION:
Lynn Creek T7 3.0
END DESCRIPTION:
XS GIS Cut Line= 3
      2724126.00      6788211.02      2724126.00      6788311.00
      2724126.00      6788761.02
#Sta/Elev= 30
  4895.8  354.10  4905.8  353.25  4915.8  351.53  4925.8  350.43  4935.8  344.48
  4943.8  334.55  4944.0  334.05  4947.5  334.05  4947.8  334.55  4965.8  339.36
  4972.0  339.66  4985.8  340.09  4993.3  337.37  4998.3  337.37  5005.8  334.79
  5015.8  335.94  5025.8  334.68  5045.8  341.17  5075.8  340.28  5134.0  340.19
  5165.8  340.00  5195.8  340.40  5245.8  341.83  5325.8  342.26  5335.8  342.86
  5375.8  347.78  5385.8  348.55  5415.8  354.81  5425.8  357.55  5445.8  358.75
#Mann=5,-1,0
  4895.8     0.1       0  4943.8    0.07       0  4947.8     0.1       0
  4972.0    0.12       0  5134.0    0.05       0
Bank Sta=4943.8,4947.8
Exp/Cntr=0.3,0.1

Type RM Length L Ch R = 1,787,357,357,357
BEGIN DESCRIPTION:
Lynn Creek T7 2.0
END DESCRIPTION:
XS GIS Cut Line= 3
      2723776.01      6788161.03      2723826.00      6788311.00
      2724076.00      6788811.00
#Sta/Elev= 30
  4836.0  349.28  4851.0  348.81  4930.8  345.09  4941.4  341.43  4951.9  334.01
  4962.5  336.74  4973.0  337.44  5008.1  337.45  5016.4  335.31  5030.4  337.69
  5038.8  334.15  5045.2  333.18  5045.4  332.68  5049.2  333.18  5052.8  334.30
  5061.2  334.06  5069.5  335.69  5083.5  335.41  5105.9  338.99  5125.2  339.80
  5226.1  341.31  5321.1  343.85  5365.8  346.81  5405.0  351.09  5410.5  350.98
  5427.3  352.83  5432.9  352.53  5449.7  354.71  5516.8  358.71  5553.1  359.87
#Mann=5,-1,0
  4836.0    0.05       0  4851.0    0.12       0  5045.2    0.07       0
  5049.2    0.12       0  5125.2    0.05       0
Bank Sta=5045.2,5049.2
Exp/Cntr=0.3,0.1

Type RM Length L Ch R = 1,430,0,0,0
BEGIN DESCRIPTION:
Lynn Creek T7 1.0
END DESCRIPTION:
XS GIS Cut Line= 3
      2723625.99      6788161.05      2723576.00      6788461.00
      2723576.00      6788761.01
#Sta/Elev= 30
  4688.1  347.04  4728.6  343.76  4759.0  341.95  4776.8  342.06  4850.3  339.52
  4921.2  338.71  4972.9  338.87  4982.1  337.81  4989.7  336.33  4994.7  336.33
  5002.2  330.75  5010.2  330.65  5010.4  330.15  5013.9  330.15  5014.2  330.65
  5032.2  332.70  5042.2  334.74  5062.2  337.21  5072.2  336.63  5082.2  335.11
  5112.2  334.83  5122.2  335.96  5142.2  340.58  5162.2  340.86  5182.2  342.49
  5195.0  344.09  5212.2  346.09  5232.2  347.53  5242.2  348.92  5292.2  352.02
#Mann=5,-1,0
  4688.1    0.05       0  4972.9    0.12       0  5010.2    0.07       0
  5014.2    0.12       0  5195.0    0.05       0
Bank Sta=5010.2,5014.2
Exp/Cntr=0.3,0.1

Chan Stop Cuts=-1