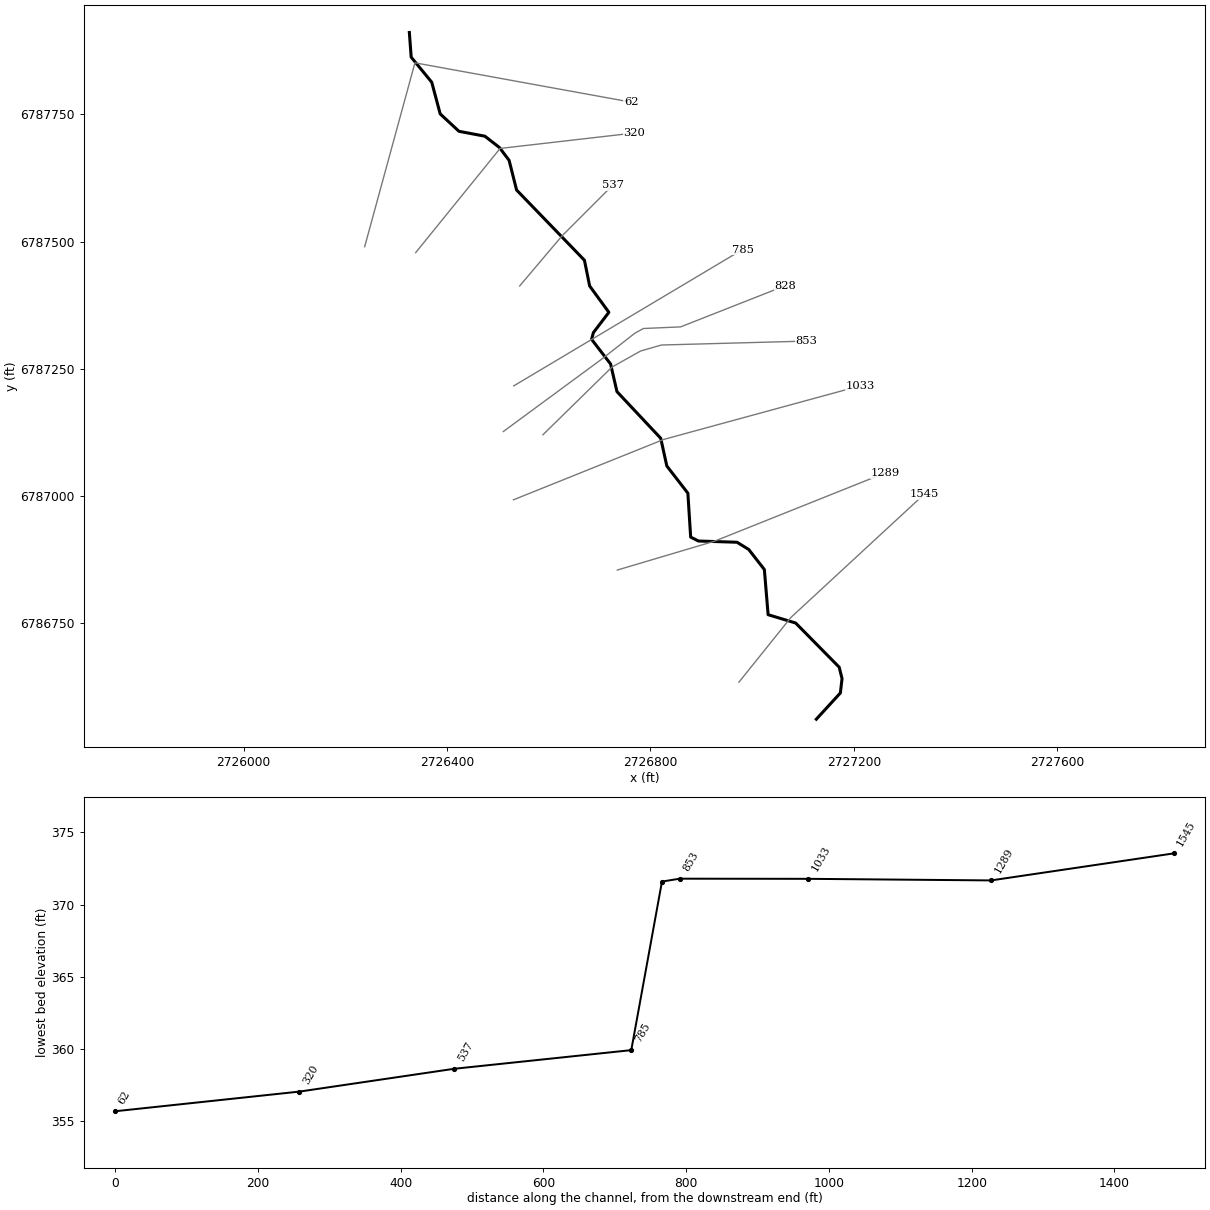
--- Lynn Creek T8.prj (project) ---

Proj Title=Lynn Creek T8 Base Level Engineering
Current Plan=p01
Default Exp/Contr=0.3,0.1
English Units
Geom File=g01
Flow File=f01
Plan File=p01
BEGIN DESCRIPTION:
Lynn Creek T8
END DESCRIPTION:

--- Lynn Creek T8.p01 (plan) ---

Plan Title=Multiple Run
Short Identifier=Multiple
Geom File=g01
Flow File=f01
Subcritical Flow
K Sum by GR= 0
Std Step Tol= 0.01
Critical Tol= 0.01
Num of Std Step Trials= 20
Max Error Tol= 0.3
Flow Tol Ratio= 0.001
Split Flow NTrial= 30
Split Flow Tol= 0.02
Split Flow Ratio= 0.02
Log Output Level= 0
Friction Slope Method= 1
Unsteady Friction Slope Method= 2
Unsteady Bridges Friction Slope Method= 1
Parabolic Critical Depth
Global Vel Dist=  1 , 1 , 1
Global Log Level= 0
CheckData=True
Encroach Param= -1, 0, 0, 0
BEGIN DESCRIPTION:
Multiple Run
END DESCRIPTION:

--- Lynn Creek T8.f01 (steady flow) ---

Flow Title=Multiple
Number of Profiles=7
Profile Names=10-year,25-year,50-year,1pct_min,100-year,1pct_plu,500-year
River Rch & RM= Lynn Creek T8,Reach-1,1545
     189     237     272     156     312     623     408
Boundary for River Rch & Prof#=Lynn Creek T8,Reach-1,1
Up Type=0
Dn Type=3
Dn Slope=0.005
Boundary for River Rch & Prof#=Lynn Creek T8,Reach-1,2
Up Type=0
Dn Type=3
Dn Slope=0.005
Boundary for River Rch & Prof#=Lynn Creek T8,Reach-1,3
Up Type=0
Dn Type=3
Dn Slope=0.005
Boundary for River Rch & Prof#=Lynn Creek T8,Reach-1,4
Up Type=0
Dn Type=3
Dn Slope=0.005
Boundary for River Rch & Prof#=Lynn Creek T8,Reach-1,5
Up Type=0
Dn Type=3
Dn Slope=0.005
Boundary for River Rch & Prof#=Lynn Creek T8,Reach-1,6
Up Type=0
Dn Type=3
Dn Slope=0.005
Boundary for River Rch & Prof#=Lynn Creek T8,Reach-1,7
Up Type=0
Dn Type=3
Dn Slope=0.005

--- Lynn Creek T8.g01 (geometry) ---

Geom Title=Existing Conditions

River Reach=Lynn Creek T8,Reach-1
Reach XY= 30
      2727126.00      6786561.00      2727173.33      6786612.62
      2727176.58      6786640.95      2727170.94      6786663.36
      2727085.40      6786750.11      2727031.26      6786766.48
      2727023.89      6786855.22      2726993.18      6786894.71
      2726970.21      6786908.89      2726894.42      6786911.31
      2726879.03      6786919.01      2726873.51      6787005.35
      2726832.14      6787058.82      2726820.16      6787113.29
      2726734.14      6787204.96      2726721.56      6787259.35
      2726684.24      6787307.77      2726687.81      6787321.04
      2726718.24      6787360.92      2726680.44      6787412.65
      2726670.19      6787463.29      2726536.79      6787601.34
      2726522.11      6787659.57      2726503.13      6787684.83
      2726474.54      6787707.10      2726423.49      6787716.76
      2726386.62      6787750.99      2726370.01      6787813.21
      2726329.60      6787862.49      2726326.00      6787911.00

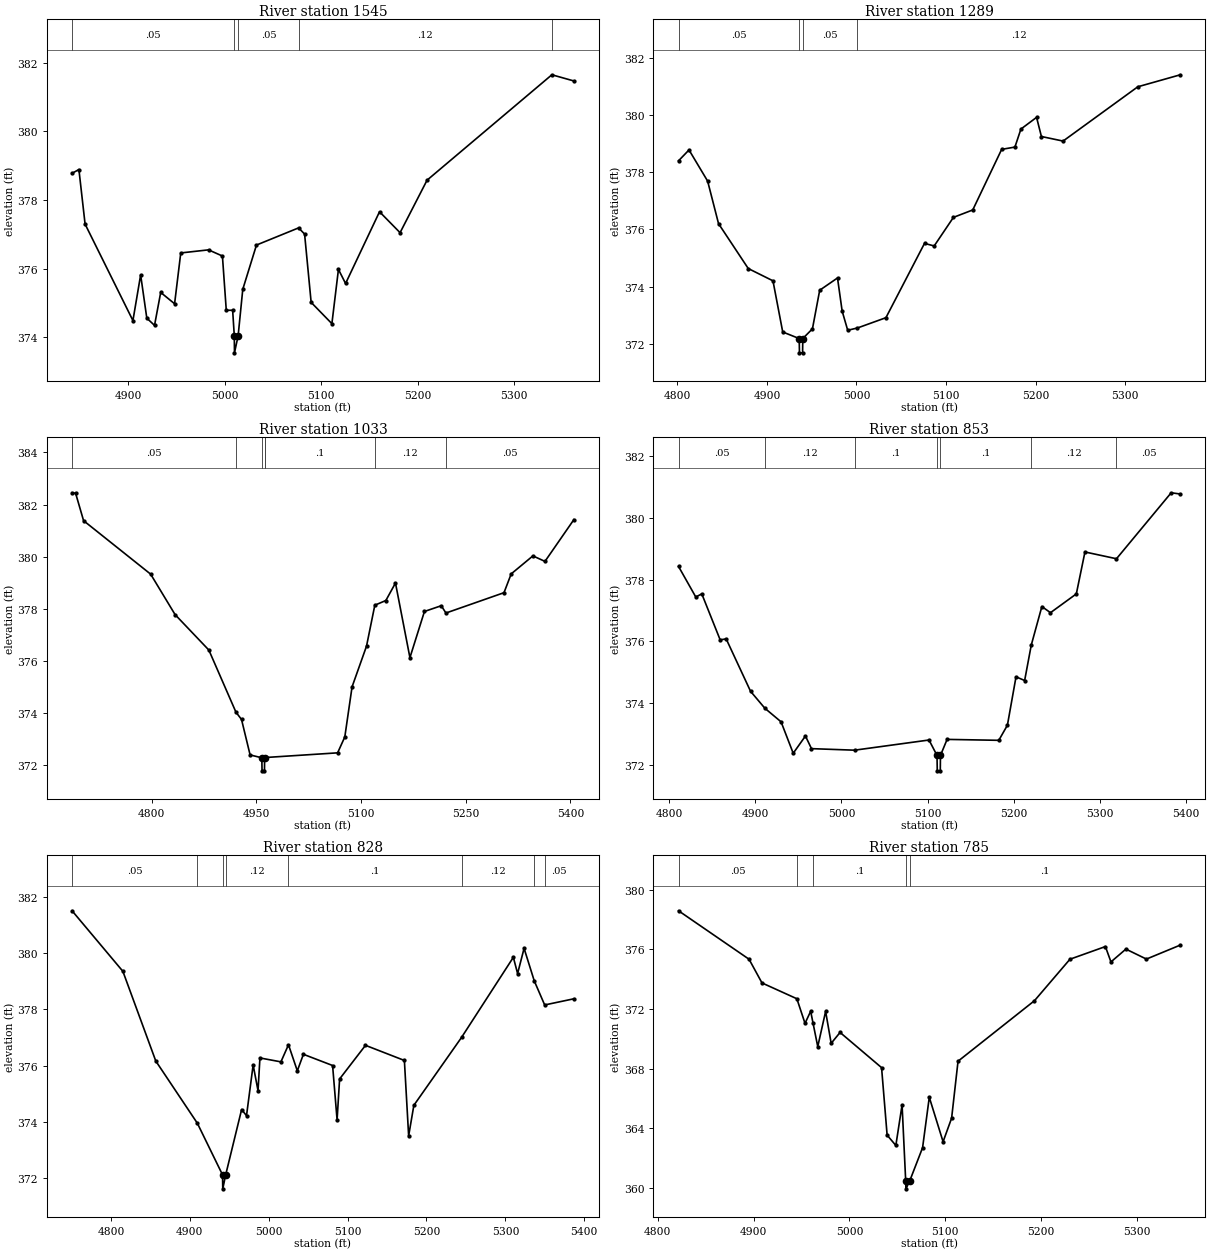
Type RM Length L Ch R = 1,1545,256,256,256
BEGIN DESCRIPTION:
Lynn Creek T8 6.0
END DESCRIPTION:
XS GIS Cut Line= 3
      2726973.89      6786633.81      2727076.00      6786761.00
      2727338.31      6787003.44
#Sta/Elev= 30
  4841.8  378.78  4848.9  378.89  4855.3  377.30  4904.9  374.49  4912.9  375.82
  4919.3  374.56  4927.3  374.35  4933.7  375.31  4948.1  374.98  4954.5  376.46
  4983.3  376.55  4997.7  376.37  5001.7  374.79  5008.3  374.79  5010.0  374.05
  5010.2  373.55  5014.0  374.05  5018.8  375.40  5033.0  376.69  5076.7  377.19
  5082.9  377.01  5089.7  375.02  5111.2  374.40  5118.0  375.98  5125.4  375.57
  5160.6  377.66  5181.9  377.05  5209.9  378.58  5339.3  381.65  5362.1  381.47
#Mann=5,-1,0
  4841.8    0.05       0  5010.0    0.05       0  5014.0    0.05       0
  5076.7    0.12       0  5339.3    0.05       0
Bank Sta=5010,5014
Exp/Cntr=0.3,0.1

Type RM Length L Ch R = 1,1289,256,256,256
BEGIN DESCRIPTION:
Lynn Creek T8 5.0
END DESCRIPTION:
XS GIS Cut Line= 3
      2726734.82      6786854.25      2726926.00      6786911.00
      2727261.35      6787045.14
#Sta/Elev= 30
  4801.2  378.40  4812.9  378.78  4833.7  377.69  4845.9  376.20  4879.1  374.63
  4906.7  374.20  4917.6  372.41  4936.0  372.18  4936.3  371.68  4939.8  371.68
  4940.0  372.18  4950.8  372.52  4958.9  373.87  4978.8  374.30  4984.0  373.14
  4990.2  372.47  5001.1  372.55  5032.9  372.91  5076.0  375.51  5086.8  375.42
  5108.3  376.42  5129.9  376.68  5162.2  378.80  5177.0  378.88  5183.7  379.51
  5201.2  379.92  5206.6  379.25  5230.8  379.09  5314.3  380.99  5361.8  381.41
#Mann=4,-1,0
  4801.2    0.05       0  4936.0    0.05       0  4940.0    0.05       0
  5001.1    0.12       0
Bank Sta=4936,4940
Exp/Cntr=0.3,0.1

Type RM Length L Ch R = 1,1033,180,180,180
BEGIN DESCRIPTION:
Lynn Creek T8 4.0
END DESCRIPTION:
XS GIS Cut Line= 3
      2726530.66      6786992.33      2726826.00      6787111.00
      2727212.60      6787216.43
#Sta/Elev= 30
  4686.0  382.45  4691.1  382.43  4702.5  381.38  4798.6  379.33  4833.6  377.78
  4882.0  376.42  4920.8  374.04  4928.8  373.76  4941.1  372.40  4957.9  372.29
  4958.2  371.79  4961.7  371.79  4961.9  372.29  4962.5  372.30  5066.5  372.48
  5076.8  373.09  5087.2  375.01  5107.9  376.57  5119.8  378.14  5135.6  378.32
  5149.4  378.99  5170.1  376.13  5190.9  377.90  5215.0  378.12  5221.7  377.84
  5304.9  378.62  5315.2  379.34  5346.3  380.03  5363.6  379.82  5405.0  381.42
#Mann=7,-1,0
  4686.0    0.05       0  4920.8    0.12       0  4957.9    0.07       0
  4961.9    0.12       0  4962.5     0.1       0  5119.8    0.12       0
  5221.7    0.05       0
Bank Sta=4957.9,4961.9
Exp/Cntr=0.3,0.1

Type RM Length L Ch R = 1,853,25,25,25
BEGIN DESCRIPTION:
Mapping XS 35f03eaa
END DESCRIPTION:
XS GIS Cut Line= 5
      2726588.58      6787120.18      2726724.33      6787253.23
      2726780.62      6787284.85      2726821.73      6787296.63
      2727106.62      6787304.37
#Sta/Elev= 30
  4810.9  378.43  4830.9  377.44  4837.9  377.54  4859.2  376.05  4866.2  376.08
  4894.5  374.38  4911.1  373.83  4929.9  373.39  4944.0  372.37  4958.2  372.93
  4965.2  372.52  5015.2  372.47  5101.6  372.80  5110.9  372.30  5111.2  371.80
  5114.7  371.80  5114.9  372.30  5122.6  372.82  5182.6  372.79  5192.6  373.28
  5202.6  374.85  5212.6  374.73  5220.3  375.88  5232.6  377.13  5242.6  376.93
  5272.6  377.54  5282.6  378.90  5319.2  378.68  5382.7  380.82  5393.3  380.78
#Mann=7,-1,0
  4810.9    0.05       0  4911.1    0.12       0  5015.2     0.1       0
  5110.9    0.07       0  5114.9     0.1       0  5220.3    0.12       0
  5319.2    0.05       0
Bank Sta=5110.9,5114.9
Exp/Cntr=0.3,0.1

Type RM Length L Ch R = 1,828,43,43,43
BEGIN DESCRIPTION:
Lynn Creek T8 3.0
END DESCRIPTION:
XS GIS Cut Line= 6
      2726510.78      6787126.57      2726704.14      6787268.86
      2726769.52      6787320.04      2726786.23      6787329.09
      2726859.23      6787332.25      2727064.72      6787413.13
#Sta/Elev= 30
  4750.8  381.52  4815.2  379.36  4856.9  376.16  4909.6  373.94  4941.5  372.10
  4941.8  371.60  4945.5  372.10  4965.7  374.43  4971.9  374.21  4980.3  376.02
  4986.5  375.10  4988.9  376.27  5015.5  376.13  5025.1  376.74  5036.3  375.81
  5044.0  376.40  5081.0  376.00  5086.7  374.06  5089.9  375.52  5122.7  376.72
  5172.0  376.18  5177.4  373.49  5184.0  374.58  5244.4  377.00  5310.1  379.86
  5315.5  379.28  5323.7  380.18  5336.6  379.02  5349.8  378.16  5386.8  378.38
#Mann=8,-1,0
  4750.8    0.05       0  4909.6    0.12       0  4941.5    0.07       0
  4945.5    0.12       0  5025.1     0.1       0  5244.4    0.12       0
  5336.6     0.1       0  5349.8    0.05       0
Bank Sta=4941.5,4945.5
Exp/Cntr=0.3,0.1

Type RM Length L Ch R = 1,785,248,248,248
BEGIN DESCRIPTION:
Mapping XS 115519b1
END DESCRIPTION:
XS GIS Cut Line= 2
      2726531.17      6787216.26      2726981.04      6787484.36
#Sta/Elev= 30
  4821.7  378.58  4895.3  375.33  4908.8  373.74  4945.2  372.68  4953.7  371.03
  4959.6  371.84  4962.0  371.07  4967.0  369.47  4975.2  371.83  4981.0  369.69
  4990.3  370.42  5033.6  368.06  5039.4  363.53  5048.5  362.84  5055.0  365.56
  5058.8  360.43  5059.0  359.93  5062.8  360.43  5076.4  362.69  5083.4  366.07
  5097.8  363.09  5106.7  364.67  5113.4  368.49  5193.2  372.55  5230.2  375.33
  5267.2  376.18  5273.0  375.15  5288.6  376.01  5310.0  375.34  5345.4  376.28
#Mann=5,-1,0
  4821.7    0.05       0  4945.2    0.12       0  4962.0     0.1       0
  5058.8    0.07       0  5062.8     0.1       0
Bank Sta=5058.8,5062.8
Exp/Cntr=0.3,0.1

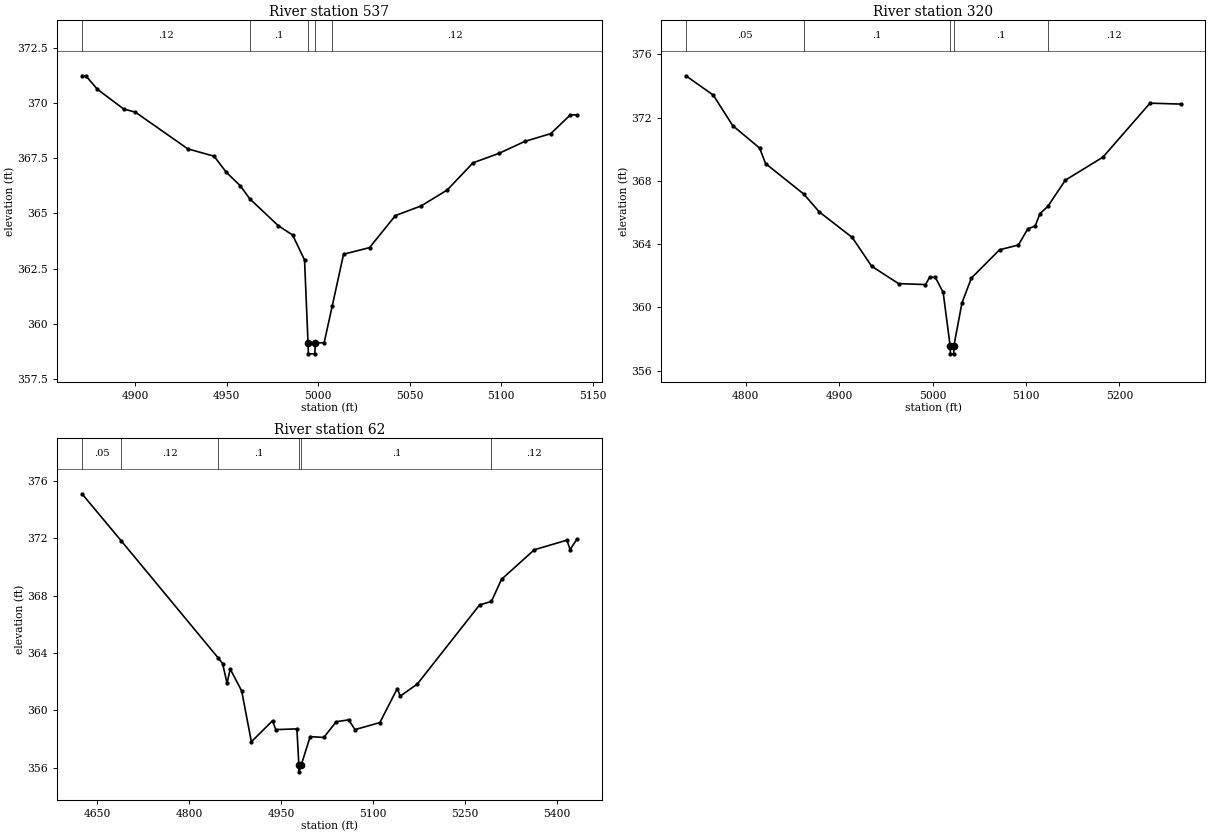
Type RM Length L Ch R = 1,537,217,217,217
BEGIN DESCRIPTION:
Lynn Creek T8 2.0
END DESCRIPTION:
XS GIS Cut Line= 3
      2726542.89      6787412.77      2726626.00      6787511.00
      2726726.01      6787611.01
#Sta/Elev= 30
  4871.1  371.23  4873.2  371.23  4879.5  370.62  4893.8  369.73  4900.3  369.58
  4928.9  367.92  4943.2  367.59  4949.8  366.87  4957.5  366.25  4962.8  365.65
  4978.3  364.44  4986.1  364.02  4992.6  362.89  4994.5  359.14  4994.7  358.64
  4998.2  358.64  4998.5  359.14  5003.3  359.14  5007.7  360.80  5013.9  363.15
  5028.1  363.45  5042.2  364.90  5056.3  365.34  5070.5  366.06  5084.6  367.29
  5098.8  367.72  5112.9  368.26  5127.0  368.61  5137.7  369.46  5141.2  369.46
#Mann=5,-1,0
  4871.1    0.12       0  4962.8     0.1       0  4994.5    0.07       0
  4998.5     0.1       0  5007.7    0.12       0
Bank Sta=4994.5,4998.5
Exp/Cntr=0.3,0.1

Type RM Length L Ch R = 1,320,258,258,258
BEGIN DESCRIPTION:
Mapping XS e45a329c
END DESCRIPTION:
XS GIS Cut Line= 3
      2726338.44      6787478.27      2726504.37      6787683.05
      2726768.56      6787713.47
#Sta/Elev= 30
  4736.0  374.64  4765.3  373.42  4786.1  371.49  4814.9  370.07  4821.3  369.09
  4862.2  367.16  4878.8  366.03  4914.0  364.42  4934.8  362.60  4963.6  361.50
  4992.4  361.44  4996.9  361.90  5002.9  361.90  5011.3  360.95  5018.8  357.56
  5019.1  357.06  5022.6  357.06  5022.8  357.56  5031.4  360.27  5041.5  361.85
  5071.7  363.64  5091.8  363.94  5101.9  364.96  5109.8  365.14  5114.9  365.92
  5123.3  366.38  5142.1  368.04  5182.4  369.50  5232.7  372.91  5265.5  372.85
#Mann=5,-1,0
  4736.0    0.05       0  4862.2     0.1       0  5018.8    0.07       0
  5022.8     0.1       0  5123.3    0.12       0
Bank Sta=5018.8,5022.8
Exp/Cntr=0.3,0.1

Type RM Length L Ch R = 1,62,0,0,0
BEGIN DESCRIPTION:
Lynn Creek T8 1.0
END DESCRIPTION:
XS GIS Cut Line= 3
      2726238.12      6787489.77      2726336.98      6787851.40
      2726761.80      6787774.10
#Sta/Elev= 30
  4625.1  375.12  4688.8  371.85  4846.7  363.68  4854.4  363.26  4861.6  361.89
  4866.8  362.88  4885.5  361.35  4901.3  357.80  4935.8  359.27  4941.0  358.65
  4975.5  358.70  4978.7  356.20  4978.9  355.70  4982.7  356.20  4997.2  358.16
  5019.3  358.10  5039.7  359.20  5060.0  359.33  5070.2  358.65  5110.8  359.14
  5139.1  361.51  5144.1  360.99  5171.8  361.83  5273.4  367.36  5292.6  367.60
  5309.2  369.15  5362.6  371.21  5415.7  371.88  5421.0  371.22  5431.8  371.94
#Mann=6,-1,0
  4625.1    0.05       0  4688.8    0.12       0  4846.7     0.1       0
  4978.7    0.07       0  4982.7     0.1       0  5292.6    0.12       0
Bank Sta=4978.7,4982.7
Exp/Cntr=0.3,0.1

Chan Stop Cuts=-1