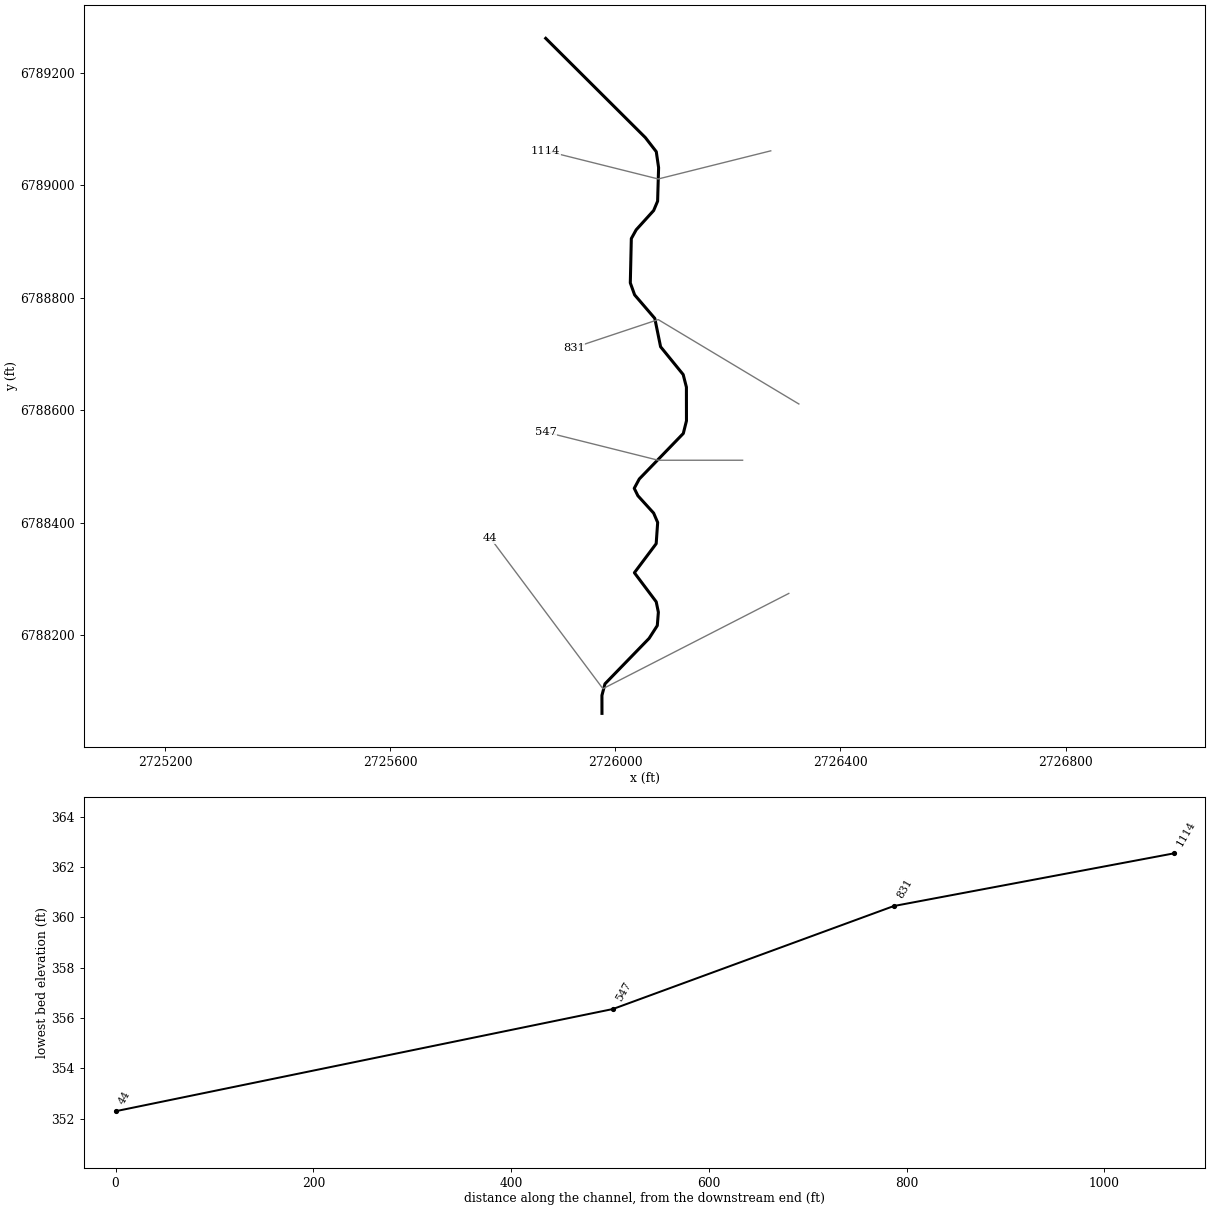
--- Lynn Creek T9.prj (project) ---

Proj Title=Lynn Creek T9 Base Level Engineering
Current Plan=p01
Default Exp/Contr=0.3,0.1
English Units
Geom File=g01
Flow File=f01
Plan File=p01
BEGIN DESCRIPTION:
Lynn Creek T9
END DESCRIPTION:

--- Lynn Creek T9.p01 (plan) ---

Plan Title=Multiple Run
Short Identifier=Multiple
Geom File=g01
Flow File=f01
Subcritical Flow
K Sum by GR= 0
Std Step Tol= 0.01
Critical Tol= 0.01
Num of Std Step Trials= 20
Max Error Tol= 0.3
Flow Tol Ratio= 0.001
Split Flow NTrial= 30
Split Flow Tol= 0.02
Split Flow Ratio= 0.02
Log Output Level= 0
Friction Slope Method= 1
Unsteady Friction Slope Method= 2
Unsteady Bridges Friction Slope Method= 1
Parabolic Critical Depth
Global Vel Dist=  1 , 1 , 1
Global Log Level= 0
CheckData=True
Encroach Param= -1, 0, 0, 0
BEGIN DESCRIPTION:
Multiple Run
END DESCRIPTION:

--- Lynn Creek T9.f01 (steady flow) ---

Flow Title=Multiple
Number of Profiles=7
Profile Names=10-year,25-year,50-year,1pct_min,100-year,1pct_plu,500-year
River Rch & RM= Lynn Creek T9,Reach-1,1114
     153     186     211     119     238     475     301
Boundary for River Rch & Prof#=Lynn Creek T9,Reach-1,1
Up Type=0
Dn Type=3
Dn Slope=0.005
Boundary for River Rch & Prof#=Lynn Creek T9,Reach-1,2
Up Type=0
Dn Type=3
Dn Slope=0.005
Boundary for River Rch & Prof#=Lynn Creek T9,Reach-1,3
Up Type=0
Dn Type=3
Dn Slope=0.005
Boundary for River Rch & Prof#=Lynn Creek T9,Reach-1,4
Up Type=0
Dn Type=3
Dn Slope=0.005
Boundary for River Rch & Prof#=Lynn Creek T9,Reach-1,5
Up Type=0
Dn Type=3
Dn Slope=0.005
Boundary for River Rch & Prof#=Lynn Creek T9,Reach-1,6
Up Type=0
Dn Type=3
Dn Slope=0.005
Boundary for River Rch & Prof#=Lynn Creek T9,Reach-1,7
Up Type=0
Dn Type=3
Dn Slope=0.005

--- Lynn Creek T9.g01 (geometry) ---

Geom Title=Existing Conditions

River Reach=Lynn Creek T9,Reach-1
Reach XY= 30
      2725876.00      6789261.00      2726053.16      6789084.52
      2726072.54      6789059.50      2726076.67      6789031.08
      2726074.90      6788971.55      2726067.91      6788954.96
      2726036.82      6788920.63      2726028.17      6788905.03
      2726026.37      6788826.27      2726034.04      6788804.95
      2726069.88      6788763.18      2726080.19      6788712.73
      2726120.36      6788663.32      2726126.11      6788640.90
      2726126.20      6788581.05      2726120.57      6788558.57
      2726042.34      6788477.69      2726033.36      6788461.08
      2726039.90      6788447.81      2726067.84      6788417.05
      2726075.01      6788400.36      2726072.36      6788362.65
      2726033.62      6788311.00      2726072.43      6788259.35
      2726076.25      6788240.84      2726074.35      6788217.05
      2726059.77      6788194.33      2725981.33      6788113.51
      2725975.93      6788092.88      2725976.00      6788061.00

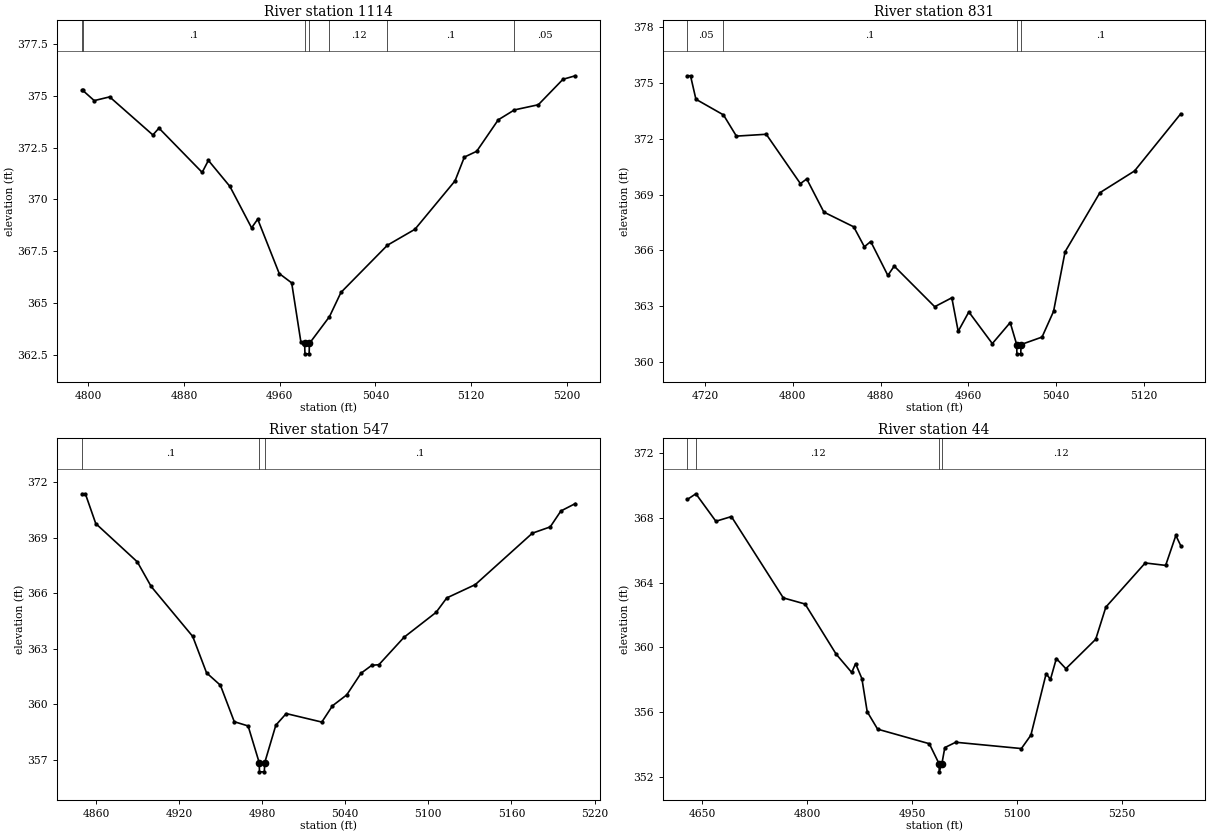
Type RM Length L Ch R = 1,1114,283,283,283
BEGIN DESCRIPTION:
Lynn Creek T9 4.0
END DESCRIPTION:
XS GIS Cut Line= 3
      2726276.02      6789061.00      2726076.00      6789011.00
      2725876.03      6789060.99
#Sta/Elev= 30
  4794.7  375.27  4795.5  375.27  4805.0  374.78  4817.9  374.96  4854.0  373.12
  4859.1  373.45  4895.2  371.31  4900.4  371.89  4918.4  370.63  4936.5  368.63
  4941.6  369.05  4959.6  366.42  4970.0  365.97  4977.7  363.11  4980.8  363.04
  4981.1  362.54  4984.6  362.54  4984.8  363.04  5001.6  364.34  5011.2  365.51
  5050.0  367.79  5073.0  368.56  5106.5  370.90  5114.3  372.05  5124.6  372.33
  5142.6  373.85  5156.1  374.33  5176.1  374.58  5196.7  375.81  5207.0  375.98
#Mann=7,-1,0
  4794.7    0.05       0  4795.5     0.1       0  4980.8    0.07       0
  4984.8     0.1       0  5001.6    0.12       0  5050.0     0.1       0
  5156.1    0.05       0
Bank Sta=4980.8,4984.8
Exp/Cntr=0.3,0.1

Type RM Length L Ch R = 1,831,284,284,284
BEGIN DESCRIPTION:
Lynn Creek T9 3.0
END DESCRIPTION:
XS GIS Cut Line= 3
      2726325.99      6788611.01      2726076.00      6788761.00
      2725926.04      6788711.01
#Sta/Elev= 30
  4703.9  375.38  4706.8  375.38  4711.7  374.12  4736.8  373.28  4748.6  372.14
  4775.8  372.24  4806.9  369.59  4812.7  369.84  4828.3  368.06  4855.5  367.27
  4865.2  366.20  4871.0  366.48  4886.6  364.66  4892.4  365.16  4929.3  362.98
  4944.9  363.46  4950.7  361.66  4960.4  362.70  4981.8  361.00  4998.1  362.13
  5004.0  360.95  5004.2  360.45  5007.7  360.45  5008.0  360.95  5027.1  361.35
  5037.6  362.73  5048.1  365.93  5079.8  369.10  5111.4  370.27  5153.5  373.34
#Mann=4,-1,0
  4703.9    0.05       0  4736.8     0.1       0  5004.0    0.07       0
  5008.0     0.1       0
Bank Sta=5004,5008
Exp/Cntr=0.3,0.1

Type RM Length L Ch R = 1,547,503,503,503
BEGIN DESCRIPTION:
Lynn Creek T9 2.0
END DESCRIPTION:
XS GIS Cut Line= 3
      2726226.00      6788511.00      2726076.00      6788511.00
      2725875.96      6788561.01
#Sta/Elev= 30
  4849.9  371.39  4852.4  371.39  4859.9  369.78  4889.9  367.71  4899.9  366.38
  4929.9  363.68  4939.9  361.71  4949.9  361.04  4959.9  359.07  4969.9  358.84
  4977.9  356.86  4978.1  356.36  4981.6  356.36  4981.9  356.86  4989.9  358.88
  4997.4  359.51  5023.1  359.05  5030.8  359.93  5041.1  360.52  5051.4  361.69
  5059.2  362.12  5064.3  362.15  5082.4  363.63  5105.6  364.98  5113.3  365.76
  5133.9  366.48  5175.1  369.26  5188.0  369.60  5195.7  370.46  5206.1  370.86
#Mann=3,-1,0
  4849.9     0.1       0  4977.9    0.07       0  4981.9     0.1       0
Bank Sta=4977.9,4981.9
Exp/Cntr=0.3,0.1

Type RM Length L Ch R = 1,44,0,0,0
BEGIN DESCRIPTION:
Lynn Creek T9 1.0
END DESCRIPTION:
XS GIS Cut Line= 3
      2726308.12      6788274.21      2725977.69      6788104.85
      2725777.58      6788372.64
#Sta/Elev= 30
  4628.7  369.15  4640.9  369.50  4669.5  367.80  4691.7  368.09  4765.9  363.06
  4797.1  362.68  4841.5  359.58  4863.7  358.45  4869.3  358.99  4878.3  358.07
  4885.9  356.02  4900.8  354.94  4974.7  354.04  4988.7  352.80  4988.9  352.30
  4992.7  352.80  4996.9  353.80  5012.5  354.13  5106.4  353.74  5120.0  354.57
  5141.8  358.37  5148.0  358.02  5156.4  359.31  5170.0  358.68  5212.7  360.50
  5227.2  362.49  5283.5  365.22  5312.7  365.07  5327.3  366.92  5334.3  366.29
#Mann=4,-1,0
  4628.7     0.1       0  4640.9    0.12       0  4988.7    0.07       0
  4992.7    0.12       0
Bank Sta=4988.7,4992.7
Exp/Cntr=0.3,0.1

Chan Stop Cuts=-1