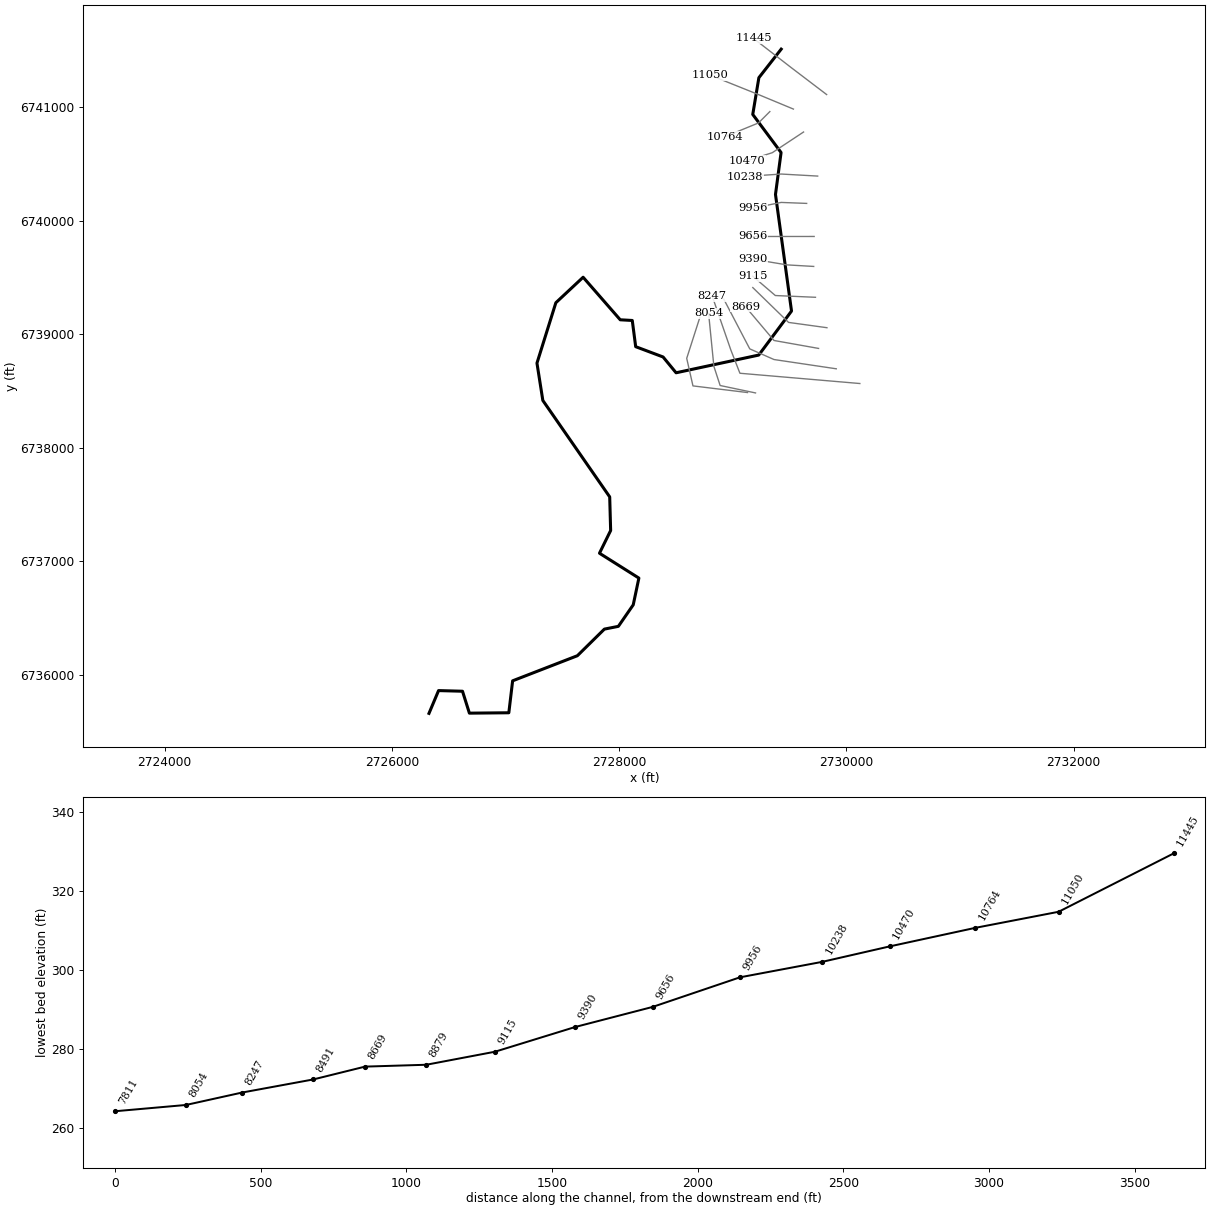
--- McAllister Slough.prj (project) ---

Proj Title=McAllister Slough Base Level Engineering
Current Plan=p01
Default Exp/Contr=0.3,0.1
English Units
Geom File=g01
Flow File=f01
Plan File=p01
Y Axis Title=Elevation
X Axis Title(PF)=Main Channel Distance
X Axis Title(XS)=Station
BEGIN DESCRIPTION:
McAllister Slough
END DESCRIPTION:
DSS Export Rating Curves= 0
DSS Export Rating Curve Sorted= 0
DSS Export Volume Flow Curves= 0
DXF OffsetX= 0
DXF OffsetY= 0
DXF ScaleX= 1
DXF ScaleY= 10

--- McAllister Slough.p01 (plan) ---

Plan Title=Multiple Run
Program Version=4.10
Short Identifier=Multiple
Geom File=g01
Flow File=f01
Subcritical Flow
K Sum by GR= 0
Std Step Tol= 0.01
Critical Tol= 0.01
Num of Std Step Trials= 20
Max Error Tol= 0.3
Flow Tol Ratio= 0.001
Split Flow NTrial= 30
Split Flow Tol= 0.02
Split Flow Ratio= 0.02
Log Output Level= 0
Friction Slope Method= 1
Unsteady Friction Slope Method= 2
Unsteady Bridges Friction Slope Method= 1
Parabolic Critical Depth
Global Vel Dist= 1 , 1 , 1
Global Log Level= 0
CheckData=True
Encroach Param=-1 ,0,0, 0
BEGIN DESCRIPTION:
Multiple Run
END DESCRIPTION:
Computation Interval=1HOUR
Output Interval=1HOUR
Run HTab= 0
Run UNet= 0
Run PostProcess= 0
Run WQNet= 0
UNET Theta= 1
UNET Theta Warmup= 1
UNET ZTol= 0.02
UNET ZSATol= 0.05
UNET MxIter= 20
UNET MaxInSteps= 0
UNET DtIC= 0
UNET DtMin= 0
UNET MaxCRTS= 20
UNET WFStab= 2
UNET SFStab= 1
UNET WFX= 1
UNET SFX= 1
UNET DSS MLevel= 4
UNET DZMax Abort= 100
UNET Convert EG Bridges= 0
UNET Use Existing IB Tables=-1
UNET Froude Reduction=False
UNET Froude Limit= 1
UNET Froude Power= 10
UNET Time Slicing=0,0, 5
UNET Junction Losses=0
Instantaneous Interval=1HOUR
Write IC File= 0
Write IC File at Sim End=0
Echo Input=False
Echo Parameters=False
Echo Output=False
Write Detailed= 0
WQ AD Non Conservative
WQ ULTIMATE=-1
WQ Max Comp Step=1HOUR
WQ Output Interval=15MIN
WQ Output Selected Increments= 0
WQ Output face flow=0
WQ Output face velocity=0
WQ Output face area=0
WQ Output face dispersion=0
WQ Output cell volume=0
WQ Output cell surface area=0
WQ Output cell continuity=0
WQ Output cumulative cell continuity=0
WQ Output face conc=0
WQ Output face dconc_dx=0
WQ Output face courant=0
WQ Output face peclet=0
WQ Output face adv mass=0
WQ Output face disp mass=0
WQ Output cell mass=0
WQ Output cell source sink temp=0
WQ Output cell source sink nsm=0
WQ Output MaxMinRange=-1
WQ Daily Max Min Mean=-1
WQ Daily Range=0
WQ Daily Time=0
WQ Create Restart=0
WQ Fixed Restart=0
WQ System Summary=0
WQ Use Fixed Temperature=0
Sorting and Armoring Iterations= 10
XS Update Threshold= 0.02
Hydraulics Update Threshold= 0.02
Energy Slope Method= 1
Volume Change Method= 0
XS Weighting Method= 0
Number of US Weighted Cross Sections= 1
Number of DS Weighted Cross Sections= 1
Upstream XS Weight=0.25
Main XS Weight=0.5
Downstream XS Weight=0.25
Number of DS XS's Weighted with US Boundary= 1
Upstream Boundary Weight= 1
Weight of XSs Associated with US Boundary= 0
Number of US XS's Weighted with DS Boundary= 1
Downstream Boundary Weight= 0.5
Weight of XSs Associated with DS Boundary= 0.5
Sediment Output Level= 4
Mass or Volume Output= 0
Output Increment Type= 1
Profile and TS Output Increment= 10
XS Output Flag= 0
XS Output Increment= 10
Disregard all LS=0
Disregard all Conn=0
Disregard all Breaches=0
Disregard all Pumps=0

--- McAllister Slough.f01 (steady flow) ---

Flow Title=Multiple
Program Version=4.10
Number of Profiles= 7
Profile Names=10-year,25-year,50-year,1pct_min,100-year,1pct_plu,500-year
River Rch & RM=McAllister Sloug,Reach-1         ,11445
     208     264     306     177     354     706     472
Boundary for River Rch & Prof#=McAllister Sloug,Reach-1         , 1
Up Type= 0
Dn Type= 3
Dn Slope=0.007
Boundary for River Rch & Prof#=McAllister Sloug,Reach-1         , 2
Up Type= 0
Dn Type= 3
Dn Slope=0.007
Boundary for River Rch & Prof#=McAllister Sloug,Reach-1         , 3
Up Type= 0
Dn Type= 3
Dn Slope=0.007
Boundary for River Rch & Prof#=McAllister Sloug,Reach-1         , 4
Up Type= 0
Dn Type= 3
Dn Slope=0.007
Boundary for River Rch & Prof#=McAllister Sloug,Reach-1         , 5
Up Type= 0
Dn Type= 3
Dn Slope=0.007
Boundary for River Rch & Prof#=McAllister Sloug,Reach-1         , 6
Up Type= 0
Dn Type= 3
Dn Slope=0.007
Boundary for River Rch & Prof#=McAllister Sloug,Reach-1         , 7
Up Type= 0
Dn Type= 3
Dn Slope=0.007
DSS Import GetInterval= 0
DSS Import GetPeak= 0
DSS Import FillOption= 0

--- McAllister Slough.g01 (geometry) ---

Geom Title=Existing Conditions

River Reach=McAllister Sloug,Reach-1
Reach XY= 30
      2729426.00      6741511.00      2729229.54      6741259.53
      2729175.68      6740935.89      2729424.95      6740600.57
      2729375.72      6740231.18      2729516.85      6739204.27
      2729228.55      6738816.73      2728500.79      6738660.67
      2728386.32      6738799.89      2728145.27      6738890.53
      2728115.25      6739121.39      2728009.30      6739127.38
      2727682.67      6739502.05      2727442.63      6739277.67
      2727276.37      6738745.73      2727328.07      6738416.86
      2727916.58      6737567.62      2727924.91      6737271.54
      2727826.53      6737071.47      2728173.37      6736852.52
      2728123.75      6736616.93      2727992.79      6736427.44
      2727869.83      6736403.14      2727632.17      6736168.86
      2727062.20      6735947.74      2727028.74      6735666.34
      2726681.65      6735662.97      2726620.99      6735856.00
      2726410.31      6735861.69      2726326.00      6735661.00

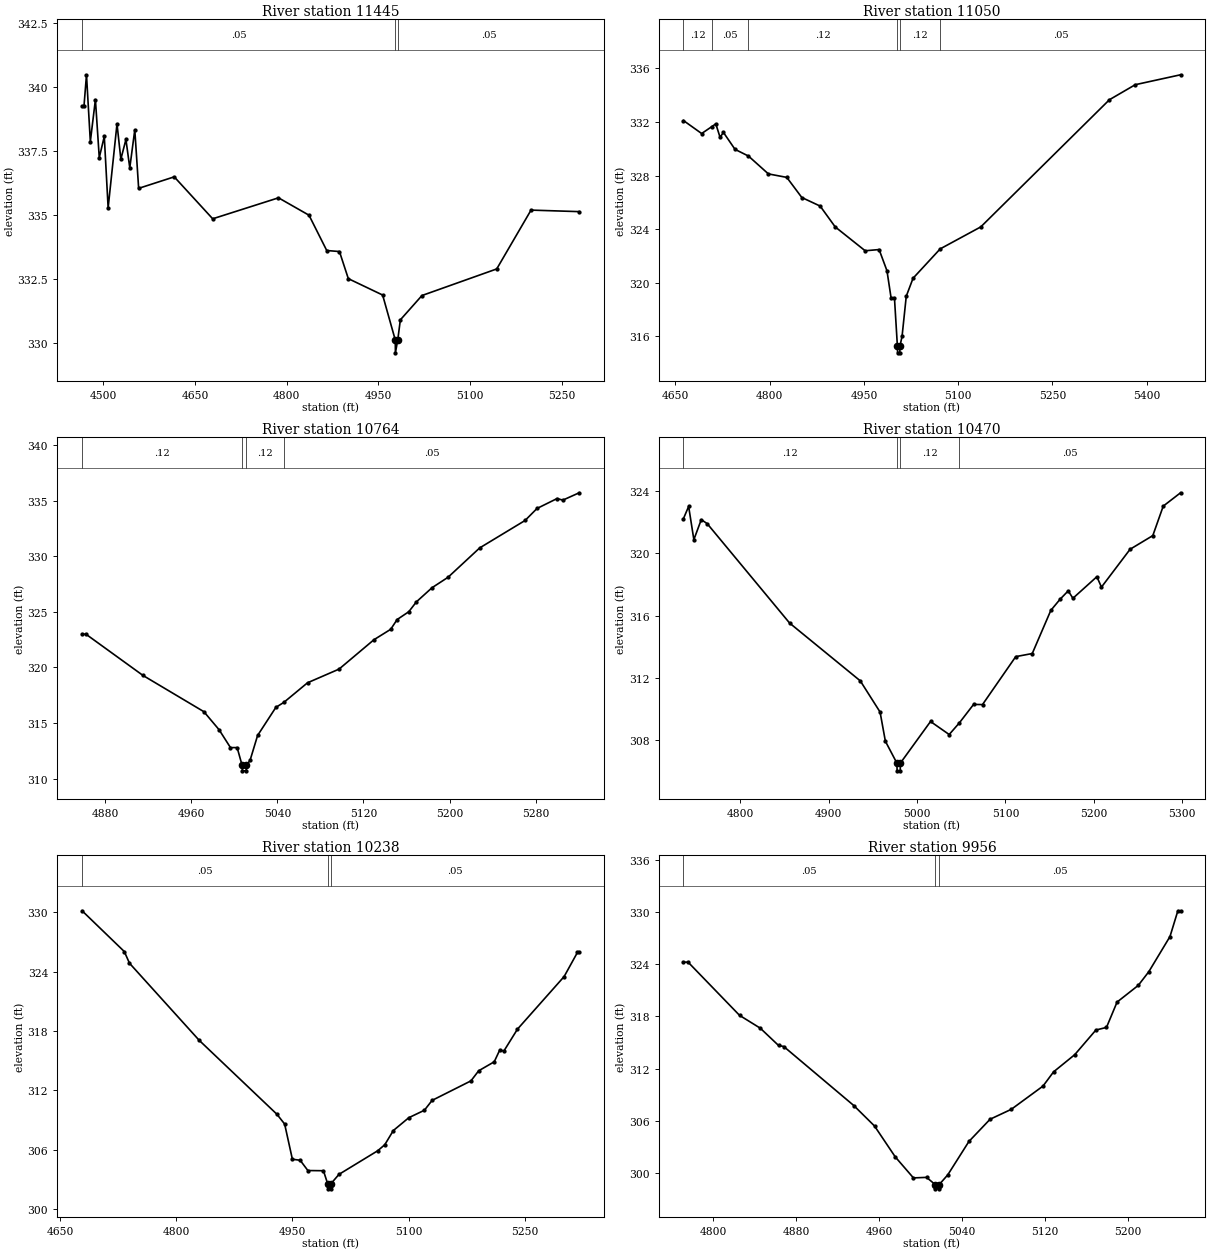
Type RM Length L Ch R = 1,11445,395,395,395
BEGIN DESCRIPTION:
McAllister Slough 16.0
END DESCRIPTION:
XS GIS Cut Line= 3
      2729825.97      6741111.02      2729516.55      6741346.50
      2729181.15      6741606.16
#Sta/Elev= 30
  4465.3  339.24  4468.4  339.24  4472.5  340.47  4478.8  337.86  4487.1  339.50
  4493.4  337.23  4501.6  338.06  4507.9  335.27  4522.4  338.55  4528.7  337.17
  4537.0  337.94  4543.3  336.83  4551.5  338.32  4557.8  336.03  4616.0  336.48
  4678.9  334.84  4786.5  335.66  4836.4  334.98  4865.4  333.60  4886.2  333.56
  4900.7  332.50  4956.8  331.86  4977.5  330.10  4977.7  329.60  4981.5  330.10
  4985.8  330.89  5021.1  331.84  5143.4  332.88  5199.5  335.18  5278.3  335.12
#Mann=3,-1,0
  4465.3    0.05       0  4977.5    0.04       0  4981.5    0.05       0
Bank Sta=4977.5,4981.5
Exp/Cntr=0.3,0.1

Type RM Length L Ch R = 1,11050,286,286,286
BEGIN DESCRIPTION:
McAllister Slough 15.0
END DESCRIPTION:
XS GIS Cut Line= 3
      2729533.58      6740983.14      2729226.00      6741111.00
      2728800.96      6741281.61
#Sta/Elev= 30
  4662.8  332.10  4691.8  331.13  4707.5  331.63  4714.3  331.85  4721.1  330.85
  4726.5  331.21  4744.9  329.95  4766.3  329.45  4798.0  328.12  4827.3  327.86
  4851.2  326.36  4880.4  325.72  4904.3  324.17  4952.0  322.39  4974.2  322.48
  4986.7  320.90  4993.2  318.89  4998.6  318.89  5003.3  315.28  5003.6  314.78
  5007.1  314.78  5007.3  315.28  5010.7  316.00  5017.4  319.00  5028.2  320.34
  5071.4  322.53  5136.0  324.17  5340.7  333.65  5381.8  334.77  5453.9  335.51
#Mann=6,-1,0
  4662.8    0.12       0  4707.5    0.05       0  4766.3    0.12       0
  5003.3    0.07       0  5007.3    0.12       0  5071.4    0.05       0
Bank Sta=5003.3,5007.3
Exp/Cntr=0.3,0.1

Type RM Length L Ch R = 1,10764,294,294,294
BEGIN DESCRIPTION:
McAllister Slough 14.0
END DESCRIPTION:
XS GIS Cut Line= 3
      2729326.02      6740961.02      2729226.00      6740861.00
      2728929.50      6740739.17
#Sta/Elev= 30
  4858.5  322.99  4862.1  322.99  4915.1  319.28  4971.7  316.02  4985.8  314.40
  4996.4  312.79  5002.6  312.79  5007.2  311.20  5007.5  310.70  5011.0  310.70
  5011.2  311.20  5014.6  311.64  5021.6  313.88  5038.6  316.41  5045.9  316.85
  5068.0  318.62  5097.3  319.85  5129.7  322.49  5145.3  323.43  5151.3  324.31
  5162.1  325.01  5169.2  325.90  5183.7  327.17  5198.6  328.11  5228.0  330.75
  5270.2  333.22  5281.3  334.30  5299.9  335.19  5305.3  335.05  5320.5  335.71
#Mann=4,-1,0
  4858.5    0.12       0  5007.2    0.07       0  5011.2    0.12       0
  5045.9    0.05       0
Bank Sta=5007.2,5011.2
Exp/Cntr=0.3,0.1

Type RM Length L Ch R = 1,10470,232,232,232
BEGIN DESCRIPTION:
McAllister Slough 13.0
END DESCRIPTION:
XS GIS Cut Line= 3
      2729622.85      6740781.23      2729347.27      6740598.80
      2729126.03      6740528.94
#Sta/Elev= 30
  4735.6  322.24  4741.5  323.03  4747.4  320.89  4755.8  322.18  4762.5  321.92
  4855.8  315.51  4935.7  311.79  4958.1  309.78  4964.1  307.90  4977.1  306.49
  4977.4  305.99  4980.9  305.99  4981.1  306.49  5015.2  309.17  5036.3  308.33
  5047.8  309.08  5063.9  310.27  5074.0  310.26  5111.6  313.35  5130.3  313.55
  5151.3  316.33  5161.8  317.05  5171.0  317.59  5176.3  317.11  5203.4  318.50
  5208.6  317.83  5241.0  320.27  5266.7  321.15  5278.5  323.05  5298.1  323.91
#Mann=4,-1,0
  4735.6    0.12       0  4977.1    0.07       0  4981.1    0.12       0
  5047.8    0.05       0
Bank Sta=4977.1,4981.1
Exp/Cntr=0.3,0.1

Type RM Length L Ch R = 1,10238,282,282,282
BEGIN DESCRIPTION:
McAllister Slough 12.0
END DESCRIPTION:
XS GIS Cut Line= 3
      2729747.09      6740393.06      2729426.00      6740411.00
      2729106.53      6740389.17
#Sta/Elev= 30
  4678.5  330.16  4733.0  326.04  4739.7  324.86  4829.8  317.06  4930.0  309.60
  4940.0  308.61  4950.0  305.05  4960.0  304.95  4970.0  303.91  4990.1  303.89
  4995.6  302.56  4995.8  302.06  4999.3  302.06  4999.6  302.56  5010.1  303.52
  5060.2  305.91  5069.3  306.52  5080.3  307.95  5100.3  309.25  5120.4  310.00
  5130.4  311.00  5180.5  312.97  5190.5  313.99  5210.6  314.90  5217.9  316.12
  5222.9  315.97  5240.6  318.20  5300.8  323.51  5318.0  325.95  5320.3  325.95
#Mann=3,-1,0
  4678.5    0.05       0  4995.6    0.04       0  4999.6    0.05       0
Bank Sta=4995.6,4999.6
Exp/Cntr=0.3,0.1

Type RM Length L Ch R = 1,9956,300,300,300
BEGIN DESCRIPTION:
McAllister Slough 11.0
END DESCRIPTION:
XS GIS Cut Line= 3
      2729650.08      6740152.37      2729426.00      6740161.00
      2729175.99      6740111.00
#Sta/Elev= 30
  4771.5  324.26  4776.0  324.26  4825.6  318.13  4845.6  316.65  4863.2  314.66
  4868.2  314.54  4935.7  307.74  4955.7  305.38  4975.7  301.82  4993.2  299.40
  5005.9  299.46  5014.1  298.64  5014.4  298.14  5017.9  298.14  5018.1  298.64
  5026.3  299.75  5046.7  303.60  5067.1  306.16  5087.5  307.30  5118.1  309.98
  5128.3  311.62  5148.7  313.60  5169.1  316.44  5179.3  316.74  5189.5  319.66
  5209.9  321.58  5220.1  323.16  5240.5  327.21  5248.1  330.18  5250.7  330.18
#Mann=3,-1,0
  4771.5    0.05       0  5014.1    0.04       0  5018.1    0.05       0
Bank Sta=5014.1,5018.1
Exp/Cntr=0.3,0.1

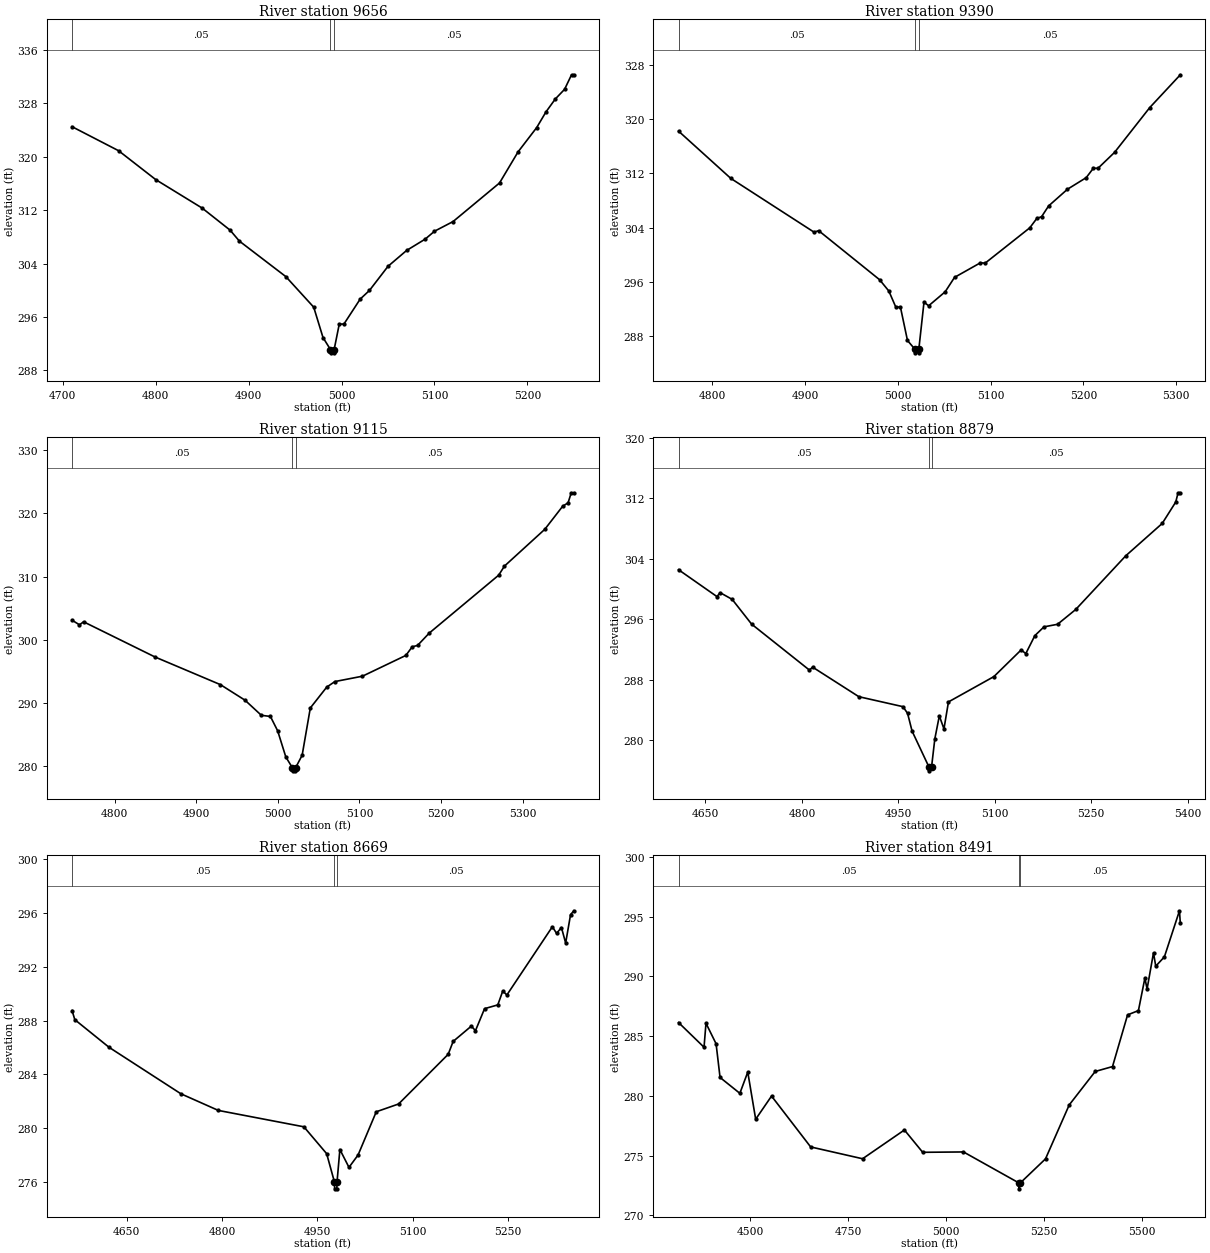
Type RM Length L Ch R = 1,9656,266,266,266
BEGIN DESCRIPTION:
McAllister Slough 10.0
END DESCRIPTION:
XS GIS Cut Line= 3
      2729716.06      6739861.22      2729426.00      6739861.00
      2729175.96      6739861.00
#Sta/Elev= 30
  4709.9  324.50  4760.0  320.90  4800.0  316.57  4850.0  312.30  4880.0  309.00
  4890.0  307.36  4940.0  302.04  4970.0  297.46  4980.0  292.91  4988.0  291.12
  4988.2  290.62  4991.7  290.62  4992.0  291.12  4997.5  294.93  5002.5  294.93
  5020.0  298.67  5030.0  299.97  5050.0  303.59  5070.0  305.96  5090.0  307.66
  5100.0  308.84  5120.0  310.29  5170.0  316.07  5190.0  320.74  5210.0  324.37
  5220.0  326.72  5230.0  328.65  5240.0  330.10  5247.5  332.28  5250.0  332.28
#Mann=3,-1,0
  4709.9    0.05       0  4988.0    0.04       0  4992.0    0.05       0
Bank Sta=4988,4992
Exp/Cntr=0.3,0.1

Type RM Length L Ch R = 1,9390,275,275,275
BEGIN DESCRIPTION:
McAllister Slough 9.0
END DESCRIPTION:
XS GIS Cut Line= 3
      2729712.19      6739597.24      2729476.00      6739611.00
      2729176.03      6739661.00
#Sta/Elev= 30
  4763.8  318.22  4820.1  311.25  4909.8  303.32  4914.8  303.54  4980.4  296.31
  4990.4  294.64  4997.9  292.27  5002.9  292.27  5010.5  287.34  5018.7  286.02
  5018.9  285.52  5022.4  285.52  5022.7  286.02  5028.3  293.00  5033.3  292.46
  5051.1  294.52  5061.2  296.65  5089.1  298.80  5094.2  298.75  5142.3  303.96
  5149.9  305.35  5155.0  305.60  5162.6  307.19  5182.9  309.65  5203.1  311.36
  5210.8  312.75  5215.8  312.74  5233.6  315.08  5271.6  321.70  5304.5  326.53
#Mann=3,-1,0
  4763.8    0.05       0  5018.7    0.04       0  5022.7    0.05       0
Bank Sta=5018.7,5022.7
Exp/Cntr=0.3,0.1

Type RM Length L Ch R = 1,9115,236,236,236
BEGIN DESCRIPTION:
McAllister Slough 8.0
END DESCRIPTION:
XS GIS Cut Line= 3
      2729727.66      6739325.50      2729374.44      6739341.02
      2729176.04      6739510.97
#Sta/Elev= 30
  4747.9  303.09  4757.0  302.36  4762.0  302.84  4849.7  297.26  4929.7  292.89
  4959.8  290.43  4979.8  288.04  4990.9  287.86  4999.8  285.58  5009.8  281.44
  5017.8  279.75  5018.1  279.25  5021.6  279.25  5021.8  279.75  5029.8  281.72
  5039.8  289.20  5059.9  292.50  5069.9  293.38  5103.7  294.23  5156.9  297.52
  5164.6  298.88  5171.2  299.10  5185.5  301.05  5270.6  310.22  5277.7  311.66
  5327.1  317.48  5349.0  321.13  5355.6  321.67  5359.5  323.26  5362.7  323.26
#Mann=3,-1,0
  4747.9    0.05       0  5017.8    0.04       0  5021.8    0.05       0
Bank Sta=5017.8,5021.8
Exp/Cntr=0.3,0.1

Type RM Length L Ch R = 1,8879,210,210,210
BEGIN DESCRIPTION:
McAllister Slough 7.0
END DESCRIPTION:
XS GIS Cut Line= 3
      2729828.65      6739057.63      2729490.90      6739104.22
      2729175.98      6739411.02
#Sta/Elev= 30
  4608.1  302.55  4667.8  299.00  4672.9  299.51  4691.5  298.63  4721.8  295.35
  4811.7  289.27  4816.7  289.66  4888.6  285.75  4957.2  284.43  4964.4  283.55
  4971.4  281.20  4997.7  276.44  4997.9  275.94  5001.7  276.44  5006.8  280.18
  5013.8  283.21  5021.0  281.49  5028.0  285.06  5098.7  288.41  5141.1  291.94
  5148.3  291.45  5162.4  293.83  5176.6  294.99  5197.7  295.33  5226.0  297.29
  5303.9  304.40  5360.5  308.67  5381.6  311.51  5385.2  312.73  5388.7  312.73
#Mann=3,-1,0
  4608.1    0.05       0  4997.7    0.04       0  5001.7    0.05       0
Bank Sta=4997.7,5001.7
Exp/Cntr=0.3,0.1

Type RM Length L Ch R = 1,8669,178,178,178
BEGIN DESCRIPTION:
McAllister Slough 6.0
END DESCRIPTION:
XS GIS Cut Line= 3
      2729754.88      6738875.18      2729362.79      6738945.06
      2729110.75      6739243.64
#Sta/Elev= 30
  4564.2  288.75  4568.5  288.07  4622.4  286.01  4735.3  282.55  4794.2  281.31
  4928.7  280.09  4964.5  278.09  4976.8  275.97  4977.0  275.47  4980.5  275.47
  4980.8  275.97  4985.3  278.40  4999.6  277.07  5013.9  277.99  5042.5  281.21
  5077.6  281.79  5155.6  285.49  5163.4  286.45  5192.0  287.59  5198.5  287.25
  5212.8  288.89  5233.6  289.17  5241.4  290.20  5247.9  289.91  5319.4  294.99
  5326.0  294.50  5333.7  294.93  5340.3  293.78  5348.0  295.89  5353.2  296.18
#Mann=3,-1,0
  4564.2    0.05       0  4976.8    0.04       0  4980.8    0.05       0
Bank Sta=4976.8,4980.8
Exp/Cntr=0.3,0.1

Type RM Length L Ch R = 1,8491,244,244,244
BEGIN DESCRIPTION:
McAllister Slough 5.0
END DESCRIPTION:
XS GIS Cut Line= 4
      2729910.87      6738695.75      2729362.68      6738777.35
      2729149.28      6738871.30      2728920.64      6739309.21
#Sta/Elev= 30
  4317.1  286.14  4382.2  284.07  4387.2  286.08  4413.0  284.36  4423.1  281.54
  4473.7  280.21  4493.9  281.99  4514.1  278.04  4554.6  279.98  4654.5  275.72
  4787.1  274.73  4893.9  277.14  4940.6  275.27  5044.8  275.30  5186.0  272.71
  5186.2  272.21  5190.0  272.71  5254.2  274.72  5314.8  279.24  5381.1  282.04
  5425.3  282.45  5463.8  286.78  5491.5  287.14  5508.0  289.86  5513.6  288.95
  5530.0  291.98  5535.7  290.86  5557.8  291.64  5596.3  295.50  5598.5  294.44
#Mann=3,-1,0
  4317.1    0.05       0  5186.0    0.04       0  5190.0    0.05       0
Bank Sta=5186,5190
Exp/Cntr=0.3,0.1

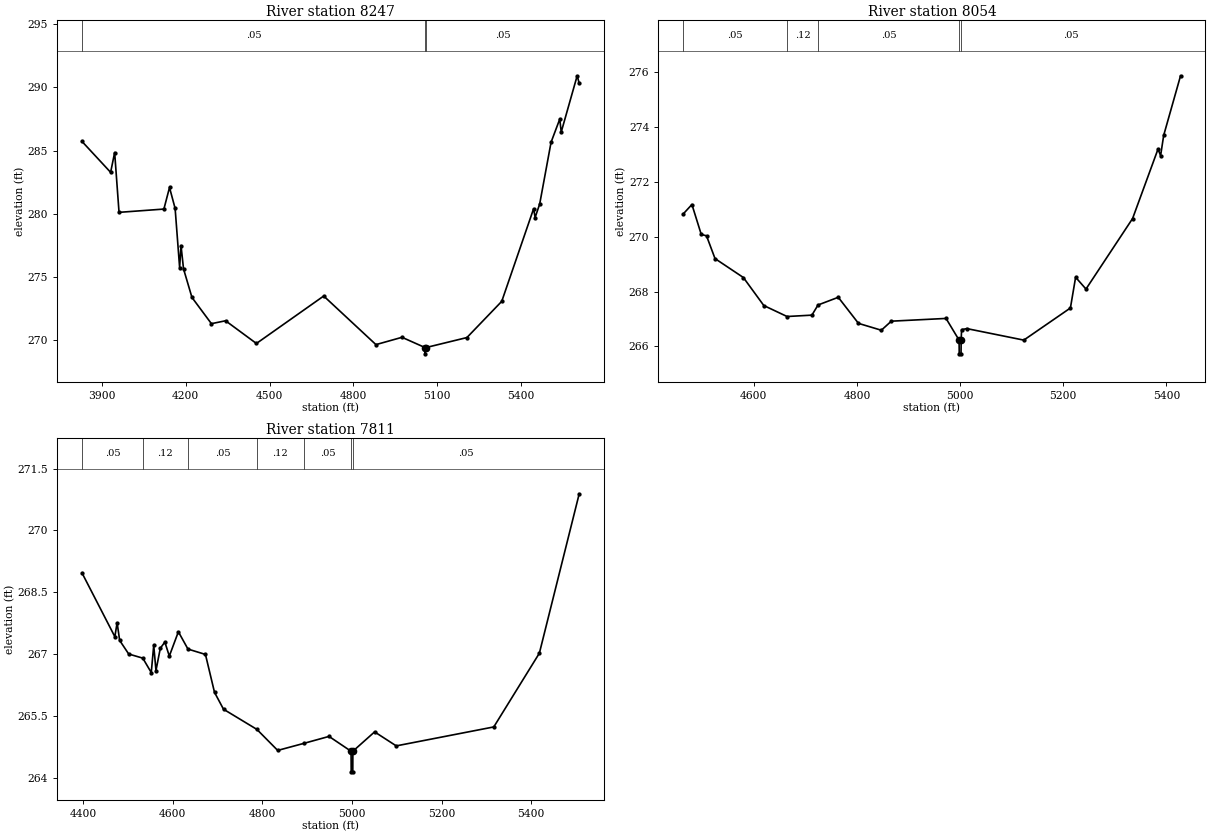
Type RM Length L Ch R = 1,8247,193,193,193
BEGIN DESCRIPTION:
McAllister Slough 4.0
END DESCRIPTION:
XS GIS Cut Line= 4
      2730118.24      6738566.07      2729062.71      6738656.49
      2728982.71      6738861.70      2728819.25      6739334.70
#Sta/Elev= 30
  3828.5  285.72  3931.1  283.27  3945.5  284.84  3961.2  280.10  4121.8  280.36
  4141.9  282.07  4162.0  280.41  4178.1  275.73  4183.1  277.47  4192.1  275.62
  4222.2  273.36  4291.9  271.28  4342.6  271.51  4453.0  269.71  4693.9  273.47
  4880.9  269.62  4974.2  270.20  5056.4  269.39  5056.7  268.89  5060.4  269.39
  5206.6  270.18  5331.3  273.05  5445.4  280.39  5450.7  279.69  5467.1  280.76
  5507.8  285.65  5539.0  287.49  5544.2  286.46  5601.3  290.92  5608.6  290.32
#Mann=3,-1,0
  3828.5    0.05       0  5056.4    0.04       0  5060.4    0.05       0
Bank Sta=5056.4,5060.4
Exp/Cntr=0.3,0.1

Type RM Length L Ch R = 1,8054,243,243,243
BEGIN DESCRIPTION:
McAllister Slough 2.0
END DESCRIPTION:
XS GIS Cut Line= 4
      2729200.06      6738483.15      2728888.60      6738548.54
      2728833.54      6738717.17      2728787.07      6739183.52
#Sta/Elev= 30
  4463.2  270.83  4479.9  271.17  4498.0  270.08  4508.2  270.03  4524.7  269.20
  4579.7  268.51  4619.3  267.49  4664.4  267.09  4712.6  267.14  4724.5  267.51
  4763.7  267.79  4802.9  266.84  4847.2  266.59  4866.6  266.92  4972.7  267.02
  4998.0  266.23  4998.3  265.73  5001.8  265.73  5002.0  266.23  5002.9  266.61
  5012.9  266.65  5123.5  266.23  5213.9  267.40  5224.0  268.52  5244.1  268.09
  5334.5  270.66  5383.8  273.19  5388.8  272.95  5394.8  273.69  5427.5  275.86
#Mann=5,-1,0
  4463.2    0.05       0  4664.4    0.12       0  4724.5    0.05       0
  4998.0    0.05       0  5002.0    0.05       0
Bank Sta=4998,5002
Exp/Cntr=0.3,0.1

Type RM Length L Ch R = 1,7811,0,0,0
BEGIN DESCRIPTION:
McAllister Slough 1.0
END DESCRIPTION:
XS GIS Cut Line= 4
      2729129.51      6738486.59      2728649.42      6738545.09
      2728594.35      6738787.72      2728709.43      6739146.69
#Sta/Elev= 30
  4397.6  268.97  4471.0  267.42  4476.0  267.76  4481.7  267.33  4501.9  267.00
  4533.3  266.90  4552.2  266.55  4557.7  267.21  4562.7  266.60  4572.4  267.14
  4582.5  267.29  4592.5  266.95  4612.7  267.54  4634.1  267.12  4673.1  266.99
  4693.3  266.07  4713.4  265.66  4787.9  265.17  4834.3  264.66  4892.3  264.83
  4948.8  265.00  4998.0  264.64  4998.3  264.14  5001.8  264.14  5002.0  264.64
  5050.5  265.11  5098.8  264.77  5316.4  265.23  5418.1  267.02  5507.0  270.89
#Mann=7,-1,0
  4397.6    0.05       0  4533.3    0.12       0  4634.1    0.05       0
  4787.9    0.12       0  4892.3    0.05       0  4998.0    0.05       0
  5002.0    0.05       0
Bank Sta=4998,5002
Exp/Cntr=0.3,0.1

Chan Stop Cuts=-1