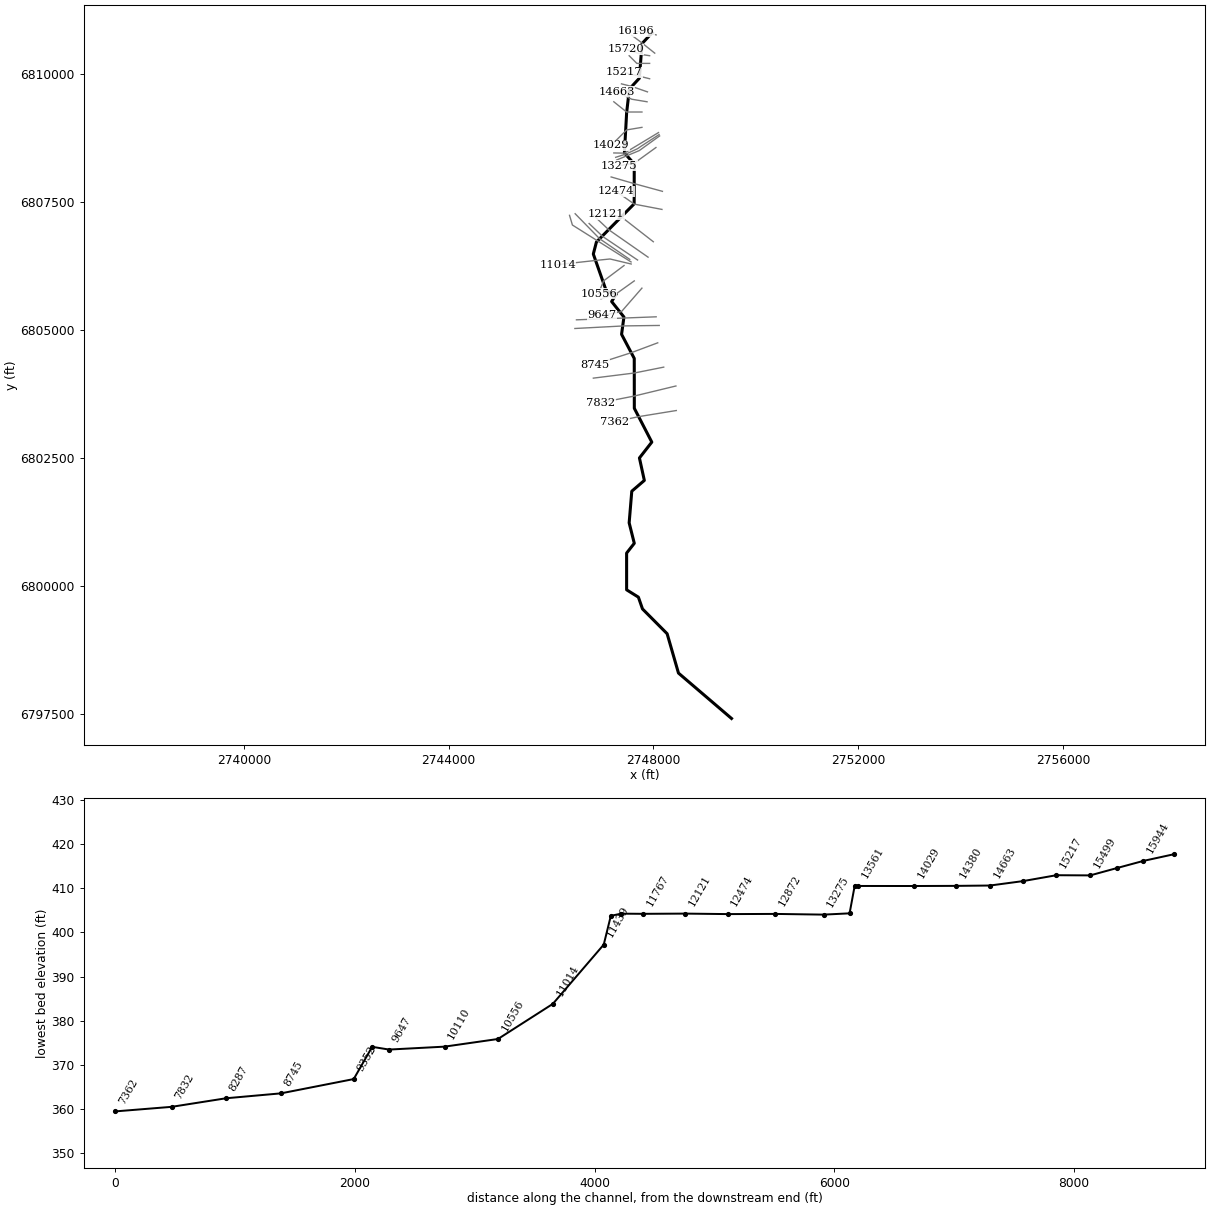
--- McGoughlin Branch.prj (project) ---

Proj Title=McGoughlin Branch Base Level Engineering
Current Plan=p01
Default Exp/Contr=0.3,0.1
English Units
Geom File=g01
Flow File=f01
Plan File=p01
Y Axis Title=Elevation
X Axis Title(PF)=Main Channel Distance
X Axis Title(XS)=Station
BEGIN DESCRIPTION:
McGoughlin Branch
END DESCRIPTION:
DSS Export Rating Curves= 0
DSS Export Rating Curve Sorted= 0
DSS Export Volume Flow Curves= 0
DXF OffsetX= 0
DXF OffsetY= 0
DXF ScaleX= 1
DXF ScaleY= 10

--- McGoughlin Branch.p01 (plan) ---

Plan Title=Multiple Run
Short Identifier=Multiple
Geom File=g01
Flow File=f01
Subcritical Flow
K Sum by GR= 0
Std Step Tol= 0.01
Critical Tol= 0.01
Num of Std Step Trials= 20
Max Error Tol= 0.3
Flow Tol Ratio= 0.001
Split Flow NTrial= 30
Split Flow Tol= 0.02
Split Flow Ratio= 0.02
Log Output Level= 0
Friction Slope Method= 1
Unsteady Friction Slope Method= 2
Unsteady Bridges Friction Slope Method= 1
Parabolic Critical Depth
Global Vel Dist=  1 , 1 , 1
Global Log Level= 0
CheckData=True
Encroach Param= -1, 0, 0, 0
BEGIN DESCRIPTION:
Multiple Run
END DESCRIPTION:

--- McGoughlin Branch.f01 (steady flow) ---

Flow Title=Multiple
Number of Profiles=7
Profile Names=10-year,25-year,50-year,1pct_min,100-year,1pct_plu,500-year
River Rch & RM= McGoughlin Branc,Reach-1,16196
     248     317     371     217     433     863     587
River Rch & RM= McGoughlin Branc,Reach-1,14029
     442     585     698     415     829    1653    1168
River Rch & RM= McGoughlin Branc,Reach-1,10556
     669     910    1110     673    1342    2678    1967
River Rch & RM= McGoughlin Branc,Reach-1,9506
     868    1197    1472     899    1793    3577    2668
River Rch & RM= McGoughlin Branc,Reach-1,6440
     953    1318    1622     991    1977    3944    2945
River Rch & RM= McGoughlin Branc,Reach-1,4617
    1019    1408    1733    1057    2110    4210    3138
Boundary for River Rch & Prof#=McGoughlin Branc,Reach-1,1
Up Type=0
Dn Type=3
Dn Slope=0.005
Boundary for River Rch & Prof#=McGoughlin Branc,Reach-1,2
Up Type=0
Dn Type=3
Dn Slope=0.005
Boundary for River Rch & Prof#=McGoughlin Branc,Reach-1,3
Up Type=0
Dn Type=3
Dn Slope=0.005
Boundary for River Rch & Prof#=McGoughlin Branc,Reach-1,4
Up Type=0
Dn Type=3
Dn Slope=0.005
Boundary for River Rch & Prof#=McGoughlin Branc,Reach-1,5
Up Type=0
Dn Type=3
Dn Slope=0.005
Boundary for River Rch & Prof#=McGoughlin Branc,Reach-1,6
Up Type=0
Dn Type=3
Dn Slope=0.005
Boundary for River Rch & Prof#=McGoughlin Branc,Reach-1,7
Up Type=0
Dn Type=3
Dn Slope=0.005

--- McGoughlin Branch.g01 (geometry) ---

Geom Title=Existing Conditions
Program Version=4.10

River Reach=McGoughlin Branc,Reach-1
Reach XY= 30
        2747976.        6810811.      2747777.96      6810599.03
      2747724.91      6809920.63      2747529.73      6809709.47
      2747476.52      6809245.78      2747433.33       6808460.9
      2747625.32      6808245.16      2747623.94      6807466.85
      2746886.47      6806720.82       2746825.6        6806486.
      2747081.34      6805758.26       2747273.4      6805703.18
       2747183.6      6805557.66      2747423.76      6805255.07
      2747377.82      6804917.12      2747625.51      6804445.78
      2747626.94      6803471.48      2747968.48      6802810.96
      2747726.75      6802501.22      2747822.55      6802062.25
       2747577.2      6801851.41      2747525.88       6801233.7
      2747626.11      6800833.68      2747476.25      6800642.42
      2747476.48      6799924.73      2747706.38      6799781.48
      2747786.51      6799551.19      2748267.84      6799067.05
      2748489.61      6798297.76        2749526.        6797411.

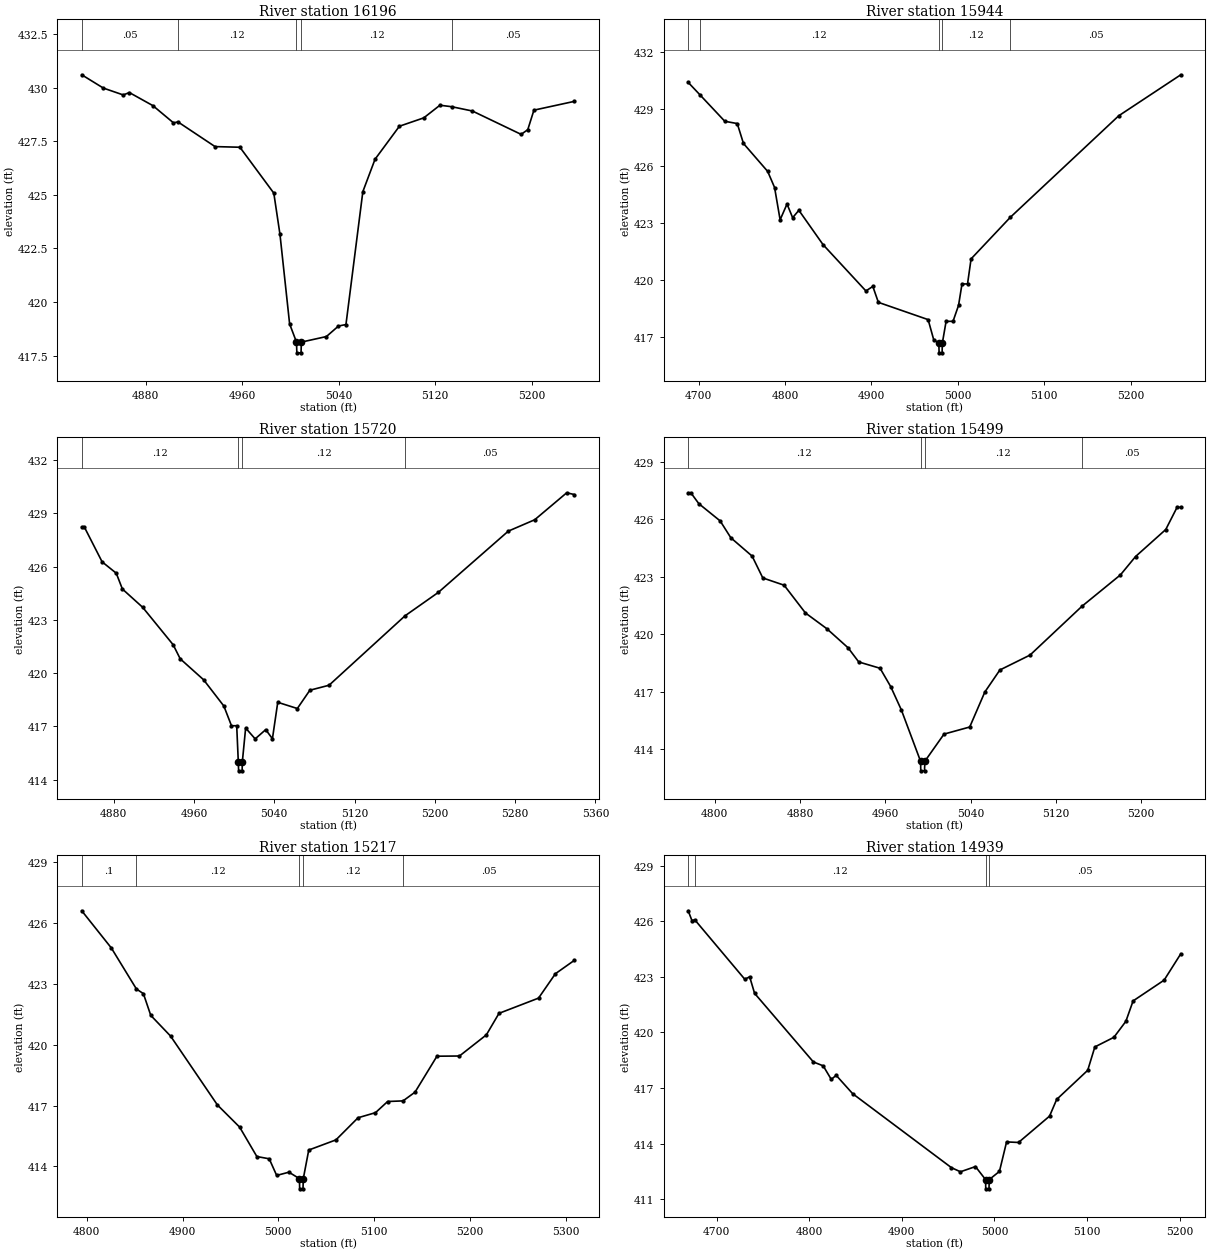
Type RM Length L Ch R = 1 ,16196   ,252,252,252
BEGIN DESCRIPTION:
McGoughlin Branch 37.0
END DESCRIPTION:
XS GIS Cut Line= 3
      2748053.34      6810767.57        2747876.        6810811.
      2747652.29      6810841.08
#Sta/Elev= 30
    4827   430.6  4844.9  429.98  4861.4  429.66  4866.5  429.77    4886  429.16
    4903  428.36  4906.8   428.4  4937.5  427.25  4958.1  427.22  4986.2  425.08
  4991.3  423.16  4999.3  418.98    5005  418.13  5005.3  417.63  5008.8  417.63
    5009  418.13  5029.8  418.39  5039.8  418.88    5046  418.95    5060  425.15
  5070.1  426.66  5090.3   428.2  5110.5  428.59  5123.9  429.18  5133.7  429.11
  5150.8  428.91  5191.2  427.82  5196.7  428.04  5201.8  428.95  5235.3  429.36
#Mann= 5 ,-1 , 0
    4827     .05       0  4906.8     .12       0    5005     .07       0
    5009     .12       0  5133.7     .05       0
Bank Sta=5005,5009
XS Rating Curve= 0 ,0
Exp/Cntr=0.3,0.1

Type RM Length L Ch R = 1 ,15944   ,224,224,224
BEGIN DESCRIPTION:
McGoughlin Branch 36.0
END DESCRIPTION:
XS GIS Cut Line= 3
      2748025.99      6810411.01        2747776.        6810611.
      2747576.04      6810760.97
#Sta/Elev= 30
    4688  430.39  4701.7  429.73  4730.4  428.34  4744.8  428.22    4752  427.17
    4780   425.7    4788  424.85  4794.4  423.15  4802.4  423.98  4808.9  423.26
  4816.1  423.65  4844.1  421.84  4893.7   419.4  4901.7  419.64  4908.1   418.8
  4965.7  417.89  4972.1  416.84  4978.1  416.64  4978.4  416.14  4981.9  416.14
  4982.1  416.64  4986.5   417.8  4994.5   417.8  5000.9  418.64  5004.9  419.77
  5011.3  419.77  5015.4  421.09  5060.8  423.28  5186.3  428.63  5258.1  430.79
#Mann= 5 ,-1 , 0
    4688     .05       0  4701.7     .12       0  4978.1     .07       0
  4982.1     .12       0  5060.8     .05       0
Bank Sta=4978.1,4982.1
XS Rating Curve= 0 ,0
Exp/Cntr=0.3,0.1

Type RM Length L Ch R = 1 ,15720   ,221,221,221
BEGIN DESCRIPTION:
McGoughlin Branch 35.0
END DESCRIPTION:
XS GIS Cut Line= 3
      2747926.04      6810360.99      2747775.96      6810383.77
      2747453.44      6810488.21
#Sta/Elev= 30
  4848.2  428.23  4850.8  428.23  4868.5  426.27  4882.6  425.63  4888.7  424.74
  4908.9  423.71  4939.3   421.6  4946.3  420.81  4969.6  419.63  4989.8  418.15
  4997.4  417.04  5002.6  417.04  5004.2     415  5004.5   414.5    5008   414.5
  5008.2     415  5011.5  416.91    5021   416.3  5031.5  416.82  5038.2  416.31
  5043.5  418.36    5063  418.01  5075.5  419.04  5094.6  419.32  5170.3  423.23
  5203.5  424.55  5273.2     428  5299.5  428.64  5331.4  430.16    5339  430.06
#Mann= 4 ,-1 , 0
  4848.2     .12       0  5004.2     .07       0  5008.2     .12       0
  5170.3     .05       0
Bank Sta=5004.2,5008.2
XS Rating Curve= 0 ,0
Exp/Cntr=0.3,0.1

Type RM Length L Ch R = 1 ,15499   ,282,282,282
BEGIN DESCRIPTION:
McGoughlin Branch 34.0
END DESCRIPTION:
XS GIS Cut Line= 3
      2747925.98        6810211.        2747676.        6810211.
      2747526.01      6810360.99
#Sta/Elev= 30
    4775  427.39  4777.5  427.39    4785  426.82    4805  425.92    4815  425.04
    4835  424.08    4845  422.94    4865  422.56    4885  421.11    4905  420.29
    4925  419.29    4935  418.55    4955  418.22    4965  417.26    4975  416.04
    4993  413.36  4993.2  412.86  4996.7  412.86    4997  413.36    5015  414.78
  5039.1  415.15  5053.3  416.98  5067.4  418.13  5095.7  418.91  5144.4  421.46
  5180.5   423.1  5194.7  424.06    5223  425.47  5233.6  426.63  5237.1  426.63
#Mann= 4 ,-1 , 0
    4775     .12       0    4993     .07       0    4997     .12       0
  5144.4     .05       0
Bank Sta=4993,4997
XS Rating Curve= 0 ,0
Exp/Cntr=0.3,0.1

Type RM Length L Ch R = 1 ,15217   ,278,278,278
BEGIN DESCRIPTION:
McGoughlin Branch 33.0
END DESCRIPTION:
XS GIS Cut Line= 3
      2747925.98        6809911.        2747726.        6809961.
      2747426.79      6810035.57
#Sta/Elev= 30
  4794.7  426.59  4825.6  424.76  4851.8  422.74  4859.1  422.51  4866.8  421.44
  4887.5  420.42  4936.4  417.03  4959.6  415.94  4977.6  414.49  4990.5  414.38
  4998.3  413.56  5011.1  413.72  5022.1   413.4  5022.3   412.9  5025.8   412.9
  5026.1   413.4  5031.8  414.81  5060.2  415.31  5083.3   416.4  5101.5  416.65
  5114.2   417.2  5130.3  417.23  5142.8  417.66  5165.7  419.43  5189.2  419.44
  5217.3  420.48  5230.5  421.54  5271.8  422.29  5289.4  423.49  5309.2  424.15
#Mann= 5 ,-1 , 0
  4794.7      .1       0  4851.8     .12       0  5022.1     .07       0
  5026.1     .12       0  5130.3     .05       0
Bank Sta=5022.1,5026.1
XS Rating Curve= 0 ,0
Exp/Cntr=0.3,0.1

Type RM Length L Ch R = 1 ,14939   ,276,276,276
BEGIN DESCRIPTION:
McGoughlin Branch 32.0
END DESCRIPTION:
XS GIS Cut Line= 3
      2747883.76      6809654.28        2747576.        6809761.
        2747376.        6809811.
#Sta/Elev= 30
  4669.3  426.56  4673.4  426.03  4676.5  426.07  4730.4  422.87  4735.7     423
    4741  422.11  4804.5  418.41  4815.1   418.2  4823.8  417.47  4829.1  417.69
  4846.9   416.7  4953.6  412.71  4963.3  412.49  4979.5  412.77  4990.4  412.07
  4990.6  411.57  4994.1  411.57  4994.4  412.07  5005.4  412.51  5013.1   414.1
    5026  414.07  5059.5  415.49  5067.2  416.39  5100.7  417.96  5108.4  419.22
    5129  419.74  5141.9   420.6  5149.7   421.7  5183.2  422.82  5201.2  424.24
#Mann= 4 ,-1 , 0
  4669.3      .1       0  4676.5     .12       0  4990.4     .05       0
  4994.4     .05       0
Bank Sta=4990.4,4994.4
XS Rating Curve= 0 ,0
Exp/Cntr=0.3,0.1

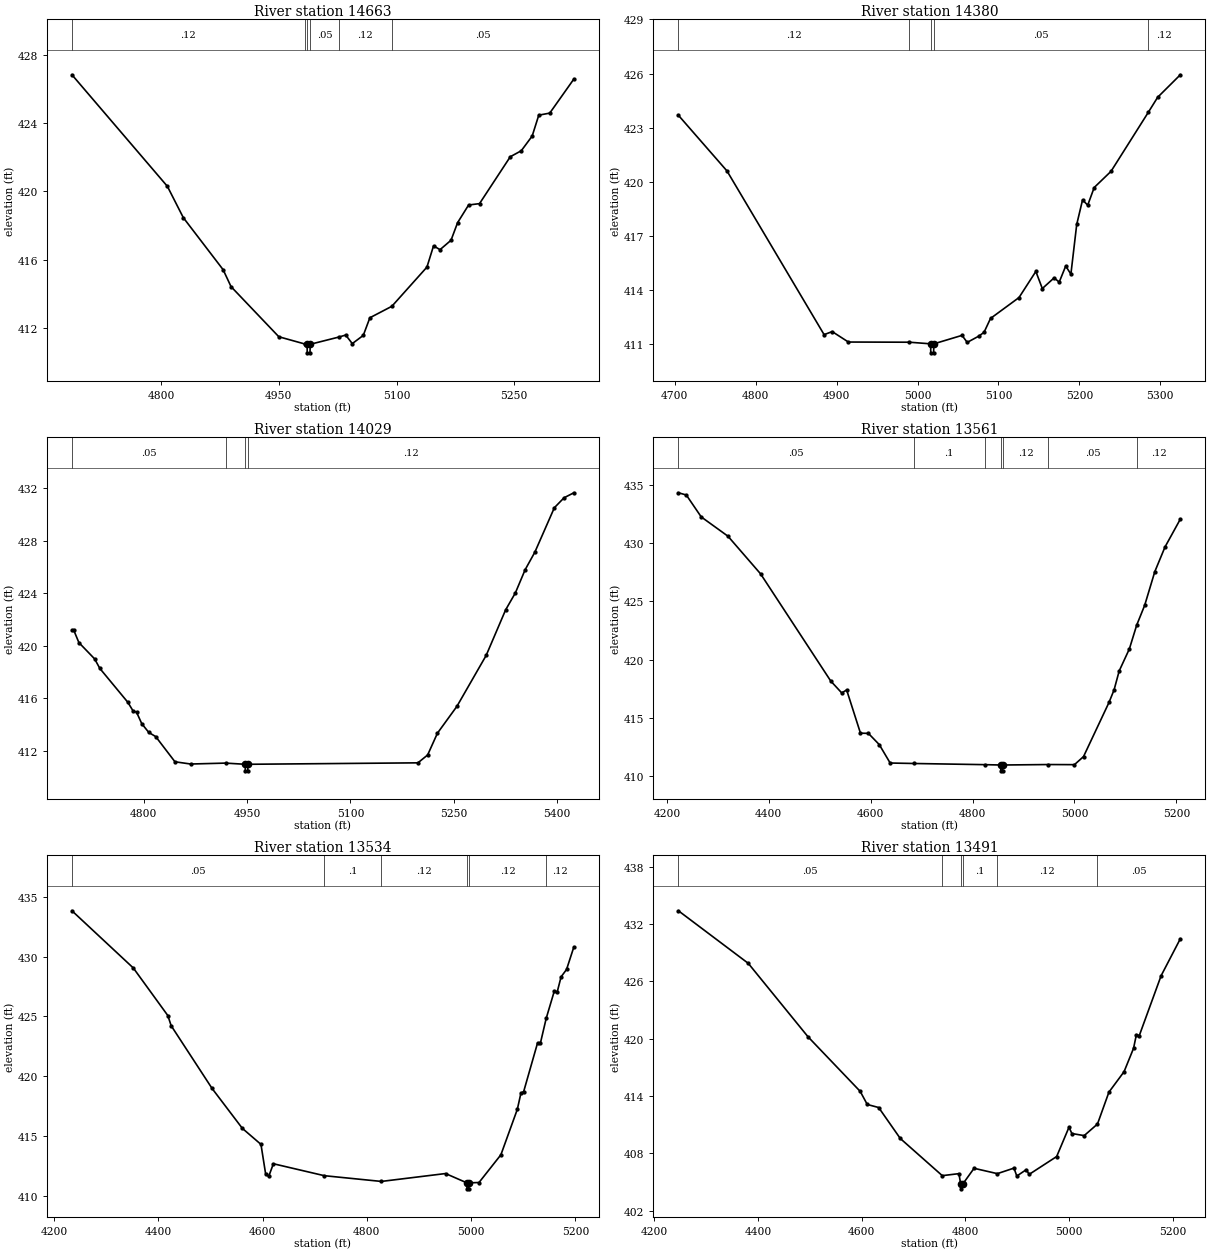
Type RM Length L Ch R = 1 ,14663   ,283,283,283
BEGIN DESCRIPTION:
McGoughlin Branch 31.0
END DESCRIPTION:
XS GIS Cut Line= 3
      2747875.99        6809461.        2747576.        6809511.
      2747276.03      6809660.98
#Sta/Elev= 30
  4686.4  426.82    4808   420.3  4828.3  418.47    4879  415.43  4889.1  414.44
    4950  411.51  4982.9  411.09    4986  411.07  4986.2  410.57  4989.7  410.57
    4990  411.07  5026.3  411.49  5035.2  411.61  5043.6  411.11  5057.6  411.59
    5066  412.62    5094  413.29  5138.7  415.58  5147.1  416.82  5155.4   416.6
  5169.4  417.15  5177.8  418.18  5191.8  419.21  5205.7  419.29  5244.9  422.03
  5258.9  422.38  5272.8  423.24  5281.2  424.46  5295.2  424.58  5325.9  426.57
#Mann= 6 ,-1 , 0
  4686.4     .12       0  4982.9     .05       0    4986     .04       0
    4990     .05       0  5026.3     .12       0    5094     .05       0
Bank Sta=4986,4990
XS Rating Curve= 0 ,0
Exp/Cntr=0.3,0.1

Type RM Length L Ch R = 1 ,14380   ,351,351,351
BEGIN DESCRIPTION:
McGoughlin Branch 30.0
END DESCRIPTION:
XS GIS Cut Line= 3
      2747775.97        6809261.        2747476.        6809261.
      2747226.02      6809460.98
#Sta/Elev= 30
  4704.6  423.68  4764.6  420.59  4884.6   411.5  4894.6  411.67  4914.6  411.09
  4990.1  411.08  5016.2  410.99  5016.4  410.49  5019.9  410.49  5020.2  410.99
    5055  411.46  5061.4  411.07  5075.8  411.42  5082.2  411.63  5090.2   412.4
  5125.4  413.56  5146.2  415.01  5154.2  414.06  5168.7  414.65  5175.1  414.42
  5183.1  415.31  5189.5  414.86  5196.7  417.62  5203.9  418.98  5210.3  418.69
  5218.3  419.67  5239.1  420.57  5285.2  423.85  5296.7  424.68  5324.7  425.93
#Mann= 5 ,-1 , 0
  4704.6     .12       0  4990.1     .05       0  5016.2     .04       0
  5020.2     .05       0  5285.2     .12       0
Bank Sta=5016.2,5020.2
XS Rating Curve= 0 ,0
Exp/Cntr=0.3,0.1

Type RM Length L Ch R = 1 ,14029   ,468,468,468
BEGIN DESCRIPTION:
McGoughlin Branch 29.0
END DESCRIPTION:
XS GIS Cut Line= 3
      2747775.96      6808960.99        2747476.        6808911.
      2747175.97      6808610.97
#Sta/Elev= 30
  4695.9   421.2  4698.4   421.2    4706  420.24  4728.8     419  4736.4  418.27
    4777  415.69  4784.6  415.03  4789.6  414.94  4797.2  414.06  4807.4  413.39
  4817.5  413.07  4845.4  411.15  4868.2  410.98  4918.9  411.05  4947.3  410.96
  4947.6  410.46  4951.1  410.46  4951.3  410.96    5198  411.07  5212.1  411.67
  5226.3  413.33  5254.6  415.38    5297  419.26  5325.3  422.74  5339.4  424.03
  5353.6   425.8  5367.7  427.14    5396  430.53  5410.1  431.29  5424.3  431.67
#Mann= 4 ,-1 , 0
  4695.9     .05       0  4918.9     .12       0  4947.3     .07       0
  4951.3     .12       0
Bank Sta=4947.3,4951.3
XS Rating Curve= 0 ,0
Exp/Cntr=0.3,0.1

Type RM Length L Ch R = 1 ,13561   ,27,27,27
BEGIN DESCRIPTION:
McGoughlin Branch 28.0
END DESCRIPTION:
XS GIS Cut Line= 3
      2748099.31      6808859.22      2747433.81      6808457.59
      2747226.04        6808461.
#Sta/Elev= 30
  4222.7   434.3  4238.2  434.11  4267.5  432.23  4319.9  430.58    4384  427.35
  4521.8  418.16  4543.2  417.15  4552.9   417.4    4580   413.7  4595.6  413.68
  4616.9  412.72  4638.3  411.14  4684.8   411.1  4823.7     411  4855.3  410.97
  4855.5  410.47    4859  410.47  4859.3  410.97    4949  411.01    5000     411
  5017.8  411.69  5067.8  416.33  5077.8  417.41  5087.8  419.03  5107.8  420.92
  5122.2  422.96  5137.8  424.65  5157.8  427.55  5177.8  429.66  5207.8  432.04
#Mann= 7 ,-1 , 0
  4222.7     .05       0  4684.8      .1       0  4823.7     .12       0
  4855.3     .04       0  4859.3     .12       0    4949     .05       0
  5122.2     .12       0
Bank Sta=4855.3,4859.3
XS Rating Curve= 0 ,0
Exp/Cntr=0.3,0.1

Type RM Length L Ch R = 1 ,13534   ,43,43,43
BEGIN DESCRIPTION:
Mapping XS 371b2209
END DESCRIPTION:
XS GIS Cut Line= 6
      2748110.52      6808819.64      2747762.99      6808594.81
      2747693.56      6808546.39      2747510.33      6808460.59
       2747476.9       6808444.2      2747262.66       6808375.5
#Sta/Elev= 30
  4234.1  433.84  4351.9  429.05  4418.1  425.07  4424.5  424.22    4503  418.97
  4561.1  415.63  4596.8  414.29  4605.9  411.78  4611.8  411.62  4620.6  412.67
  4718.4  411.67  4827.8  411.19    4951  411.85    4992  411.07  4992.2  410.57
  4995.7  410.57    4996  411.07  5015.2   411.1  5057.2  413.42  5088.7  417.22
  5095.6  418.57  5100.9  418.71  5127.7   422.8    5133  422.76  5144.1  424.83
  5159.9  427.15  5165.1  427.02  5172.7  428.31  5183.2  428.93  5197.2  430.81
#Mann= 6 ,-1 , 0
  4234.1     .05       0  4718.4      .1       0  4827.8     .12       0
    4992     .04       0    4996     .12       0  5144.1     .12       0
Bank Sta=4992,4996
XS Rating Curve= 0 ,0
Exp/Cntr=0.3,0.1

Type RM Length L Ch R = 1 ,13491   ,216,216,216
BEGIN DESCRIPTION:
Mapping XS 42b6c318
END DESCRIPTION:
XS GIS Cut Line= 3
      2748121.41      6808793.91      2747723.91      6808507.29
      2747282.72       6808323.5
#Sta/Elev= 30
  4246.7  433.38  4381.4  427.88  4496.7  420.19  4597.3  414.48  4610.9  413.11
  4632.9  412.79  4674.6  409.55  4755.6  405.66  4787.7  405.87  4791.1  404.78
  4791.3  404.28  4795.1  404.78  4816.9  406.43  4861.8  405.87  4893.9  406.45
  4899.3  405.62  4917.7  406.29  4923.1  405.79  4976.2  407.66    5000  410.73
  5005.5  410.07  5029.3  409.85  5054.9  411.06    5077   414.4  5106.2  416.54
  5124.5  418.99    5130  420.42  5135.5  420.31  5177.7  426.59  5214.7  430.45
#Mann= 6 ,-1 , 0
  4246.7     .05       0  4755.6      .1       0  4791.1     .07       0
  4795.1      .1       0  4861.8     .12       0  5054.9     .05       0
Bank Sta=4791.1,4795.1
XS Rating Curve= 0 ,0
Exp/Cntr=0.3,0.1

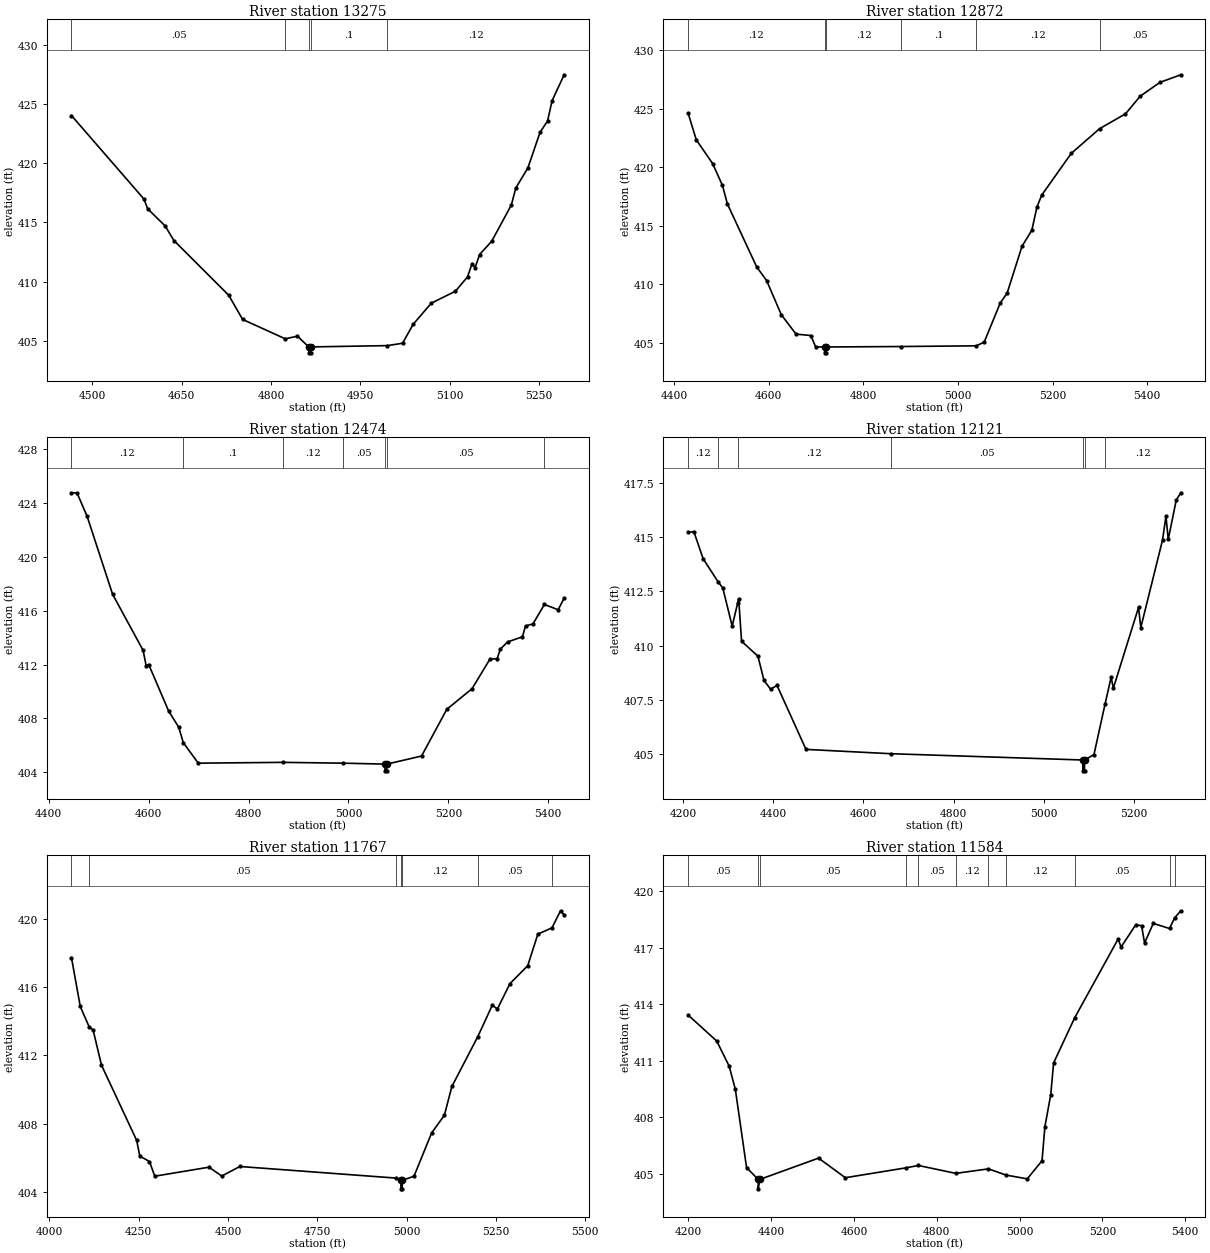
Type RM Length L Ch R = 1 ,13275   ,403,403,403
BEGIN DESCRIPTION:
McGoughlin Branch 27.0
END DESCRIPTION:
XS GIS Cut Line= 3
      2748049.58      6808567.24        2747626.        6808261.
      2747326.03        6808211.
#Sta/Elev= 30
  4465.3  424.02  4586.9  416.97  4593.1  416.15  4622.5   414.7  4637.2  413.47
  4729.2  408.85  4752.5  406.81  4824.2  405.17  4844.5   405.4  4863.4  404.49
  4863.6  403.99  4867.1  403.99  4867.4  404.49  4995.5   404.6  5020.9   404.8
  5038.7   406.4  5069.1  408.18  5109.6  409.19  5129.9   410.4  5137.5  411.51
  5142.6  411.18  5150.2  412.29  5170.5  413.41  5203.4  416.46    5211  417.91
  5231.3  419.61  5251.6   422.6  5264.2  423.56  5271.9  425.28  5292.1  427.46
#Mann= 5 ,-1 , 0
  4465.3     .05       0  4824.2      .1       0  4863.4     .07       0
  4867.4      .1       0  4995.5     .12       0
Bank Sta=4863.4,4867.4
XS Rating Curve= 0 ,0
Exp/Cntr=0.3,0.1

Type RM Length L Ch R = 1 ,12872   ,398,398,398
BEGIN DESCRIPTION:
McGoughlin Branch 26.0
END DESCRIPTION:
XS GIS Cut Line= 3
      2748176.02      6807710.99        2747626.        6807861.
       2747173.7      6807992.01
#Sta/Elev= 30
  4429.9  424.64  4447.2  422.36  4481.7  420.33  4502.5  418.46  4512.8  416.89
    4575  411.48  4595.8  410.33  4626.9   407.4    4658  405.75  4689.1  405.63
  4699.4  404.66  4718.1  404.65  4718.4  404.15  4721.9  404.15  4722.1  404.65
  4879.1  404.69    5039  404.75  5055.6  405.07  5089.2  408.39  5104.1  409.27
  5135.4  413.26  5156.2  414.63  5166.8  416.59    5177  417.63  5239.5   421.2
  5299.3  423.31    5354  424.58  5385.2  426.09  5426.9  427.27  5470.9  427.92
#Mann= 6 ,-1 , 0
  4429.9     .12       0  4718.1     .07       0  4722.1     .12       0
  4879.1      .1       0    5039     .12       0  5299.3     .05       0
Bank Sta=4718.1,4722.1
XS Rating Curve= 0 ,0
Exp/Cntr=0.3,0.1

Type RM Length L Ch R = 1 ,12474   ,353,353,353
BEGIN DESCRIPTION:
McGoughlin Branch 25.0
END DESCRIPTION:
XS GIS Cut Line= 3
      2748166.86      6807357.78        2747626.        6807461.
      2747269.79      6807712.05
#Sta/Elev= 30
  4445.4  424.77  4456.5  424.76  4476.8  423.01  4527.7  417.23  4588.8  413.06
  4594.9  411.91    4600  412.01  4639.7  408.57  4660.1  407.35  4669.2  406.21
  4699.2  404.68    4868  404.74  4989.6  404.68  5072.8  404.61  5073.1  404.11
  5076.6  404.11  5076.8  404.61  5146.3  405.21  5196.8  408.68  5247.3  410.21
    5283   412.4  5297.8  412.45  5303.9  413.15  5318.7  413.69  5348.3  414.07
  5354.4  414.88  5369.2  415.02  5392.2  416.47  5419.7  416.08  5431.8  416.94
#Mann= 7 ,-1 , 0
  4445.4     .12       0  4669.2      .1       0    4868     .12       0
  4989.6     .05       0  5072.8     .03       0  5076.8     .05       0
  5392.2     .12       0
Bank Sta=5072.8,5076.8
XS Rating Curve= 0 ,0
Exp/Cntr=0.3,0.1

Type RM Length L Ch R = 1 ,12121   ,354,354,354
BEGIN DESCRIPTION:
McGoughlin Branch 24.0
END DESCRIPTION:
XS GIS Cut Line= 3
      2747998.18      6806725.97        2747376.        6807211.
      2747076.04      6807260.99
#Sta/Elev= 30
  4211.1  415.22  4223.8  415.26  4244.6     414  4277.7  412.94    4288  412.66
  4308.9   410.9  4321.3  411.98  4323.3  412.16  4329.7   410.2    4366  409.51
  4379.4   408.4  4393.9  407.99  4408.4  408.16  4472.6  405.21  4661.2  405.01
  5086.7  404.72    5087  404.22  5090.5  404.22  5090.7  404.72  5111.5  404.97
  5136.1   407.3  5149.5  408.53  5154.6  408.04  5210.4  411.76  5215.4  410.83
  5263.6  414.87  5271.2  415.97  5276.3   414.9    5294  416.71  5304.1  417.05
#Mann= 7 ,-1 , 0
  4211.1     .12       0  4277.7      .1       0  4321.3     .12       0
  4661.2     .05       0  5086.7     .03       0  5090.7     .05       0
  5136.1     .12       0
Bank Sta=5086.7,5090.7
XS Rating Curve= 0 ,0
Exp/Cntr=0.3,0.1

Type RM Length L Ch R = 1 ,11767   ,183,183,183
BEGIN DESCRIPTION:
McGoughlin Branch 23.0
END DESCRIPTION:
XS GIS Cut Line= 3
      2747895.18      6806424.71        2747126.        6806961.
      2746805.14      6807264.44
#Sta/Elev= 30
  4062.1  417.72  4086.7  414.86  4112.1  413.64  4122.5  413.49  4146.1  411.42
  4244.6  407.01  4253.4  406.09  4280.5  405.77  4295.2  404.91  4447.1  405.44
  4482.8  404.92  4533.4  405.48  4970.9   404.8  4984.3  404.67  4984.5  404.17
    4988  404.17  4988.3  404.67    5021  404.91  5070.4  407.45    5106  408.48
    5127  410.17  5199.8   413.1  5240.3  414.94  5254.4  414.71  5289.6   416.2
  5339.4  417.25  5367.7   419.1  5407.3  419.47  5431.2  420.47  5441.4  420.22
#Mann= 7 ,-1 , 0
  4062.1     .12       0  4112.1     .05       0  4970.9     .12       0
  4984.3     .07       0  4988.3     .12       0  5199.8     .05       0
  5407.3     .12       0
Bank Sta=4984.3,4988.3
XS Rating Curve= 0 ,0
Exp/Cntr=0.3,0.1

Type RM Length L Ch R = 1 ,11584   ,86,86,86
BEGIN DESCRIPTION:
Mapping XS caff3f19
END DESCRIPTION:
XS GIS Cut Line= 3
      2747690.74      6806368.98       2747014.3      6806824.68
      2746743.43      6807082.26
#Sta/Elev= 30
  4199.8  413.43  4268.9  412.05  4298.9  410.72  4313.9  409.48  4340.9  405.34
  4368.9  404.71  4369.1  404.21  4372.9  404.71  4514.8  405.84  4579.3   404.8
  4724.7  405.32  4755.7  405.45    4846  405.03    4925  405.27  4967.3  404.94
  5018.6  404.74  5054.2   405.7  5061.1   407.5  5075.3  409.21  5082.2  410.89
  5133.2  413.29  5237.9  417.46  5245.1  417.04  5280.3  418.21  5294.5  418.17
  5301.8  417.25  5322.8  418.29    5362  418.02  5374.3  418.58  5389.2  418.96
#Mann= 11 ,-1 , 0
  4199.8     .05       0  4368.9     .07       0  4372.9     .05       0
  4724.7     .12       0  4755.7     .05       0    4846     .12       0
    4925     .05       0  4967.3     .12       0  5133.2     .05       0
    5362     .12       0  5374.3     .05       0
Bank Sta=4368.9,4372.9
XS Rating Curve= 0 ,0
Exp/Cntr=0.3,0.1

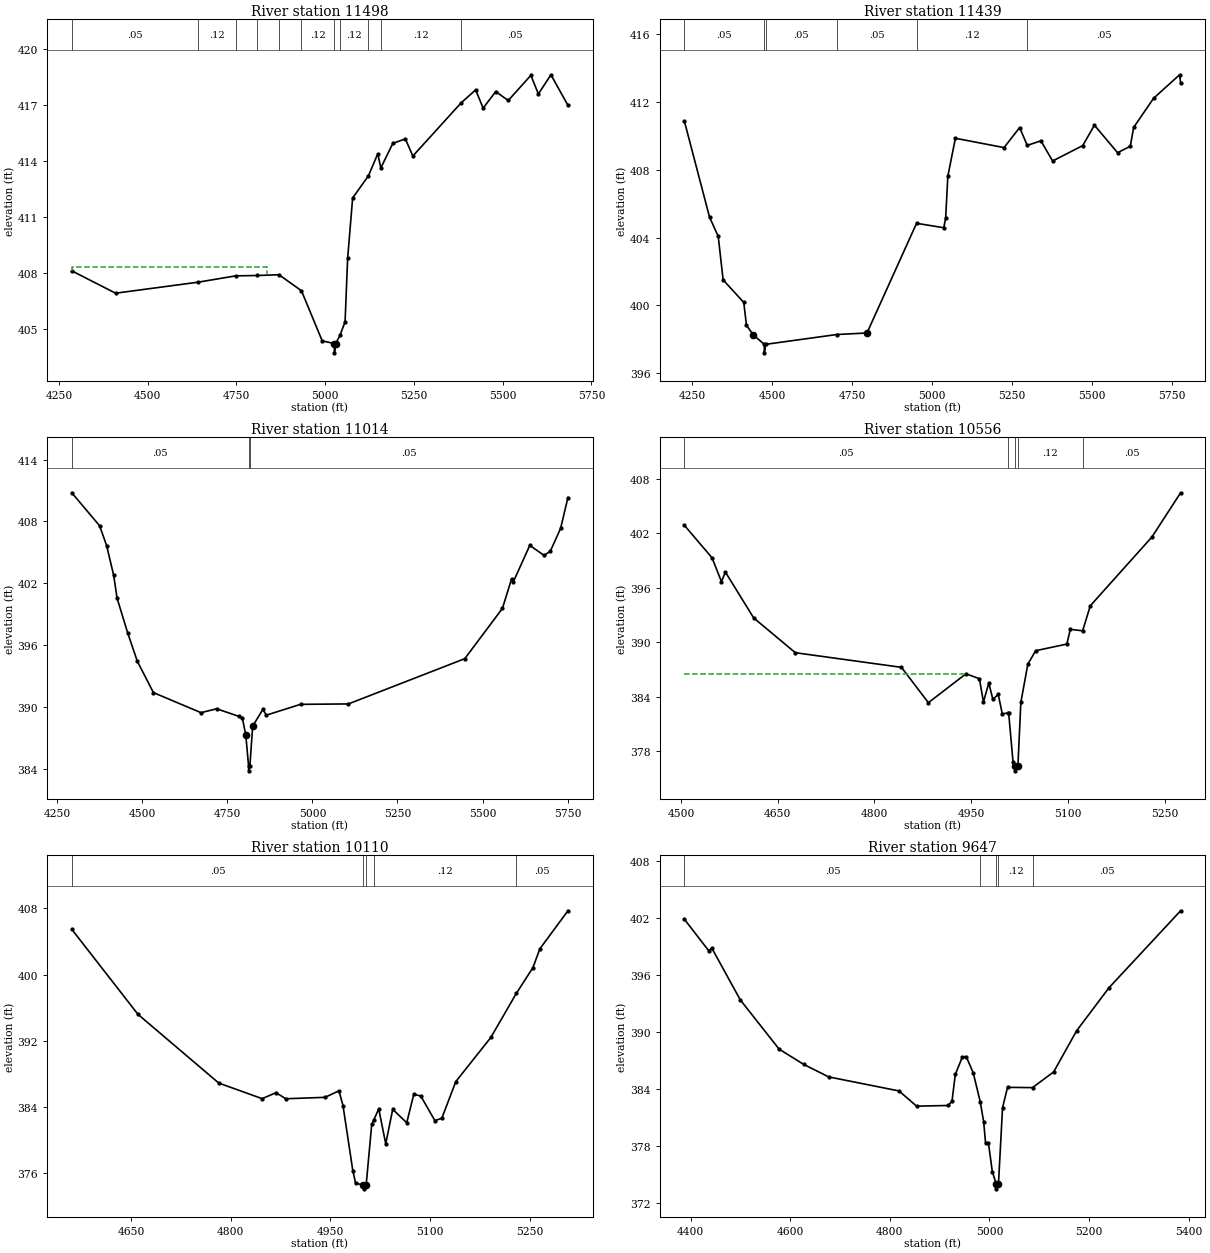
Type RM Length L Ch R = 1 ,11498   ,59,59,59
BEGIN DESCRIPTION:
McGoughlin Branch 22.0
END DESCRIPTION:
XS GIS Cut Line= 3
      2747537.74      6806380.96      2746949.12      6806784.73
      2746470.67       6807273.4
#Sta/Elev= 30
  4286.2  408.11  4409.6  406.91  4641.6   407.5    4748  407.84  4808.9  407.86
    4870   407.9  4933.2  407.04  4991.7  404.35  5025.8  404.21  5026.1  403.71
  5029.8  404.21    5042  404.66  5056.1  405.38  5063.3  408.78  5077.4  412.02
  5121.9  413.21  5148.1  414.39  5156.8  413.63  5190.6  414.95  5225.9  415.19
    5247  414.27  5382.8  417.12  5423.9  417.82    5445  416.84  5480.5  417.73
  5515.7  417.25  5579.5   418.6  5600.6   417.6    5636  418.63  5683.9  416.99
#Mann= 11 ,-1 , 0
  4286.2     .05       0  4641.6     .12       0    4748     .05       0
  4808.9     .12       0    4870     .05       0  4933.2     .12       0
  5025.8     .05       0    5042     .12       0  5121.9     .05       0
  5156.8     .12       0  5382.8     .05       0
#XS Ineff= 2 , 0
         4834.79   408.3
Permanent Ineff=
       F       F
Bank Sta=5025.8,5029.8
XS Rating Curve= 0 ,0
Exp/Cntr=0.3,0.1

Type RM Length L Ch R = 1 ,11439   ,425,425,425
BEGIN DESCRIPTION:
Mapping XS c42c114b
END DESCRIPTION:
XS GIS Cut Line= 3
       2747562.9      6806331.32       2746416.9      6807052.81
      2746360.94       6807241.8
#Sta/Elev= 30
    4226  410.84  4304.5   405.2  4331.6  404.07  4346.9  401.51  4411.4  400.18
  4419.9  398.83  4441.1  398.27  4475.6  397.71  4475.8  397.21  4479.6  397.71
  4702.5  398.29  4796.7  398.38  4951.7  404.84  5036.8  404.58  5042.7  405.16
  5049.5  407.61  5073.1  409.85  5225.2   409.3    5274  410.48  5297.8  409.43
  5340.6   409.7  5377.1  408.51  5471.3  409.42  5507.8  410.62  5580.2     409
    5620  409.38  5630.5  410.49    5693  412.21  5774.2  413.59  5777.3  413.11
#Mann= 6 ,-1 , 0
    4226     .05       0  4475.6     .07       0  4479.6     .05       0
  4702.5     .05       0  4951.7     .12       0  5297.8     .05       0
Bank Sta=4441.1,4796.7
XS Rating Curve= 0 ,0
Exp/Cntr=0.3,0.1

Type RM Length L Ch R = 1 ,11014   ,458,458,458
BEGIN DESCRIPTION:
McGoughlin Branch 21.0
END DESCRIPTION:
XS GIS Cut Line= 4
      2747565.61      6806290.88      2747151.44      6806389.19
        2746876.        6806361.      2746124.63      6806277.97
#Sta/Elev= 30
  4292.6  410.78  4374.4  407.58    4395  405.66  4415.5  402.81  4425.8  400.55
  4456.6  397.22  4485.1  394.45  4532.5   391.4  4672.5  389.45  4718.3  389.83
  4784.1  389.09  4794.1  388.92  4804.2  387.26  4812.2  384.31  4812.5  383.81
  4816.2  384.31  4824.3  388.15  4854.4  389.77  4864.5  389.21    4965  390.26
  5105.8   390.3  5447.9  394.69  5558.6  399.57  5585.3  402.42  5590.4  402.13
    5639  405.68  5681.2   404.7  5699.4  405.12  5729.6  407.33  5751.1  410.32
#Mann= 3 ,-1 , 0
  4292.6     .05       0  4812.2     .04       0  4816.2     .05       0
Bank Sta=4804.2,4824.3
XS Rating Curve= 0 ,0
Exp/Cntr=0.3,0.1

Type RM Length L Ch R = 1 ,10556   ,446,446,446
BEGIN DESCRIPTION:
McGoughlin Branch 20.0
END DESCRIPTION:
XS GIS Cut Line= 3
      2747426.04      6806261.03        2747026.        6805961.
        2746926.        6805711.
#Sta/Elev= 30
  4505.4  402.88  4548.2  399.31  4562.7   396.7    4569  397.73  4612.7   392.7
  4677.3  388.87  4841.9  387.26  4883.6  383.37  4941.9  386.55  4962.7  386.01
    4969  383.45  4977.3  385.54  4983.6  383.73  4991.9  384.28  4998.2  382.15
  5006.6  382.23  5008.1  382.23  5014.9  376.83  5018.1  376.37  5018.5  375.87
  5022.4  376.37    5027  383.41  5037.8   387.6  5049.9  389.09  5098.3  389.82
  5103.7  391.44  5122.8  391.28  5134.7  394.04  5230.3  401.61  5274.7  406.47
#Mann= 5 ,-1 , 0
  4505.4     .05       0  5006.6     .12       0  5018.1     .04       0
  5022.4     .12       0  5122.8     .05       0
#XS Ineff= 2 , 0
         4942.76  386.57
Permanent Ineff=
       F       F
Bank Sta=5018.1,5022.4
XS Rating Curve= 0 ,0
Exp/Cntr=0.3,0.1

Type RM Length L Ch R = 1 ,10110   ,463,463,463
BEGIN DESCRIPTION:
McGoughlin Branch 19.0
END DESCRIPTION:
XS GIS Cut Line= 3
      2747626.01      6805961.01        2747276.        6805711.
      2746975.96      6805610.99
#Sta/Elev= 30
  4561.1  405.48  4660.7  395.21  4782.3  386.91  4847.5  385.03  4868.3  385.75
  4883.1  385.02  4942.1  385.19    4963  385.98  4969.1   384.2  4983.9  376.32
  4988.2  374.79  4999.6  374.64    5000  374.14    5004  374.64  5012.3  381.91
  5015.7  382.51  5022.9  383.79  5033.4  379.58  5043.9  383.74    5065  382.12
  5075.6  385.56  5086.1  385.35  5107.2  382.39  5117.7  382.65  5138.8  387.09
  5191.5  392.42  5229.9  397.75  5254.8  400.85  5265.3  403.13  5307.5  407.72
#Mann= 5 ,-1 , 0
  4561.1     .05       0  4999.6     .04       0    5004     .05       0
  5015.7     .12       0  5229.9     .05       0
#XS Ineff= 2 , 0
                         5076.96          385.46
Permanent Ineff=
       F       F
Bank Sta=4999.6,5004
XS Rating Curve= 0 ,0
Exp/Cntr=0.3,0.1

Type RM Length L Ch R = 1 ,9647    ,141,141,141
BEGIN DESCRIPTION:
McGoughlin Branch 18.0
END DESCRIPTION:
XS GIS Cut Line= 3
      2747775.42      6805819.66        2747376.        6805361.
      2746994.83      6805285.86
#Sta/Elev= 30
  4387.4  401.84  4435.9  398.55  4442.6  398.79  4499.5  393.37  4577.4  388.19
  4626.7  386.58  4677.1  385.26  4818.5  383.78  4853.7  382.18  4917.3  382.25
  4924.9  382.72  4931.5  385.52  4945.7  387.36  4953.4   387.4  4967.6  385.67
  4981.8  382.59  4988.5  380.52  4992.3  378.29  4998.1  378.29  5005.8   375.3
  5013.8  373.98  5014.2  373.48  5018.2  373.98  5026.4  382.02  5036.4  384.16
  5086.6  384.13    5129  385.78  5175.3  390.12  5240.2  394.64  5384.1  402.74
#Mann= 5 ,-1 , 0
  4387.4     .05       0  4981.8     .12       0  5013.8     .07       0
  5018.2     .12       0  5086.6     .05       0
#XS Ineff= 2 , 0
         4953.23  387.36
Permanent Ineff=
       F       F
Bank Sta=5013.8,5018.2
XS Rating Curve= 0 ,0
Exp/Cntr=0.3,0.1

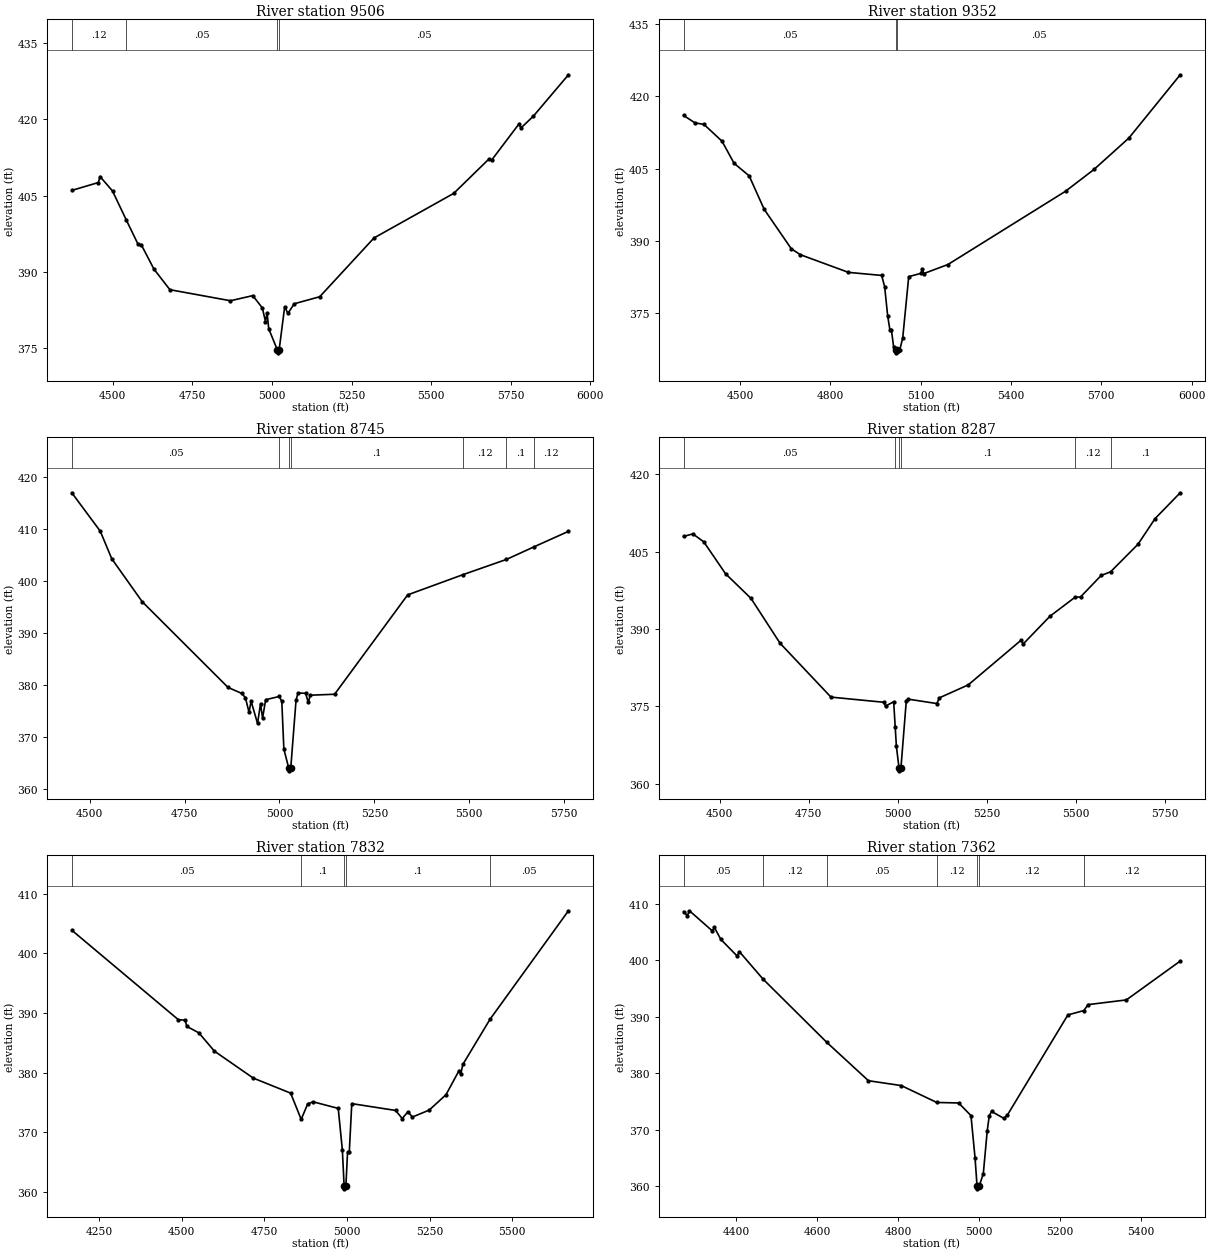
Type RM Length L Ch R = 1 ,9506    ,154,154,154
BEGIN DESCRIPTION:
Mapping XS a2098c30
END DESCRIPTION:
XS GIS Cut Line= 2
      2748053.58       6805259.2      2746496.09      6805200.17
#Sta/Elev= 30
  4372.2     406  4455.7  407.55  4460.7  408.73  4499.9  405.89  4543.2  400.19
  4579.9  395.45  4589.9  395.37    4630  390.54    4680   386.5  4870.1  384.33
  4940.2  385.34  4970.2  382.91    4980  380.24    4985  381.98  4990.2  378.83
  5017.7   374.6  5018.4   374.1  5022.7   374.6  5040.3  383.17  5050.3  381.84
  5070.3  383.74  5150.3  385.12  5320.5  396.66  5570.6  405.41  5680.7  412.13
  5690.7  412.03  5776.3  419.12  5781.3  418.23  5820.8  420.59  5930.8  428.71
#Mann= 4 ,-1 , 0
  4372.2     .12       0  4543.2     .05       0  5017.7     .05       0
  5022.7     .05       0
Bank Sta=5017.7,5022.7
XS Rating Curve= 0 ,0
Exp/Cntr=0.3,0.1

Type RM Length L Ch R = 1 ,9352    ,607,607,607
BEGIN DESCRIPTION:
McGoughlin Branch 17.0
END DESCRIPTION:
XS GIS Cut Line= 3
       2748113.8      6805090.35      2747426.26      6805081.55
      2746465.49       6805030.9
#Sta/Elev= 30
  4312.4  416.03  4350.2  414.49  4380.2  414.17  4440.2  410.68  4480.2   406.1
  4530.2  403.51  4580.2  396.56  4670.2  388.39  4700.2  387.16  4860.2  383.49
  4970.3  382.86  4980.3  380.53  4990.3  374.49  4997.6  371.62  5002.6  371.62
  5010.3  367.99  5017.8  367.31  5018.4  366.81  5022.8  367.31  5030.3  367.37
  5040.3  369.88  5060.3  382.61  5100.4  383.28  5105.4  384.11  5110.5  383.25
  5190.5  385.12  5581.1  400.31  5675.7  404.83  5791.4  411.33  5962.1  424.46
#Mann= 3 ,-1 , 0
  4312.4     .05       0  5017.8     .05       0  5022.8     .05       0
Bank Sta=5017.8,5022.8
XS Rating Curve= 0 ,0
Exp/Cntr=0.3,0.1

Type RM Length L Ch R = 1 ,8745    ,458,458,458
BEGIN DESCRIPTION:
McGoughlin Branch 16.0
END DESCRIPTION:
XS GIS Cut Line= 3
      2748084.19      6804751.11        2747576.        6804561.
      2746847.17      6804326.55
#Sta/Elev= 30
  4453.1  416.99    4528  409.62  4558.3  404.32  4638.5  396.07  4864.7   379.6
  4900.4  378.46  4910.3  377.65    4920   374.8  4925.3  376.98  4942.3  372.69
  4950.3  376.48  4955.6  373.68  4963.7  377.24  4999.3  377.86  5006.2  376.95
  5011.7  367.75  5024.6  364.08  5025.3  363.58  5029.8  364.08  5043.8  377.19
  5049.1  378.54  5069.2  378.47  5075.9  376.71  5081.1  378.11  5145.3  378.29
  5337.8  397.38  5482.6  401.24    5598  404.19  5671.3  406.63  5761.3  409.58
#Mann= 7 ,-1 , 0
  4453.1     .05       0  4999.3      .1       0  5024.6     .07       0
  5029.8      .1       0  5482.6     .12       0    5598      .1       0
  5671.3     .12       0
Bank Sta=5024.6,5029.8
XS Rating Curve= 0 ,0
Exp/Cntr=0.3,0.1

Type RM Length L Ch R = 1 ,8287    ,455,455,455
BEGIN DESCRIPTION:
McGoughlin Branch 15.0
END DESCRIPTION:
XS GIS Cut Line= 3
      2748201.44      6804275.93        2747626.        6804161.
      2746826.03        6804061.
#Sta/Elev= 30
  4399.1  407.97    4425  408.46  4455.6  406.93  4516.8  400.73  4588.2  395.94
  4669.8  387.23  4812.5  376.78  4960.4  375.78  4965.5  375.03  4988.4  375.88
  4992.7  370.97    4996  367.21  5003.5  362.97  5004.2  362.47  5008.7  362.97
  5023.7  375.99  5028.7  376.39  5109.4  375.53  5116.9  376.65  5197.5  379.15
  5346.2  387.85  5351.2  387.06  5426.8  392.48  5497.4  396.18  5512.5  396.22
  5570.4  400.39  5596.9  401.11  5673.7  406.45  5721.6  411.43  5792.1  416.44
#Mann= 6 ,-1 , 0
  4399.1     .05       0  4992.7      .1       0  5003.5     .07       0
  5008.7      .1       0  5497.4     .12       0  5596.9      .1       0
Bank Sta=5003.5,5008.7
XS Rating Curve= 0 ,0
Exp/Cntr=0.3,0.1

Type RM Length L Ch R = 1 ,7832    ,470,470,470
BEGIN DESCRIPTION:
McGoughlin Branch 14.0
END DESCRIPTION:
XS GIS Cut Line= 3
       2748439.8       6803907.6        2747626.        6803711.
       2746972.4      6803583.15
#Sta/Elev= 30
    4167  403.87  4489.8  388.86  4509.9  388.81    4515  387.76  4551.6  386.67
  4598.8   383.6  4716.2  379.09  4829.3  376.57  4861.3  372.17  4880.8  374.75
    4897  375.12  4973.4  374.01  4985.9  367.04  4991.2  361.03    4992  360.53
  4996.6  361.03  5001.6  366.63  5006.8  366.63  5014.4  374.81  5146.9  373.67
  5167.2  372.31  5184.5  373.46  5197.8  372.56  5248.8  373.73  5299.7  376.31
  5339.1  380.35  5344.2  379.77  5350.7  381.39  5432.5  388.92  5670.2  407.13
#Mann= 5 ,-1 , 0
    4167     .05       0  4861.3      .1       0  4991.2     .07       0
  4996.6      .1       0  5432.5     .05       0
Bank Sta=4991.2,4996.6
XS Rating Curve= 0 ,0
Exp/Cntr=0.3,0.1

Type RM Length L Ch R = 1 ,7362    ,474,474,474
BEGIN DESCRIPTION:
McGoughlin Branch 13.0
END DESCRIPTION:
XS GIS Cut Line= 3
      2748446.91      6803428.06        2747726.        6803311.
      2747239.88      6803208.78
#Sta/Elev= 30
  4269.7  408.59  4279.1   407.9  4284.2  408.75  4340.7  405.19  4345.8   405.8
  4361.8  403.67  4402.3  400.72  4407.4  401.53  4465.9  396.66  4623.5  385.45
  4726.5  378.65  4807.6  377.79  4895.2   374.8  4949.4  374.71  4979.8  372.47
  4989.9  364.97  4994.8     360  4995.6   359.5  5000.2     360  5010.3  362.19
  5019.9  369.74    5025  372.45  5030.7  373.21  5061.4  371.97  5069.7  372.56
  5219.2   390.3  5258.8  391.08  5269.1  392.13  5363.7  392.96  5496.8  399.84
#Mann= 7 ,-1 , 0
  4269.7     .05       0  4465.9     .12       0  4623.5     .05       0
  4895.2     .12       0  4994.8     .07       0  5000.2     .12       0
  5258.8     .12       0
Bank Sta=4994.8,5000.2
XS Rating Curve= 0 ,0
Exp/Cntr=0.3,0.1