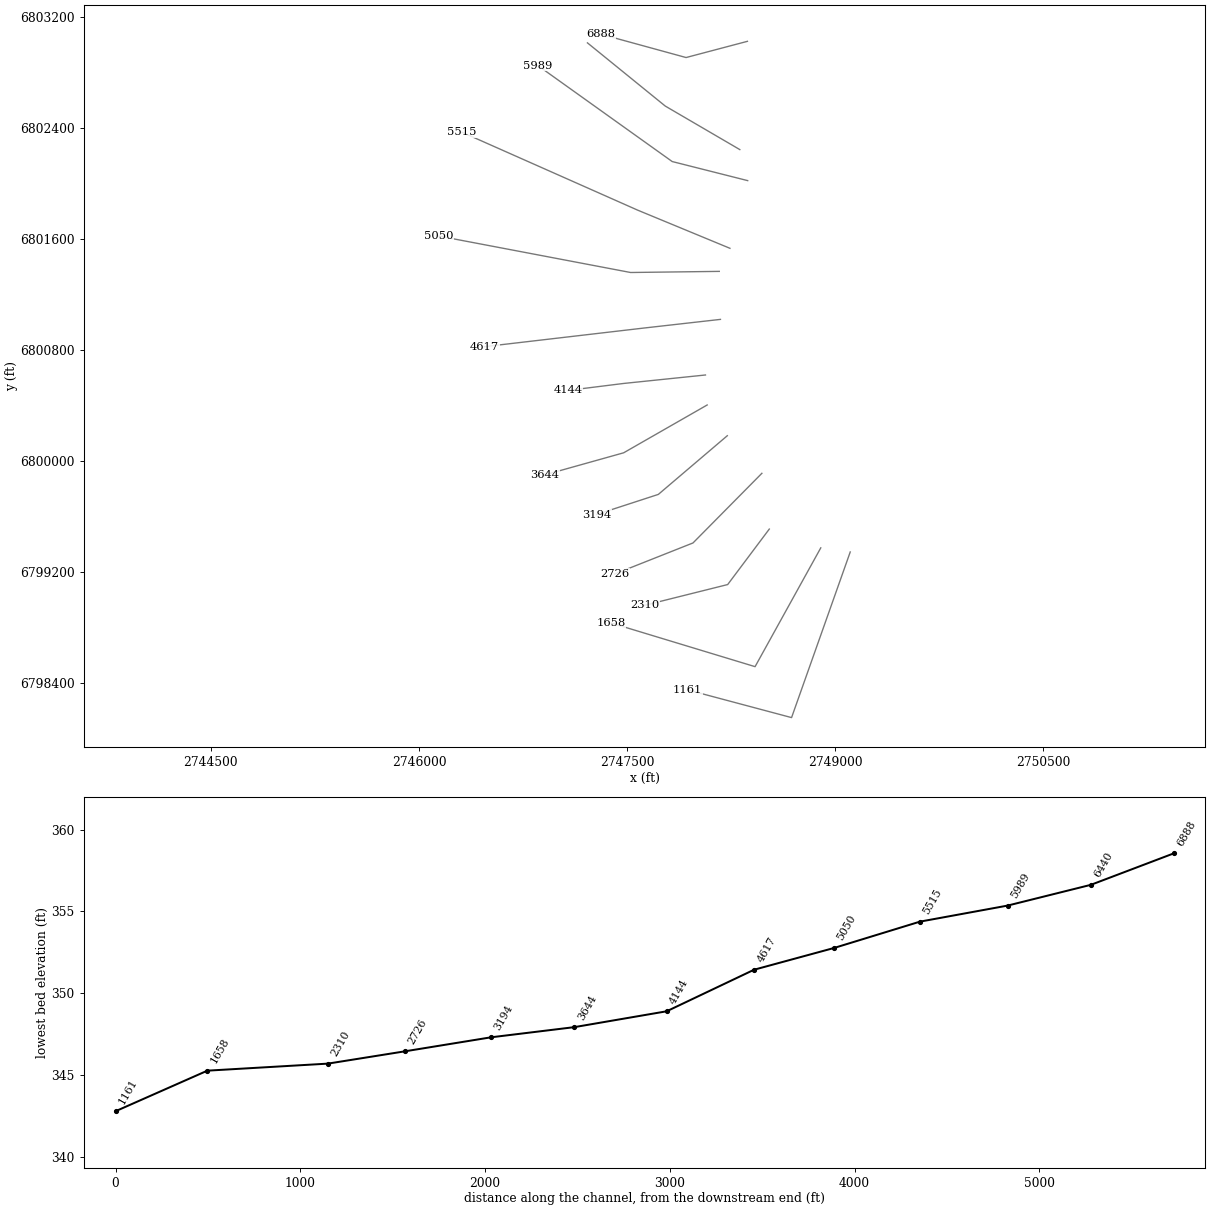
HEC-RAS study McGoughlin Branch.prj: McGoughlin Branch Base Level Engineering

--- McGoughlin Branch.g01 (geometry) --- (continued)

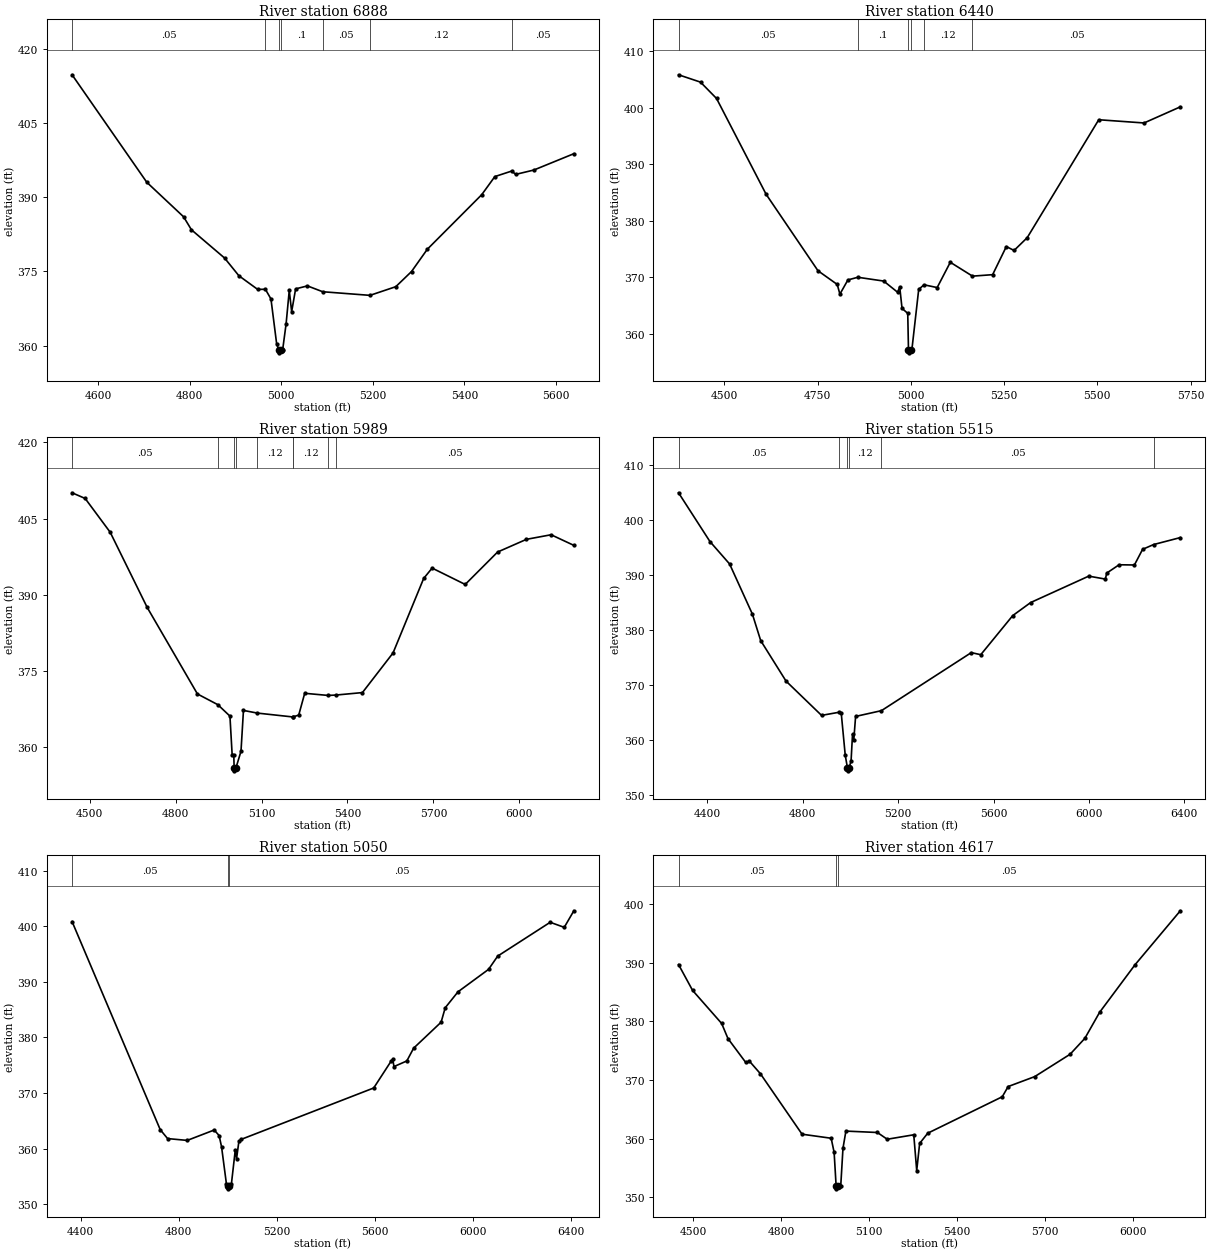
Type RM Length L Ch R = 1 ,6888    ,448,448,448
BEGIN DESCRIPTION:
McGoughlin Branch 12.0
END DESCRIPTION:
XS GIS Cut Line= 3
      2748368.29      6803027.85        2747926.        6802911.
      2747309.48      6803079.91
#Sta/Elev= 30
  4542.6  414.71  4705.9     393  4786.4  386.02  4803.5   383.4  4875.9   377.7
  4907.2  374.12  4948.3  371.36  4965.1  371.39  4977.3  369.43  4989.7  360.39
  4994.7  359.05  4995.5  358.55  5000.2  359.05  5002.7  359.05  5010.4  364.42
  5017.3  371.16  5022.5  366.86  5031.2  371.47    5057  372.07  5090.4  370.89
  5193.7  370.16  5250.1  371.91  5284.5  374.97    5319  379.47    5438   390.5
  5466.6  394.15  5503.6  395.27  5512.1  394.59  5551.8  395.47  5639.3  398.77
#Mann= 7 ,-1 , 0
  4542.6     .05       0  4965.1      .1       0  4994.7     .07       0
  5000.2      .1       0  5090.4     .05       0  5193.7     .12       0
  5503.6     .05       0
Bank Sta=4994.7,5000.2
XS Rating Curve= 0 ,0
Exp/Cntr=0.3,0.1

Type RM Length L Ch R = 1 ,6440    ,451,451,451
BEGIN DESCRIPTION:
McGoughlin Branch 11.0
END DESCRIPTION:
XS GIS Cut Line= 3
      2748313.44      6802247.24        2747776.        6802561.
      2747214.77      6803016.75
#Sta/Elev= 30
  4377.4  405.79  4436.3  404.49  4479.3   401.6  4612.4  384.64  4751.3  371.14
  4802.9  368.72    4810  367.01  4831.5  369.52  4858.1  369.99  4927.4  369.32
  4964.6  367.35  4970.4  368.28  4976.6  364.49  4991.9  363.61  4993.9  357.13
  4994.8  356.63  4999.7  357.13  5002.9  357.13  5021.3  367.85  5035.5  368.66
  5070.8  368.17    5106  372.64  5165.5  370.19  5219.5  370.45  5256.2  375.42
    5277  374.73  5312.2  376.99    5504  397.84  5625.4  397.27  5722.7  400.12
#Mann= 6 ,-1 , 0
  4377.4     .05       0  4858.1      .1       0  4993.9     .07       0
  4999.7      .1       0  5035.5     .12       0  5165.5     .05       0
Bank Sta=4993.9,4999.7
XS Rating Curve= 0 ,0
Exp/Cntr=0.3,0.1

Type RM Length L Ch R = 1 ,5989    ,474,474,474
BEGIN DESCRIPTION:
McGoughlin Branch 10.0
END DESCRIPTION:
XS GIS Cut Line= 3
      2748370.31      6802023.45        2747826.        6802161.
      2746857.55      6802853.01
#Sta/Elev= 30
  4438.7  410.08  4484.4  408.96  4571.8  402.31    4701  387.51  4876.3  370.49
  4947.5  368.38  4989.8  366.13  4997.5  358.55  5003.2  358.55  5004.5  355.86
  5005.5  355.36  5010.4  355.86  5028.4  359.21    5037  367.25  5084.8  366.73
  5208.5  365.97  5209.6  365.97  5229.9  366.33  5250.8  370.62  5332.3   370.2
  5358.9  370.27  5452.3  370.76  5559.2  378.56  5666.1  393.22  5695.6  395.26
  5811.1  392.04  5924.2  398.42    6025  400.92    6111  401.82  6190.4  399.73
#Mann= 9 ,-1 , 0
  4438.7     .05       0  4947.5      .1       0  5004.5     .07       0
  5010.4      .1       0  5084.8     .12       0  5208.5      .1       0
  5209.6     .12       0  5332.3      .1       0  5358.9     .05       0
Bank Sta=5004.5,5010.4
XS Rating Curve= 0 ,0
Exp/Cntr=0.3,0.1

Type RM Length L Ch R = 1 ,5515    ,465,465,465
BEGIN DESCRIPTION:
McGoughlin Branch 9.0
END DESCRIPTION:
XS GIS Cut Line= 3
      2748242.34      6801535.46        2747576.        6801811.
      2746310.59      6802372.11
#Sta/Elev= 30
  4278.5  405.02  4410.3  396.14  4492.8  392.05  4588.4  382.92  4623.2   378.1
  4729.6  370.72  4878.5  364.48  4953.5  365.06    4961  364.95  4977.9  357.23
  4987.3  354.88  4988.3  354.38  4993.3  354.88  5002.3  356.11  5008.5  361.07
  5013.9  360.05  5021.4  364.29  5129.8  365.34  5506.8  375.91  5546.5  375.53
  5680.6  382.65  5755.9  385.03  5999.6  389.84  6069.4   389.3  6074.9  390.39
  6126.9  391.91  6191.2  391.87  6225.5  394.72  6271.6  395.59  6383.8  396.86
#Mann= 6 ,-1 , 0
  4278.5     .05       0  4953.5     .12       0  4987.3     .07       0
  4993.3     .12       0  5129.8     .05       0  6271.6      .1       0
Bank Sta=4987.3,4993.3
XS Rating Curve= 0 ,0
Exp/Cntr=0.3,0.1

Type RM Length L Ch R = 1 ,5050    ,433,433,433
BEGIN DESCRIPTION:
McGoughlin Branch 8.0
END DESCRIPTION:
XS GIS Cut Line= 3
      2748165.44      6801369.09        2747526.        6801361.
      2746144.24      6801623.66
#Sta/Elev= 30
  4365.1  400.84  4724.6  363.41  4754.6  361.81  4834.6  361.48  4944.6  363.35
  4964.6  362.36  4974.6  360.34  4994.6  353.61  4998.9  353.27  4999.9  352.77
  5005.2  353.27  5014.8  353.66  5030.7  359.79  5035.8  358.21  5045.3  361.31
  5055.5  361.68    5595  370.91  5666.2  375.75  5672.6  376.05  5677.7  374.76
    5730  375.77  5757.8  378.07  5869.8  382.74  5886.6  385.34  5938.8  388.21
  6063.2  392.24  6100.6  394.63  6314.6  400.71  6371.9   399.8  6411.1  402.78
#Mann= 3 ,-1 , 0
  4365.1     .05       0  4998.9     .04       0  5005.2     .05       0
Bank Sta=4998.9,5005.2
XS Rating Curve= 0 ,0
Exp/Cntr=0.3,0.1

Type RM Length L Ch R = 1 ,4617    ,473,473,473
BEGIN DESCRIPTION:
McGoughlin Branch 7.0
END DESCRIPTION:
XS GIS Cut Line= 3
      2748173.72      6801022.93        2747626.        6800961.
      2746472.26      6800826.24
#Sta/Elev= 30
  4449.2  389.66  4497.2  385.25  4596.4  379.62    4618  377.04  4678.4  372.99
  4691.2  373.19  4728.7  371.05  4870.8  360.75  4970.2  360.06  4980.3  357.65
  4987.1  351.94  4988.2  351.44  4993.5  351.94  5002.9  351.97  5010.5  358.35
  5020.5  361.28    5128  361.04  5161.5  359.89  5252.1  360.65  5262.2  354.56
  5272.2  359.18  5299.8  360.92  5554.2  367.13  5574.3  368.87  5664.9  370.56
  5785.7  374.37  5836.1  377.08  5886.4  381.51  6007.2  389.61    6162  398.82
#Mann= 3 ,-1 , 0
  4449.2     .05       0  4987.1     .04       0  4993.5     .05       0
Bank Sta=4987.1,4993.5
XS Rating Curve= 0 ,0
Exp/Cntr=0.3,0.1

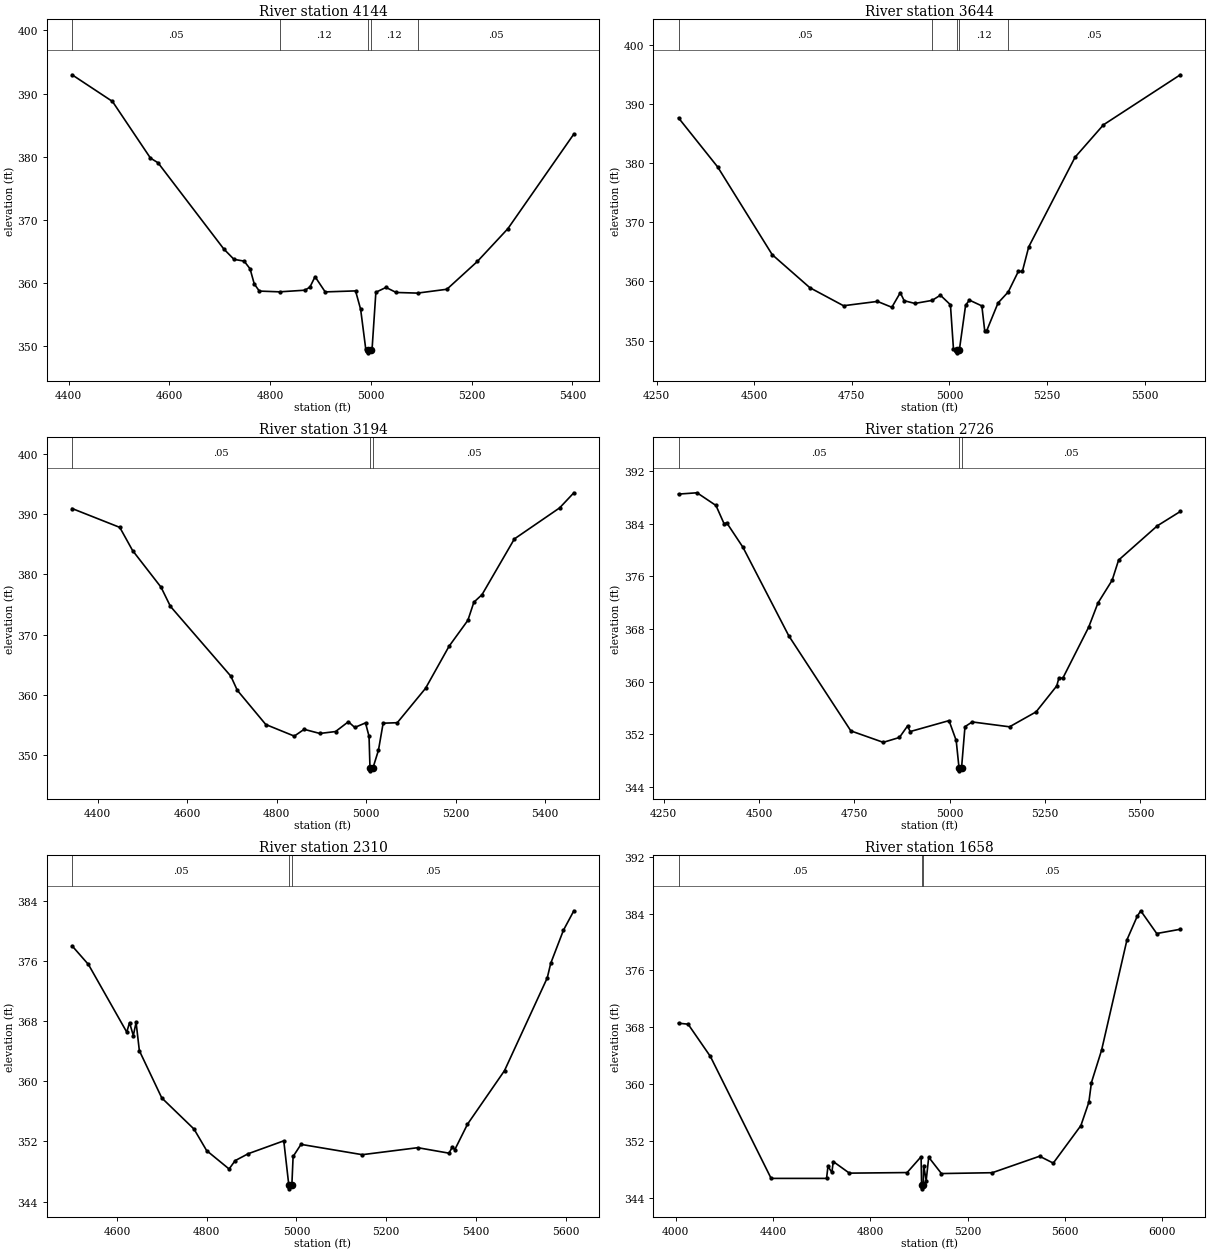
Type RM Length L Ch R = 1 ,4144    ,500,500,500
BEGIN DESCRIPTION:
McGoughlin Branch 6.0
END DESCRIPTION:
XS GIS Cut Line= 3
      2748065.73      6800622.02        2747476.        6800561.
      2747075.99        6800511.
#Sta/Elev= 30
    4407  392.98  4487.2  388.75  4562.6  379.77  4577.6  379.03  4708.3  365.35
  4728.4  363.72  4748.5  363.44  4760.3  362.22  4768.6  359.83  4778.7  358.69
  4818.9  358.57  4869.2  358.83  4879.2  359.33  4889.3  360.97  4909.4  358.56
  4969.7  358.72  4979.8  355.79  4989.8  349.58  4994.1   349.4  4995.1   348.9
  5000.7   349.4  5002.4   349.4    5010   358.5  5030.1  359.27  5050.3  358.47
  5092.7  358.37    5151  358.98  5211.5  363.39    5272  368.58    5403  383.59
#Mann= 5 ,-1 , 0
    4407     .05       0  4818.9     .12       0  4994.1     .07       0
  5000.7     .12       0  5092.7     .05       0
Bank Sta=4994.1,5000.7
XS Rating Curve= 0 ,0
Exp/Cntr=0.3,0.1

Type RM Length L Ch R = 1 ,3644    ,450,450,450
BEGIN DESCRIPTION:
McGoughlin Branch 5.0
END DESCRIPTION:
XS GIS Cut Line= 3
      2748078.24      6800405.84        2747476.        6800061.
      2746906.29      6799901.48
#Sta/Elev= 30
    4306  387.63  4406.4  379.33    4546  364.52  4642.4  358.94  4728.7  355.89
  4815.6  356.62  4852.5  355.63  4874.1  358.09  4884.1  356.74  4911.5  356.28
  4955.6  356.79  4976.9  357.67  5002.6  356.05  5010.4  348.56  5018.9  348.43
    5020  347.93  5025.5  348.43  5041.5  355.98  5051.2  356.84  5083.1  355.86
  5090.5  351.63  5095.7   351.7  5124.6  356.36  5150.7  358.22  5176.5  361.68
  5186.9  361.69  5203.2  365.84  5321.9  380.99  5394.6  386.46  5591.6  394.92
#Mann= 5 ,-1 , 0
    4306     .05       0  4955.6     .12       0  5018.9     .07       0
  5025.5     .12       0  5150.7     .05       0
Bank Sta=5018.9,5025.5
XS Rating Curve= 0 ,0
Exp/Cntr=0.3,0.1

Type RM Length L Ch R = 1 ,3194    ,468,468,468
BEGIN DESCRIPTION:
McGoughlin Branch 4.0
END DESCRIPTION:
XS GIS Cut Line= 3
      2748223.29      6800184.18        2747726.        6799761.
      2747280.88      6799616.06
#Sta/Elev= 30
  4342.9  390.97  4449.5  387.83  4478.1  383.98  4541.8  377.86  4562.6  374.69
  4697.7  363.06    4712  360.72  4775.7  355.02  4839.4  353.09  4861.4  354.22
  4896.5  353.53  4931.6  353.85  4960.2  355.48  4974.5  354.53  4998.5  355.29
  5006.4  353.06  5008.5  347.81  5009.5  347.31  5015.2  347.81  5027.4  350.73
  5037.9  355.24  5069.5  355.32  5132.6  361.04  5185.2  368.05  5227.2  372.36
  5240.6  375.38  5258.8  376.63  5331.1  385.91  5432.1  391.07    5464  393.59
#Mann= 3 ,-1 , 0
  4342.9     .05       0  5008.5     .04       0  5015.2     .05       0
Bank Sta=5008.5,5015.2
XS Rating Curve= 0 ,0
Exp/Cntr=0.3,0.1

Type RM Length L Ch R = 1 ,2726    ,416,416,416
BEGIN DESCRIPTION:
McGoughlin Branch 3.0
END DESCRIPTION:
XS GIS Cut Line= 3
      2748472.55      6799913.12        2747976.        6799411.
      2747409.93       6799186.6
#Sta/Elev= 30
  4289.4   388.5  4337.9   388.7  4387.5  386.77  4408.6  384.02  4415.8  384.13
  4458.2  380.42  4578.4  366.96    4741  352.52  4825.9  350.78  4868.3  351.52
  4889.5  353.26  4896.6  352.42  4998.3  354.08  5017.1  351.06  5024.4  346.95
  5025.5  346.45  5031.2  346.95  5040.1  353.16  5059.1  353.88  5156.9  353.14
  5226.5  355.41  5280.6  359.35    5286   360.5  5296.8  360.56  5364.3  368.28
  5388.6  371.95  5425.9  375.42  5442.7  378.47  5544.2  383.68  5604.5  385.86
#Mann= 3 ,-1 , 0
  4289.4     .05       0  5024.4     .04       0  5031.2     .05       0
Bank Sta=5024.4,5031.2
XS Rating Curve= 0 ,0
Exp/Cntr=0.3,0.1

Type RM Length L Ch R = 1 ,2310    ,652,652,652
BEGIN DESCRIPTION:
McGoughlin Branch 2.0
END DESCRIPTION:
XS GIS Cut Line= 3
        2748526.        6799511.        2748226.        6799111.
      2747625.97      6798960.99
#Sta/Elev= 30
    4500     378  4536.5  375.52  4621.9  366.53  4628.1   367.8  4636.5  366.07
  4642.7  367.82    4650  364.06    4700  357.78  4771.9  353.64    4800  350.78
    4850  348.34  4863.5  349.45  4892.7  350.37  4971.9  352.08  4983.1   346.2
  4984.2   345.7  4989.9   346.2  4992.7     350  5010.3  351.61  5146.9  350.24
  5270.6  351.17  5340.2  350.44  5347.9   351.3    5353  350.89  5381.4  354.29
  5463.9  361.41  5559.2  373.74  5566.9  375.67  5595.3  380.08  5618.5  382.66
#Mann= 3 ,-1 , 0
    4500     .05       0  4983.1     .04       0  4989.9     .05       0
Bank Sta=4983.1,4989.9
XS Rating Curve= 0 ,0
Exp/Cntr=0.3,0.1

Type RM Length L Ch R = 1 ,1658    ,497,497,497
BEGIN DESCRIPTION:
Mapping XS 5d29c49d
END DESCRIPTION:
XS GIS Cut Line= 3
      2748897.17      6799375.52       2748423.5      6798518.99
      2747386.21      6798833.53
#Sta/Elev= 30
  4011.5  368.58  4050.9  368.44  4142.4   363.9  4392.1  346.74    4620  346.74
  4625.8  348.45  4641.8  347.57  4647.5  349.11  4713.7  347.48  4951.1  347.56
  5008.6  349.79  5010.7  345.77  5011.8  345.27  5017.5  345.77  5019.3  348.55
  5029.5  346.43  5039.9  349.72  5092.2  347.42  5301.2  347.54  5495.7  349.86
  5551.9  348.89  5665.4  354.17  5698.2  357.46  5708.8  360.23  5750.5  364.78
    5855  380.33  5896.8  383.61  5911.4   384.4  5977.2   381.2  6074.2   381.8
#Mann= 3 ,-1 , 0
  4011.5     .05       0  5010.7     .04       0  5017.5     .05       0
Bank Sta=5010.7,5017.5
XS Rating Curve= 0 ,0
Exp/Cntr=0.3,0.1

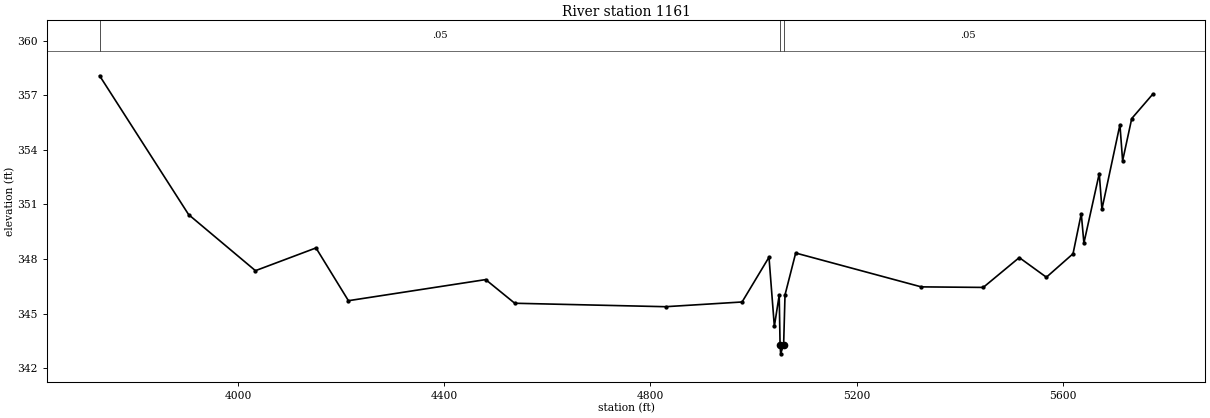
Type RM Length L Ch R = 1 ,1161    ,0,0,0
BEGIN DESCRIPTION:
McGoughlin Branch 1.0
END DESCRIPTION:
XS GIS Cut Line= 3
      2749109.68      6799345.95       2748686.6      6798151.63
      2747936.55      6798351.63
#Sta/Elev= 30
  3731.5  358.07  3904.2  350.44  4033.8  347.36  4151.3  348.61  4214.2  345.71
  4480.5  346.87  4536.9  345.57  4829.5  345.38    4978  345.64  5030.2   348.1
  5040.6   344.3    5050  346.01  5051.7  343.29  5052.8  342.79  5058.6  343.29
  5061.3  346.03    5082  348.33  5325.6  346.47  5445.9  346.44  5515.8  348.08
  5568.4     347  5620.1  348.29  5636.1  350.49  5641.2  348.88    5671   352.7
  5676.2  350.74  5711.1  355.38  5716.3   353.4    5734  355.72  5774.8  357.06
#Mann= 3 ,-1 , 0
  3731.5     .05       0  5051.7     .05       0  5058.6     .05       0
Bank Sta=5051.7,5058.6
XS Rating Curve= 0 ,0
Exp/Cntr=0.3,0.1

Chan Stop Cuts=-1
Use User Specified Reach Order=0
Composite Channel Slope=5