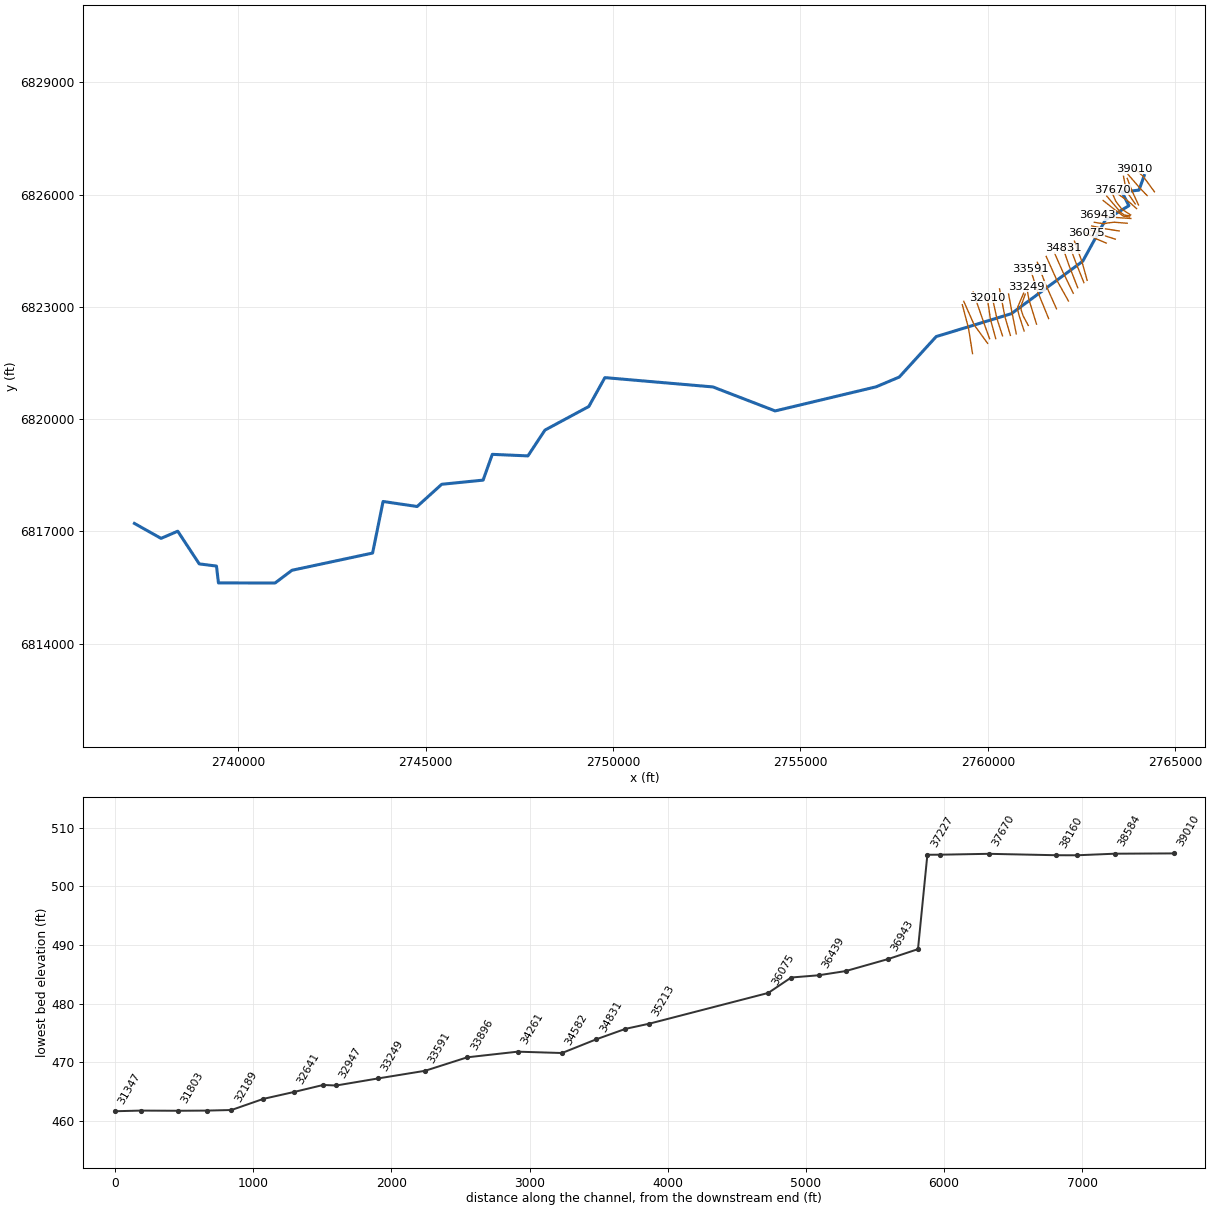
--- Mill Creek.prj (project) ---

Proj Title=Mill Creek Base Level Engineering
Current Plan=p01
Default Exp/Contr=0.3,0.1
English Units
Geom File=g01
Flow File=f01
Plan File=p01
BEGIN DESCRIPTION:
Mill Creek
END DESCRIPTION:

--- Mill Creek.p01 (plan) ---

Plan Title=Multiple Run
Short Identifier=Multiple
Geom File=g01
Flow File=f01
Subcritical Flow
K Sum by GR= 0
Std Step Tol= 0.01
Critical Tol= 0.01
Num of Std Step Trials= 20
Max Error Tol= 0.3
Flow Tol Ratio= 0.001
Split Flow NTrial= 30
Split Flow Tol= 0.02
Split Flow Ratio= 0.02
Log Output Level= 0
Friction Slope Method= 1
Unsteady Friction Slope Method= 2
Unsteady Bridges Friction Slope Method= 1
Parabolic Critical Depth
Global Vel Dist=  1 , 1 , 1
Global Log Level= 0
CheckData=True
Encroach Param= -1, 0, 0, 0
BEGIN DESCRIPTION:
Multiple Run
END DESCRIPTION:

--- Mill Creek.f01 (steady flow) ---

Flow Title=Multiple
Number of Profiles=7
Profile Names=10-year,25-year,50-year,1pct_min,100-year,1pct_plu,500-year
River Rch & RM= Mill Creek,Reach-1,39010
     517     694     839     505    1007    2010    1454
River Rch & RM= Mill Creek,Reach-1,35213
    1066    1484    1836    1127    2249    4488    3385
River Rch & RM= Mill Creek,Reach-1,27544
    1132    1581    1959    1204    2403    4795    3627
River Rch & RM= Mill Creek,Reach-1,27100
    1399    1969    2455    1516    3025    6036    4611
River Rch & RM= Mill Creek,Reach-1,22476
    1421    2002    2497    1543    3079    6143    4696
River Rch & RM= Mill Creek,Reach-1,22368
    2027    2895    3643    2269    4527    9033    7015
River Rch & RM= Mill Creek,Reach-1,14647
    2305    3308    4176    2609    5206   10386    8114
River Rch & RM= Mill Creek,Reach-1,13496
    2292    3284    4141    2583    5154   10284    8012
River Rch & RM= Mill Creek,Reach-1,12202
    2341    3353    4227    2636    5259   10493    8167
River Rch & RM= Mill Creek,Reach-1,9351
    2507    3597    4539    2833    5652   11278    8795
River Rch & RM= Mill Creek,Reach-1,6767
    2536    3638    4591    2865    5717   11406    8892
River Rch & RM= Mill Creek,Reach-1,5196
    3449    4988    6324    3955    7891   15744   12290
River Rch & RM= Mill Creek,Reach-1,2262
    3381    4893    6204    3880    7742   15447   12063
Boundary for River Rch & Prof#=Mill Creek,Reach-1,1
Up Type=0
Dn Type=3
Dn Slope=0.005
Boundary for River Rch & Prof#=Mill Creek,Reach-1,2
Up Type=0
Dn Type=3
Dn Slope=0.005
Boundary for River Rch & Prof#=Mill Creek,Reach-1,3
Up Type=0
Dn Type=3
Dn Slope=0.005
Boundary for River Rch & Prof#=Mill Creek,Reach-1,4
Up Type=0
Dn Type=3
Dn Slope=0.005
Boundary for River Rch & Prof#=Mill Creek,Reach-1,5
Up Type=0
Dn Type=3
Dn Slope=0.005
Boundary for River Rch & Prof#=Mill Creek,Reach-1,6
Up Type=0
Dn Type=3
Dn Slope=0.005
Boundary for River Rch & Prof#=Mill Creek,Reach-1,7
Up Type=0
Dn Type=3
Dn Slope=0.005

--- Mill Creek.g01 (geometry) ---

Geom Title=Existing Conditions

River Reach=Mill Creek,Reach-1
Reach XY= 30
      2764176.00      6826511.00      2764036.11      6826121.62
      2763583.46      6826067.67      2763766.72      6825704.31
      2763142.01      6825328.12      2762535.95      6824221.11
      2760628.30      6822816.83      2758623.55      6822205.54
      2757639.24      6821124.61      2757020.37      6820862.74
      2754326.06      6820218.28      2752665.49      6820859.78
      2749781.93      6821108.75      2749353.63      6820337.30
      2748181.59      6819705.39      2747728.43      6819016.40
      2746777.22      6819057.48      2746532.21      6818368.81
      2745427.47      6818257.45      2744770.56      6817663.17
      2743862.24      6817797.77      2743582.42      6816419.00
      2741431.53      6815958.63      2740979.67      6815618.69
      2739468.93      6815619.99      2739415.83      6816070.71
      2738955.64      6816129.80      2738382.50      6817003.38
      2737936.76      6816811.70      2737226.00      6817211.00

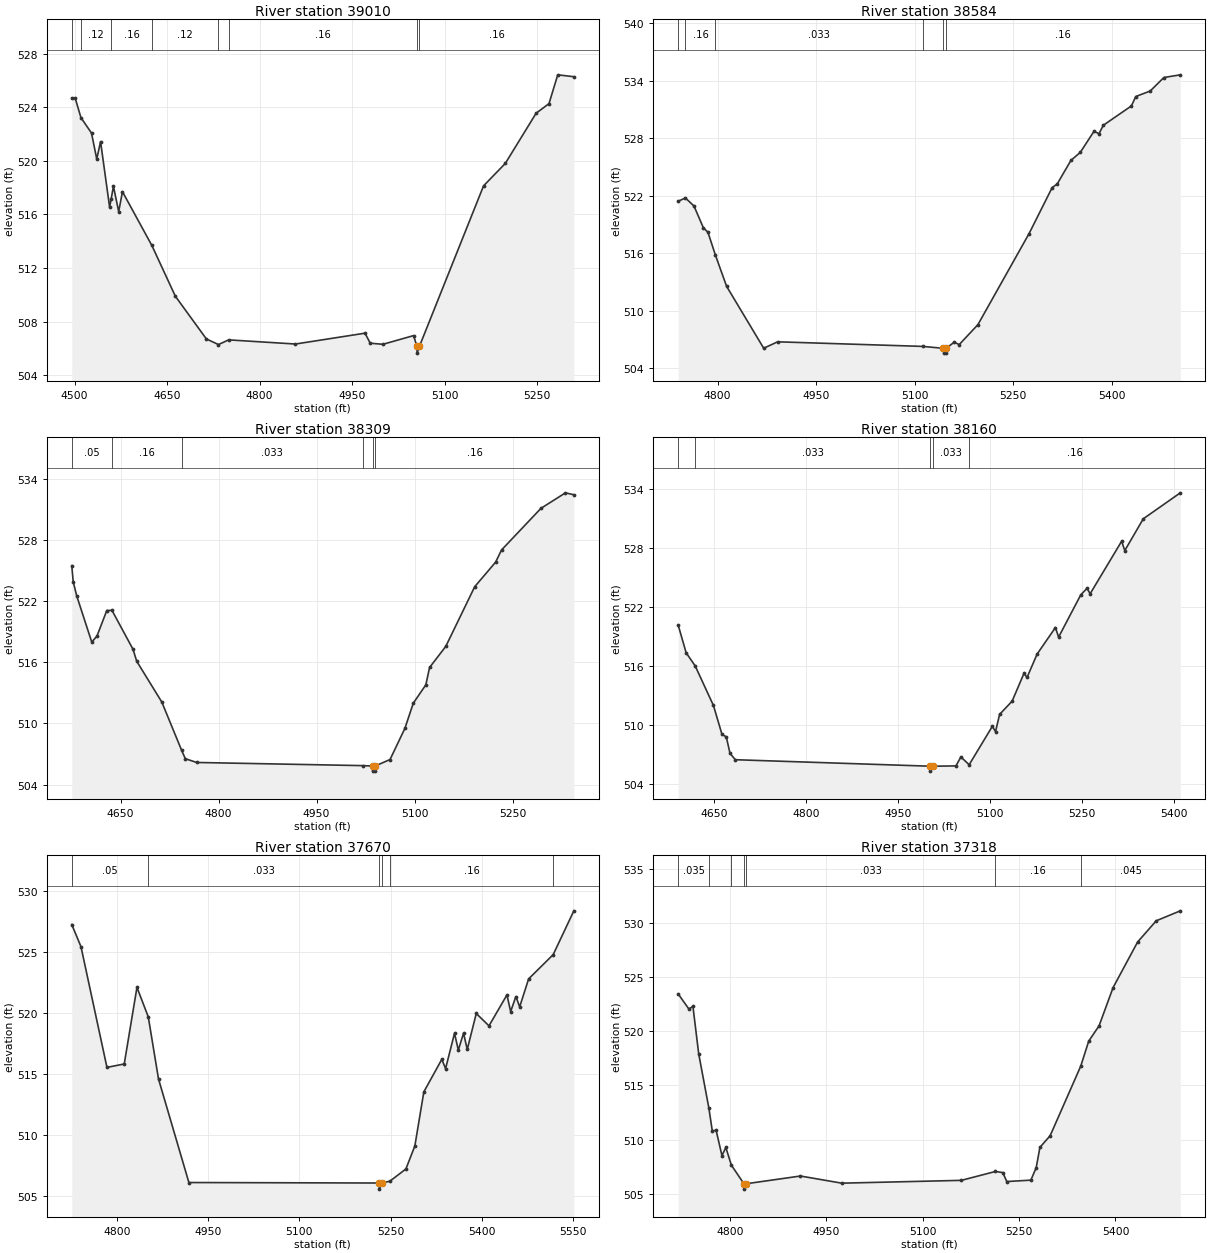
Type RM Length L Ch R = 1,39010,426,426,426
BEGIN DESCRIPTION:
Mill Creek39009.524
END DESCRIPTION:
XS GIS Cut Line= 3
      2764447.84      6826077.38      2764150.99      6826485.42
      2763921.26      6826693.11
#Sta/Elev= 30
  4495.4  524.71  4500.8  524.71  4510.3  523.23  4527.4  522.08  4535.9  520.14
  4542.1  521.44  4556.8  516.54  4559.4  517.19  4563.0  518.10  4571.5  516.21
  4577.6  517.70  4625.2  513.69  4663.4  509.89  4713.7  506.70  4733.3  506.28
  4749.9  506.63  4858.2  506.32  4971.0  507.13  4979.5  506.38  5000.0  506.30
  5049.8  506.95  5055.2  506.14  5055.5  505.64  5059.2  506.14  5163.3  518.14
  5198.5  519.81  5248.5  523.56  5269.4  524.28  5283.6  526.43  5309.7  526.29
#Mann=8,-1,0
  4495.4    0.05       0  4510.3    0.12       0  4559.4    0.16       0
  4625.2    0.12       0  4733.3   0.033       0  4749.9    0.16       0
  5055.2    0.07       0  5059.2    0.16       0
Bank Sta=5055.2,5059.2
Exp/Cntr=0.3,0.1

Type RM Length L Ch R = 1,38584,275,275,275
BEGIN DESCRIPTION:
Mill Creek38583.69
END DESCRIPTION:
XS GIS Cut Line= 3
      2764254.79      6825975.80      2764071.67      6826160.94
      2763742.61      6826542.55
#Sta/Elev= 30
  4740.1  521.43  4751.0  521.77  4764.1  520.93  4778.3  518.67  4785.4  518.18
  4796.8  515.79  4813.7  512.56  4870.2  506.10  4891.4  506.77  5112.6  506.29
  5143.9  506.09  5144.1  505.59  5147.6  505.59  5147.9  506.09  5160.2  506.73
  5167.8  506.48  5196.3  508.56  5274.2  518.06  5309.3  522.85  5317.0  523.23
  5337.9  525.69  5352.1  526.52  5373.0  528.72  5380.6  528.47  5387.2  529.35
  5430.0  531.37  5436.6  532.35  5458.5  532.92  5479.4  534.33  5504.4  534.61
#Mann=6,-1,0
  4740.1    0.05       0  4751.0    0.16       0  4796.8   0.033       0
  5112.6    0.16       0  5143.9   0.033       0  5147.9    0.16       0
Bank Sta=5143.9,5147.9
Exp/Cntr=0.3,0.1

Type RM Length L Ch R = 1,38309,149,149,149
BEGIN DESCRIPTION:
Mill Creek38308.82
END DESCRIPTION:
XS GIS Cut Line= 3
      2764022.81      6825725.93      2763843.54      6826113.78
      2763723.26      6826432.99
#Sta/Elev= 30
  4575.4  525.48  4577.6  523.91  4583.1  522.49  4606.0  517.98  4614.0  518.58
  4629.0  521.08  4636.9  521.10  4669.1  517.28  4674.8  516.10  4713.2  512.10
  4743.6  507.35  4749.2  506.54  4766.6  506.17  5020.8  505.86  5035.7  505.82
  5035.9  505.32  5039.4  505.32  5039.7  505.82  5062.5  506.46  5085.2  509.51
  5098.1  511.99  5117.3  513.79  5123.0  515.49  5147.8  517.56  5192.1  523.42
  5224.1  525.83  5233.1  527.02  5293.5  531.11  5331.0  532.63  5343.8  532.44
#Mann=6,-1,0
  4575.4    0.05       0  4636.9    0.16       0  4743.6   0.033       0
  5020.8    0.16       0  5035.7   0.033       0  5039.7    0.16       0
Bank Sta=5035.7,5039.7
Exp/Cntr=0.3,0.1

Type RM Length L Ch R = 1,38160,490,490,490
BEGIN DESCRIPTION:
Mill Creek38160.49
END DESCRIPTION:
XS GIS Cut Line= 3
      2763936.19      6825752.36      2763700.77      6826092.09
      2763622.65      6826490.27
#Sta/Elev= 30
  4591.4  520.16  4604.3  517.36  4619.0  516.03  4648.8  512.01  4662.7  509.08
  4669.8  508.81  4675.9  507.13  4684.6  506.49  5002.5  505.83  5002.8  505.33
  5006.5  505.83  5044.4  505.86  5052.5  506.77  5066.0  505.98  5103.9  509.89
  5109.0  509.34  5115.7  511.10  5136.1  512.44  5155.4  515.26  5160.5  514.86
  5176.9  517.23  5206.8  519.93  5211.9  518.95  5248.2  523.26  5258.3  523.91
  5263.4  523.36  5314.8  528.70  5319.9  527.75  5350.1  530.98  5410.5  533.62
#Mann=5,-1,0
  4591.4    0.05       0  4619.0   0.033       0  5002.5   0.033       0
  5006.5   0.033       0  5066.0    0.16       0
Bank Sta=5002.5,5006.5
Exp/Cntr=0.3,0.1

Type RM Length L Ch R = 1,37670,352,352,352
BEGIN DESCRIPTION:
Mill Creek37669.65
END DESCRIPTION:
XS GIS Cut Line= 3
      2763972.34      6825625.97      2763762.73      6825813.05
      2763319.75      6826128.54
#Sta/Elev= 30
  4726.1  527.22  4741.2  525.41  4783.9  515.53  4812.3  515.81  4833.2  522.08
  4851.8  519.66  4868.6  514.58  4918.5  506.11  5231.2  506.07  5231.4  505.57
  5235.2  506.07  5248.7  506.22  5275.0  507.22  5289.7  509.10  5304.5  513.53
  5334.0  516.19  5340.2  515.43  5354.9  518.33  5361.1  516.94  5369.7  518.33
  5375.8  517.00  5390.6  519.94  5411.5  518.93  5441.0  521.46  5447.1  520.10
  5455.7  521.33  5461.9  520.48  5476.6  522.77  5517.0  524.76  5550.9  528.34
#Mann=6,-1,0
  4726.1    0.05       0  4851.8   0.033       0  5231.2   0.033       0
  5235.2   0.033       0  5248.7    0.16       0  5517.0   0.045       0
Bank Sta=5231.2,5235.2
Exp/Cntr=0.3,0.1

Type RM Length L Ch R = 1,37318,91,91,91
BEGIN DESCRIPTION:
Mill Creek37317.97
END DESCRIPTION:
XS GIS Cut Line= 4
      2763814.75      6825456.47      2763577.21      6825613.43
      2763417.80      6825820.80      2763324.82      6826037.19
#Sta/Elev= 30
  4719.2  523.44  4735.7  522.06  4742.1  522.29  4751.1  517.90  4766.8  512.94
  4772.2  510.81  4778.2  510.85  4787.3  508.51  4793.3  509.27  4801.9  507.64
  4821.4  505.92  4821.6  505.42  4825.4  505.92  4909.5  506.63  4973.8  505.97
  5160.1  506.23  5213.1  507.05  5224.5  506.95  5230.8  506.12  5268.3  506.25
  5276.6  507.40  5282.4  509.28  5298.3  510.35  5345.9  516.77  5358.4  519.09
  5374.5  520.50  5396.3  524.03  5434.5  528.24  5463.5  530.20  5501.0  531.12
#Mann=7,-1,0
  4719.2   0.035       0  4766.8    0.05       0  4801.9   0.033       0
  4821.4   0.033       0  4825.4   0.033       0  5213.1    0.16       0
  5345.9   0.045       0
Bank Sta=4821.4,4825.4
Exp/Cntr=0.3,0.1

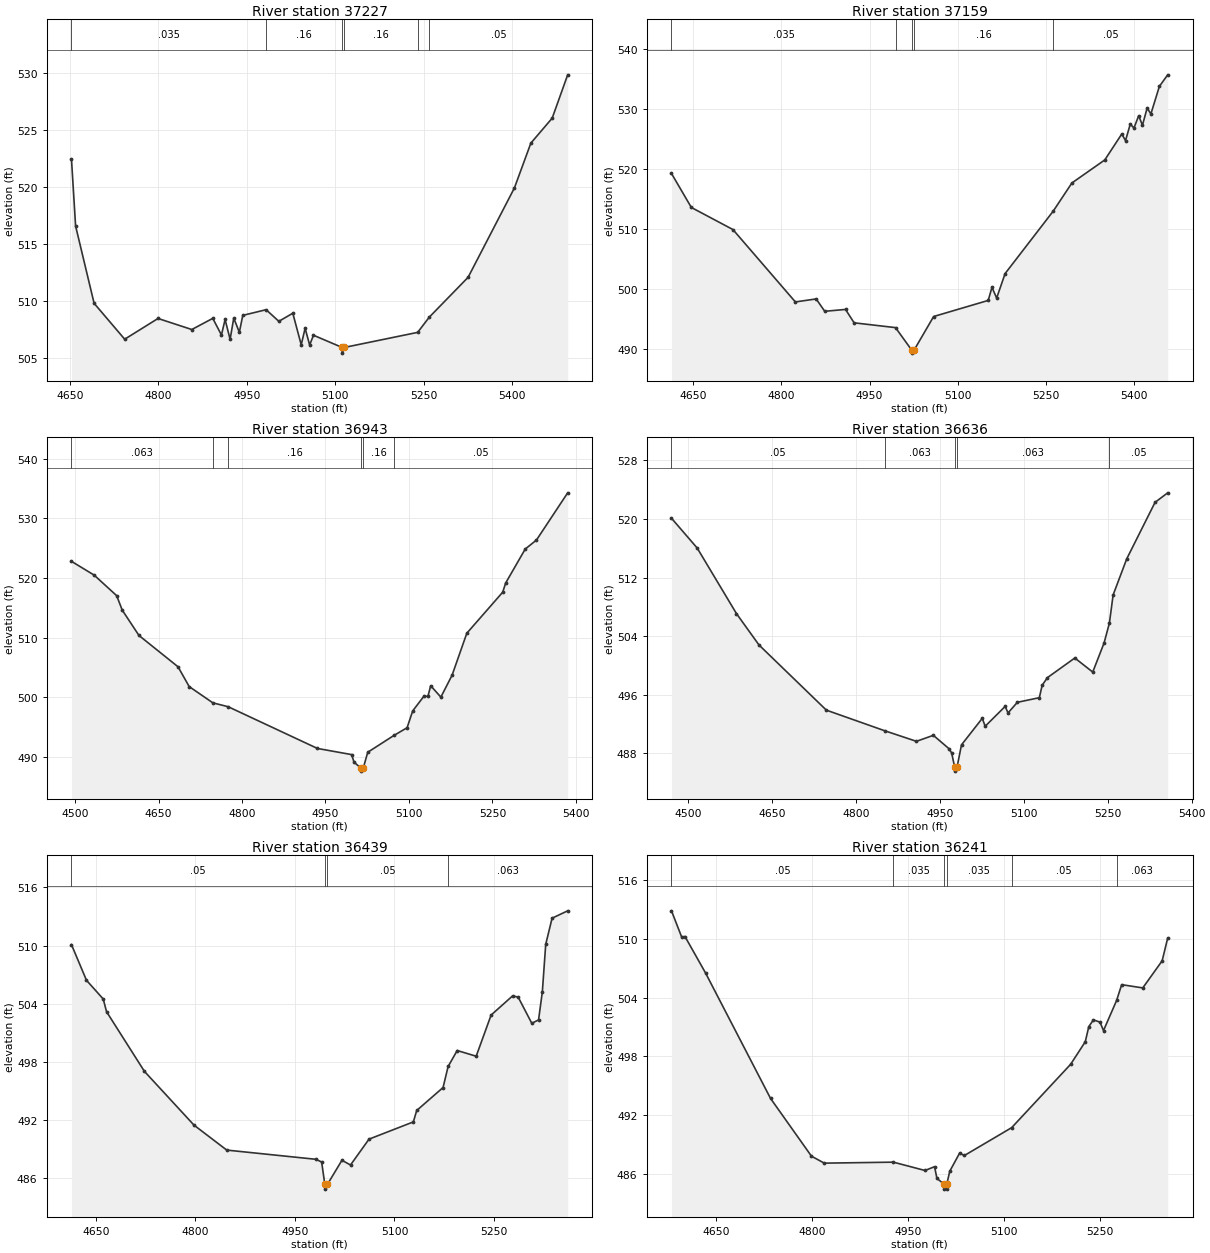
Type RM Length L Ch R = 1,37227,68,68,68
BEGIN DESCRIPTION:
Mill Creek37226.92
END DESCRIPTION:
XS GIS Cut Line= 5
      2763794.06      6825434.55      2763645.86      6825454.30
      2763538.12      6825532.19      2763494.85      6825588.28
      2763177.12      6825959.72
#Sta/Elev= 30
  4652.5  522.42  4659.5  516.56  4690.9  509.78  4742.8  506.63  4799.4  508.45
  4856.7  507.48  4892.3  508.46  4907.0  507.00  4913.2  508.36  4921.7  506.62
  4927.9  508.48  4937.4  507.24  4943.2  508.72  4982.8  509.22  5004.4  508.20
  5028.1  508.91  5042.4  506.14  5049.0  507.59  5056.7  506.12  5063.2  506.98
  5111.7  505.91  5112.0  505.41  5115.7  505.91  5240.0  507.23  5259.8  508.57
  5325.6  512.06  5404.2  519.90  5432.1  523.83  5468.3  526.02  5494.6  529.82
#Mann=6,-1,0
  4652.5   0.035       0  4982.8    0.16       0  5111.7    0.07       0
  5115.7    0.16       0  5240.0    0.16       0  5259.8    0.05       0
Bank Sta=5111.7,5115.7
Exp/Cntr=0.3,0.1

Type RM Length L Ch R = 1,37159,216,216,216
BEGIN DESCRIPTION:
Mill Creek37159.31
END DESCRIPTION:
XS GIS Cut Line= 5
      2763779.40      6825403.02      2763615.64      6825427.58
      2763465.15      6825540.79      2763436.00      6825560.86
      2763079.71      6825844.65
#Sta/Elev= 30
  4612.8  519.24  4646.6  513.58  4717.4  509.90  4823.7  497.84  4859.1  498.34
  4873.7  496.28  4909.1  496.59  4923.7  494.36  4994.2  493.56  5021.8  489.81
  5022.1  489.31  5025.8  489.81  5059.1  495.41  5152.0  498.09  5158.4  500.26
  5166.4  498.49  5180.8  502.57  5262.7  512.97  5294.5  517.66  5350.5  521.50
  5379.4  525.82  5385.8  524.72  5393.8  527.45  5400.2  526.83  5408.2  528.87
  5414.6  527.28  5422.6  530.14  5429.0  529.17  5443.4  533.75  5457.6  535.68
#Mann=5,-1,0
  4612.8   0.035       0  4994.2    0.16       0  5021.8    0.07       0
  5025.8    0.16       0  5262.7    0.05       0
Bank Sta=5021.8,5025.8
Exp/Cntr=0.3,0.1

Type RM Length L Ch R = 1,36943,307,307,307
BEGIN DESCRIPTION:
Mill Creek36942.887
END DESCRIPTION:
XS GIS Cut Line= 3
      2763817.03      6825363.00      2763309.74      6825396.57
      2762930.49      6825452.12
#Sta/Elev= 30
  4493.6  522.77  4534.4  520.46  4574.8  517.02  4584.8  514.60  4614.9  510.35
  4685.1  505.10  4705.1  501.79  4747.7  499.06  4775.2  498.41  4935.6  491.42
  4997.0  490.39  5001.4  489.11  5013.9  488.12  5014.1  487.62  5017.9  488.12
  5026.0  490.78  5072.9  493.59  5096.7  494.89  5106.8  497.71  5127.1  500.19
  5134.1  500.13  5139.1  501.93  5157.4  500.02  5177.6  503.70  5204.0  510.72
  5268.6  517.61  5273.8  519.13  5309.0  524.83  5329.2  526.34  5385.3  534.25
#Mann=6,-1,0
  4493.6   0.063       0  4747.7   0.035       0  4775.2    0.16       0
  5013.9    0.07       0  5017.9    0.16       0  5072.9    0.05       0
Bank Sta=5013.9,5017.9
Exp/Cntr=0.3,0.1

Type RM Length L Ch R = 1,36636,197,197,197
BEGIN DESCRIPTION:
Mill Creek36636.38
END DESCRIPTION:
XS GIS Cut Line= 6
      2763721.77      6825235.35      2763372.74      6825263.16
      2763234.24      6825246.78      2763196.85      6825243.27
      2763107.02      6825220.28      2762843.66      6825260.59
#Sta/Elev= 30
  4470.9  520.11  4516.8  516.04  4587.0  507.08  4627.2  502.80  4747.5  493.90
  4851.9  491.08  4908.4  489.64  4938.6  490.46  4966.3  488.65  4971.3  488.06
  4976.8  486.07  4977.1  485.57  4980.8  486.07  4988.9  489.16  5026.0  492.78
  5031.2  491.70  5066.9  494.41  5072.0  493.52  5088.7  494.97  5127.9  495.60
  5133.0  497.30  5142.4  498.34  5191.3  501.02  5223.3  499.10  5243.6  503.08
  5253.1  505.80  5259.7  509.63  5284.0  514.56  5334.6  522.28  5357.2  523.58
#Mann=5,-1,0
  4470.9    0.05       0  4851.9   0.063       0  4976.8   0.063       0
  4980.8   0.063       0  5253.1    0.05       0
Bank Sta=4976.8,4980.8
Exp/Cntr=0.3,0.1

Type RM Length L Ch R = 1,36439,198,198,198
BEGIN DESCRIPTION:
Mill Creek36439.34
END DESCRIPTION:
XS GIS Cut Line= 3
      2763508.28      6825028.48      2763127.60      6825089.28
      2762773.03      6825163.72
#Sta/Elev= 30
  4613.2  510.09  4635.8  506.41  4661.0  504.48  4666.1  503.16  4723.1  497.01
  4797.8  491.46  4847.2  488.88  4981.5  487.93  4990.2  487.65  4995.0  485.35
  4995.2  484.85  4999.0  485.35  5020.8  487.83  5033.7  487.34  5061.6  490.01
  5128.4  491.79  5133.5  492.97  5173.2  495.34  5180.8  497.51  5194.5  499.16
  5223.1  498.57  5245.6  502.82  5278.0  504.80  5286.4  504.67  5306.9  501.97
  5317.1  502.32  5322.8  505.21  5327.9  510.12  5337.5  512.82  5361.0  513.58
#Mann=4,-1,0
  4613.2    0.05       0  4995.0    0.05       0  4999.0    0.05       0
  5180.8   0.063       0
Bank Sta=4995,4999
Exp/Cntr=0.3,0.1

Type RM Length L Ch R = 1,36241,166,166,166
BEGIN DESCRIPTION:
Mill Creek36240.62
END DESCRIPTION:
XS GIS Cut Line= 3
      2763403.45      6824810.28      2763005.63      6824938.22
      2762680.56      6825088.47
#Sta/Elev= 30
  4580.3  512.85  4596.2  510.18  4601.4  510.23  4633.5  506.52  4735.2  493.72
  4799.2  487.83  4819.2  487.12  4927.3  487.22  4976.8  486.37  4991.7  486.76
  4995.4  485.56  5006.8  484.97  5007.0  484.47  5010.5  484.47  5010.8  484.97
  5015.5  486.30  5030.8  488.13  5038.4  487.90  5112.3  490.74  5204.5  497.20
  5227.4  499.50  5232.9  501.04  5240.1  501.73  5250.4  501.50  5255.9  500.64
  5276.4  503.71  5284.3  505.32  5317.3  504.99  5347.6  507.75  5356.3  510.08
#Mann=6,-1,0
  4580.3    0.05       0  4927.3   0.035       0  5006.8   0.035       0
  5010.8   0.035       0  5112.3    0.05       0  5276.4   0.063       0
Bank Sta=5006.8,5010.8
Exp/Cntr=0.3,0.1

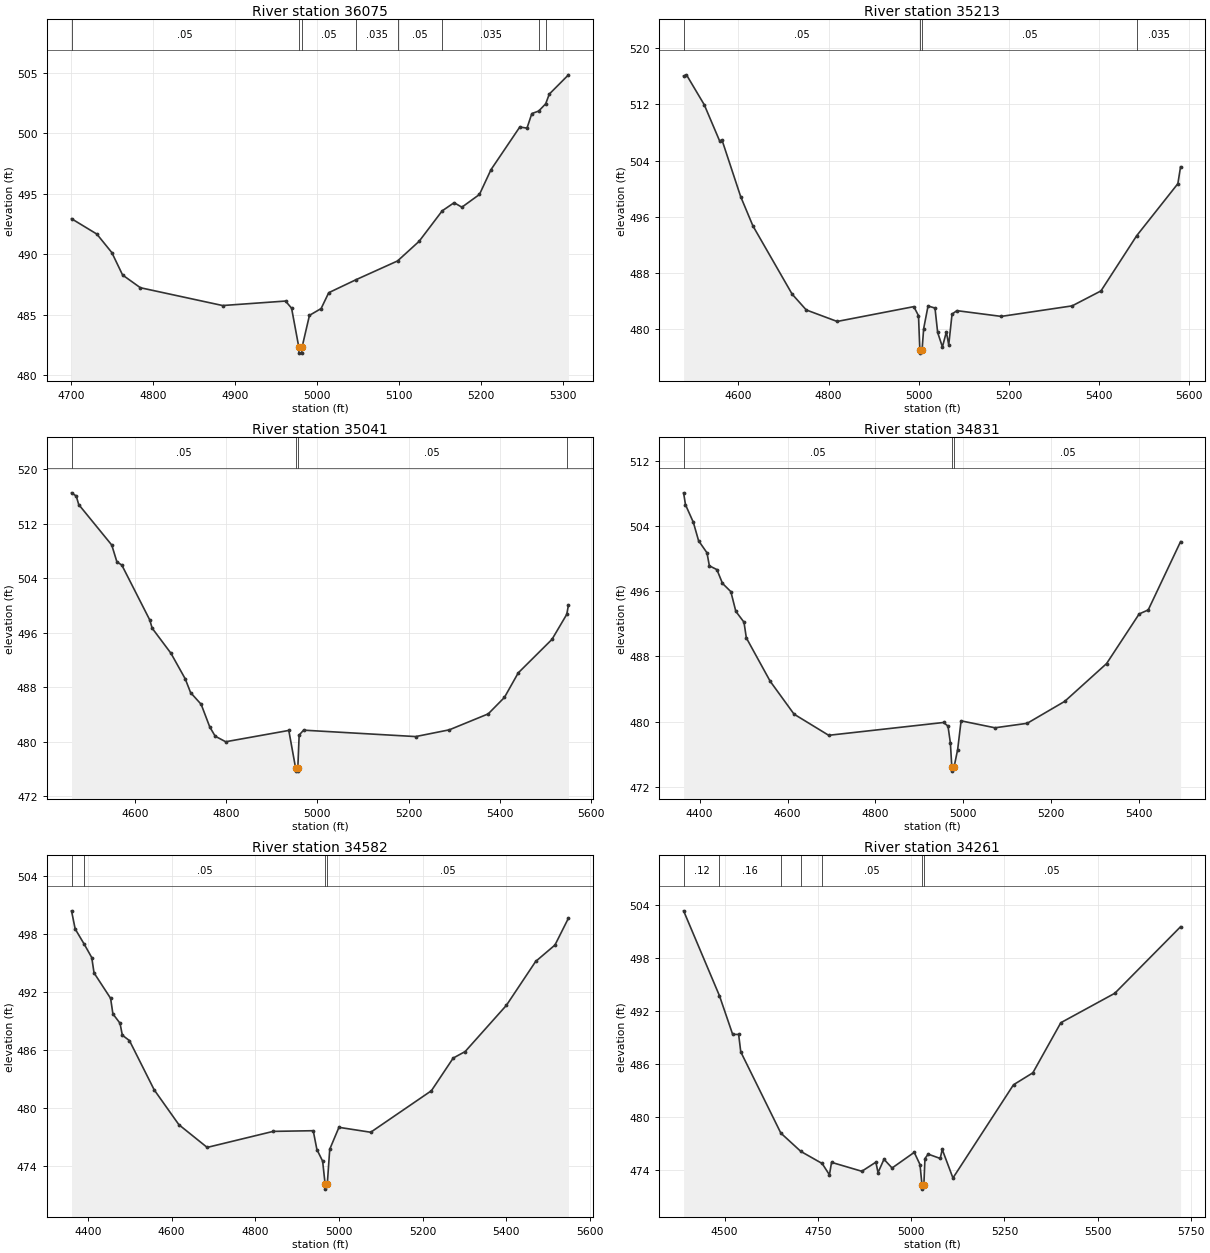
Type RM Length L Ch R = 1,36075,862,862,862
BEGIN DESCRIPTION:
Mill Creek36075.15
END DESCRIPTION:
XS GIS Cut Line= 3
      2763163.45      6824705.70      2762882.77      6824823.51
      2762625.36      6824980.87
#Sta/Elev= 30
  4700.7  492.94  4731.6  491.67  4749.9  490.14  4763.0  488.29  4784.7  487.24
  4885.0  485.77  4961.7  486.14  4969.1  485.55  4977.9  482.34  4978.2  481.84
  4981.7  481.84  4981.9  482.34  4990.9  484.96  5005.1  485.52  5014.4  486.83
  5047.9  487.91  5098.3  489.45  5124.6  491.07  5152.8  493.59  5167.3  494.26
  5176.8  493.89  5198.2  494.94  5212.3  496.99  5247.4  500.51  5256.2  500.42
  5262.1  501.62  5270.5  501.83  5279.0  502.43  5283.4  503.23  5306.8  504.82
#Mann=8,-1,0
  4700.7    0.05       0  4977.9    0.05       0  4981.9    0.05       0
  5047.9   0.035       0  5098.3    0.05       0  5152.8   0.035       0
  5270.5   0.063       0  5279.0   0.035       0
Bank Sta=4977.9,4981.9
Exp/Cntr=0.3,0.1

Type RM Length L Ch R = 1,35213,172,172,172
BEGIN DESCRIPTION:
Mill Creek35212.95
END DESCRIPTION:
XS GIS Cut Line= 3
      2762652.50      6823709.12      2762511.45      6824216.59
      2762312.87      6824756.63
#Sta/Elev= 30
  4478.3  516.05  4484.7  516.22  4524.1  511.96  4558.3  506.79  4563.5  506.93
  4604.8  498.89  4632.0  494.71  4719.0  484.99  4750.3  482.74  4818.8  481.10
  4988.8  483.21  4999.2  481.93  5002.2  477.09  5002.6  476.59  5007.2  477.09
  5010.7  480.09  5020.4  483.30  5035.8  483.01  5041.7  479.53  5052.3  477.47
  5061.0  479.61  5066.3  477.77  5073.6  482.14  5084.3  482.64  5182.8  481.82
  5340.0  483.32  5403.9  485.45  5483.2  493.32  5574.4  500.72  5580.4  503.13
#Mann=4,-1,0
  4478.3    0.05       0  5002.2    0.05       0  5007.2    0.05       0
  5483.2   0.035       0
Bank Sta=5002.2,5007.2
Exp/Cntr=0.3,0.1

Type RM Length L Ch R = 1,35041,210,210,210
BEGIN DESCRIPTION:
Mill Creek35041
END DESCRIPTION:
XS GIS Cut Line= 3
      2762565.78      6823648.60      2762362.31      6824154.49
      2762170.56      6824664.88
#Sta/Elev= 30
  4460.5  516.54  4470.9  516.07  4476.3  514.82  4548.8  508.88  4560.1  506.41
  4570.9  505.94  4632.1  497.90  4637.5  496.68  4678.7  493.00  4710.0  489.25
  4721.8  487.23  4745.0  485.51  4763.8  482.20  4775.7  480.84  4798.8  480.02
  4937.3  481.68  4952.1  476.21  4952.4  475.71  4956.7  475.71  4957.1  476.21
  4960.0  481.00  4969.7  481.72  5215.7  480.78  5289.5  481.77  5374.9  484.11
  5410.4  486.52  5440.7  490.12  5514.8  495.04  5547.2  498.71  5551.0  500.10
#Mann=4,-1,0
  4460.5    0.05       0  4952.1    0.05       0  4957.1    0.05       0
  5547.2   0.035       0
Bank Sta=4952.1,4957.1
Exp/Cntr=0.3,0.1

Type RM Length L Ch R = 1,34831,249,249,249
BEGIN DESCRIPTION:
Mill Creek34831.42
END DESCRIPTION:
XS GIS Cut Line= 3
      2762401.95      6823510.39      2762168.72      6824106.46
      2762008.56      6824570.10
#Sta/Elev= 30
  4363.6  508.04  4367.9  506.58  4385.7  504.44  4397.7  502.17  4416.8  500.69
  4422.2  499.10  4439.4  498.63  4452.0  496.95  4471.1  495.93  4482.4  493.52
  4501.0  492.19  4506.3  490.27  4560.6  484.95  4614.9  480.92  4693.7  478.33
  4954.9  479.90  4965.1  479.46  4970.5  477.40  4973.8  474.44  4974.2  473.94
  4978.9  474.44  4987.1  476.59  4994.9  480.10  5072.0  479.25  5145.3  479.80
  5230.7  482.49  5325.9  487.12  5400.0  493.20  5420.6  493.69  5494.2  502.06
#Mann=3,-1,0
  4363.6    0.05       0  4973.8    0.05       0  4978.9    0.05       0
Bank Sta=4973.8,4978.9
Exp/Cntr=0.3,0.1

Type RM Length L Ch R = 1,34582,321,321,321
BEGIN DESCRIPTION:
Mill Creek34581.5
END DESCRIPTION:
XS GIS Cut Line= 3
      2762282.45      6823363.13      2762001.54      6823940.73
      2761780.41      6824440.51
#Sta/Elev= 30
  4360.4  500.41  4369.2  498.53  4391.0  496.94  4408.8  495.57  4414.3  493.98
  4453.9  491.35  4459.4  489.74  4476.4  488.77  4482.0  487.53  4499.0  486.97
  4558.2  481.87  4617.3  478.26  4684.9  475.91  4842.8  477.57  4938.6  477.64
  4947.4  475.69  4961.1  474.49  4967.1  472.09  4967.4  471.59  4972.2  472.09
  4978.1  475.72  5000.1  477.99  5076.1  477.48  5221.3  481.78  5273.4  485.16
  5302.1  485.84  5400.8  490.63  5470.7  495.17  5516.9  496.87  5549.2  499.66
#Mann=4,-1,0
  4360.4    0.16       0  4391.0    0.05       0  4967.1    0.05       0
  4972.2    0.05       0
Bank Sta=4967.1,4972.2
Exp/Cntr=0.3,0.1

Type RM Length L Ch R = 1,34261,365,365,365
BEGIN DESCRIPTION:
Mill Creek34261.12
END DESCRIPTION:
XS GIS Cut Line= 3
      2762152.98      6823157.36      2761850.93      6823698.05
      2761559.42      6824348.15
#Sta/Elev= 30
  4390.3  503.31  4486.4  493.70  4521.8  489.33  4537.8  489.32  4543.5  487.35
  4650.9  478.16  4704.4  476.09  4761.6  474.72  4781.1  473.44  4786.8  474.85
  4867.9  473.84  4905.6  474.87  4911.3  473.69  4927.3  475.20  4949.0  474.21
  5008.4  475.98  5023.8  474.60  5029.1  472.32  5029.4  471.82  5034.2  472.32
  5037.1  475.28  5045.7  475.78  5078.0  475.29  5083.4  476.31  5112.1  473.08
  5274.4  483.63  5326.2  484.98  5401.2  490.65  5545.8  493.98  5722.1  501.51
#Mann=7,-1,0
  4390.3    0.12       0  4486.4    0.16       0  4650.9    0.05       0
  4704.4    0.16       0  4761.6    0.05       0  5029.1    0.05       0
  5034.2    0.05       0
Bank Sta=5029.1,5034.2
Exp/Cntr=0.3,0.1

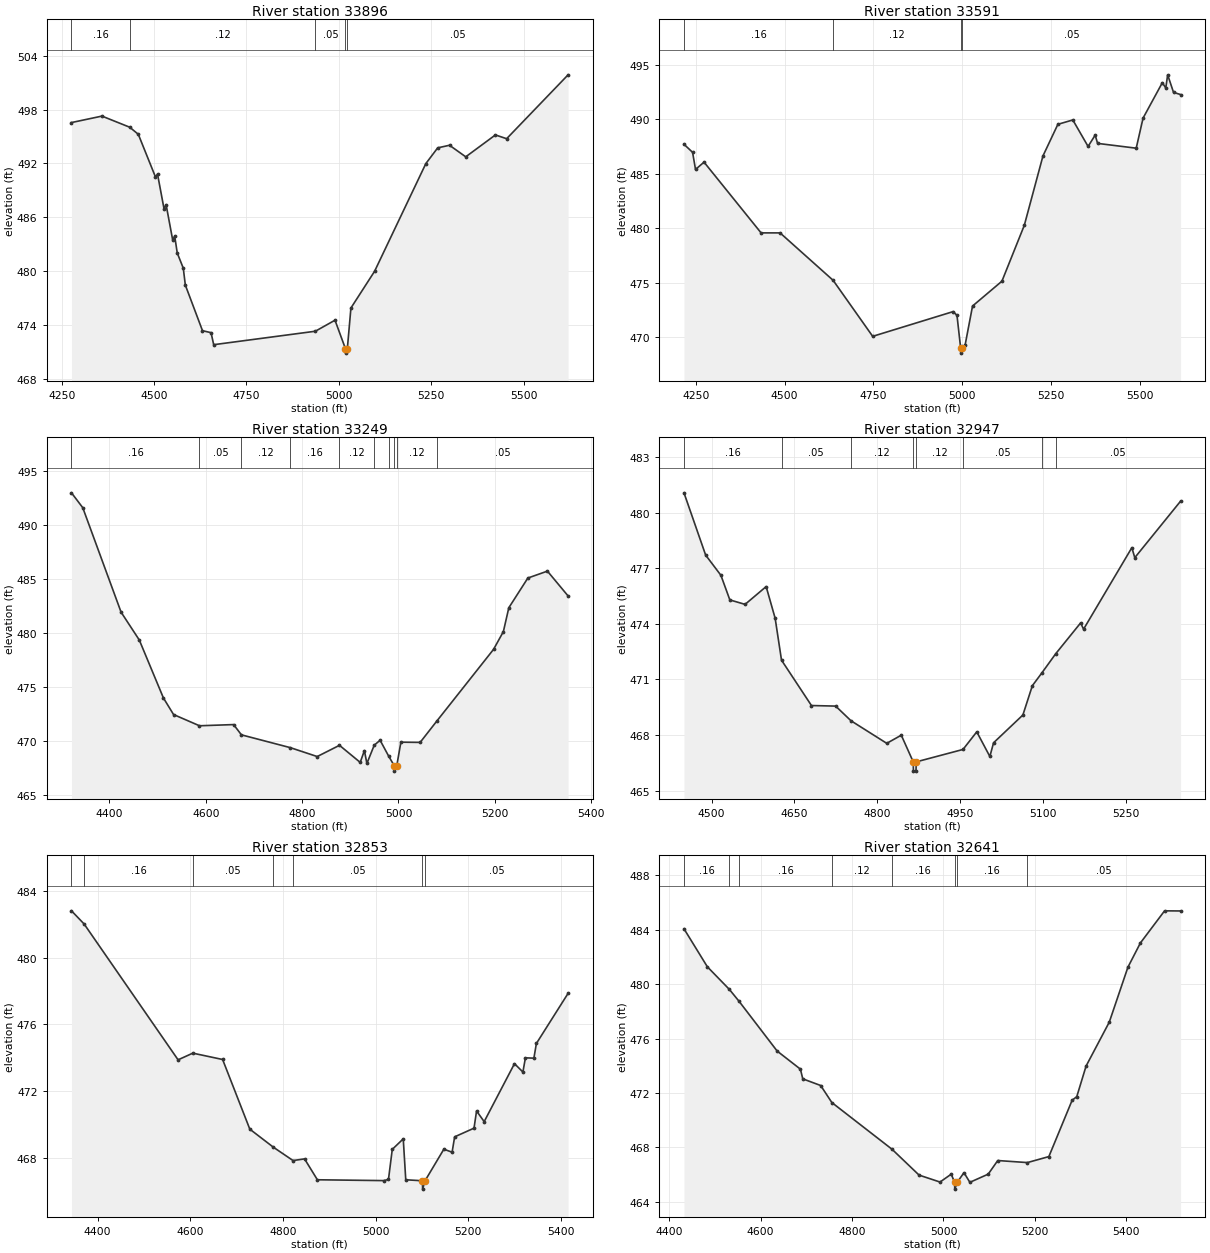
Type RM Length L Ch R = 1,33896,305,305,305
BEGIN DESCRIPTION:
Mill Creek33896.27
END DESCRIPTION:
XS GIS Cut Line= 3
      2761833.96      6822949.50      2761537.67      6823615.06
      2761322.91      6824191.74
#Sta/Elev= 30
  4276.7  496.56  4359.1  497.28  4434.3  496.04  4457.5  495.25  4504.0  490.49
  4509.5  490.82  4527.2  486.93  4532.7  487.41  4550.5  483.48  4556.0  483.90
  4562.9  482.02  4579.2  480.33  4584.8  478.44  4631.2  473.36  4654.4  473.14
  4661.5  471.80  4936.6  473.30  4989.8  474.53  5018.0  471.36  5018.4  470.86
  5023.2  471.36  5032.9  475.89  5096.9  479.98  5235.7  491.99  5267.7  493.74
  5299.7  494.03  5343.6  492.74  5423.9  495.18  5454.3  494.76  5620.6  501.88
#Mann=5,-1,0
  4276.7    0.16       0  4434.3    0.12       0  4936.6    0.05       0
  5018.0    0.05       0  5023.2    0.05       0
Bank Sta=5018,5023.2
Exp/Cntr=0.3,0.1

Type RM Length L Ch R = 1,33591,342,342,342
BEGIN DESCRIPTION:
Mill Creek33591.19
END DESCRIPTION:
XS GIS Cut Line= 3
      2761624.37      6822688.62      2761327.22      6823419.13
      2761139.56      6823999.93
#Sta/Elev= 30
  4216.7  487.72  4240.9  486.98  4249.2  485.41  4273.2  486.08  4433.9  479.59
  4487.4  479.59  4636.8  475.24  4748.3  470.10  4975.0  472.37  4985.8  472.02
  4996.0  469.06  4996.4  468.56  5001.2  469.06  5008.9  469.34  5029.6  472.88
  5112.4  475.16  5175.4  480.28  5228.0  486.65  5270.0  489.55  5312.1  489.95
  5355.1  487.52  5375.1  488.56  5381.9  487.80  5490.7  487.36  5510.0  490.12
  5564.3  493.37  5574.0  492.88  5579.3  494.09  5595.8  492.48  5615.7  492.28
#Mann=4,-1,0
  4216.7    0.16       0  4636.8    0.12       0  4996.0    0.05       0
  5001.2    0.05       0
Bank Sta=4996,5001.2
Exp/Cntr=0.3,0.1

Type RM Length L Ch R = 1,33249,302,302,302
BEGIN DESCRIPTION:
Mill Creek33249.34
END DESCRIPTION:
XS GIS Cut Line= 3
      2761301.72      6822538.69      2761097.42      6823198.76
      2761039.27      6823533.28
#Sta/Elev= 30
  4321.5  493.02  4344.9  491.64  4424.4  481.97  4462.2  479.39  4512.3  474.02
  4533.3  472.49  4587.1  471.45  4657.9  471.56  4674.1  470.61  4775.9  469.42
  4831.4  468.60  4877.6  469.64  4920.6  468.06  4929.3  469.15  4934.5  467.96
  4949.7  469.65  4961.9  470.11  4979.4  468.66  4991.2  467.75  4991.6  467.25
  4996.5  467.75  5005.0  469.93  5045.0  469.91  5079.3  471.87  5197.4  478.53
  5217.7  480.17  5229.0  482.38  5268.5  485.13  5309.1  485.77  5352.0  483.47
#Mann=10,-1,0
  4321.5    0.16       0  4587.1    0.05       0  4674.1    0.12       0
  4775.9    0.16       0  4877.6    0.12       0  4949.7    0.05       0
  4979.4    0.12       0  4991.2    0.07       0  4996.5    0.12       0
  5079.3    0.05       0
Bank Sta=4991.2,4996.5
Exp/Cntr=0.3,0.1

Type RM Length L Ch R = 1,32947,94,94,94
BEGIN DESCRIPTION:
Mill Creek32947.24
END DESCRIPTION:
XS GIS Cut Line= 5
      2761081.15      6822504.29      2760946.44      6822754.24
      2760890.95      6822919.57      2760884.96      6823014.67
      2761000.12      6823340.07
#Sta/Elev= 30
  4450.2  481.07  4489.4  477.71  4517.0  476.62  4533.2  475.29  4560.8  475.05
  4598.9  476.01  4615.2  474.30  4626.7  472.04  4680.9  469.59  4724.7  469.56
  4752.4  468.77  4817.2  467.55  4843.5  467.99  4865.1  466.55  4865.5  466.05
  4870.1  466.05  4870.6  466.55  4955.2  467.22  4980.1  468.17  5003.8  466.84
  5010.5  467.58  5063.6  469.08  5080.7  470.66  5098.4  471.37  5123.1  472.39
  5168.1  474.05  5173.4  473.71  5260.8  478.11  5266.1  477.57  5349.0  480.62
#Mann=8,-1,0
  4450.2    0.16       0  4626.7    0.05       0  4752.4    0.12       0
  4865.1    0.05       0  4870.6    0.12       0  4955.2    0.05       0
  5098.4    0.12       0  5123.1    0.05       0
Bank Sta=4865.1,4870.6
Exp/Cntr=0.3,0.1

Type RM Length L Ch R = 1,32853,212,212,212
BEGIN DESCRIPTION:
Mill Creek32852.68
END DESCRIPTION:
XS GIS Cut Line= 5
      2760970.90      6822354.40      2760841.72      6822753.84
      2760799.19      6822915.16      2760799.12      6822993.09
      2760958.28      6823367.71
#Sta/Elev= 30
  4343.7  482.80  4371.0  482.01  4573.7  473.88  4605.5  474.28  4669.8  473.90
  4728.5  469.73  4779.3  468.65  4821.8  467.85  4846.6  467.95  4874.3  466.70
  5017.7  466.65  5027.7  466.72  5035.9  468.52  5059.6  469.15  5065.0  466.70
  5101.0  466.64  5101.4  466.14  5106.6  466.64  5147.2  468.53  5165.0  468.35
  5170.5  469.27  5212.3  469.79  5217.8  470.82  5234.2  470.18  5299.6  473.65
  5317.8  473.15  5323.2  474.00  5341.5  473.98  5346.9  474.86  5415.3  477.86
#Mann=7,-1,0
  4343.7    0.12       0  4371.0    0.16       0  4605.5    0.05       0
  4779.3    0.12       0  4821.8    0.05       0  5101.0    0.05       0
  5106.6    0.05       0
Bank Sta=5101,5106.6
Exp/Cntr=0.3,0.1

Type RM Length L Ch R = 1,32641,221,221,221
BEGIN DESCRIPTION:
Mill Creek32640.53
END DESCRIPTION:
XS GIS Cut Line= 3
      2760761.47      6822277.85      2760648.52      6822840.05
      2760555.37      6823344.28
#Sta/Elev= 30
  4432.5  484.06  4483.6  481.27  4531.7  479.61  4553.1  478.73  4636.3  475.08
  4687.2  473.75  4692.3  473.04  4731.5  472.55  4755.9  471.30  4887.5  467.87
  4946.7  465.97  4992.5  465.46  5017.1  466.04  5024.3  465.44  5024.8  464.94
  5030.1  465.44  5044.9  466.15  5057.8  465.44  5097.9  466.04  5118.8  467.04
  5183.6  466.89  5230.6  467.33  5281.5  471.47  5291.6  471.73  5312.0  473.98
  5362.8  477.21  5403.5  481.24  5430.8  483.02  5483.7  485.38  5518.7  485.37
#Mann=8,-1,0
  4432.5    0.16       0  4531.7    0.12       0  4553.1    0.16       0
  4755.9    0.12       0  4887.5    0.16       0  5024.3    0.07       0
  5030.1    0.16       0  5183.6    0.05       0
Bank Sta=5024.3,5030.1
Exp/Cntr=0.3,0.1

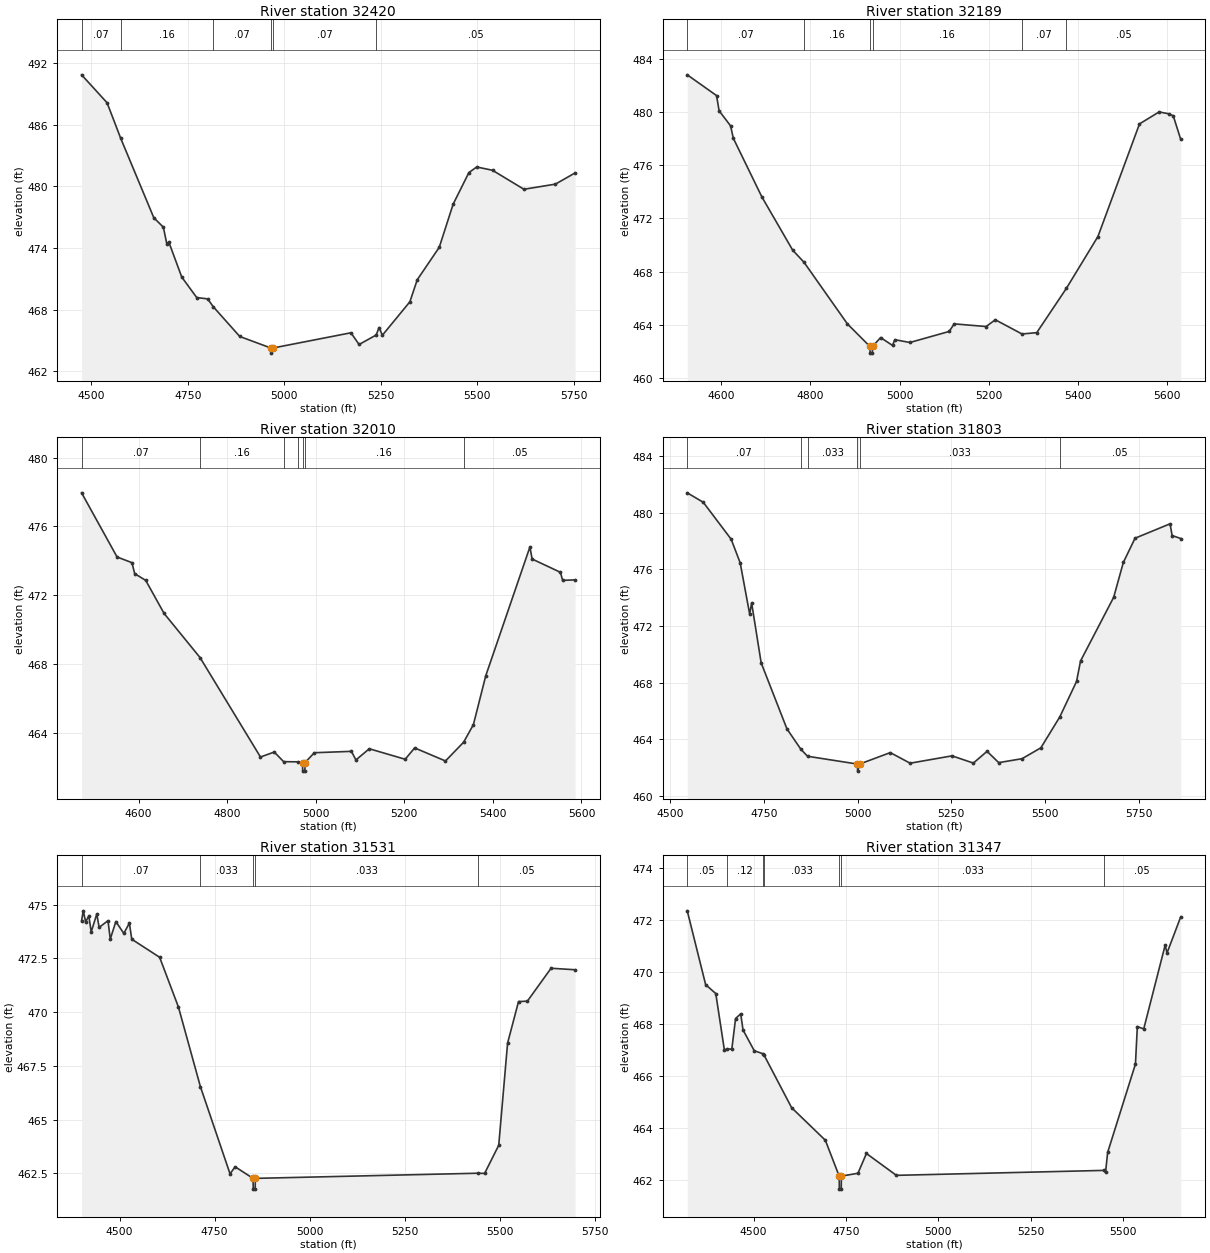
Type RM Length L Ch R = 1,32420,231,231,231
BEGIN DESCRIPTION:
Mill Creek32419.87
END DESCRIPTION:
XS GIS Cut Line= 3
      2760603.48      6822237.65      2760455.81      6822746.67
      2760314.41      6823480.98
#Sta/Elev= 30
  4475.1  490.86  4541.1  488.14  4576.4  484.68  4662.1  476.95  4686.8  476.03
  4695.7  474.42  4700.9  474.59  4734.5  471.17  4773.2  469.18  4801.4  469.05
  4816.4  468.27  4884.7  465.39  4965.1  464.27  4965.6  463.77  4970.9  464.27
  5172.5  465.75  5193.6  464.61  5237.8  465.53  5245.5  466.26  5253.9  465.51
  5325.2  468.77  5344.2  470.91  5401.2  474.07  5437.2  478.27  5478.0  481.35
  5498.3  481.89  5539.1  481.57  5620.5  479.72  5702.0  480.22  5752.9  481.31
#Mann=6,-1,0
  4475.1    0.07       0  4576.4    0.16       0  4816.4    0.07       0
  4965.1    0.07       0  4970.9    0.07       0  5237.8    0.05       0
Bank Sta=4965.1,4970.9
Exp/Cntr=0.3,0.1

Type RM Length L Ch R = 1,32189,179,179,179
BEGIN DESCRIPTION:
Mill Creek32188.58
END DESCRIPTION:
XS GIS Cut Line= 3
      2760393.16      6822228.54      2760243.75      6822688.98
      2760111.57      6823297.41
#Sta/Elev= 30
  4523.9  482.80  4589.6  481.24  4595.3  480.10  4621.1  478.96  4627.2  478.03
  4691.2  473.62  4760.4  469.61  4785.6  468.71  4883.0  464.07  4933.6  462.37
  4934.1  461.87  4938.9  461.87  4939.4  462.37  4957.5  463.04  4984.2  462.45
  4989.4  462.88  5023.2  462.67  5111.2  463.50  5122.6  464.07  5194.2  463.87
  5214.7  464.38  5274.6  463.31  5307.7  463.41  5374.3  466.75  5444.9  470.64
  5538.1  479.11  5582.1  480.01  5603.6  479.87  5613.8  479.72  5630.6  477.94
#Mann=6,-1,0
  4523.9    0.07       0  4785.6    0.16       0  4933.6    0.07       0
  4939.4    0.16       0  5274.6    0.07       0  5374.3    0.05       0
Bank Sta=4933.6,4939.4
Exp/Cntr=0.3,0.1

Type RM Length L Ch R = 1,32010,207,207,207
BEGIN DESCRIPTION:
Mill Creek32009.96
END DESCRIPTION:
XS GIS Cut Line= 3
      2760212.79      6822151.31      2760073.93      6822660.59
      2759986.28      6823240.34
#Sta/Elev= 30
  4471.3  477.95  4551.4  474.22  4585.0  473.89  4591.2  473.25  4616.1  472.86
  4657.5  470.94  4738.8  468.37  4875.2  462.59  4906.3  462.88  4927.5  462.32
  4959.9  462.31  4970.1  462.27  4970.5  461.77  4975.4  461.77  4975.9  462.27
  4996.8  462.84  5080.5  462.92  5090.7  462.42  5120.9  463.07  5201.9  462.46
  5223.3  463.12  5292.9  462.36  5333.8  463.45  5355.9  464.47  5383.9  467.32
  5483.5  474.80  5488.6  474.10  5552.4  473.33  5557.4  472.86  5585.5  472.89
#Mann=7,-1,0
  4471.3    0.07       0  4738.8    0.16       0  4927.5   0.033       0
  4959.9    0.16       0  4970.1    0.07       0  4975.9    0.16       0
  5333.8    0.05       0
Bank Sta=4970.1,4975.9
Exp/Cntr=0.3,0.1

Type RM Length L Ch R = 1,31803,272,272,272
BEGIN DESCRIPTION:
Mill Creek31802.99
END DESCRIPTION:
XS GIS Cut Line= 3
      2760048.16      6822150.77      2759890.51      6822586.84
      2759612.12      6823393.99
#Sta/Elev= 30
  4545.0  481.42  4587.8  480.75  4662.2  478.14  4686.3  476.47  4711.6  472.85
  4716.9  473.63  4742.3  469.40  4811.1  464.73  4848.5  463.28  4866.3  462.79
  4999.3  462.24  4999.8  461.74  5005.1  462.24  5087.1  463.05  5140.0  462.30
  5251.8  462.82  5308.9  462.31  5345.4  463.14  5376.6  462.34  5439.0  462.62
  5489.1  463.39  5539.5  465.57  5584.3  468.08  5595.0  469.53  5683.4  474.03
  5709.3  476.50  5740.5  478.21  5834.1  479.23  5839.4  478.40  5862.5  478.19
#Mann=6,-1,0
  4545.0    0.07       0  4848.5    0.16       0  4866.3   0.033       0
  4999.3   0.033       0  5005.1   0.033       0  5539.5    0.05       0
Bank Sta=4999.3,5005.1
Exp/Cntr=0.3,0.1

Type RM Length L Ch R = 1,31531,184,184,184
BEGIN DESCRIPTION:
Mill Creek31531.12
END DESCRIPTION:
XS GIS Cut Line= 3
      2759995.36      6822024.84      2759639.44      6822514.91
      2759359.39      6823148.83
#Sta/Elev= 30
  4399.8  474.25  4404.2  474.71  4410.4  474.20  4418.9  474.47  4425.1  473.73
  4439.8  474.56  4446.0  473.94  4469.2  474.25  4475.3  473.40  4490.0  474.21
  4510.9  473.66  4525.6  474.14  4531.8  473.39  4605.2  472.55  4654.6  470.24
  4712.4  466.54  4790.5  462.48  4803.8  462.81  4851.1  462.27  4851.6  461.77
  4856.6  461.77  4857.1  462.27  5443.6  462.51  5460.4  462.50  5497.6  463.81
  5520.9  468.56  5549.7  470.49  5573.0  470.51  5635.3  472.04  5698.5  471.97
#Mann=5,-1,0
  4399.8    0.07       0  4712.4   0.033       0  4851.1   0.033       0
  4857.1   0.033       0  5443.6    0.05       0
Bank Sta=4851.1,4857.1
Exp/Cntr=0.3,0.1

Type RM Length L Ch R = 1,31347,255,255,255
BEGIN DESCRIPTION:
Mill Creek31347.3
END DESCRIPTION:
XS GIS Cut Line= 3
      2759593.37      6821751.81      2759485.57      6822434.95
      2759320.45      6823057.84
#Sta/Elev= 30
  4320.2  472.36  4370.0  469.52  4397.4  469.18  4420.6  467.02  4427.5  467.04
  4440.9  467.05  4451.0  468.22  4464.9  468.40  4471.2  467.78  4501.6  466.98
  4526.3  466.86  4527.5  466.83  4602.8  464.79  4694.0  463.54  4731.5  462.16
  4732.0  461.66  4737.0  461.66  4737.5  462.16  4782.3  462.27  4805.3  463.03
  4886.3  462.19  5447.1  462.38  5452.6  462.30  5458.3  463.07  5533.6  466.47
  5538.7  467.91  5556.0  467.82  5614.0  471.04  5619.1  470.74  5656.2  472.13
#Mann=7,-1,0
  4320.2    0.05       0  4427.5    0.12       0  4526.3    0.16       0
  4527.5   0.033       0  4731.5   0.033       0  4737.5   0.033       0
  5447.1    0.05       0
Bank Sta=4731.5,4737.5
Exp/Cntr=0.3,0.1