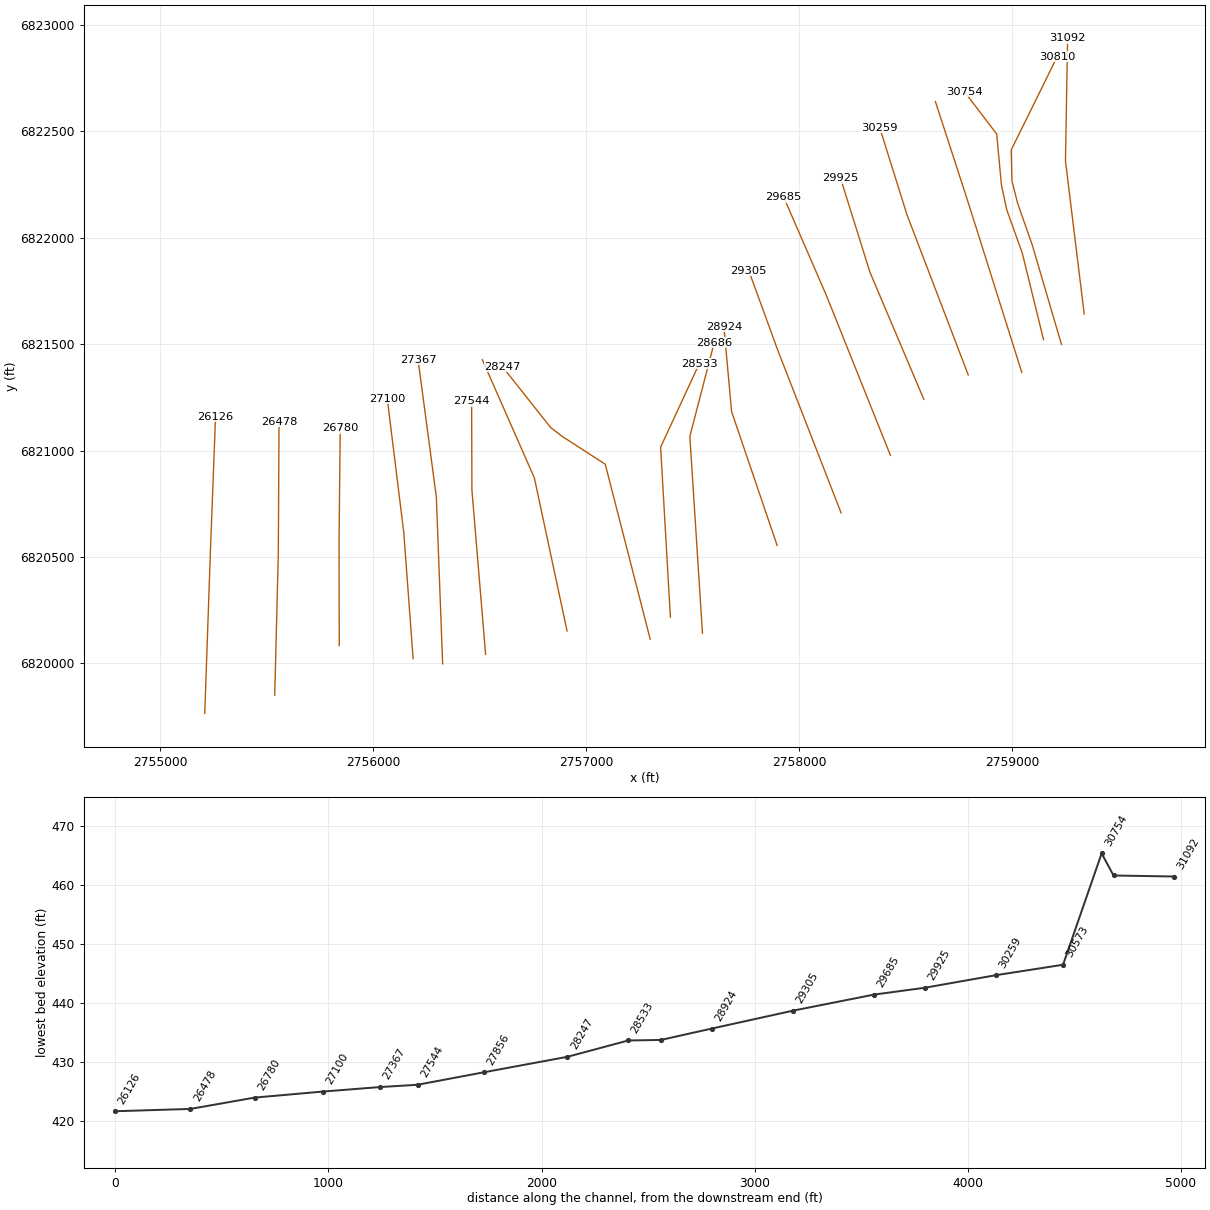
HEC-RAS study Mill Creek.prj: Mill Creek Base Level Engineering

--- Mill Creek.g01 (geometry) --- (continued)

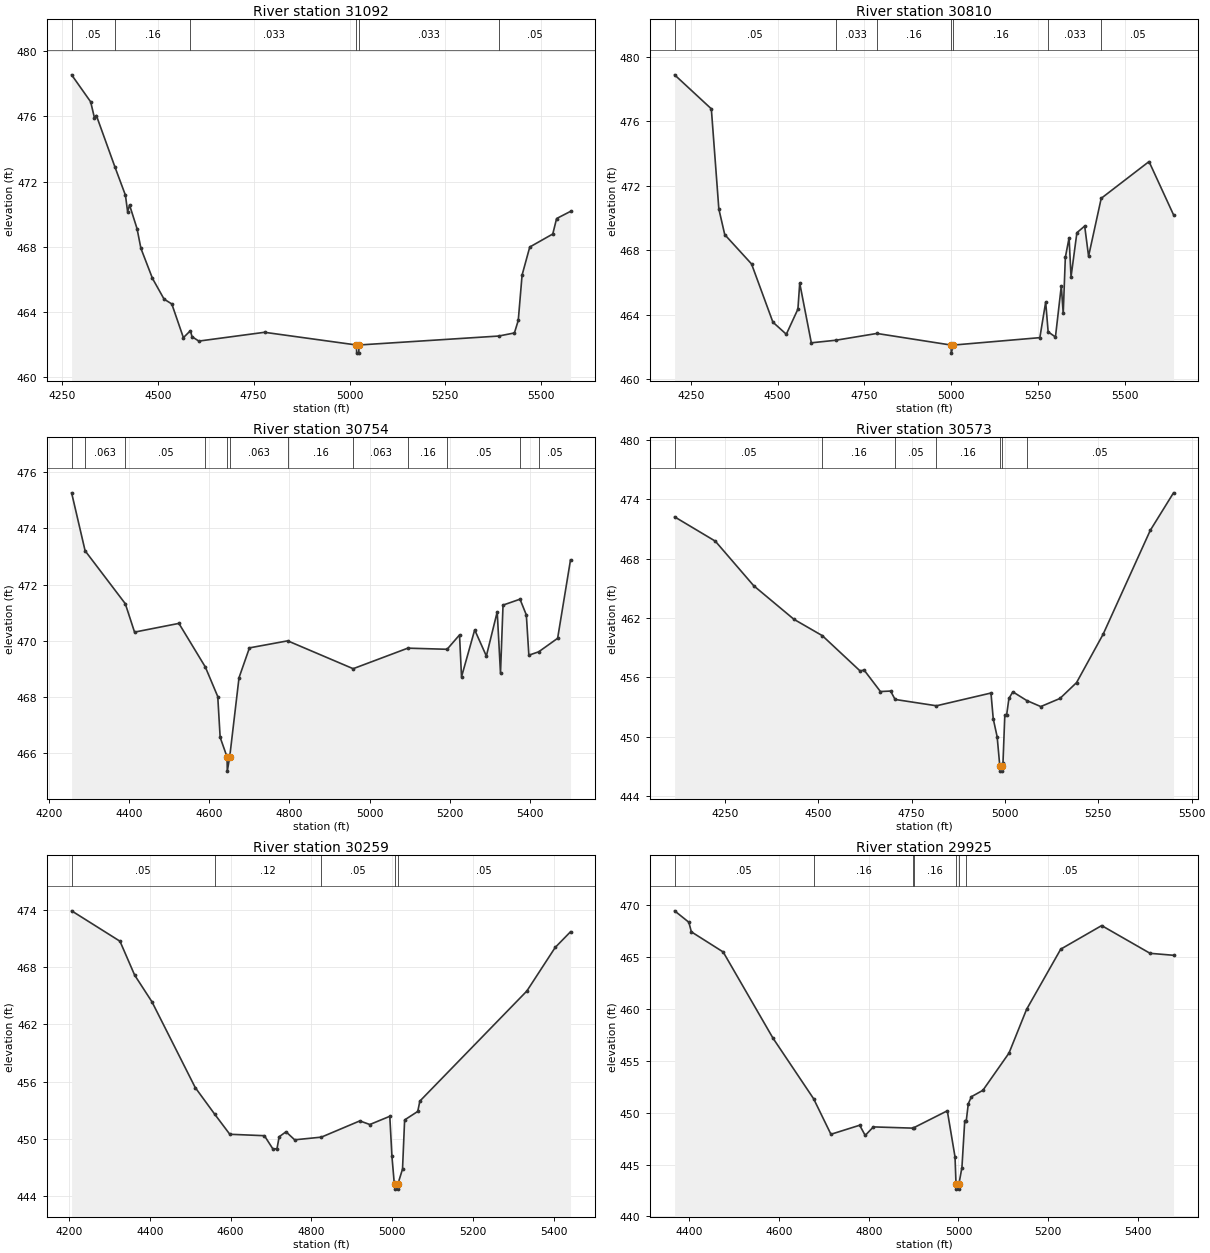
Type RM Length L Ch R = 1,31092,282,282,282
BEGIN DESCRIPTION:
Mill Creek31091.67
END DESCRIPTION:
XS GIS Cut Line= 3
      2759338.81      6821641.67      2759250.70      6822361.68
      2759260.86      6822937.30
#Sta/Elev= 30
  4275.3  478.56  4325.0  476.90  4334.8  475.92  4339.9  476.06  4388.4  472.89
  4415.7  471.16  4421.3  470.15  4426.4  470.56  4445.9  469.11  4456.0  467.90
  4486.2  466.05  4516.4  464.78  4536.6  464.48  4566.8  462.41  4585.2  462.84
  4589.3  462.47  4607.1  462.20  4778.4  462.74  5018.2  461.96  5018.7  461.46
  5024.2  461.46  5024.7  461.96  5389.1  462.51  5430.1  462.70  5440.1  463.47
  5450.1  466.26  5470.1  467.98  5530.1  468.78  5540.1  469.73  5576.4  470.17
#Mann=6,-1,0
  4275.3    0.05       0  4388.4    0.16       0  4585.2   0.033       0
  5018.2   0.033       0  5024.7   0.033       0  5389.1    0.05       0
Bank Sta=5018.2,5024.7
Exp/Cntr=0.3,0.1

Type RM Length L Ch R = 1,30810,56,56,56
BEGIN DESCRIPTION:
Mill Creek30810.3
END DESCRIPTION:
XS GIS Cut Line= 6
      2759232.05      6821498.75      2759094.98      6821965.63
      2759026.26      6822161.38      2758999.43      6822267.24
      2758995.89      6822412.62      2759211.62      6822850.37
#Sta/Elev= 30
  4203.2  478.89  4309.0  476.78  4330.6  470.57  4347.6  468.98  4424.8  467.16
  4486.3  463.55  4524.9  462.80  4558.3  464.36  4563.5  465.97  4596.9  462.27
  4667.7  462.43  4785.7  462.85  4999.4  462.13  4999.9  461.63  5005.9  462.13
  5255.0  462.59  5271.8  464.80  5278.9  462.95  5299.9  462.63  5316.8  465.80
  5322.3  464.09  5328.4  467.57  5339.2  468.78  5344.8  466.36  5361.7  469.10
  5384.1  469.51  5395.3  467.64  5431.7  471.23  5569.4  473.51  5639.9  470.21
#Mann=7,-1,0
  4203.2    0.05       0  4667.7   0.033       0  4785.7    0.16       0
  4999.4    0.07       0  5005.9    0.16       0  5278.9   0.033       0
  5431.7    0.05       0
Bank Sta=4999.4,5005.9
Exp/Cntr=0.3,0.1

Type RM Length L Ch R = 1,30754,181,181,181
BEGIN DESCRIPTION:
Mapping XS 6962a45d
END DESCRIPTION:
XS GIS Cut Line= 6
      2759147.88      6821520.96      2759047.93      6821927.64
      2758974.98      6822131.52      2758950.09      6822247.81
      2758927.71      6822487.55      2758776.37      6822686.65
#Sta/Elev= 30
  4256.4  475.26  4290.1  473.20  4390.4  471.32  4413.5  470.31  4524.2  470.62
  4590.2  469.07  4621.2  468.02  4627.2  466.57  4644.5  465.87  4645.0  465.37
  4651.0  465.87  4674.3  468.69  4700.3  469.75  4795.8  470.00  4959.2  469.01
  5095.6  469.74  5193.7  469.70  5224.7  470.21  5229.7  468.72  5262.6  470.39
  5291.7  469.46  5318.8  471.03  5327.0  468.85  5333.3  471.27  5375.7  471.48
  5391.5  470.92  5397.8  469.49  5422.3  469.61  5469.6  470.09  5501.8  472.88
#Mann=12,-1,0
  4256.4   0.035       0  4290.1   0.063       0  4390.4    0.05       0
  4590.2   0.063       0  4644.5   0.063       0  4651.0   0.063       0
  4795.8    0.16       0  4959.2   0.063       0  5095.6    0.16       0
  5193.7    0.05       0  5375.7   0.063       0  5422.3    0.05       0
Bank Sta=4644.5,4651
Exp/Cntr=0.3,0.1

Type RM Length L Ch R = 1,30573,314,314,314
BEGIN DESCRIPTION:
Mill Creek30572.52
END DESCRIPTION:
XS GIS Cut Line= 4
      2759045.64      6821366.92      2758830.53      6822050.11
      2758778.00      6822215.08      2758639.77      6822640.29
#Sta/Elev= 30
  4114.9  472.24  4224.0  469.78  4326.9  465.27  4434.5  461.88  4510.7  460.22
  4611.9  456.65  4622.4  456.75  4666.3  454.57  4693.5  454.62  4705.6  453.77
  4816.4  453.13  4962.4  454.42  4968.5  451.81  4979.0  449.99  4986.1  447.02
  4986.6  446.52  4992.1  446.52  4992.6  447.02  4994.6  447.37  4999.5  452.19
  5004.3  452.19  5010.5  453.87  5021.0  454.54  5058.3  453.66  5095.8  453.05
  5147.2  453.87  5191.6  455.47  5262.9  460.37  5389.1  470.87  5451.4  474.67
#Mann=7,-1,0
  4114.9    0.05       0  4510.7    0.16       0  4705.6    0.05       0
  4816.4    0.16       0  4986.1    0.07       0  4992.6    0.16       0
  5058.3    0.05       0
Bank Sta=4986.1,4992.6
Exp/Cntr=0.3,0.1

Type RM Length L Ch R = 1,30259,334,334,334
BEGIN DESCRIPTION:
Mill Creek30258.74
END DESCRIPTION:
XS GIS Cut Line= 3
      2758794.15      6821355.20      2758506.82      6822106.78
      2758378.23      6822517.59
#Sta/Elev= 30
  4206.6  473.88  4326.3  470.70  4362.7  467.15  4405.5  464.36  4512.6  455.39
  4560.5  452.62  4598.2  450.50  4683.9  450.35  4705.3  448.94  4715.1  449.00
  4720.4  450.24  4737.4  450.76  4758.8  449.92  4824.9  450.20  4920.1  451.90
  4944.8  451.52  4994.3  452.38  4999.6  448.19  5005.0  445.53  5007.6  445.26
  5008.1  444.76  5013.6  444.76  5014.1  445.26  5025.8  446.86  5031.0  452.00
  5063.5  452.89  5068.7  453.97  5333.6  465.49  5403.8  470.05  5441.7  471.69
#Mann=5,-1,0
  4206.6    0.05       0  4560.5    0.12       0  4824.9    0.05       0
  5007.6    0.05       0  5014.1    0.05       0
Bank Sta=5007.6,5014.1
Exp/Cntr=0.3,0.1

Type RM Length L Ch R = 1,29925,240,240,240
BEGIN DESCRIPTION:
Mill Creek29924.76
END DESCRIPTION:
XS GIS Cut Line= 3
      2758585.25      6821241.03      2758332.57      6821837.57
      2758193.87      6822281.04
#Sta/Elev= 30
  4367.0  469.42  4398.8  468.32  4404.3  467.40  4475.3  465.46  4586.3  457.17
  4677.0  451.33  4715.6  447.91  4779.7  448.78  4792.0  447.80  4810.3  448.62
  4899.0  448.50  4899.8  448.53  4975.1  450.17  4992.3  445.73  4994.5  443.13
  4995.0  442.63  5000.5  442.63  5001.0  443.13  5007.7  444.71  5014.0  449.22
  5017.4  449.22  5021.9  450.85  5028.9  451.53  5054.4  452.14  5112.7  455.73
  5151.8  459.93  5228.0  465.73  5319.3  468.00  5427.2  465.33  5479.5  465.14
#Mann=7,-1,0
  4367.0    0.05       0  4677.0    0.16       0  4899.0    0.05       0
  4899.8    0.16       0  4994.5    0.07       0  5001.0    0.16       0
  5017.4    0.05       0
Bank Sta=4994.5,5001
Exp/Cntr=0.3,0.1

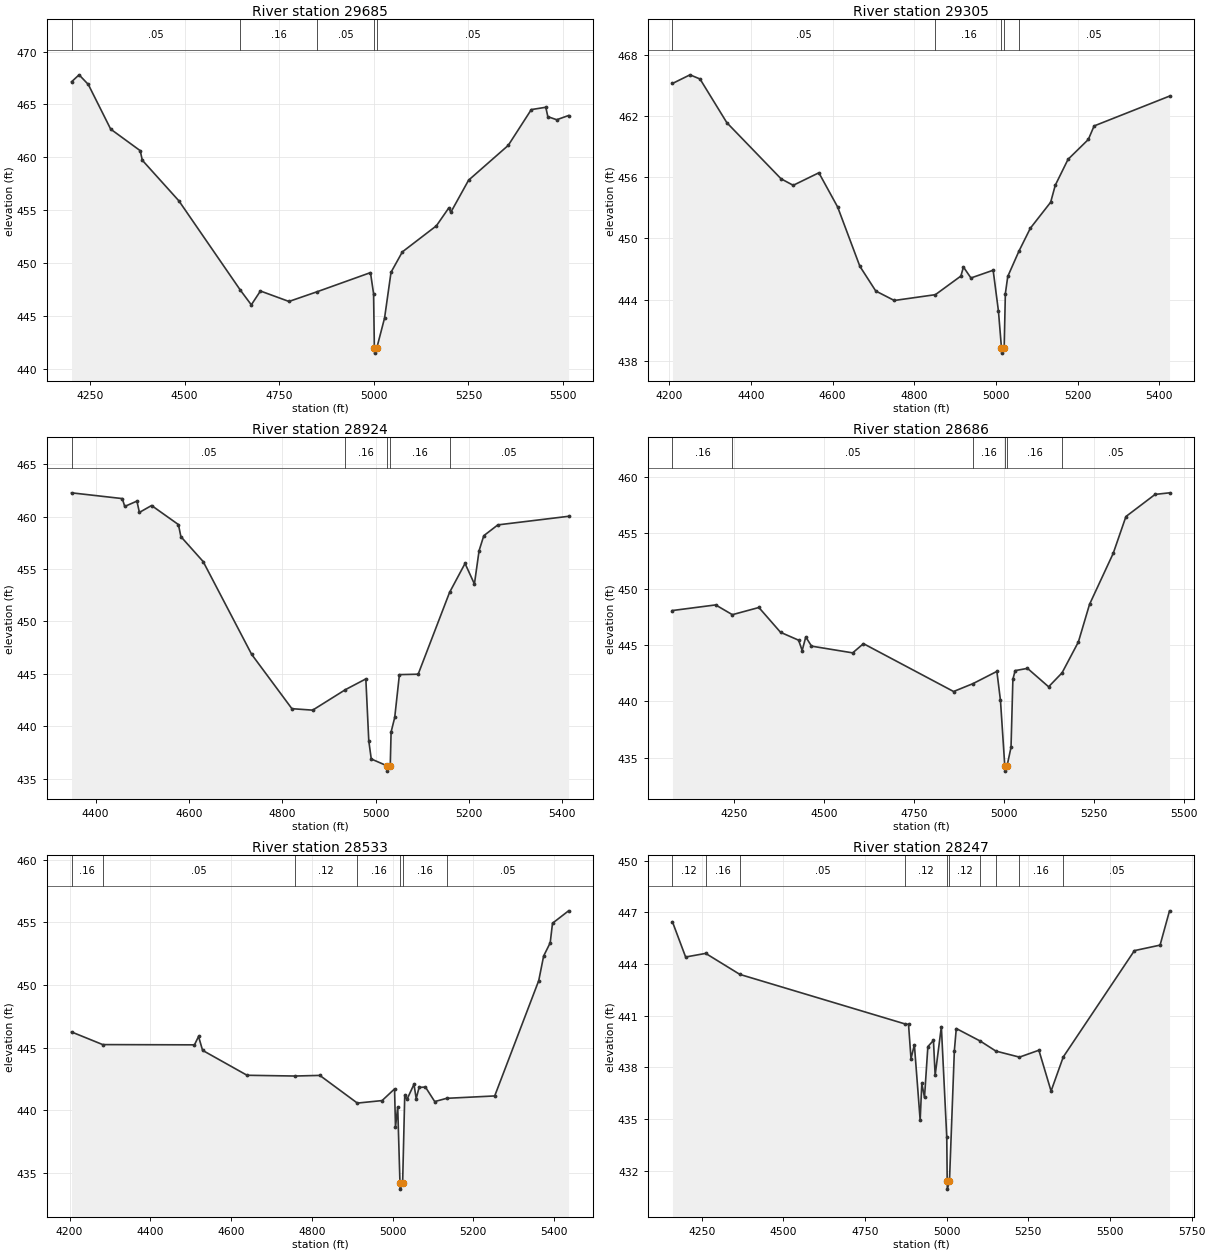
Type RM Length L Ch R = 1,29685,380,380,380
BEGIN DESCRIPTION:
Mill Creek29685.37
END DESCRIPTION:
XS GIS Cut Line= 3
      2758428.48      6820977.48      2758127.95      6821728.67
      2757927.06      6822191.37
#Sta/Elev= 30
  4201.0  467.14  4221.0  467.80  4245.3  466.89  4304.5  462.66  4382.6  460.62
  4388.0  459.72  4484.8  455.87  4647.0  447.43  4676.1  446.03  4700.2  447.34
  4775.6  446.35  4850.0  447.27  4991.0  449.08  4999.2  447.09  5001.3  441.96
  5001.8  441.46  5007.8  441.96  5028.3  444.79  5045.3  449.11  5075.2  451.04
  5165.2  453.51  5197.9  455.20  5203.3  454.79  5250.3  457.83  5355.0  461.12
  5416.0  464.51  5454.3  464.73  5459.7  463.84  5483.2  463.55  5514.5  463.95
#Mann=5,-1,0
  4201.0    0.05       0  4647.0    0.16       0  4850.0    0.05       0
  5001.3    0.05       0  5007.8    0.05       0
Bank Sta=5001.3,5007.8
Exp/Cntr=0.3,0.1

Type RM Length L Ch R = 1,29305,381,381,381
BEGIN DESCRIPTION:
Mill Creek29305.19
END DESCRIPTION:
XS GIS Cut Line= 3
      2758196.93      6820706.85      2757900.56      6821468.56
      2757763.51      6821844.52
#Sta/Elev= 30
  4207.7  465.22  4250.7  466.07  4275.2  465.66  4340.9  461.37  4473.7  455.86
  4503.5  455.22  4566.3  456.45  4612.3  453.09  4666.7  447.27  4705.7  444.84
  4751.0  443.91  4851.7  444.48  4914.2  446.31  4920.4  447.20  4938.8  446.12
  4993.2  446.88  5006.2  442.86  5013.6  439.24  5014.1  438.74  5020.2  439.24
  5023.1  444.58  5029.0  446.27  5056.2  448.74  5084.2  451.00  5134.1  453.56
  5145.3  455.22  5176.6  457.77  5226.3  459.72  5240.5  461.05  5425.2  463.98
#Mann=5,-1,0
  4207.7    0.05       0  4851.7    0.16       0  5013.6    0.07       0
  5020.2    0.16       0  5056.2    0.05       0
Bank Sta=5013.6,5020.2
Exp/Cntr=0.3,0.1

Type RM Length L Ch R = 1,28924,238,238,238
BEGIN DESCRIPTION:
Mill Creek28923.66
END DESCRIPTION:
XS GIS Cut Line= 3
      2757896.36      6820554.06      2757682.60      6821182.70
      2757646.43      6821581.88
#Sta/Elev= 30
  4348.4  462.27  4457.2  461.72  4462.4  460.97  4488.5  461.48  4493.8  460.40
  4519.9  461.06  4577.4  459.24  4582.7  458.09  4630.4  455.71  4734.2  446.86
  4820.5  441.67  4865.0  441.53  4935.3  443.49  4978.9  444.51  4985.2  438.60
  4990.5  436.87  5024.6  436.21  5025.1  435.71  5031.2  436.21  5033.0  439.44
  5040.8  440.84  5050.8  444.92  5091.0  444.96  5158.2  452.76  5191.4  455.53
  5211.5  453.57  5221.5  456.75  5231.6  458.18  5261.7  459.21  5413.2  460.03
#Mann=5,-1,0
  4348.4    0.05       0  4935.3    0.16       0  5024.6    0.07       0
  5031.2    0.16       0  5158.2    0.05       0
Bank Sta=5024.6,5031.2
Exp/Cntr=0.3,0.1

Type RM Length L Ch R = 1,28686,153,153,153
BEGIN DESCRIPTION:
Mill Creek28685.84
END DESCRIPTION:
XS GIS Cut Line= 3
      2757545.75      6820141.26      2757486.49      6821066.37
      2757600.67      6821506.19
#Sta/Elev= 30
  4078.5  448.09  4198.5  448.59  4245.0  447.72  4318.7  448.36  4378.9  446.15
  4429.0  445.45  4439.0  444.53  4449.0  445.74  4464.9  444.92  4579.3  444.32
  4609.3  445.14  4859.8  440.88  4913.6  441.58  4980.1  442.67  4990.1  440.08
  5002.0  434.29  5002.5  433.79  5008.6  434.29  5019.4  435.91  5024.6  441.97
  5030.9  442.74  5065.2  442.94  5123.9  441.30  5161.2  442.54  5206.6  445.29
  5237.6  448.64  5303.4  453.18  5338.8  456.46  5419.9  458.43  5459.9  458.57
#Mann=6,-1,0
  4078.5    0.16       0  4245.0    0.05       0  4913.6    0.16       0
  5002.0    0.07       0  5008.6    0.16       0  5161.2    0.05       0
Bank Sta=5002,5008.6
Exp/Cntr=0.3,0.1

Type RM Length L Ch R = 1,28533,286,286,286
BEGIN DESCRIPTION:
Mill Creek28532.65
END DESCRIPTION:
XS GIS Cut Line= 3
      2757395.07      6820216.86      2757349.17      6821015.84
      2757530.22      6821407.08
#Sta/Elev= 30
  4204.7  446.25  4282.0  445.24  4509.3  445.22  4519.4  445.89  4529.4  444.78
  4639.6  442.79  4758.2  442.73  4819.9  442.78  4912.8  440.57  4974.1  440.77
  5005.0  441.70  5007.3  438.65  5012.8  440.26  5018.4  434.20  5018.9  433.70
  5025.0  434.20  5030.2  441.18  5035.7  440.86  5053.1  442.07  5058.6  440.93
  5065.8  441.82  5081.5  441.85  5104.5  440.69  5134.0  440.95  5253.1  441.14
  5362.2  450.35  5374.3  452.31  5390.6  453.37  5396.3  454.93  5436.1  455.92
#Mann=7,-1,0
  4204.7    0.16       0  4282.0    0.05       0  4758.2    0.12       0
  4912.8    0.16       0  5018.4    0.07       0  5025.0    0.16       0
  5134.0    0.05       0
Bank Sta=5018.4,5025
Exp/Cntr=0.3,0.1

Type RM Length L Ch R = 1,28247,391,391,391
BEGIN DESCRIPTION:
Mill Creek28246.72
END DESCRIPTION:
XS GIS Cut Line= 5
      2757300.18      6820113.69      2757089.10      6820935.48
      2756883.41      6821068.75      2756831.73      6821109.02
      2756606.84      6821393.49
#Sta/Elev= 30
  4160.5  446.44  4200.8  444.40  4262.2  444.61  4366.9  443.39  4871.8  440.52
  4883.2  440.49  4890.8  438.50  4901.1  439.31  4918.8  434.93  4923.9  437.07
  4932.1  436.25  4942.4  439.20  4959.5  439.56  4964.7  437.53  4983.7  440.36
  5000.2  433.97  5001.6  431.43  5002.1  430.93  5008.6  431.43  5023.5  438.96
  5029.4  440.25  5103.0  439.52  5150.7  438.94  5222.8  438.59  5282.3  438.99
  5319.6  436.62  5356.9  438.60  5574.7  444.77  5653.3  445.09  5682.2  447.08
#Mann=10,-1,0
  4160.5    0.12       0  4262.2    0.16       0  4366.9    0.05       0
  4871.8    0.12       0  5001.6    0.07       0  5008.6    0.12       0
  5103.0    0.16       0  5150.7    0.05       0  5222.8    0.16       0
  5356.9    0.05       0
Bank Sta=5001.6,5008.6
Exp/Cntr=0.3,0.1

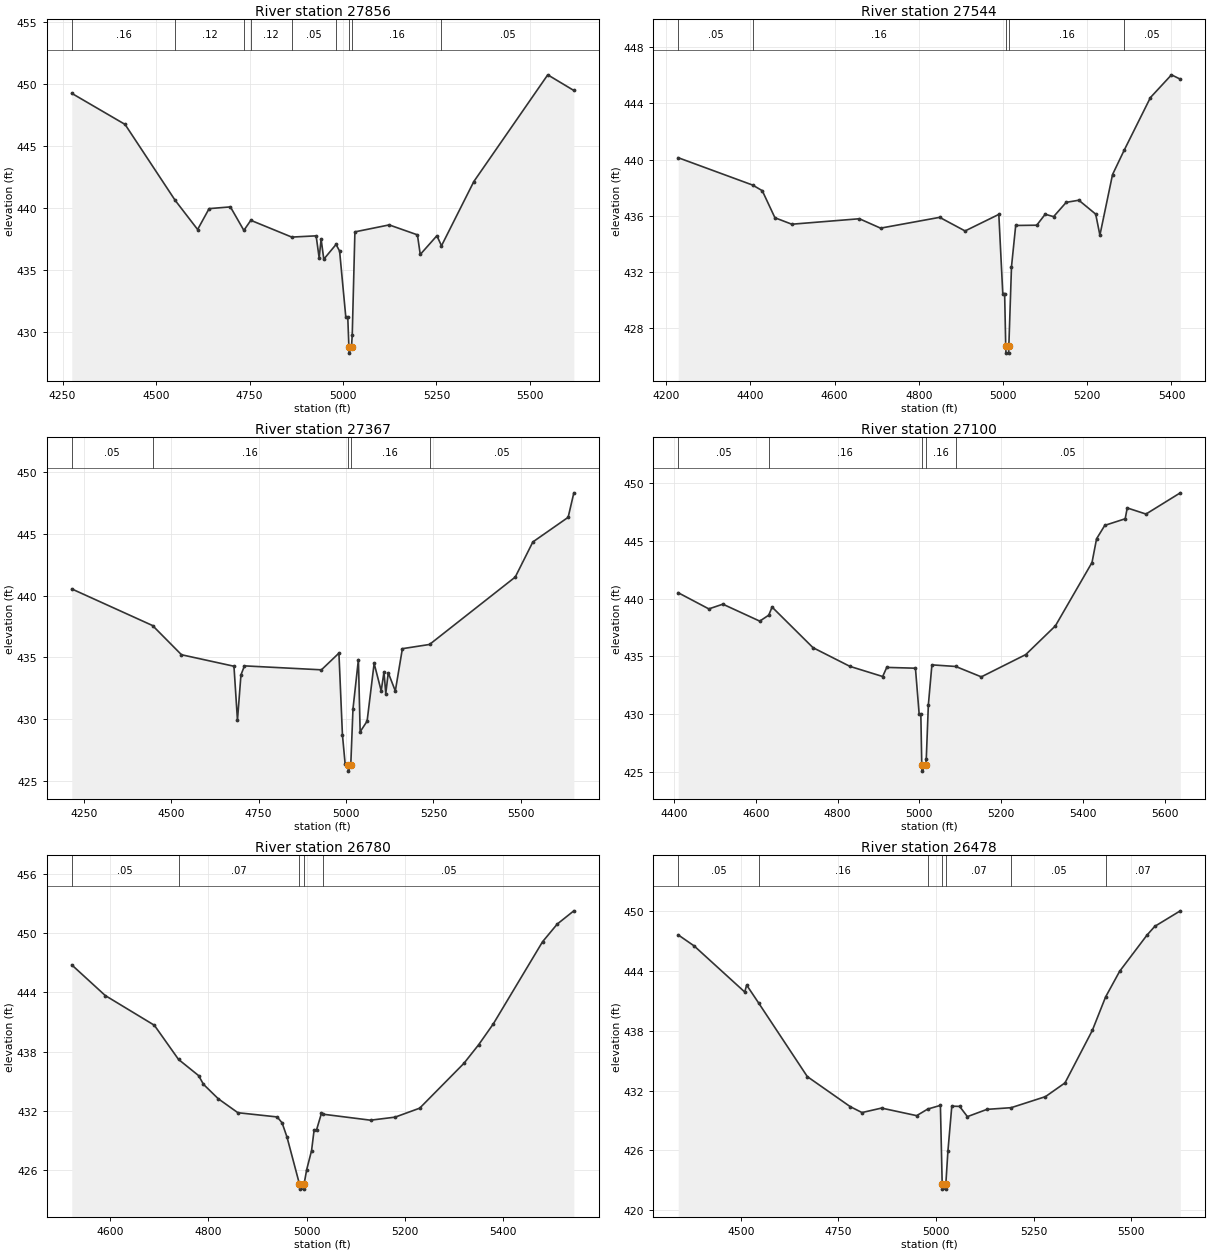
Type RM Length L Ch R = 1,27856,312,312,312
BEGIN DESCRIPTION:
Mill Creek27855.6
END DESCRIPTION:
XS GIS Cut Line= 3
      2756909.70      6820151.76      2756756.23      6820871.10
      2756511.60      6821427.03
#Sta/Elev= 30
  4274.5  449.23  4417.0  446.73  4551.0  440.62  4611.1  438.27  4641.8  439.95
  4698.8  440.09  4734.8  438.20  4753.4  439.01  4862.9  437.66  4928.1  437.76
  4936.2  435.98  4941.4  437.50  4948.6  435.88  4981.4  437.07  4990.9  436.53
  5007.4  431.24  5012.7  431.24  5015.7  428.82  5016.2  428.32  5022.7  428.82
  5024.7  429.81  5031.8  438.08  5123.5  438.64  5199.0  437.84  5206.6  436.26
  5251.1  437.77  5263.4  436.96  5349.9  442.13  5547.6  450.72  5617.4  449.46
#Mann=9,-1,0
  4274.5    0.16       0  4551.0    0.12       0  4734.8    0.05       0
  4753.4    0.12       0  4862.9    0.05       0  4981.4    0.16       0
  5015.7    0.07       0  5022.7    0.16       0  5263.4    0.05       0
Bank Sta=5015.7,5022.7
Exp/Cntr=0.3,0.1

Type RM Length L Ch R = 1,27544,177,177,177
BEGIN DESCRIPTION:
Mapping XS e07c7e76
END DESCRIPTION:
XS GIS Cut Line= 3
      2756527.12      6820042.09      2756462.78      6820814.68
      2756461.46      6821232.02
#Sta/Elev= 30
  4228.4  440.13  4405.2  438.18  4428.0  437.78  4458.1  435.85  4498.2  435.39
  4658.7  435.78  4709.0  435.11  4849.4  435.88  4909.7  434.91  4989.9  436.09
  4999.3  430.45  5003.7  430.45  5006.3  426.70  5006.8  426.20  5013.2  426.20
  5013.7  426.70  5020.0  432.36  5030.0  435.30  5080.0  435.32  5100.0  436.10
  5120.0  435.93  5150.0  436.95  5180.0  437.10  5220.0  436.11  5230.0  434.61
  5260.0  438.93  5287.4  440.65  5350.0  444.42  5400.0  446.04  5421.0  445.73
#Mann=5,-1,0
  4228.4    0.05       0  4405.2    0.16       0  5006.3    0.07       0
  5013.7    0.16       0  5287.4    0.05       0
Bank Sta=5006.3,5013.7
Exp/Cntr=0.3,0.1

Type RM Length L Ch R = 1,27367,267,267,267
BEGIN DESCRIPTION:
Mapping XS 9081c8f6
END DESCRIPTION:
XS GIS Cut Line= 3
      2756325.34      6819997.41      2756295.70      6820781.35
      2756209.79      6821427.16
#Sta/Elev= 30
  4215.5  440.54  4446.6  437.58  4529.3  435.22  4679.4  434.29  4689.4  429.93
  4699.4  433.59  4709.4  434.32  4929.6  434.00  4979.6  435.35  4989.6  428.76
  4997.3  426.41  5005.9  426.31  5006.4  425.81  5013.5  426.31  5019.8  430.84
  5035.3  434.83  5040.3  428.99  5060.2  429.85  5080.3  434.52  5100.5  432.30
  5108.5  433.83  5113.6  432.08  5120.7  433.76  5140.9  432.29  5161.1  435.71
  5238.7  436.05  5483.9  441.50  5534.3  444.34  5635.2  446.33  5651.5  448.31
#Mann=5,-1,0
  4215.5    0.05       0  4446.6    0.16       0  5005.9    0.07       0
  5013.5    0.16       0  5238.7    0.05       0
Bank Sta=5005.9,5013.5
Exp/Cntr=0.3,0.1

Type RM Length L Ch R = 1,27100,320,320,320
BEGIN DESCRIPTION:
Mill Creek27100
END DESCRIPTION:
XS GIS Cut Line= 3
      2756186.58      6820022.06      2756142.80      6820614.11
      2756065.02      6821244.37
#Sta/Elev= 30
  4409.9  440.51  4484.8  439.11  4519.1  439.52  4609.4  438.05  4631.5  438.57
  4639.5  439.27  4739.7  435.75  4830.0  434.13  4910.2  433.25  4920.2  434.04
  4990.4  433.97  4999.5  429.99  5003.6  429.99  5005.9  425.55  5006.4  425.05
  5015.2  425.55  5016.9  426.09  5022.0  430.79  5030.7  434.26  5089.0  434.12
  5151.6  433.22  5260.3  435.15  5332.9  437.64  5422.5  443.13  5433.7  445.19
  5453.8  446.35  5503.7  446.92  5508.7  447.86  5554.6  447.33  5638.6  449.17
#Mann=5,-1,0
  4409.9    0.05       0  4631.5    0.16       0  5005.9    0.07       0
  5015.2    0.16       0  5089.0    0.05       0
Bank Sta=5005.9,5015.2
Exp/Cntr=0.3,0.1

Type RM Length L Ch R = 1,26780,302,302,302
BEGIN DESCRIPTION:
Mill Creek26779.51
END DESCRIPTION:
XS GIS Cut Line= 3
      2755839.64      6820082.88      2755838.69      6820576.42
      2755844.24      6821104.75
#Sta/Elev= 30
  4521.9  446.80  4590.0  443.69  4690.0  440.67  4739.2  437.20  4780.0  435.56
  4790.0  434.67  4820.0  433.21  4860.0  431.79  4940.0  431.36  4950.0  430.76
  4960.0  429.31  4985.4  424.53  4985.9  424.03  4994.2  424.03  4994.7  424.53
  5000.0  426.00  5010.0  427.95  5015.2  430.06  5020.2  430.06  5030.0  431.71
  5033.0  431.64  5130.0  431.03  5180.0  431.34  5230.0  432.25  5320.0  436.80
  5350.0  438.69  5380.0  440.82  5480.1  449.15  5510.1  450.95  5543.8  452.29
#Mann=5,-1,0
  4521.9    0.05       0  4739.2    0.07       0  4985.4    0.07       0
  4994.7    0.07       0  5033.0    0.05       0
Bank Sta=4985.4,4994.7
Exp/Cntr=0.3,0.1

Type RM Length L Ch R = 1,26478,352,352,352
BEGIN DESCRIPTION:
Mill Creek26477.75
END DESCRIPTION:
XS GIS Cut Line= 3
      2755536.57      6819850.37      2755553.46      6820517.54
      2755556.81      6821136.35
#Sta/Elev= 30
  4339.5  447.64  4380.1  446.54  4509.8  441.91  4514.8  442.60  4545.2  440.82
  4670.2  433.41  4780.3  430.39  4810.3  429.80  4860.3  430.25  4950.3  429.49
  4978.6  430.15  5011.1  430.52  5015.7  422.61  5016.2  422.11  5024.5  422.11
  5025.0  422.61  5030.3  425.90  5040.3  430.44  5060.3  430.42  5080.3  429.39
  5130.3  430.12  5192.4  430.29  5280.3  431.40  5330.3  432.78  5400.3  438.05
  5434.3  441.41  5470.3  443.99  5540.3  447.62  5560.3  448.50  5625.7  450.06
#Mann=7,-1,0
  4339.5    0.05       0  4545.2    0.16       0  4978.6    0.07       0
  5015.7    0.07       0  5025.0    0.07       0  5192.4    0.05       0
  5434.3    0.07       0
Bank Sta=5015.7,5025
Exp/Cntr=0.3,0.1

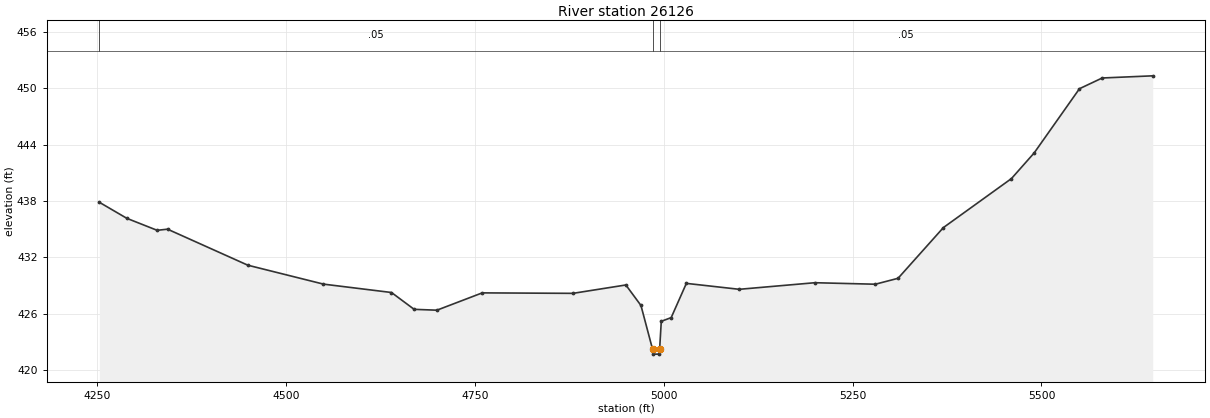
Type RM Length L Ch R = 1,26126,412,412,412
BEGIN DESCRIPTION:
Mill Creek26125.56
END DESCRIPTION:
XS GIS Cut Line= 3
      2755207.90      6819764.52      2755233.92      6820509.79
      2755258.50      6821157.90
#Sta/Elev= 30
  4253.0  437.86  4289.5  436.15  4329.5  434.88  4343.3  435.00  4449.6  431.17
  4549.7  429.16  4639.7  428.27  4669.7  426.48  4699.8  426.39  4759.8  428.23
  4879.9  428.18  4949.9  429.07  4969.9  426.89  4985.3  422.22  4985.8  421.72
  4994.1  421.72  4994.6  422.22  4996.8  425.21  5009.9  425.60  5030.0  429.24
  5100.0  428.61  5200.1  429.31  5280.1  429.15  5310.2  429.78  5370.2  435.17
  5460.3  440.38  5490.3  443.10  5550.3  449.93  5580.4  451.07  5647.3  451.30
#Mann=3,-1,0
  4253.0    0.05       0  4985.3    0.05       0  4994.6    0.05       0
Bank Sta=4985.3,4994.6
Exp/Cntr=0.3,0.1