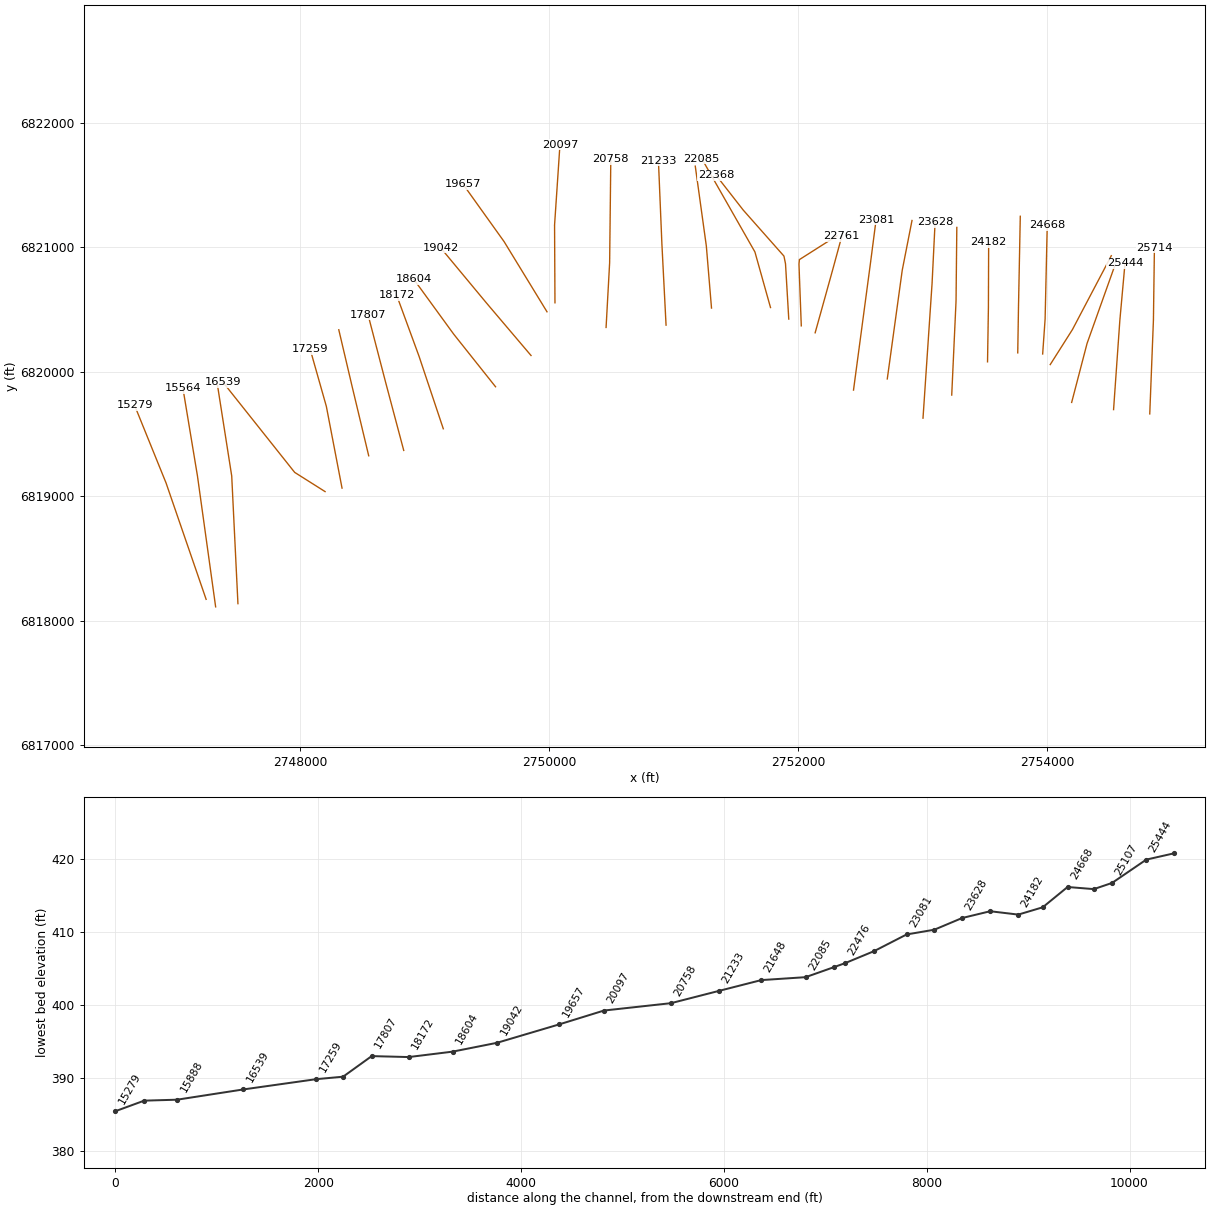
HEC-RAS study Mill Creek.prj: Mill Creek Base Level Engineering

--- Mill Creek.g01 (geometry) --- (continued)

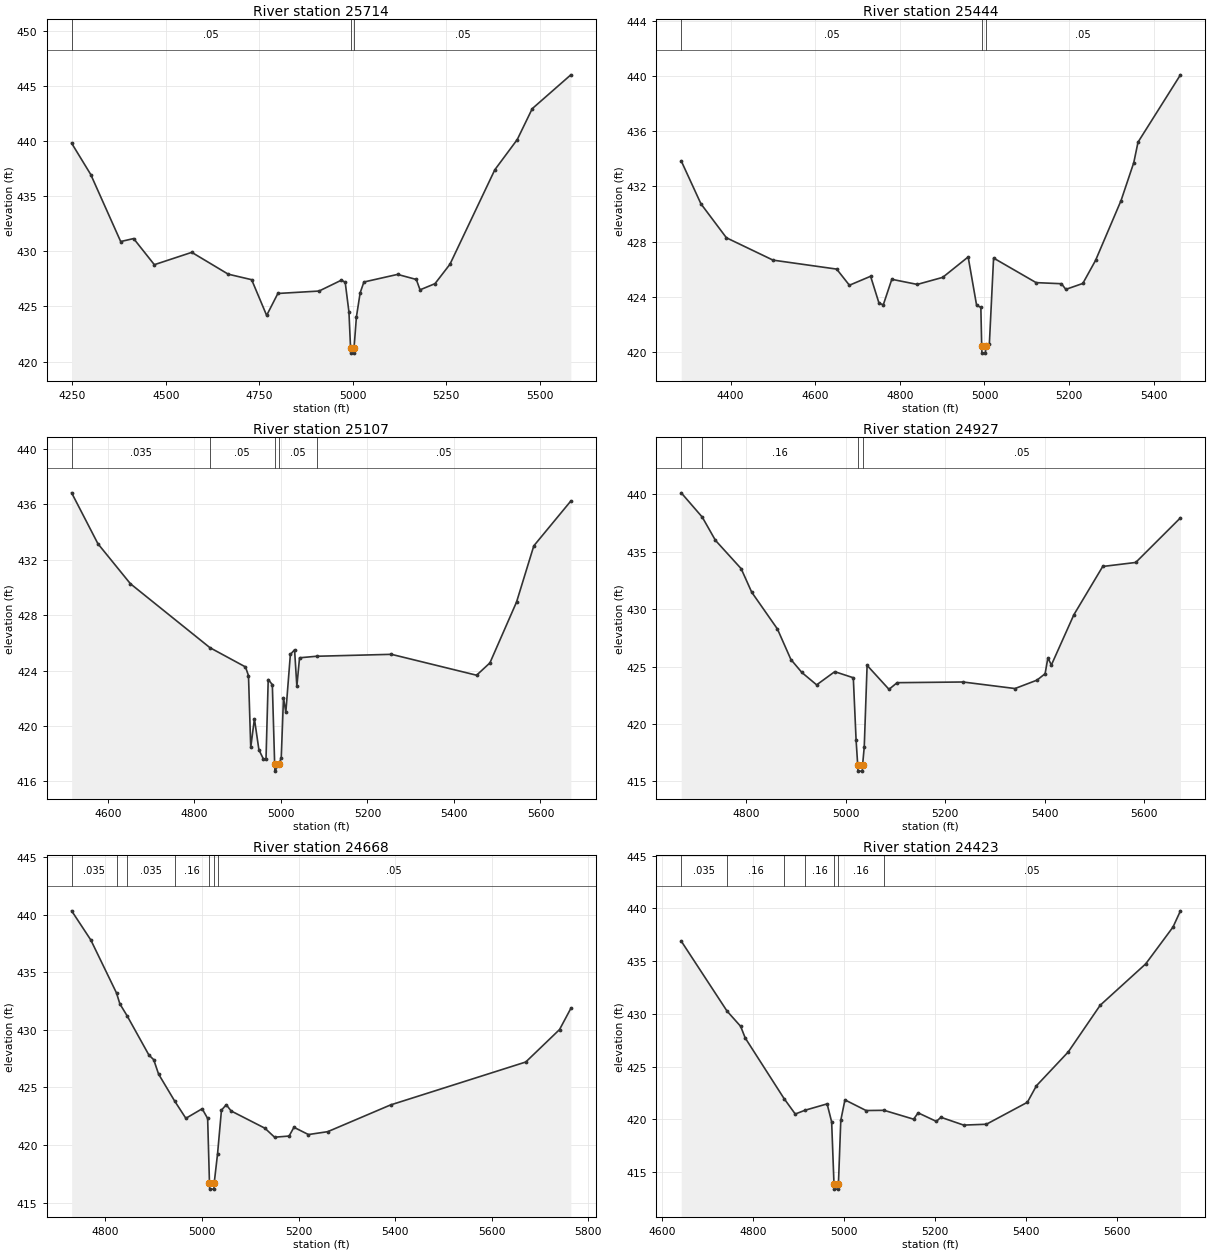
Type RM Length L Ch R = 1,25714,270,270,270
BEGIN DESCRIPTION:
Mill Creek25713.76
END DESCRIPTION:
XS GIS Cut Line= 3
      2754824.54      6819659.94      2754854.03      6820413.98
      2754862.01      6820994.31
#Sta/Elev= 30
  4248.4  439.81  4299.5  436.97  4379.6  430.89  4414.2  431.16  4469.6  428.79
  4569.7  429.91  4667.2  427.93  4729.8  427.43  4769.9  424.19  4799.9  426.18
  4910.0  426.40  4970.0  427.39  4980.0  427.19  4990.0  424.50  4994.3  421.27
  4994.8  420.77  5003.2  420.77  5003.7  421.27  5010.0  424.06  5020.0  426.24
  5030.0  427.22  5120.1  427.91  5170.1  427.45  5180.1  426.51  5220.1  427.07
  5260.1  428.83  5380.1  437.40  5440.1  440.14  5480.1  442.94  5583.4  446.01
#Mann=3,-1,0
  4248.4    0.05       0  4994.3    0.05       0  5003.7    0.05       0
Bank Sta=4994.3,5003.7
Exp/Cntr=0.3,0.1

Type RM Length L Ch R = 1,25444,337,337,337
BEGIN DESCRIPTION:
Mill Creek25443.89
END DESCRIPTION:
XS GIS Cut Line= 3
      2754533.85      6819694.51      2754584.15      6820409.23
      2754625.88      6820870.86
#Sta/Elev= 30
  4283.3  433.85  4329.9  430.74  4390.1  428.28  4500.3  426.66  4650.7  426.01
  4680.8  424.84  4730.9  425.49  4750.9  423.53  4761.0  423.43  4781.0  425.27
  4841.2  424.90  4901.3  425.41  4961.5  426.89  4981.5  423.38  4991.5  423.24
  4993.5  420.42  4994.0  419.92  5002.4  419.92  5002.9  420.42  5011.6  420.58
  5021.6  426.81  5122.1  425.03  5182.1  424.95  5192.3  424.54  5232.5  424.97
  5262.6  426.64  5322.9  430.98  5353.0  433.73  5363.0  435.21  5463.3  440.09
#Mann=3,-1,0
  4283.3    0.05       0  4993.5    0.05       0  5002.9    0.05       0
Bank Sta=4993.5,5002.9
Exp/Cntr=0.3,0.1

Type RM Length L Ch R = 1,25107,180,180,180
BEGIN DESCRIPTION:
Mill Creek25107.06
END DESCRIPTION:
XS GIS Cut Line= 3
      2754197.28      6819752.19      2754321.04      6820226.21
      2754544.04      6820851.63
#Sta/Elev= 30
  4516.3  436.84  4577.1  433.16  4652.2  430.27  4836.0  425.65  4918.1  424.26
  4925.1  423.63  4930.3  418.44  4938.8  420.51  4949.2  418.27  4959.5  417.61
  4965.6  417.61  4970.7  423.35  4980.2  422.98  4985.6  417.23  4986.1  416.73
  4995.3  417.23  5000.8  417.69  5006.0  422.04  5011.4  420.98  5021.9  425.16
  5031.6  425.50  5036.9  422.86  5043.1  424.92  5082.3  425.03  5255.5  425.17
  5452.3  423.66  5483.1  424.55  5544.7  428.95  5584.6  433.01  5670.2  436.25
#Mann=5,-1,0
  4516.3   0.035       0  4836.0    0.05       0  4985.6   0.035       0
  4995.3    0.05       0  5082.3    0.05       0
Bank Sta=4985.6,4995.3
Exp/Cntr=0.3,0.1

Type RM Length L Ch R = 1,24927,259,259,259
BEGIN DESCRIPTION:
Mill Creek24927.43
END DESCRIPTION:
XS GIS Cut Line= 3
      2754025.26      6820056.25      2754203.67      6820337.66
      2754515.66      6820930.59
#Sta/Elev= 30
  4669.3  440.14  4711.6  438.02  4738.0  436.00  4789.7  433.53  4810.9  431.48
  4862.6  428.27  4889.7  425.61  4911.7  424.48  4941.4  423.40  4977.8  424.55
  5015.1  424.02  5020.7  418.57  5024.0  416.38  5024.5  415.88  5033.2  415.88
  5033.7  416.38  5037.1  418.01  5042.8  425.10  5086.8  423.01  5103.2  423.59
  5235.5  423.65  5340.0  423.08  5384.1  423.81  5400.5  424.37  5406.1  425.76
  5413.1  425.13  5458.3  429.51  5516.3  433.72  5582.6  434.07  5672.5  437.96
#Mann=4,-1,0
  4669.3   0.035       0  4711.6    0.16       0  5024.0    0.07       0
  5033.7    0.05       0
Bank Sta=5024,5033.7
Exp/Cntr=0.3,0.1

Type RM Length L Ch R = 1,24668,245,245,245
BEGIN DESCRIPTION:
Mill Creek24668.09
END DESCRIPTION:
XS GIS Cut Line= 3
      2753964.40      6820141.38      2753984.05      6820422.40
      2754001.12      6821174.40
#Sta/Elev= 30
  4729.9  440.34  4769.6  437.81  4822.9  433.20  4829.8  432.26  4844.7  431.23
  4889.9  427.82  4899.9  427.41  4910.0  426.16  4943.0  423.84  4966.5  422.32
  5000.2  423.15  5011.6  422.31  5015.4  416.67  5015.9  416.17  5024.6  416.17
  5025.1  416.67  5032.1  419.23  5040.2  423.03  5050.2  423.50  5060.2  422.96
  5130.2  421.46  5150.2  420.68  5180.3  420.78  5190.3  421.54  5220.3  420.91
  5260.3  421.16  5390.3  423.48  5670.4  427.21  5740.4  430.03  5763.8  431.87
#Mann=7,-1,0
  4729.9   0.035       0  4822.9    0.16       0  4844.7   0.035       0
  4943.0    0.16       0  5015.4    0.07       0  5025.1    0.16       0
  5032.1    0.05       0
Bank Sta=5015.4,5025.1
Exp/Cntr=0.3,0.1

Type RM Length L Ch R = 1,24423,241,241,241
BEGIN DESCRIPTION:
Mill Creek24423.38
END DESCRIPTION:
XS GIS Cut Line= 3
      2753764.26      6820150.40      2753770.15      6820514.20
      2753784.67      6821247.40
#Sta/Elev= 30
  4641.6  436.90  4742.2  430.27  4772.2  428.82  4782.2  427.72  4867.5  421.98
  4892.2  420.51  4913.9  420.87  4962.2  421.47  4972.2  419.76  4977.3  413.89
  4977.8  413.39  4986.6  413.39  4987.1  413.89  4992.3  419.92  5001.4  421.85
  5047.9  420.84  5087.4  420.86  5152.3  420.02  5162.3  420.62  5202.3  419.81
  5212.3  420.20  5262.3  419.46  5312.3  419.54  5402.3  421.62  5422.3  423.19
  5492.3  426.40  5562.4  430.82  5662.4  434.74  5722.4  438.23  5738.8  439.77
#Mann=7,-1,0
  4641.6   0.035       0  4742.2    0.16       0  4867.5    0.12       0
  4913.9    0.16       0  4977.3    0.07       0  4987.1    0.16       0
  5087.4    0.05       0
Bank Sta=4977.3,4987.1
Exp/Cntr=0.3,0.1

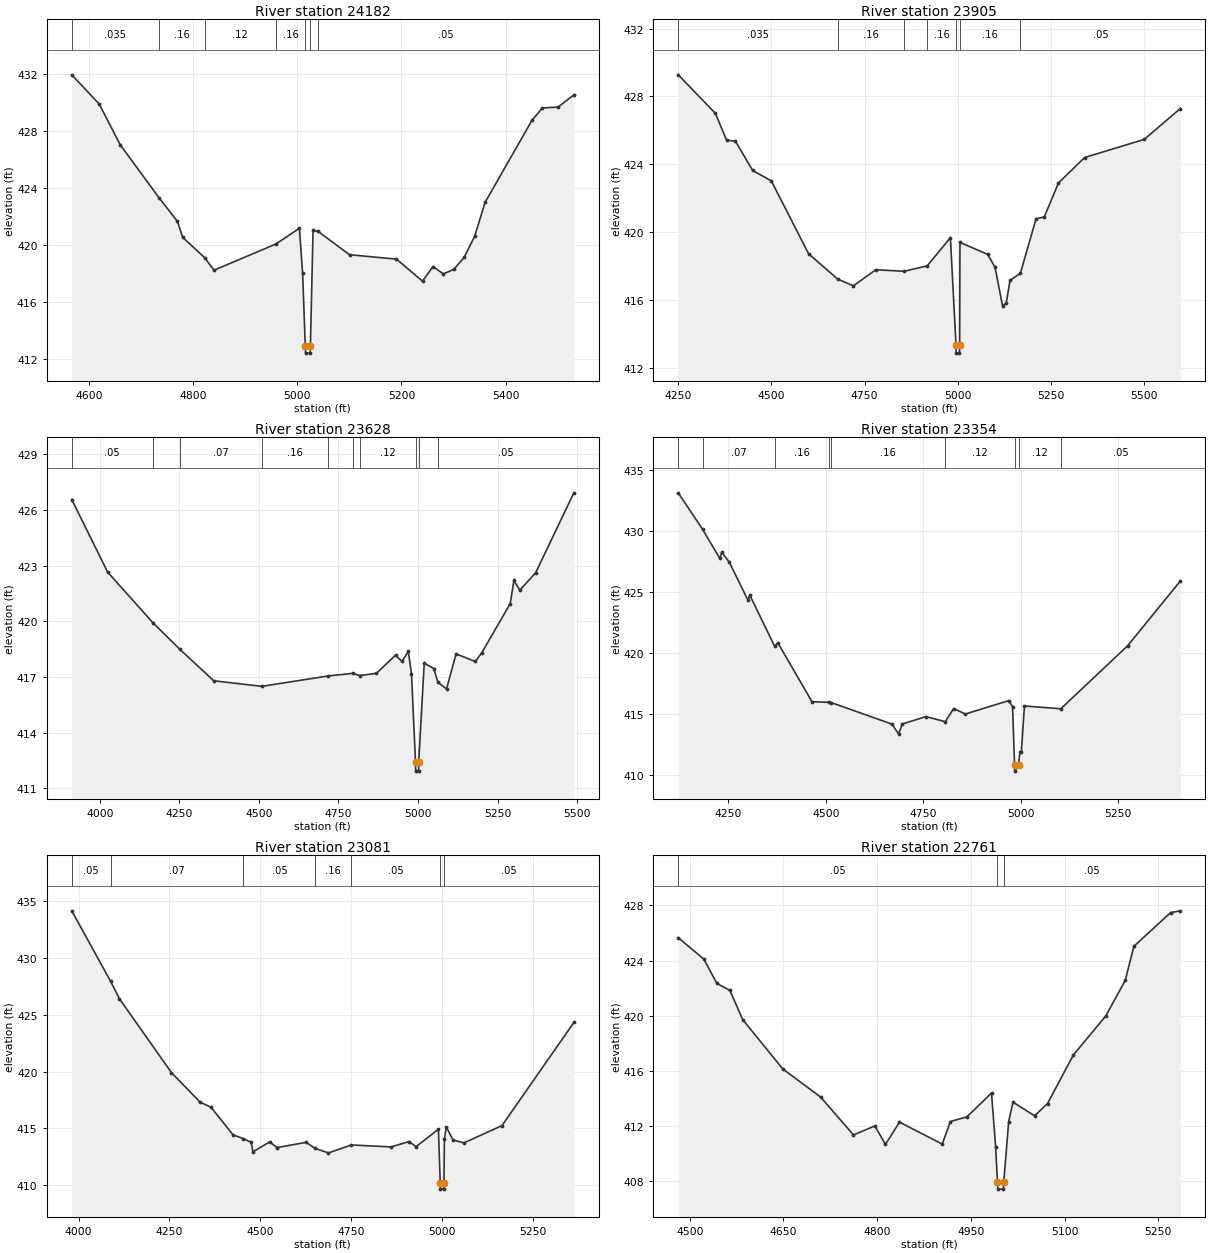
Type RM Length L Ch R = 1,24182,277,277,277
BEGIN DESCRIPTION:
Mill Creek24181.7
END DESCRIPTION:
XS GIS Cut Line= 3
      2753521.58      6820078.18      2753528.65      6820514.82
      2753530.61      6821041.32
#Sta/Elev= 30
  4567.5  431.96  4620.3  429.90  4660.3  427.05  4734.6  423.33  4770.3  421.65
  4780.3  420.53  4822.5  419.10  4840.4  418.22  4958.9  420.06  5004.2  421.17
  5010.4  417.99  5015.5  412.89  5016.0  412.39  5024.8  412.39  5025.3  412.89
  5030.4  421.03  5040.1  420.95  5100.4  419.31  5190.4  419.00  5240.4  417.45
  5260.4  418.48  5280.4  417.96  5300.4  418.28  5320.4  419.13  5340.4  420.60
  5360.4  422.99  5450.4  428.76  5470.4  429.63  5500.4  429.69  5530.7  430.55
#Mann=7,-1,0
  4567.5   0.035       0  4734.6    0.16       0  4822.5    0.12       0
  4958.9    0.16       0  5015.5    0.07       0  5025.3    0.16       0
  5040.1    0.05       0
Bank Sta=5015.5,5025.3
Exp/Cntr=0.3,0.1

Type RM Length L Ch R = 1,23905,277,277,277
BEGIN DESCRIPTION:
Mill Creek23905.33
END DESCRIPTION:
XS GIS Cut Line= 3
      2753234.02      6819811.47      2753268.66      6820567.41
      2753274.88      6821157.94
#Sta/Elev= 30
  4249.8  429.27  4349.4  427.00  4379.5  425.42  4403.4  425.35  4449.5  423.63
  4499.6  423.01  4599.7  418.71  4677.6  417.22  4719.8  416.82  4779.9  417.77
  4856.2  417.68  4917.9  418.00  4980.1  419.66  4995.2  413.35  4995.7  412.85
  5004.5  412.85  5005.0  413.35  5005.8  419.38  5080.1  418.68  5100.1  417.91
  5120.1  415.63  5130.1  415.82  5140.1  417.14  5167.9  417.56  5210.1  420.78
  5232.0  420.88  5270.1  422.89  5340.1  424.39  5500.2  425.46  5597.1  427.28
#Mann=7,-1,0
  4249.8   0.035       0  4677.6    0.16       0  4856.2    0.12       0
  4917.9    0.16       0  4995.2    0.07       0  5005.0    0.16       0
  5167.9    0.05       0
Bank Sta=4995.2,5005
Exp/Cntr=0.3,0.1

Type RM Length L Ch R = 1,23628,274,274,274
BEGIN DESCRIPTION:
Mill Creek23628.119
END DESCRIPTION:
XS GIS Cut Line= 3
      2753003.31      6819625.78      2753076.31      6820711.33
      2753100.45      6821200.63
#Sta/Elev= 30
  3912.0  426.56  4024.6  422.65  4166.3  419.93  4251.4  418.49  4358.2  416.79
  4509.2  416.49  4718.0  417.05  4795.2  417.19  4816.3  417.07  4869.4  417.19
  4929.5  418.17  4949.6  417.83  4969.6  418.37  4979.6  417.18  4992.3  412.42
  4992.8  411.92  5001.8  411.92  5002.3  412.42  5019.7  417.74  5049.7  417.45
  5062.6  416.71  5089.8  416.35  5119.8  418.24  5179.9  417.83  5199.9  418.28
  5290.0  420.95  5301.5  422.20  5320.1  421.67  5370.1  422.62  5489.9  426.92
#Mann=10,-1,0
  3912.0    0.05       0  4166.3   0.035       0  4251.4    0.07       0
  4509.2    0.16       0  4718.0    0.12       0  4795.2    0.16       0
  4816.3    0.12       0  4992.3    0.07       0  5002.3    0.12       0
  5062.6    0.05       0
Bank Sta=4992.3,5002.3
Exp/Cntr=0.3,0.1

Type RM Length L Ch R = 1,23354,273,273,273
BEGIN DESCRIPTION:
Mill Creek23353.62
END DESCRIPTION:
XS GIS Cut Line= 3
      2752716.37      6819940.96      2752836.40      6820813.26
      2752914.93      6821213.51
#Sta/Elev= 30
  4121.4  433.13  4183.7  430.15  4228.1  427.75  4233.1  428.26  4252.7  427.43
  4300.1  424.34  4305.1  424.74  4368.8  420.55  4377.1  420.83  4464.6  416.01
  4509.3  415.96  4513.8  415.94  4670.2  414.17  4686.7  413.37  4696.8  414.19
  4757.4  414.79  4806.8  414.37  4828.0  415.45  4858.3  415.00  4969.4  416.10
  4979.4  415.60  4984.5  410.82  4985.0  410.32  4994.6  410.82  4998.3  411.90
  5001.9  411.90  5009.8  415.66  5103.1  415.43  5274.8  420.60  5409.8  425.90
#Mann=9,-1,0
  4121.4    0.05       0  4183.7    0.07       0  4368.8    0.16       0
  4509.3    0.05       0  4513.8    0.16       0  4806.8    0.12       0
  4984.5    0.07       0  4994.6    0.12       0  5103.1    0.05       0
Bank Sta=4984.5,4994.6
Exp/Cntr=0.3,0.1

Type RM Length L Ch R = 1,23081,320,320,320
BEGIN DESCRIPTION:
Mill Creek23081.367
END DESCRIPTION:
XS GIS Cut Line= 3
      2752445.11      6819851.33      2752582.03      6820876.38
      2752626.64      6821220.35
#Sta/Elev= 30
  3981.2  434.12  4088.1  427.92  4112.0  426.41  4255.3  419.91  4334.0  417.32
  4364.2  416.86  4424.8  414.44  4453.0  414.11  4474.5  413.79  4479.5  412.95
  4525.7  413.82  4545.8  413.32  4625.7  413.78  4651.2  413.24  4687.1  412.85
  4750.3  413.55  4860.1  413.38  4909.0  413.85  4928.1  413.40  4989.7  414.93
  4994.8  410.17  4995.3  409.67  5004.4  409.67  5004.9  410.17  5006.2  414.05
  5011.3  415.13  5030.1  413.98  5060.3  413.74  5164.5  415.25  5362.2  424.31
#Mann=7,-1,0
  3981.2    0.05       0  4088.1    0.07       0  4453.0    0.05       0
  4651.2    0.16       0  4750.3    0.05       0  4994.8    0.05       0
  5004.9    0.05       0
Bank Sta=4994.8,5004.9
Exp/Cntr=0.3,0.1

Type RM Length L Ch R = 1,22761,285,285,285
BEGIN DESCRIPTION:
Mill Creek22761.135
END DESCRIPTION:
XS GIS Cut Line= 3
      2752137.04      6820311.46      2752276.00      6820811.00
      2752351.01      6821086.05
#Sta/Elev= 30
  4481.6  425.66  4522.6  424.10  4543.4  422.34  4564.2  421.83  4584.9  419.70
  4649.0  416.12  4709.5  414.08  4762.1  411.33  4796.3  411.98  4813.3  410.64
  4835.7  412.26  4904.2  410.66  4917.1  412.30  4943.6  412.64  4983.0  414.37
  4989.7  410.42  4992.5  407.89  4993.0  407.39  5002.1  407.39  5002.6  407.89
  5010.5  412.30  5017.4  413.71  5051.9  412.72  5072.7  413.61  5114.1  417.14
  5166.0  419.98  5197.0  422.55  5210.9  425.03  5269.6  427.48  5285.2  427.61
#Mann=3,-1,0
  4481.6    0.05       0  4992.5    0.05       0  5002.6    0.05       0
Bank Sta=4992.5,5002.6
Exp/Cntr=0.3,0.1

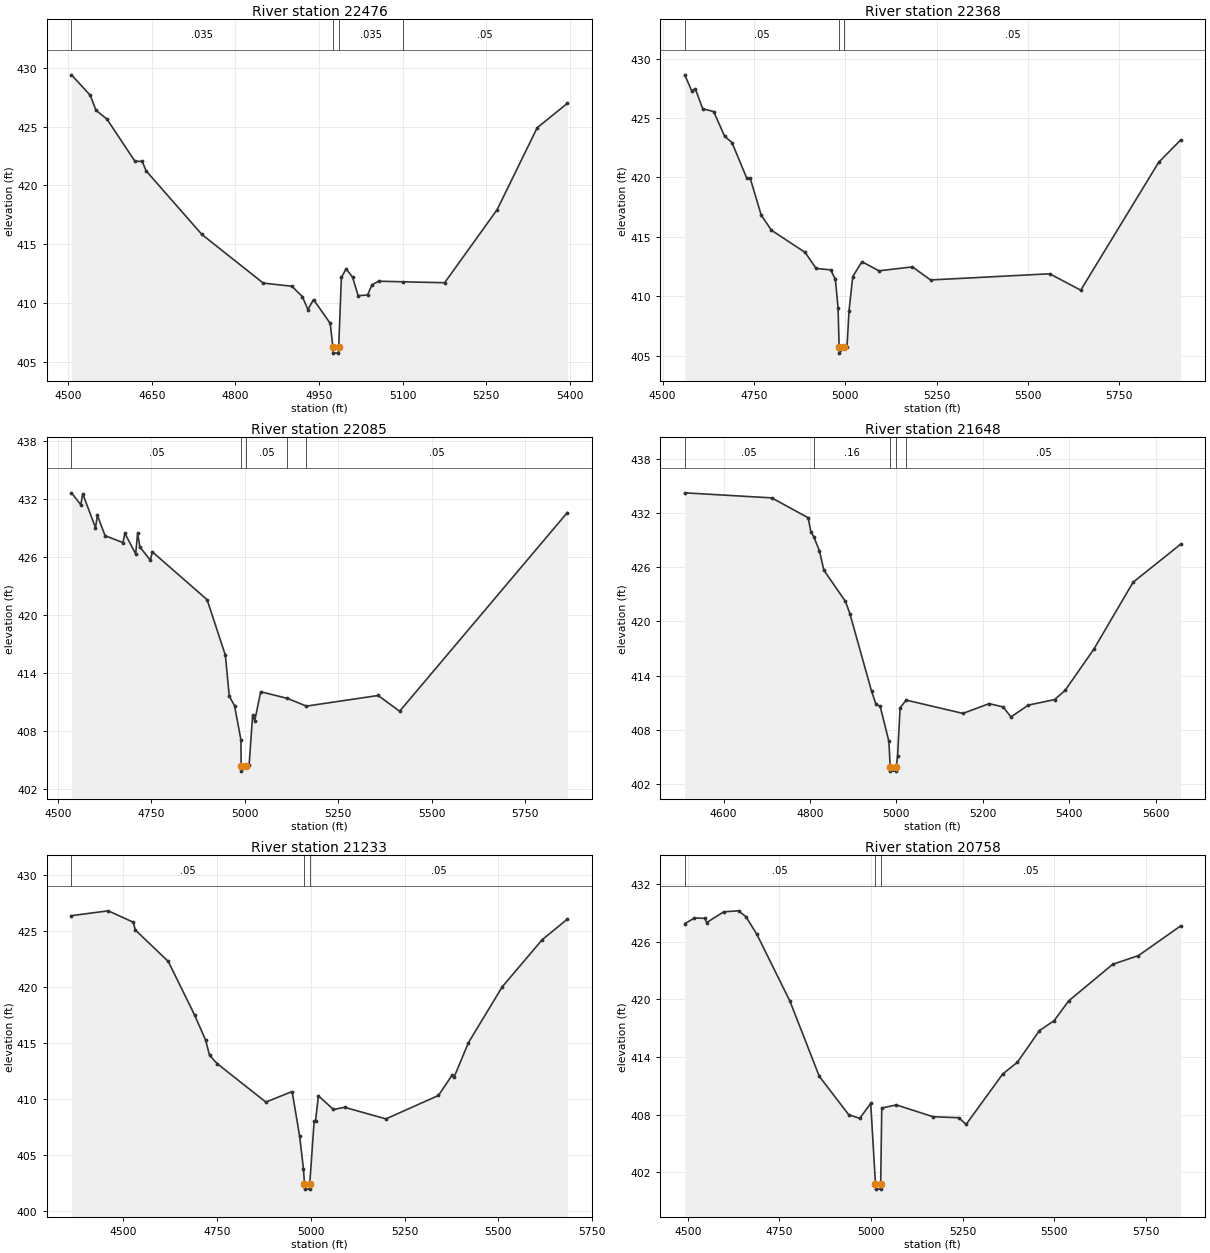
Type RM Length L Ch R = 1,22476,108,108,108
BEGIN DESCRIPTION:
Mapping XS 94bac7dd
END DESCRIPTION:
XS GIS Cut Line= 4
      2752025.69      6820367.25      2752007.10      6820862.93
      2752010.63      6820899.38      2752311.76      6821090.65
#Sta/Elev= 30
  4505.9  429.39  4539.7  427.65  4549.7  426.39  4569.7  425.62  4619.7  422.05
  4632.8  422.04  4639.7  421.24  4739.8  415.83  4849.9  411.70  4901.3  411.43
  4919.9  410.56  4930.0  409.45  4940.0  410.30  4970.0  408.28  4974.8  406.25
  4975.3  405.75  4984.7  405.75  4985.2  406.25  4990.0  412.18  4998.5  412.91
  5010.0  412.21  5020.1  410.63  5036.9  410.69  5044.9  411.56  5056.8  411.86
  5100.3  411.81  5175.2  411.73  5269.4  417.94  5341.1  424.89  5395.3  426.97
#Mann=4,-1,0
  4505.9   0.035       0  4974.8   0.035       0  4985.2   0.035       0
  5100.3    0.05       0
Bank Sta=4974.8,4985.2
Exp/Cntr=0.3,0.1

Type RM Length L Ch R = 1,22368,283,283,283
BEGIN DESCRIPTION:
Mapping XS b4d33517
END DESCRIPTION:
XS GIS Cut Line= 5
      2751925.14      6820421.93      2751898.99      6820865.51
      2751886.46      6820927.55      2751560.04      6821296.34
      2751340.15      6821578.29
#Sta/Elev= 30
  4560.5  428.64  4579.6  427.30  4589.6  427.46  4609.7  425.78  4639.7  425.55
  4669.8  423.47  4689.8  422.94  4729.9  419.98  4739.9  419.92  4769.9  416.83
  4797.9  415.56  4890.1  413.69  4920.2  412.34  4960.3  412.22  4973.0  411.41
  4980.3  409.05  4983.3  405.71  4983.8  405.21  4997.3  405.71  5004.8  405.75
  5010.4  408.79  5020.6  411.66  5045.7  412.91  5092.1  412.14  5184.1  412.47
  5233.5  411.37  5559.7  411.89  5644.7  410.51  5858.2  421.28  5918.2  423.15
#Mann=3,-1,0
  4560.5    0.05       0  4983.3    0.05       0  4997.3    0.05       0
Bank Sta=4983.3,4997.3
Exp/Cntr=0.3,0.1

Type RM Length L Ch R = 1,22085,437,437,437
BEGIN DESCRIPTION:
Mill Creek22084.891
END DESCRIPTION:
XS GIS Cut Line= 3
      2751778.46      6820514.47      2751653.25      6820960.94
      2751226.00      6821710.99
#Sta/Elev= 30
  4536.3  432.67  4561.3  431.43  4566.5  432.57  4600.6  429.06  4605.8  430.33
  4626.2  428.23  4674.0  427.51  4679.2  428.47  4708.1  426.34  4713.3  428.47
  4719.6  427.05  4747.4  425.68  4752.5  426.56  4899.3  421.59  4948.1  415.84
  4958.5  411.60  4972.7  410.60  4989.7  407.08  4990.4  404.32  4990.9  403.82
  5004.5  404.32  5011.6  404.44  5021.0  409.59  5026.8  409.06  5042.6  412.05
  5114.0  411.36  5165.0  410.56  5356.8  411.66  5414.4  410.03  5863.2  430.63
#Mann=5,-1,0
  4536.3    0.05       0  4990.4    0.05       0  5004.5    0.05       0
  5114.0    0.16       0  5165.0    0.05       0
Bank Sta=4990.4,5004.5
Exp/Cntr=0.3,0.1

Type RM Length L Ch R = 1,21648,415,415,415
BEGIN DESCRIPTION:
Mapping XS d8526861
END DESCRIPTION:
XS GIS Cut Line= 3
      2751304.59      6820510.15      2751263.18      6821007.93
      2751174.18      6821649.99
#Sta/Elev= 30
  4510.2  434.23  4711.7  433.67  4795.9  431.47  4802.1  429.91  4808.8  429.39
  4822.1  427.79  4832.2  425.67  4882.3  422.20  4892.4  420.86  4942.5  412.29
  4952.6  410.86  4962.6  410.58  4982.7  406.73  4985.7  403.92  4986.2  403.42
  4999.3  403.42  4999.8  403.92  5002.8  405.04  5008.7  410.45  5023.0  411.28
  5154.1  409.81  5214.7  410.89  5247.1  410.53  5265.2  409.42  5305.6  410.73
  5366.2  411.34  5390.6  412.36  5457.0  416.92  5547.9  424.33  5657.9  428.54
#Mann=5,-1,0
  4510.2    0.05       0  4808.8    0.16       0  4985.7    0.07       0
  4999.8    0.16       0  5023.0    0.05       0
Bank Sta=4985.7,4999.8
Exp/Cntr=0.3,0.1

Type RM Length L Ch R = 1,21233,475,475,475
BEGIN DESCRIPTION:
Mill Creek21233.14
END DESCRIPTION:
XS GIS Cut Line= 3
      2750939.54      6820373.03      2750906.22      6821023.36
      2750878.26      6821694.60
#Sta/Elev= 30
  4361.3  426.36  4459.4  426.79  4526.4  425.77  4531.4  425.09  4619.6  422.27
  4689.7  417.50  4719.2  415.25  4729.7  413.89  4749.8  413.16  4879.9  409.72
  4950.0  410.66  4970.1  406.67  4980.1  403.79  4983.0  402.45  4983.5  401.95
  4996.6  401.95  4997.1  402.45  5008.8  408.05  5012.5  408.05  5020.1  410.28
  5060.2  409.06  5090.2  409.25  5200.3  408.22  5340.4  410.31  5376.8  412.12
  5381.8  411.92  5420.5  415.03  5510.6  420.01  5617.1  424.21  5684.3  426.05
#Mann=3,-1,0
  4361.3    0.05       0  4983.0    0.05       0  4997.1    0.05       0
Bank Sta=4983,4997.1
Exp/Cntr=0.3,0.1

Type RM Length L Ch R = 1,20758,661,661,661
BEGIN DESCRIPTION:
Mill Creek20758.29
END DESCRIPTION:
XS GIS Cut Line= 3
      2750457.82      6820354.42      2750486.44      6820874.69
      2750495.79      6821706.08
#Sta/Elev= 30
  4491.7  427.86  4518.3  428.47  4546.5  428.43  4551.5  427.99  4598.4  429.11
  4638.5  429.21  4658.5  428.61  4688.6  426.76  4778.7  419.81  4858.8  411.99
  4939.0  408.00  4969.0  407.62  4999.0  409.18  5012.0  400.76  5012.5  400.26
  5025.7  400.26  5026.2  400.76  5029.1  408.70  5069.1  409.02  5169.1  407.79
  5239.1  407.69  5259.1  406.99  5359.1  412.24  5399.1  413.46  5459.1  416.75
  5499.1  417.78  5539.1  419.85  5659.1  423.65  5729.1  424.55  5844.2  427.64
#Mann=3,-1,0
  4491.7    0.05       0  5012.0    0.05       0  5026.2    0.05       0
Bank Sta=5012,5026.2
Exp/Cntr=0.3,0.1

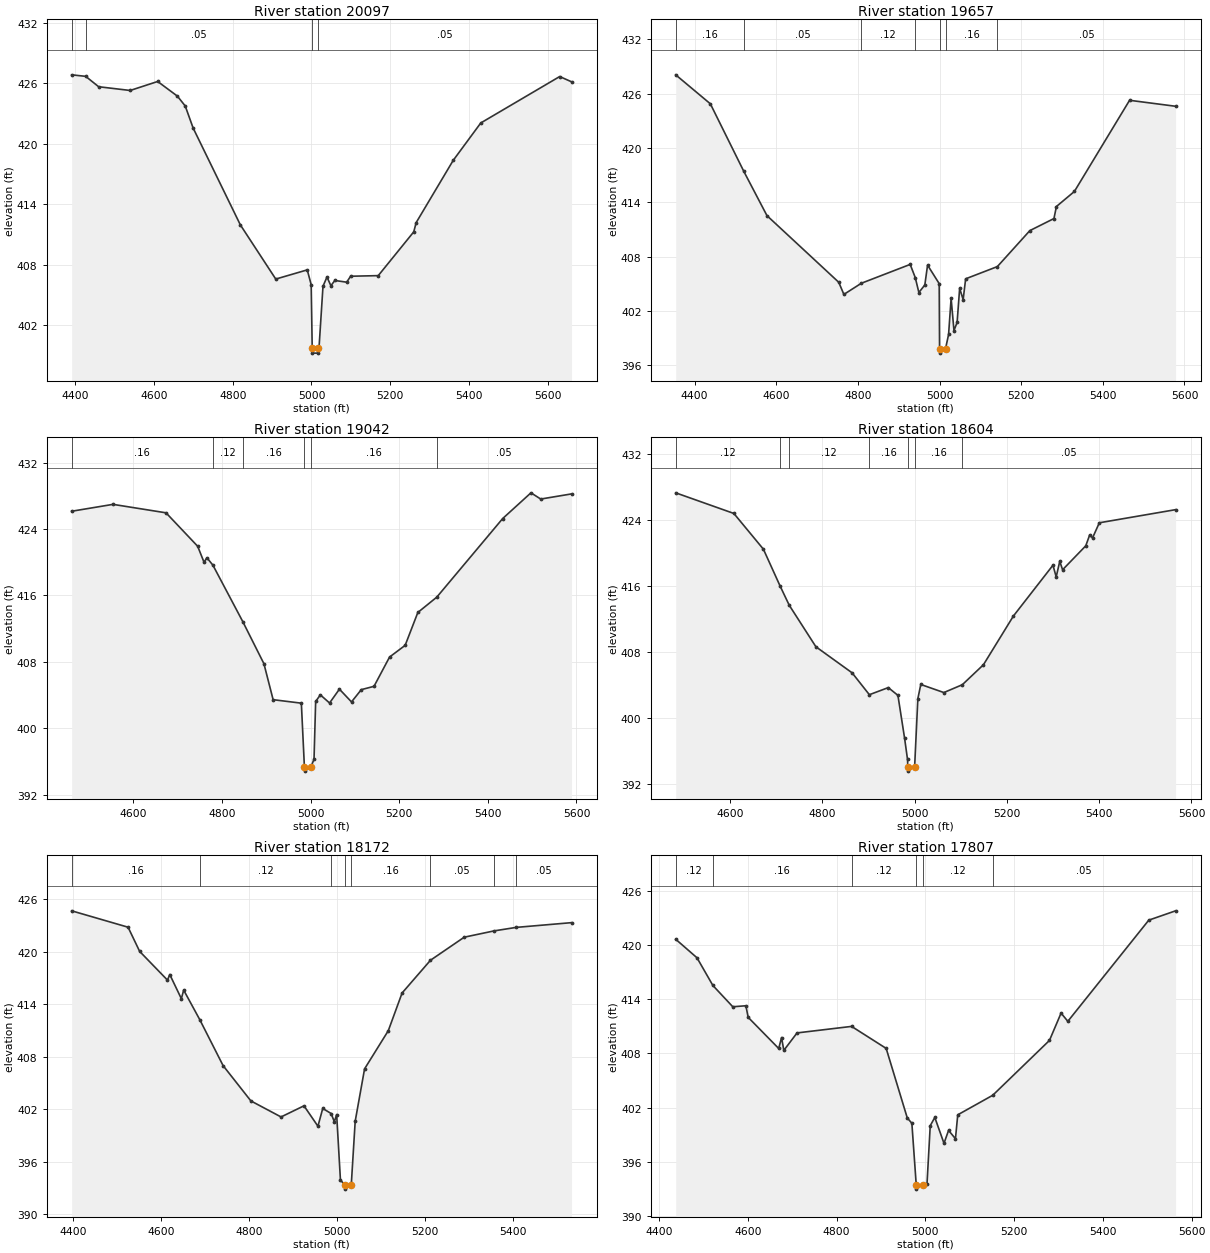
Type RM Length L Ch R = 1,20097,440,440,440
BEGIN DESCRIPTION:
Mill Creek20097.08
END DESCRIPTION:
XS GIS Cut Line= 3
      2750047.32      6820552.40      2750044.06      6821175.76
      2750087.31      6821821.04
#Sta/Elev= 30
  4390.7  426.83  4426.3  426.68  4459.3  425.65  4539.3  425.28  4609.3  426.17
  4659.3  424.72  4679.3  423.74  4699.3  421.56  4819.3  411.96  4909.3  406.59
  4989.3  407.50  4999.3  406.03  5001.9  399.75  5002.4  399.25  5016.0  399.25
  5016.5  399.75  5019.3  399.83  5029.3  405.88  5039.4  406.79  5049.4  405.93
  5059.4  406.45  5089.5  406.28  5099.5  406.87  5169.7  406.93  5259.9  411.27
  5266.1  412.19  5360.1  418.35  5430.2  422.06  5630.7  426.66  5660.8  426.14
#Mann=4,-1,0
  4390.7    0.16       0  4426.3    0.05       0  5001.9    0.05       0
  5016.5    0.05       0
Bank Sta=5001.9,5016.5
Exp/Cntr=0.3,0.1

Type RM Length L Ch R = 1,19657,615,615,615
BEGIN DESCRIPTION:
Mill Creek19657.45
END DESCRIPTION:
XS GIS Cut Line= 3
      2749983.28      6820480.26      2749638.96      6821043.47
      2749310.70      6821502.69
#Sta/Elev= 30
  4353.7  428.07  4438.6  424.87  4520.5  417.42  4577.3  412.53  4753.1  405.18
  4765.7  403.84  4808.5  405.07  4928.1  407.15  4940.6  405.69  4949.4  404.05
  4964.0  404.88  4970.7  407.07  4999.2  405.03  5000.1  397.86  5000.6  397.36
  5014.8  397.86  5022.2  399.42  5028.4  403.40  5035.4  399.85  5043.1  400.75
  5049.3  404.51  5057.9  403.27  5064.0  405.56  5141.7  406.91  5221.3  410.88
  5280.3  412.21  5286.4  413.54  5330.4  415.20  5465.6  425.26  5578.3  424.60
#Mann=7,-1,0
  4353.7    0.16       0  4520.5    0.05       0  4808.5    0.12       0
  4940.6    0.16       0  5000.1    0.07       0  5014.8    0.16       0
  5141.7    0.05       0
Bank Sta=5000.1,5014.8
Exp/Cntr=0.3,0.1

Type RM Length L Ch R = 1,19042,438,438,438
BEGIN DESCRIPTION:
Mill Creek19042.25
END DESCRIPTION:
XS GIS Cut Line= 3
      2749855.02      6820129.10      2749496.45      6820551.67
      2749129.81      6820993.32
#Sta/Elev= 30
  4460.6  426.15  4553.9  426.98  4673.6  425.96  4745.0  421.93  4759.3  420.01
  4765.9  420.54  4779.4  419.65  4847.0  412.83  4894.5  407.78  4915.3  403.44
  4979.0  403.02  4985.9  395.33  4986.4  394.83  5000.6  395.33  5007.6  396.27
  5011.3  403.23  5021.9  404.02  5042.7  403.04  5064.9  404.71  5092.2  403.17
  5114.3  404.65  5143.0  405.05  5178.1  408.58  5213.3  409.99  5241.9  413.95
  5284.7  415.80  5433.4  425.27  5497.2  428.37  5519.3  427.62  5588.8  428.24
#Mann=6,-1,0
  4460.6    0.16       0  4779.4    0.12       0  4847.0    0.16       0
  4985.9    0.07       0  5000.6    0.16       0  5284.7    0.05       0
Bank Sta=4985.9,5000.6
Exp/Cntr=0.3,0.1

Type RM Length L Ch R = 1,18604,432,432,432
BEGIN DESCRIPTION:
Mill Creek18603.54
END DESCRIPTION:
XS GIS Cut Line= 3
      2749570.02      6819878.02      2749233.47      6820301.15
      2748914.18      6820740.30
#Sta/Elev= 30
  4482.0  427.34  4608.1  424.84  4672.1  420.51  4708.1  416.07  4728.1  413.72
  4785.9  408.69  4864.4  405.53  4901.8  402.88  4942.8  403.74  4963.7  402.80
  4978.1  397.63  4984.5  395.04  4985.2  394.12  4985.7  393.62  4999.9  394.12
  5006.9  402.40  5013.3  404.12  5063.3  403.14  5103.3  404.09  5149.1  406.51
  5214.0  412.41  5299.8  418.57  5306.8  417.15  5314.5  419.04  5320.7  418.02
  5370.9  420.92  5379.4  422.24  5385.6  421.88  5400.3  423.71  5565.6  425.30
#Mann=7,-1,0
  4482.0    0.12       0  4708.1    0.16       0  4728.1    0.12       0
  4901.8    0.16       0  4985.2    0.07       0  4999.9    0.16       0
  5103.3    0.05       0
Bank Sta=4985.2,4999.9
Exp/Cntr=0.3,0.1

Type RM Length L Ch R = 1,18172,365,365,365
BEGIN DESCRIPTION:
Mill Creek18171.67
END DESCRIPTION:
XS GIS Cut Line= 3
      2749150.34      6819540.62      2748955.51      6820123.01
      2748776.16      6820612.26
#Sta/Elev= 30
  4397.5  424.65  4525.6  422.78  4551.9  420.02  4615.1  416.74  4620.3  417.38
  4646.6  414.62  4651.9  415.60  4688.5  412.22  4741.4  406.98  4804.5  402.95
  4873.0  401.12  4925.1  402.39  4956.8  400.06  4967.7  402.09  4986.8  401.51
  4994.0  400.57  4999.3  401.39  5007.9  393.91  5017.7  393.38  5018.2  392.88
  5032.5  393.38  5041.4  400.63  5062.7  406.61  5116.6  410.97  5147.9  415.27
  5212.4  419.01  5289.0  421.64  5356.8  422.36  5407.2  422.76  5532.7  423.30
#Mann=8,-1,0
  4397.5    0.16       0  4688.5    0.12       0  4986.8    0.16       0
  5017.7    0.07       0  5032.5    0.16       0  5212.4    0.05       0
  5356.8    0.16       0  5407.2    0.05       0
Bank Sta=5017.7,5032.5
Exp/Cntr=0.3,0.1

Type RM Length L Ch R = 1,17807,282,282,282
BEGIN DESCRIPTION:
Mill Creek17806.98
END DESCRIPTION:
XS GIS Cut Line= 3
      2748832.58      6819366.74      2748687.11      6819913.93
      2748546.19      6820456.01
#Sta/Elev= 30
  4437.5  420.62  4485.5  418.57  4521.3  415.51  4566.1  413.16  4595.6  413.27
  4600.8  411.99  4669.6  408.55  4676.0  409.76  4681.1  408.34  4710.9  410.27
  4833.8  410.99  4911.7  408.56  4959.3  400.87  4969.6  400.29  4979.4  393.51
  4979.9  393.01  4994.3  393.51  5003.7  393.59  5011.0  400.02  5021.3  400.93
  5042.0  398.07  5052.3  399.50  5067.8  398.58  5073.0  401.22  5151.8  403.38
  5279.6  409.44  5305.8  412.46  5321.0  411.55  5503.4  422.73  5563.8  423.76
#Mann=6,-1,0
  4437.5    0.12       0  4521.3    0.16       0  4833.8    0.12       0
  4979.4    0.07       0  4994.3    0.12       0  5151.8    0.05       0
Bank Sta=4979.4,4994.3
Exp/Cntr=0.3,0.1

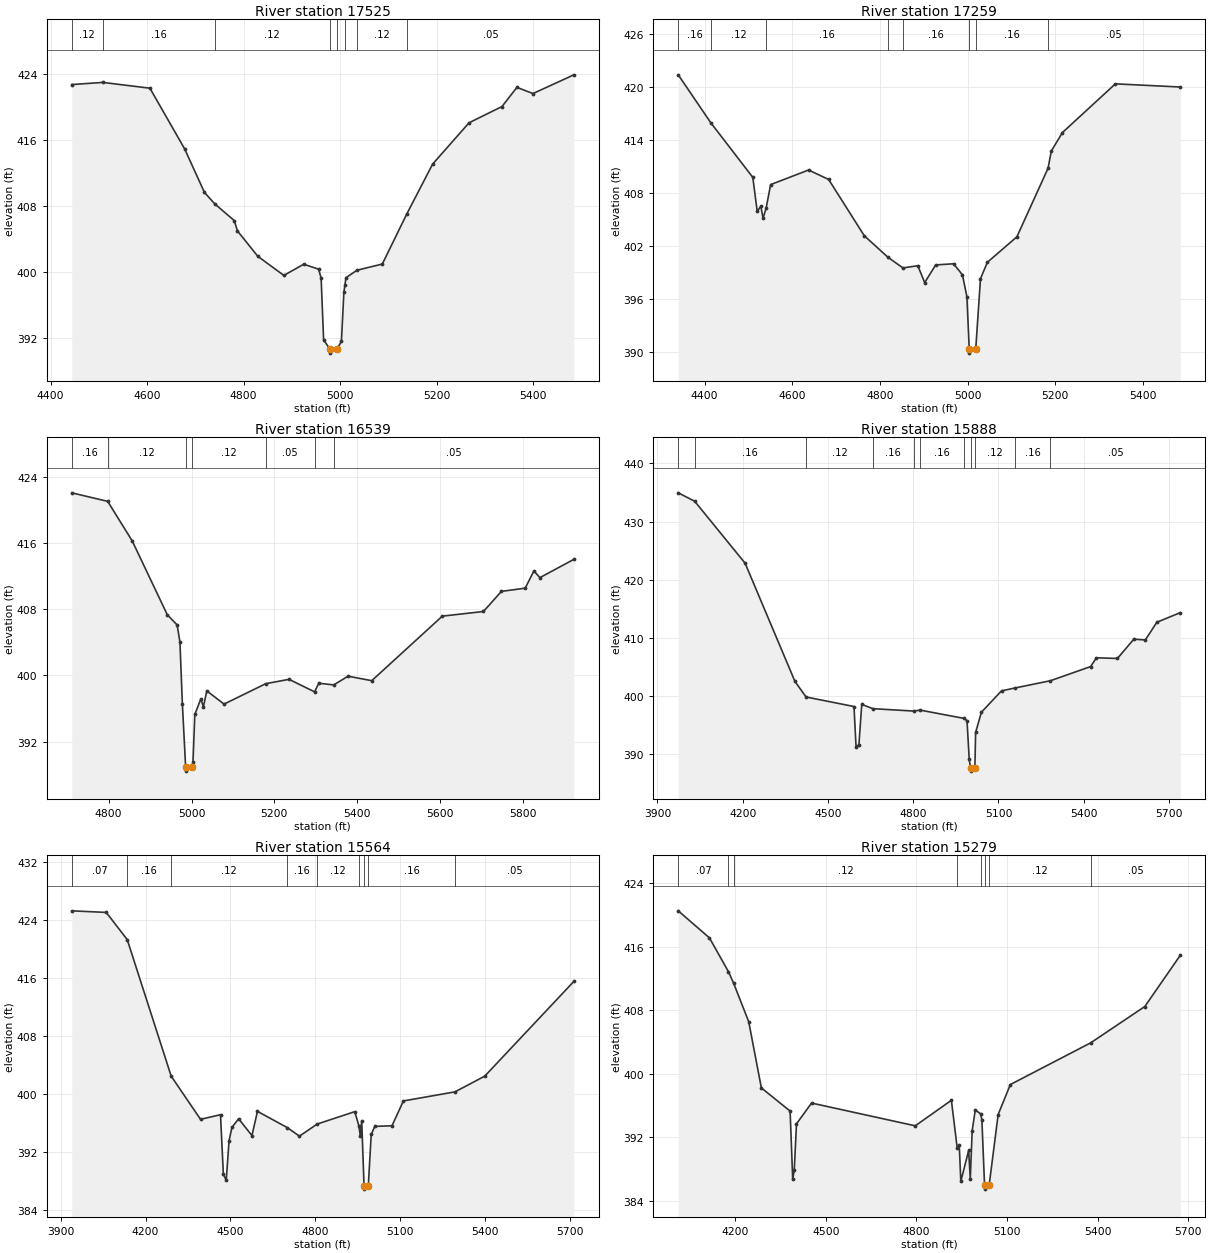
Type RM Length L Ch R = 1,17525,266,266,266
BEGIN DESCRIPTION:
Mill Creek17525.23
END DESCRIPTION:
XS GIS Cut Line= 3
      2748551.37      6819323.59      2748419.00      6819876.31
      2748310.98      6820335.84
#Sta/Elev= 30
  4443.9  422.75  4508.1  423.01  4605.8  422.31  4677.7  414.96  4718.9  409.67
  4740.3  408.28  4780.6  406.26  4787.3  405.00  4829.4  401.93  4883.4  399.61
  4924.5  400.97  4955.4  400.37  4960.6  399.28  4965.8  391.79  4978.8  390.69
  4979.3  390.19  4993.7  390.69  5002.7  391.63  5007.8  397.59  5009.8  398.40
  5012.1  399.33  5034.9  400.24  5087.4  400.99  5138.2  407.07  5191.7  413.11
  5267.2  418.12  5335.5  420.09  5366.3  422.41  5399.6  421.66  5484.3  423.93
#Mann=8,-1,0
  4443.9    0.12       0  4508.1    0.16       0  4740.3    0.12       0
  4978.8    0.07       0  4993.7    0.12       0  5009.8    0.16       0
  5034.9    0.12       0  5138.2    0.05       0
Bank Sta=4978.8,4993.7
Exp/Cntr=0.3,0.1

Type RM Length L Ch R = 1,17259,720,720,720
BEGIN DESCRIPTION:
Mill Creek17258.59
END DESCRIPTION:
XS GIS Cut Line= 3
      2748337.09      6819063.89      2748211.05      6819720.65
      2748080.96      6820179.83
#Sta/Elev= 30
  4339.7  421.34  4414.1  415.91  4509.9  409.74  4520.0  405.89  4528.2  406.48
  4533.3  405.12  4540.2  406.22  4550.6  408.92  4637.2  410.57  4683.0  409.50
  4764.4  403.13  4818.8  400.68  4852.7  399.49  4886.6  399.74  4902.2  397.83
  4927.3  399.83  4968.1  399.96  4988.4  398.71  4998.6  396.23  5003.9  390.35
  5004.4  389.85  5018.8  390.35  5029.6  398.27  5045.3  400.13  5112.7  403.01
  5183.8  410.77  5191.4  412.73  5216.7  414.81  5337.5  420.32  5485.7  419.96
#Mann=8,-1,0
  4339.7    0.16       0  4414.1    0.12       0  4540.2    0.16       0
  4818.8    0.12       0  4852.7    0.16       0  5003.9    0.07       0
  5018.8    0.16       0  5183.8    0.05       0
Bank Sta=5003.9,5018.8
Exp/Cntr=0.3,0.1

Type RM Length L Ch R = 1,16539,651,651,651
BEGIN DESCRIPTION:
Mill Creek16539.142
END DESCRIPTION:
XS GIS Cut Line= 3
      2748200.96      6819036.03      2747956.56      6819190.45
      2747382.11      6819912.91
#Sta/Elev= 30
  4710.9  422.07  4797.6  421.04  4856.7  416.27  4941.5  407.34  4965.2  406.11
  4972.0  404.06  4977.9  396.59  4985.8  388.94  4986.3  388.44  5000.7  388.94
  5003.5  389.50  5008.0  395.30  5022.4  397.15  5028.8  396.23  5036.9  398.14
  5078.5  396.54  5179.4  399.01  5235.5  399.53  5297.1  398.02  5307.3  399.06
  5343.3  398.86  5378.0  399.91  5435.1  399.37  5605.5  407.17  5704.8  407.73
  5748.1  410.16  5805.6  410.55  5826.6  412.64  5841.0  411.82  5923.0  414.03
#Mann=7,-1,0
  4710.9    0.16       0  4797.6    0.12       0  4985.8    0.07       0
  5000.7    0.12       0  5179.4    0.05       0  5297.1    0.16       0
  5343.3    0.05       0
Bank Sta=4985.8,5000.7
Exp/Cntr=0.3,0.1

Type RM Length L Ch R = 1,15888,324,324,324
BEGIN DESCRIPTION:
Mill Creek15887.788
END DESCRIPTION:
XS GIS Cut Line= 3
      2747501.00      6818135.96      2747451.01      6819161.55
      2747336.43      6819892.62
#Sta/Elev= 30
  3973.2  434.94  4031.0  433.49  4208.5  422.83  4383.9  402.48  4423.0  399.80
  4591.7  398.16  4599.0  391.19  4609.0  391.62  4619.0  398.53  4658.0  397.79
  4801.3  397.38  4824.8  397.54  4977.5  396.13  4989.4  395.74  4997.2  389.05
  5002.0  387.54  5002.5  387.04  5017.1  387.54  5019.7  393.69  5039.9  397.17
  5110.8  400.86  5157.2  401.34  5283.0  402.60  5424.6  405.04  5444.8  406.55
  5518.7  406.43  5576.3  409.75  5616.9  409.62  5657.4  412.66  5740.0  414.32
#Mann=11,-1,0
  3973.2    0.07       0  4031.0    0.16       0  4423.0    0.12       0
  4658.0    0.16       0  4801.3    0.12       0  4824.8    0.16       0
  4977.5    0.12       0  5002.0    0.07       0  5017.1    0.12       0
  5157.2    0.16       0  5283.0    0.05       0
Bank Sta=5002,5017.1
Exp/Cntr=0.3,0.1

Type RM Length L Ch R = 1,15564,285,285,285
BEGIN DESCRIPTION:
Mill Creek15563.993
END DESCRIPTION:
XS GIS Cut Line= 3
      2747321.90      6818110.26      2747175.93      6819161.18
      2747059.25      6819865.17
#Sta/Elev= 30
  3939.0  425.31  4060.9  425.09  4135.0  421.34  4290.5  402.49  4394.1  396.54
  4464.7  397.18  4474.8  388.97  4484.9  388.12  4495.0  393.59  4505.1  395.42
  4528.7  396.62  4575.8  394.30  4595.3  397.64  4700.3  395.41  4743.7  394.22
  4806.5  395.89  4939.2  397.60  4953.6  395.68  4958.8  394.26  4963.8  396.34
  4972.0  387.41  4972.5  386.91  4987.2  387.41  4997.4  394.45  5010.0  395.57
  5070.8  395.65  5111.3  399.08  5293.4  400.33  5398.7  402.50  5713.6  415.57
#Mann=9,-1,0
  3939.0    0.07       0  4135.0    0.16       0  4290.5    0.12       0
  4700.3    0.16       0  4806.5    0.12       0  4953.6    0.16       0
  4972.0    0.07       0  4987.2    0.16       0  5293.4    0.05       0
Bank Sta=4972,4987.2
Exp/Cntr=0.3,0.1

Type RM Length L Ch R = 1,15279,632,632,632
BEGIN DESCRIPTION:
Mill Creek15278.643
END DESCRIPTION:
XS GIS Cut Line= 3
      2747245.46      6818170.80      2746923.67      6819105.25
      2746670.49      6819729.89
#Sta/Elev= 30
  4011.7  420.54  4115.0  417.13  4178.1  412.86  4195.3  411.39  4245.1  406.56
  4286.9  398.22  4382.1  395.30  4390.7  386.70  4395.9  387.90  4403.2  393.69
  4453.1  396.31  4796.5  393.44  4916.1  396.66  4935.4  390.61  4942.1  390.99
  4947.3  386.44  4973.3  390.33  4978.6  386.77  4984.9  392.83  4995.1  395.43
  5012.7  394.96  5017.0  394.21  5025.9  385.96  5026.4  385.46  5041.1  385.96
  5070.9  394.86  5111.2  398.64  5377.7  403.91  5556.5  408.48  5674.0  414.94
#Mann=8,-1,0
  4011.7    0.07       0  4178.1    0.16       0  4195.3    0.12       0
  4935.4    0.16       0  5012.7    0.12       0  5025.9    0.07       0
  5041.1    0.12       0  5377.7    0.05       0
Bank Sta=5025.9,5041.1
Exp/Cntr=0.3,0.1