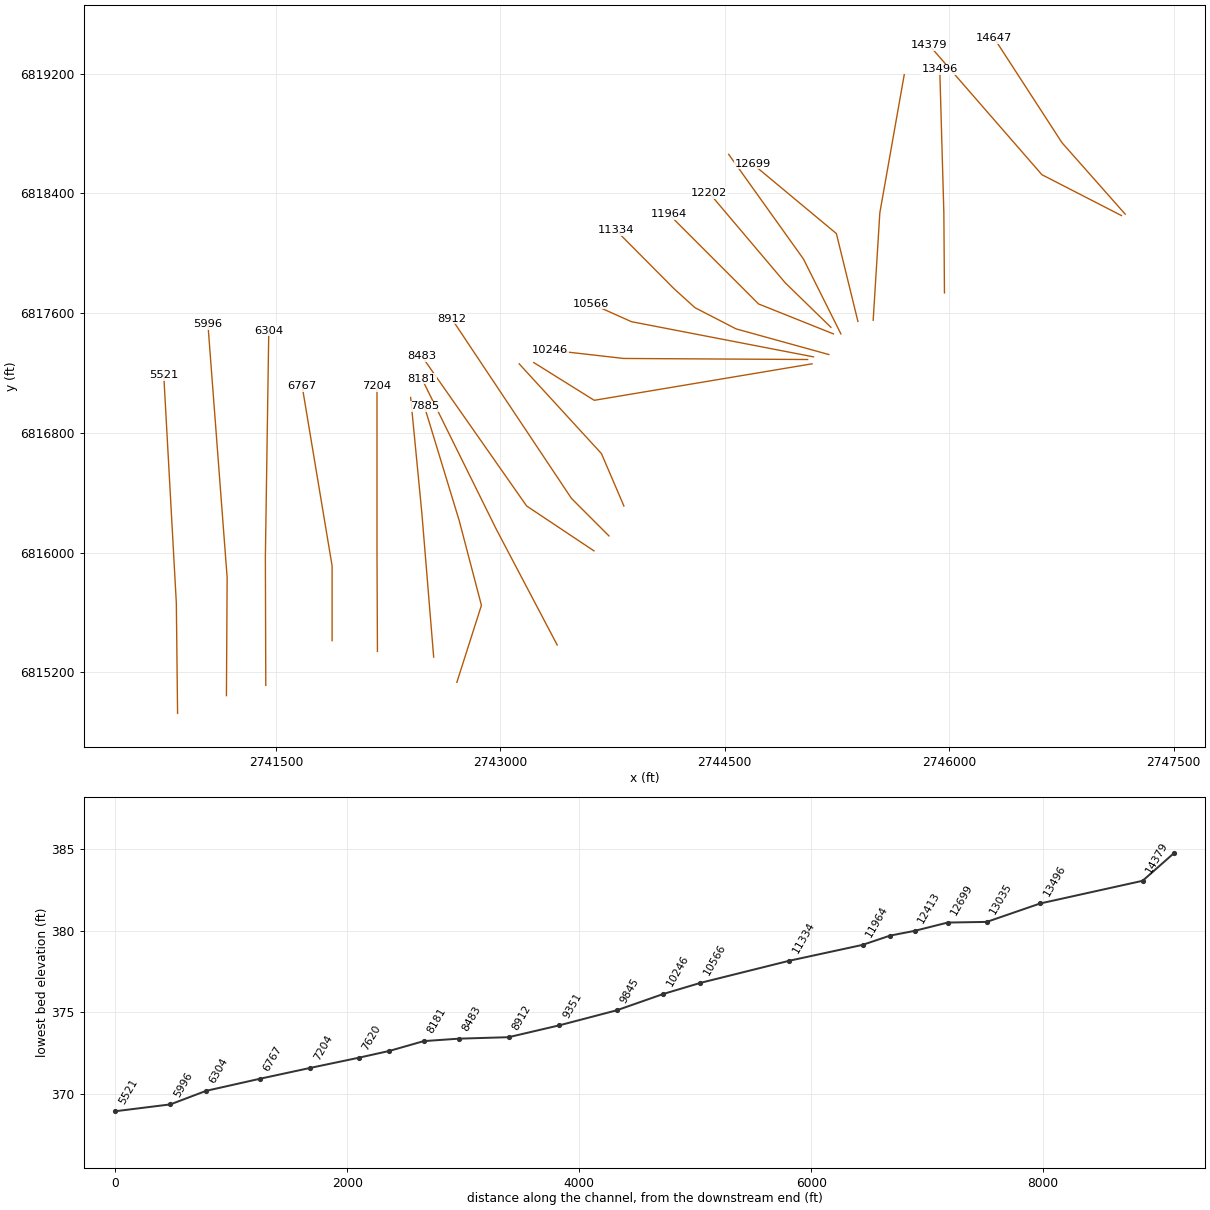
HEC-RAS study Mill Creek.prj: Mill Creek Base Level Engineering

--- Mill Creek.g01 (geometry) --- (continued)

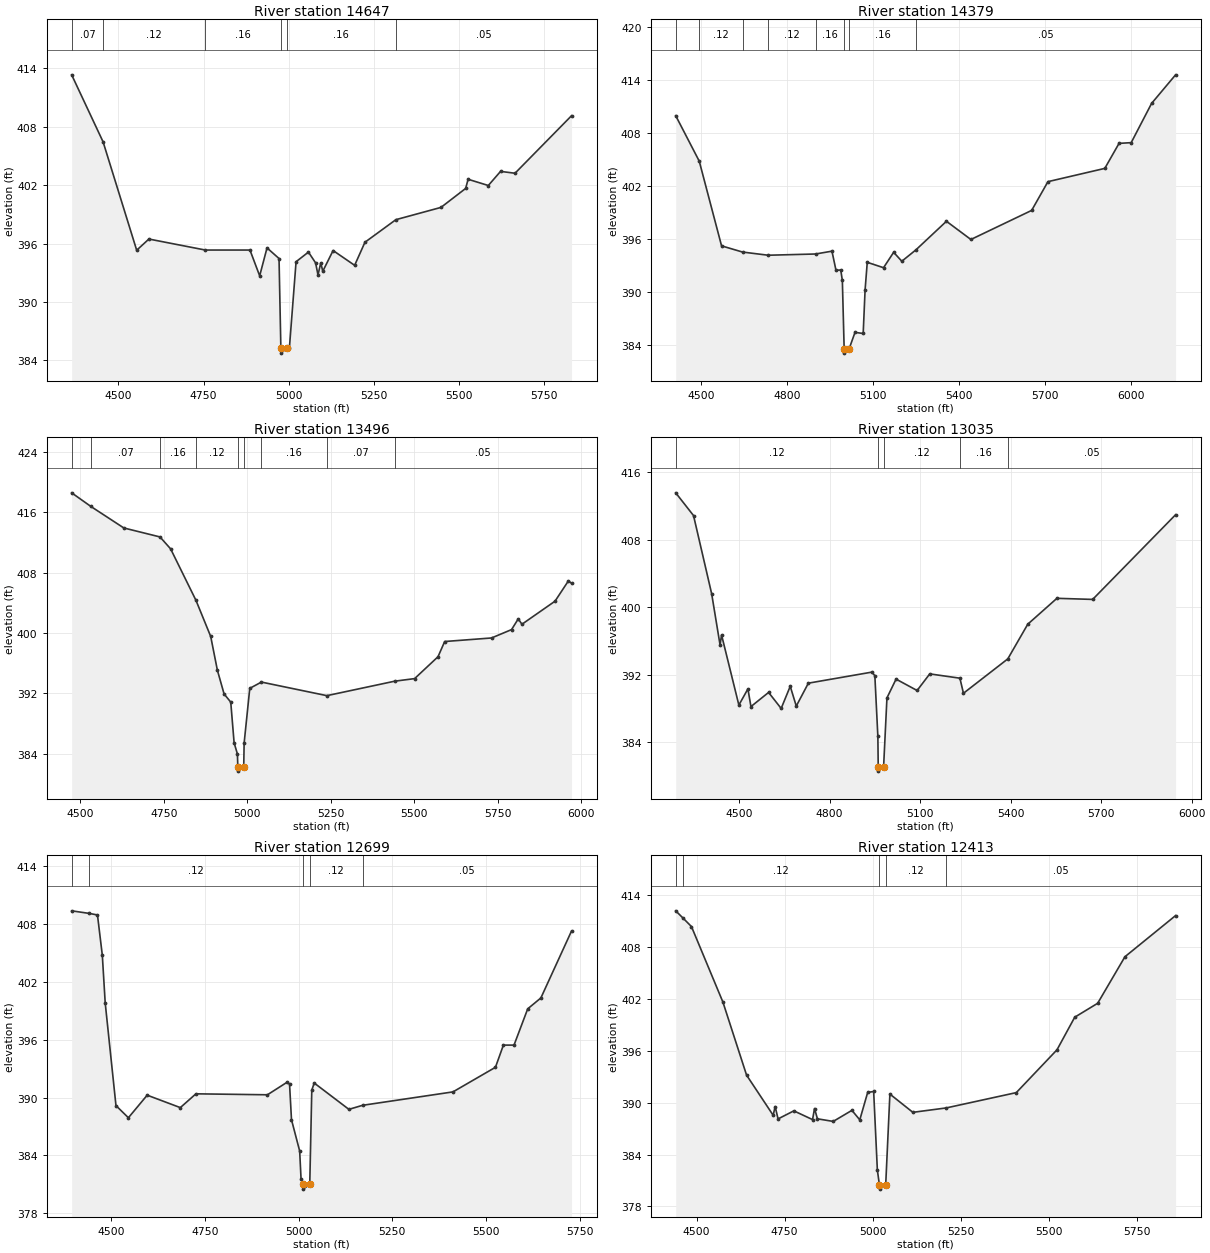
Type RM Length L Ch R = 1,14647,268,268,268
BEGIN DESCRIPTION:
Mill Creek14647.169
END DESCRIPTION:
XS GIS Cut Line= 3
      2747175.99      6818261.01      2746753.53      6818738.57
      2746300.99      6819436.02
#Sta/Elev= 30
  4362.4  413.34  4454.8  406.45  4553.5  395.32  4589.4  396.47  4755.2  395.34
  4886.4  395.34  4914.9  392.69  4936.5  395.56  4971.8  394.47  4977.2  385.25
  4977.7  384.75  4994.7  385.25  5002.3  385.30  5021.9  394.14  5058.2  395.13
  5079.3  394.02  5086.3  392.78  5094.4  394.02  5100.4  393.16  5130.7  395.29
  5194.0  393.77  5224.3  396.14  5315.2  398.46  5447.7  399.72  5520.3  401.67
  5527.4  402.61  5586.8  401.97  5622.8  403.42  5665.3  403.23  5831.4  409.14
#Mann=6,-1,0
  4362.4    0.07       0  4454.8    0.12       0  4755.2    0.16       0
  4977.2    0.07       0  4994.7    0.16       0  5315.2    0.05       0
Bank Sta=4977.2,4994.7
Exp/Cntr=0.3,0.1

Type RM Length L Ch R = 1,14379,883,883,883
BEGIN DESCRIPTION:
Mill Creek14379.07
END DESCRIPTION:
XS GIS Cut Line= 3
      2747150.92      6818251.64      2746619.52      6818524.64
      2745866.66      6819389.82
#Sta/Elev= 30
  4410.1  409.92  4492.2  404.78  4570.1  395.20  4643.2  394.50  4732.9  394.14
  4898.3  394.28  4955.3  394.60  4969.4  392.44  4986.0  392.47  4991.6  391.29
  4997.9  383.57  4998.4  383.07  5015.4  383.57  5035.8  385.42  5064.3  385.29
  5070.9  390.20  5078.5  393.34  5135.3  392.73  5170.6  394.47  5199.1  393.46
  5248.4  394.75  5354.8  397.98  5440.1  395.92  5652.2  399.21  5709.0  402.46
  5907.4  403.96  5957.1  406.79  5999.5  406.87  6070.7  411.31  6154.4  414.54
#Mann=8,-1,0
  4410.1    0.07       0  4492.2    0.12       0  4643.2    0.16       0
  4732.9    0.12       0  4898.3    0.16       0  4997.9    0.07       0
  5015.4    0.16       0  5248.4    0.05       0
Bank Sta=4997.9,5015.4
Exp/Cntr=0.3,0.1

Type RM Length L Ch R = 1,13496,461,461,461
BEGIN DESCRIPTION:
Mill Creek13496.25
END DESCRIPTION:
XS GIS Cut Line= 3
      2745968.09      6817734.93      2745964.08      6818269.93
      2745936.65      6819230.43
#Sta/Elev= 30
  4474.5  418.59  4531.8  416.79  4630.6  413.93  4738.8  412.74  4770.6  411.16
  4846.6  404.32  4890.6  399.54  4910.6  395.06  4930.6  391.92  4950.6  390.83
  4960.6  385.45  4970.6  383.94  4971.7  382.18  4972.2  381.68  4989.4  382.18
  4990.6  385.38  5007.5  392.66  5042.4  393.49  5238.2  391.69  5441.4  393.61
  5500.8  393.95  5570.8  396.85  5590.8  398.87  5730.9  399.34  5790.9  400.45
  5810.9  401.87  5822.0  401.16  5921.0  404.22  5961.0  406.91  5970.4  406.59
#Mann=9,-1,0
  4474.5    0.16       0  4531.8    0.07       0  4738.8    0.16       0
  4846.6    0.12       0  4971.7    0.07       0  4989.4    0.12       0
  5042.4    0.16       0  5238.2    0.07       0  5441.4    0.05       0
Bank Sta=4971.7,4989.4
Exp/Cntr=0.3,0.1

Type RM Length L Ch R = 1,13035,336,336,336
BEGIN DESCRIPTION:
Mill Creek13035.17
END DESCRIPTION:
XS GIS Cut Line= 3
      2745491.73      6817552.05      2745536.28      6818270.07
      2745699.38      6819193.57
#Sta/Elev= 30
  4289.6  413.58  4348.7  410.88  4408.8  401.60  4436.6  395.53  4441.6  396.71
  4499.0  388.39  4529.0  390.31  4539.0  388.21  4597.5  389.89  4639.2  387.99
  4669.3  390.62  4689.3  388.27  4729.4  390.99  4939.8  392.30  4949.8  391.88
  4959.8  384.66  4961.0  381.05  4961.5  380.55  4978.8  381.05  4989.9  389.24
  5020.1  391.47  5089.9  390.12  5131.8  392.09  5231.8  391.58  5243.5  389.79
  5390.5  393.87  5456.8  397.99  5553.4  401.06  5671.9  400.93  5946.8  410.98
#Mann=5,-1,0
  4289.6    0.12       0  4961.0    0.07       0  4978.8    0.12       0
  5231.8    0.16       0  5390.5    0.05       0
Bank Sta=4961,4978.8
Exp/Cntr=0.3,0.1

Type RM Length L Ch R = 1,12699,286,286,286
BEGIN DESCRIPTION:
Mill Creek12698.658
END DESCRIPTION:
XS GIS Cut Line= 3
      2745389.84      6817544.18      2745245.84      6818131.38
      2744686.40      6818596.76
#Sta/Elev= 30
  4395.4  409.36  4442.7  409.09  4464.2  408.93  4477.1  404.76  4484.8  399.81
  4513.5  389.17  4546.6  387.91  4596.7  390.25  4685.0  388.96  4726.6  390.39
  4917.2  390.29  4968.7  391.57  4976.1  391.42  4981.3  387.71  5003.1  384.46
  5006.8  381.55  5012.2  381.01  5012.7  380.51  5030.0  381.01  5035.4  390.77
  5041.9  391.51  5134.3  388.78  5170.9  389.20  5411.7  390.59  5524.9  393.14
  5546.1  395.44  5574.4  395.44  5610.9  399.20  5646.0  400.33  5727.7  407.27
#Mann=5,-1,0
  4395.4    0.16       0  4442.7    0.12       0  5012.2    0.07       0
  5030.0    0.12       0  5170.9    0.05       0
Bank Sta=5012.2,5030
Exp/Cntr=0.3,0.1

Type RM Length L Ch R = 1,12413,211,211,211
BEGIN DESCRIPTION:
Mill Creek12412.92
END DESCRIPTION:
XS GIS Cut Line= 3
      2745275.98      6817461.04      2745026.00      6817961.00
      2744526.00      6818661.00
#Sta/Elev= 30
  4440.8  412.18  4460.6  411.38  4485.5  410.36  4574.9  401.62  4642.0  393.18
  4717.5  388.54  4723.1  389.55  4731.4  388.12  4776.2  389.05  4829.3  388.04
  4834.9  389.32  4843.2  388.13  4888.0  387.83  4941.1  389.11  4963.4  388.01
  4985.8  391.18  5002.8  391.29  5013.3  382.21  5019.1  380.50  5019.6  380.00
  5037.0  380.50  5048.9  390.99  5114.1  388.88  5208.9  389.39  5407.8  391.16
  5523.3  396.11  5573.7  399.88  5638.8  401.49  5716.2  406.87  5860.0  411.63
#Mann=5,-1,0
  4440.8    0.16       0  4460.6    0.12       0  5019.1    0.07       0
  5037.0    0.12       0  5208.9    0.05       0
Bank Sta=5019.1,5037
Exp/Cntr=0.3,0.1

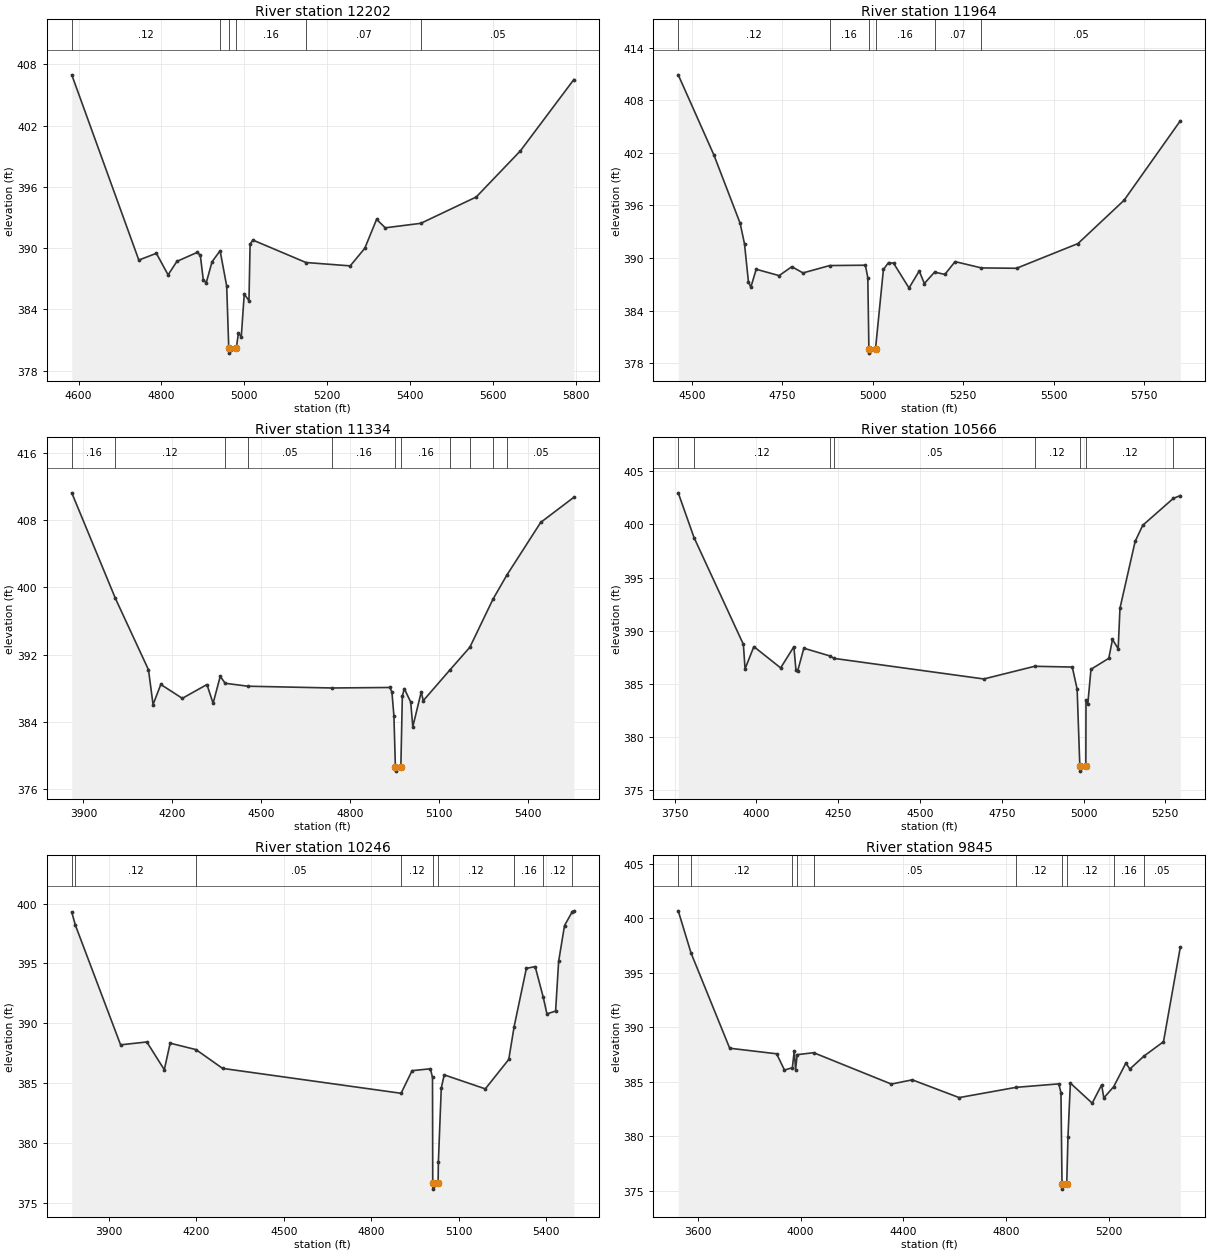
Type RM Length L Ch R = 1,12202,238,238,238
BEGIN DESCRIPTION:
Mill Creek12201.79
END DESCRIPTION:
XS GIS Cut Line= 3
      2745209.19      6817505.24      2744904.40      6817801.86
      2744396.04      6818402.77
#Sta/Elev= 30
  4583.5  406.98  4745.4  388.83  4787.8  389.49  4816.1  387.38  4837.4  388.70
  4886.8  389.59  4894.0  389.28  4901.0  386.91  4908.1  386.59  4922.3  388.67
  4941.7  389.74  4957.6  386.28  4962.6  380.21  4963.1  379.71  4980.9  380.21
  4985.9  381.68  4992.8  381.31  5000.0  385.50  5011.4  384.85  5014.1  390.38
  5020.8  390.79  5149.0  388.59  5255.9  388.26  5291.0  389.98  5319.6  392.82
  5340.5  391.99  5426.4  392.43  5560.2  395.01  5666.8  399.53  5795.9  406.52
#Mann=6,-1,0
  4583.5    0.12       0  4941.7    0.16       0  4962.6    0.07       0
  4980.9    0.16       0  5149.0    0.07       0  5426.4    0.05       0
Bank Sta=4962.6,4980.9
Exp/Cntr=0.3,0.1

Type RM Length L Ch R = 1,11964,630,630,630
BEGIN DESCRIPTION:
Mill Creek11964.38
END DESCRIPTION:
XS GIS Cut Line= 3
      2745226.00      6817461.00      2744726.00      6817661.00
      2744126.03      6818260.97
#Sta/Elev= 30
  4462.6  410.92  4560.9  401.79  4633.6  393.97  4645.7  391.61  4656.5  387.29
  4663.2  386.67  4678.0  388.72  4741.3  387.99  4776.3  389.01  4807.3  388.30
  4880.9  389.14  4979.6  389.18  4986.3  387.76  4989.3  379.64  4989.8  379.14
  5007.6  379.64  5029.4  388.69  5043.5  389.48  5057.7  389.40  5100.1  386.58
  5128.4  388.52  5142.5  387.09  5170.7  388.39  5199.1  388.13  5227.4  389.59
  5300.2  388.87  5397.1  388.83  5566.8  391.65  5694.1  396.59  5849.6  405.67
#Mann=6,-1,0
  4462.6    0.12       0  4880.9    0.16       0  4989.3    0.07       0
  5007.6    0.16       0  5170.7    0.07       0  5300.2    0.05       0
Bank Sta=4989.3,5007.6
Exp/Cntr=0.3,0.1

Type RM Length L Ch R = 1,11334,768,768,768
BEGIN DESCRIPTION:
Mill Creek11333.748
END DESCRIPTION:
XS GIS Cut Line= 5
      2745195.45      6817323.00      2744575.64      6817494.38
      2744301.00      6817636.00      2744162.12      6817761.56
      2743771.62      6818154.81
#Sta/Elev= 30
  3860.7  411.24  4007.7  398.71  4119.5  390.21  4134.9  386.08  4161.0  388.47
  4233.6  386.82  4316.6  388.46  4337.4  386.23  4361.5  389.43  4378.1  388.61
  4454.9  388.26  4738.3  388.05  4933.1  388.11  4940.5  387.60  4947.3  384.74
  4952.3  378.67  4952.8  378.17  4970.7  378.67  4975.7  387.10  4982.4  387.97
  5003.9  386.38  5011.0  383.44  5039.3  387.56  5046.4  386.55  5137.1  390.23
  5203.4  392.89  5281.7  398.62  5328.0  401.45  5442.3  407.72  5554.2  410.71
#Mann=11,-1,0
  3860.7    0.16       0  4007.7    0.12       0  4378.1    0.16       0
  4454.9    0.05       0  4738.3    0.16       0  4952.3    0.07       0
  4970.7    0.16       0  5137.1    0.05       0  5203.4    0.16       0
  5281.7    0.12       0  5328.0    0.05       0
Bank Sta=4952.3,4970.7
Exp/Cntr=0.3,0.1

Type RM Length L Ch R = 1,10566,320,320,320
BEGIN DESCRIPTION:
Mill Creek10584.12
END DESCRIPTION:
XS GIS Cut Line= 3
      2745092.95      6817307.54      2743876.83      6817542.44
      2743606.72      6817663.02
#Sta/Elev= 30
  3761.4  402.96  3809.6  398.76  3960.5  388.72  3965.6  386.42  3992.5  388.51
  4074.4  386.51  4114.8  388.50  4121.1  386.33  4126.2  386.20  4145.3  388.36
  4224.2  387.64  4238.3  387.40  4695.3  385.47  4850.5  386.66  4965.6  386.59
  4980.5  384.51  4988.7  377.31  4989.2  376.81  5007.1  377.31  5007.6  383.47
  5013.0  383.11  5022.8  386.38  5077.2  387.41  5088.5  389.18  5105.9  388.31
  5111.4  392.12  5157.8  398.40  5181.0  399.91  5274.5  402.44  5295.8  402.70
#Mann=8,-1,0
  3761.4    0.16       0  3809.6    0.12       0  4224.2    0.16       0
  4238.3    0.05       0  4850.5    0.12       0  4988.7    0.07       0
  5007.1    0.12       0  5274.5    0.05       0
Bank Sta=4988.7,5007.1
Exp/Cntr=0.3,0.1

Type RM Length L Ch R = 1,10246,401,401,401
BEGIN DESCRIPTION:
Mapping XS 338a819f
END DESCRIPTION:
XS GIS Cut Line= 3
      2745053.48      6817289.77      2743825.01      6817296.75
      2743334.16      6817352.55
#Sta/Elev= 30
  3772.3  399.27  3785.0  398.17  3939.8  388.19  4029.8  388.43  4089.8  386.11
  4109.8  388.33  4198.5  387.79  4289.8  386.22  4902.0  384.14  4939.8  386.03
  5002.8  386.19  5009.9  385.46  5010.7  376.63  5011.2  376.13  5029.1  376.63
  5030.0  378.37  5040.0  384.58  5050.1  385.68  5191.0  384.51  5271.5  386.97
  5290.0  389.72  5331.9  394.58  5362.1  394.73  5389.8  392.17  5402.4  390.78
  5432.2  391.01  5442.6  395.16  5462.8  398.16  5489.7  399.33  5494.8  399.39
#Mann=9,-1,0
  3772.3    0.16       0  3785.0    0.12       0  4198.5    0.05       0
  4902.0    0.12       0  5010.7    0.07       0  5029.1    0.12       0
  5290.0    0.16       0  5389.8    0.12       0  5489.7    0.05       0
Bank Sta=5010.7,5029.1
Exp/Cntr=0.3,0.1

Type RM Length L Ch R = 1,9845,494,494,494
BEGIN DESCRIPTION:
Mill Creek10160.664
END DESCRIPTION:
XS GIS Cut Line= 3
      2745083.37      6817261.00      2743627.76      6817017.15
      2743223.62      6817269.40
#Sta/Elev= 30
  3524.1  400.67  3574.0  396.79  3724.2  388.06  3906.7  387.55  3937.1  386.06
  3967.9  386.27  3975.3  387.82  3980.4  386.10  3986.6  387.47  4050.7  387.65
  4352.9  384.77  4434.0  385.16  4616.5  383.53  4837.4  384.47  5004.0  384.79
  5012.3  383.97  5016.4  375.63  5016.9  375.13  5034.8  375.63  5039.5  379.89
  5048.9  384.86  5133.8  383.02  5170.4  384.70  5178.9  383.50  5217.3  384.53
  5264.8  386.70  5280.1  386.15  5335.7  387.35  5411.0  388.66  5476.4  397.34
#Mann=10,-1,0
  3524.1    0.16       0  3574.0    0.12       0  3967.9    0.05       0
  3986.6    0.12       0  4050.7    0.05       0  4837.4    0.12       0
  5016.4    0.07       0  5034.8    0.12       0  5217.3    0.16       0
  5335.7    0.05       0
Bank Sta=5016.4,5034.8
Exp/Cntr=0.3,0.1

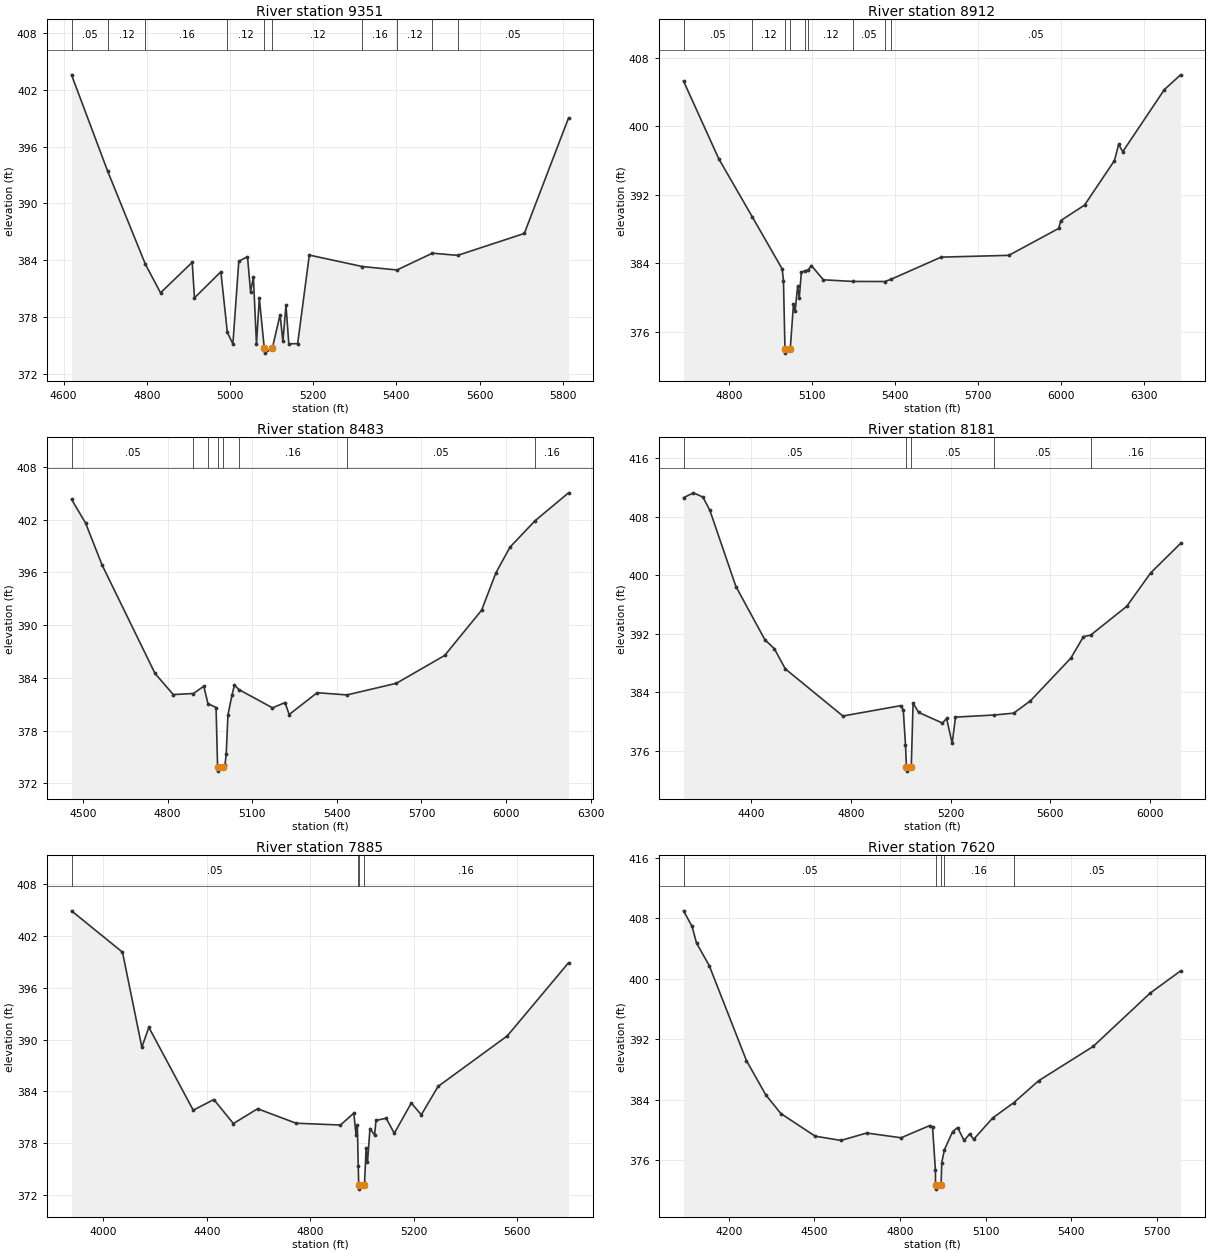
Type RM Length L Ch R = 1,9351,439,439,439
BEGIN DESCRIPTION:
Mill Creek9350.683
END DESCRIPTION:
XS GIS Cut Line= 3
      2743826.00      6816310.99      2743676.00      6816661.00
      2743126.03      6817260.97
#Sta/Elev= 30
  4619.2  403.56  4705.8  393.43  4797.0  383.56  4833.2  380.57  4909.3  383.79
  4914.8  380.04  4978.2  382.79  4993.8  376.39  5007.1  375.18  5021.3  383.90
  5042.2  384.38  5049.6  380.69  5056.4  382.22  5063.8  375.17  5070.6  380.02
  5082.6  374.71  5083.1  374.21  5101.8  374.71  5120.5  378.25  5127.3  375.44
  5134.7  379.28  5141.5  375.19  5162.8  375.21  5190.8  384.55  5318.6  383.34
  5401.5  382.98  5486.7  384.75  5547.4  384.52  5707.6  386.83  5813.9  399.01
#Mann=10,-1,0
  4619.2    0.05       0  4705.8    0.12       0  4797.0    0.16       0
  4993.8    0.12       0  5082.6    0.07       0  5101.8    0.12       0
  5318.6    0.16       0  5401.5    0.12       0  5486.7    0.16       0
  5547.4    0.05       0
Bank Sta=5082.6,5101.8
Exp/Cntr=0.3,0.1

Type RM Length L Ch R = 1,8912,429,429,429
BEGIN DESCRIPTION:
Mill Creek8911.782
END DESCRIPTION:
XS GIS Cut Line= 3
      2743725.97      6816111.03      2743476.00      6816361.00
      2742676.01      6817560.98
#Sta/Elev= 30
  4635.3  405.28  4762.5  396.20  4884.0  389.39  4991.8  383.31  4996.3  381.95
  5001.7  373.98  5002.2  373.48  5020.9  373.98  5032.4  379.20  5038.4  378.40
  5047.4  381.27  5053.4  379.93  5060.9  382.94  5075.6  383.12  5085.6  383.19
  5097.0  383.72  5140.5  382.05  5246.6  381.86  5362.5  381.85  5385.5  382.12
  5565.7  384.70  5810.6  384.91  5990.8  388.06  5998.4  388.98  6084.0  390.78
  6192.2  395.99  6207.2  397.88  6222.2  397.03  6372.4  404.28  6431.0  406.01
#Mann=9,-1,0
  4635.3    0.05       0  4884.0    0.12       0  5001.7    0.07       0
  5020.9    0.12       0  5075.6    0.16       0  5085.6    0.12       0
  5246.6    0.05       0  5362.5    0.16       0  5385.5    0.05       0
Bank Sta=5001.7,5020.9
Exp/Cntr=0.3,0.1

Type RM Length L Ch R = 1,8483,302,302,302
BEGIN DESCRIPTION:
Mill Creek8483.199
END DESCRIPTION:
XS GIS Cut Line= 3
      2743626.03      6816010.98      2743176.00      6816311.00
      2742476.01      6817310.98
#Sta/Elev= 30
  4459.7  404.31  4509.3  401.63  4567.9  396.85  4755.7  384.50  4820.3  382.10
  4891.9  382.22  4928.5  383.05  4943.1  381.08  4972.0  380.62  4977.4  373.89
  4977.9  373.39  4996.6  373.89  5003.6  374.11  5008.0  375.33  5014.1  379.79
  5028.9  382.10  5037.2  383.18  5052.9  382.67  5171.9  380.59  5216.4  381.19
  5231.2  379.83  5330.1  382.31  5435.8  382.06  5610.9  383.38  5782.2  386.55
  5913.0  391.69  5963.6  395.93  6013.7  398.87  6102.4  401.87  6221.2  405.05
#Mann=8,-1,0
  4459.7    0.05       0  4891.9    0.16       0  4943.1    0.12       0
  4977.4    0.07       0  4996.6    0.12       0  5052.9    0.16       0
  5435.8    0.05       0  6102.4    0.16       0
Bank Sta=4977.4,4996.6
Exp/Cntr=0.3,0.1

Type RM Length L Ch R = 1,8181,296,296,296
BEGIN DESCRIPTION:
Mill Creek8054.615
END DESCRIPTION:
XS GIS Cut Line= 3
      2743380.09      6815382.13      2742973.73      6816154.56
      2742475.99      6817161.01
#Sta/Elev= 30
  4127.2  410.59  4166.8  411.26  4205.0  410.68  4233.0  408.85  4337.5  398.46
  4453.6  391.20  4491.8  389.96  4535.8  387.21  4767.0  380.77  5000.0  382.19
  5009.5  381.59  5018.3  376.85  5022.3  373.74  5022.8  373.24  5041.5  373.74
  5048.8  382.53  5071.2  381.26  5166.5  379.81  5183.4  380.43  5205.8  377.05
  5219.1  380.62  5375.6  380.91  5452.6  381.16  5519.9  382.84  5682.5  388.69
  5733.0  391.62  5761.7  391.82  5906.9  395.76  6002.2  400.30  6122.8  404.35
#Mann=5,-1,0
  4127.2    0.05       0  5022.3    0.05       0  5041.5    0.05       0
  5375.6    0.05       0  5761.7    0.16       0
Bank Sta=5022.3,5041.5
Exp/Cntr=0.3,0.1

Type RM Length L Ch R = 1,7885,265,265,265
BEGIN DESCRIPTION:
Mapping XS 4701aaff
END DESCRIPTION:
XS GIS Cut Line= 4
      2742709.72      6815132.37      2742873.86      6815647.18
      2742726.03      6816211.08      2742492.99      6816975.86
#Sta/Elev= 30
  3876.7  404.94  4073.9  400.14  4148.8  389.11  4175.8  391.42  4347.6  381.80
  4427.3  383.04  4502.9  380.25  4596.7  381.97  4745.2  380.29  4917.2  380.08
  4968.9  381.46  4977.2  378.98  4982.4  380.07  4986.0  375.36  4987.7  373.14
  4988.2  372.64  5007.1  373.14  5010.4  373.39  5016.4  377.43  5021.7  375.74
  5031.3  379.67  5049.3  378.91  5054.5  380.61  5094.0  380.87  5125.4  379.12
  5191.1  382.63  5229.9  381.27  5294.8  384.56  5562.7  390.43  5799.5  398.91
#Mann=4,-1,0
  3876.7    0.05       0  4986.0    0.16       0  4987.7    0.07       0
  5007.1    0.16       0
Bank Sta=4987.7,5007.1
Exp/Cntr=0.3,0.1

Type RM Length L Ch R = 1,7620,416,416,416
BEGIN DESCRIPTION:
Mill Creek7619.729
END DESCRIPTION:
XS GIS Cut Line= 3
      2742554.77      6815301.28      2742476.00      6816261.00
      2742401.00      6817036.04
#Sta/Elev= 30
  4041.5  408.96  4071.3  406.90  4087.0  404.70  4131.5  401.73  4262.0  389.18
  4329.6  384.67  4382.4  382.20  4502.8  379.21  4593.1  378.65  4683.4  379.63
  4803.8  379.00  4904.1  380.61  4914.1  380.38  4924.2  374.69  4924.5  372.72
  4925.0  372.22  4943.9  372.72  4946.3  375.72  4955.5  377.41  4984.4  379.81
  5001.9  380.35  5024.5  378.65  5044.6  379.52  5058.0  378.80  5125.0  381.62
  5198.8  383.64  5285.8  386.53  5476.6  391.05  5675.9  398.08  5783.1  401.03
#Mann=5,-1,0
  4041.5    0.05       0  4924.5    0.07       0  4943.9    0.05       0
  4955.5    0.16       0  5198.8    0.05       0
Bank Sta=4924.5,4943.9
Exp/Cntr=0.3,0.1

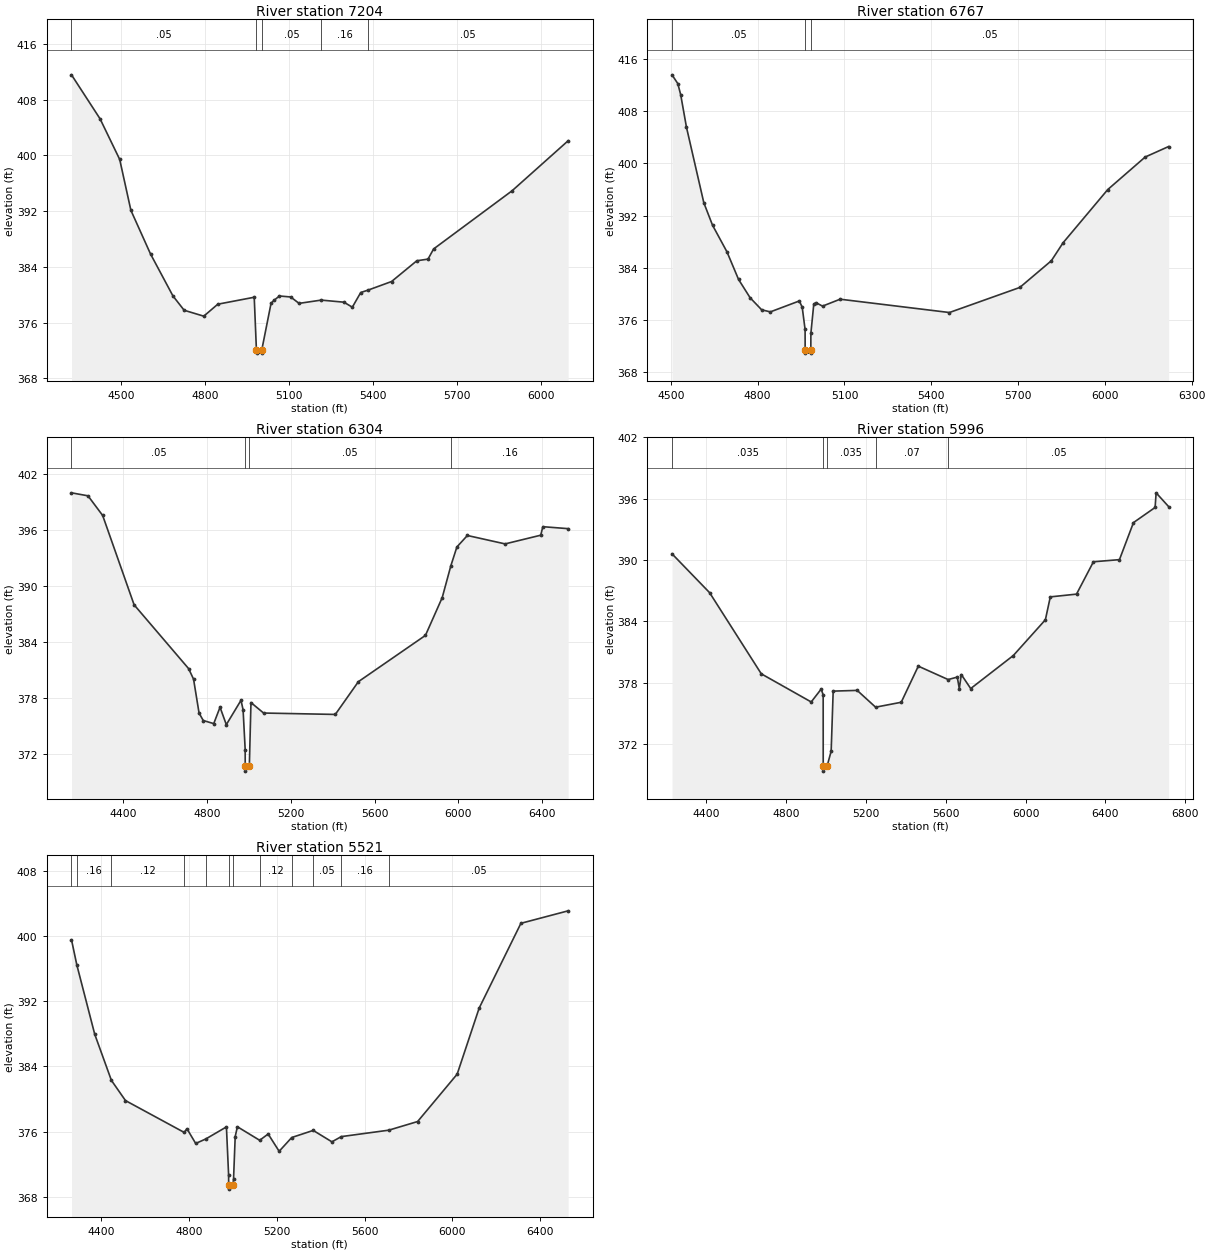
Type RM Length L Ch R = 1,7204,437,437,437
BEGIN DESCRIPTION:
Mill Creek7204.003
END DESCRIPTION:
XS GIS Cut Line= 3
      2742178.96      6815339.08      2742176.00      6816011.00
      2742176.00      6817110.98
#Sta/Elev= 30
  4324.1  411.59  4426.0  405.27  4496.0  399.44  4536.0  392.12  4606.0  385.85
  4686.0  379.82  4726.0  377.76  4796.0  376.91  4846.0  378.63  4976.0  379.63
  4983.8  372.10  4984.3  371.60  5002.7  371.60  5003.2  372.10  5036.0  378.75
  5046.0  379.17  5066.0  379.81  5106.0  379.67  5136.0  378.75  5215.1  379.22
  5296.0  378.92  5326.0  378.20  5356.0  380.31  5381.8  380.65  5466.0  381.89
  5556.0  384.87  5596.0  385.11  5616.0  386.57  5896.0  394.93  6096.0  402.12
#Mann=5,-1,0
  4324.1    0.05       0  4983.8    0.05       0  5003.2    0.05       0
  5215.1    0.16       0  5381.8    0.05       0
Bank Sta=4983.8,5003.2
Exp/Cntr=0.3,0.1

Type RM Length L Ch R = 1,6767,463,463,463
BEGIN DESCRIPTION:
Mill Creek6767.169
END DESCRIPTION:
XS GIS Cut Line= 3
      2741876.00      6815410.97      2741876.00      6815911.00
      2741676.00      6817111.02
#Sta/Elev= 30
  4503.9  413.56  4523.9  412.22  4533.9  410.52  4553.9  405.53  4613.9  393.96
  4643.9  390.53  4693.9  386.44  4733.9  382.22  4773.9  379.41  4813.9  377.56
  4843.9  377.25  4943.9  378.92  4953.9  377.97  4963.9  374.55  4964.1  371.43
  4964.6  370.93  4983.2  370.93  4983.7  371.43  4983.9  373.97  4993.9  378.43
  5001.4  378.66  5024.2  378.13  5085.0  379.19  5462.7  377.15  5706.0  380.99
  5815.0  385.08  5855.5  387.83  6010.1  395.99  6139.4  400.97  6220.5  402.58
#Mann=3,-1,0
  4503.9    0.05       0  4964.1    0.05       0  4983.7    0.05       0
Bank Sta=4964.1,4983.7
Exp/Cntr=0.3,0.1

Type RM Length L Ch R = 1,6304,308,308,308
BEGIN DESCRIPTION:
Mill Creek6304.35
END DESCRIPTION:
XS GIS Cut Line= 3
      2741432.91      6815112.33      2741430.09      6815971.20
      2741452.89      6817481.86
#Sta/Elev= 30
  4154.2  399.94  4232.9  399.62  4302.9  397.52  4452.9  387.97  4712.9  381.15
  4736.6  380.02  4762.9  376.39  4782.9  375.60  4832.9  375.27  4862.9  377.02
  4892.9  375.16  4962.9  377.76  4972.9  376.75  4982.9  372.49  4983.1  370.69
  4983.6  370.19  5002.7  370.69  5010.5  377.52  5070.7  376.40  5412.9  376.25
  5522.9  379.75  5843.0  384.70  5923.0  388.74  5964.3  392.15  5993.0  394.15
  6043.0  395.38  6223.0  394.48  6393.0  395.41  6403.2  396.32  6523.9  396.11
#Mann=4,-1,0
  4154.2    0.05       0  4983.1    0.05       0  5002.7    0.05       0
  5964.3    0.16       0
Bank Sta=4983.1,5002.7
Exp/Cntr=0.3,0.1

Type RM Length L Ch R = 1,5996,475,475,475
BEGIN DESCRIPTION:
Mill Creek5996.3
END DESCRIPTION:
XS GIS Cut Line= 3
      2741169.90      6815043.70      2741174.61      6815833.49
      2741046.11      6817526.82
#Sta/Elev= 30
  4229.0  390.60  4417.4  386.80  4676.3  378.87  4926.3  376.12  4976.3  377.38
  4986.3  376.81  4986.5  369.86  4987.0  369.36  5006.1  369.86  5026.3  371.31
  5036.4  377.18  5156.7  377.25  5248.9  375.61  5377.3  376.09  5462.8  379.62
  5612.2  378.31  5658.1  378.55  5668.2  377.42  5678.2  378.80  5725.3  377.43
  5938.9  380.66  6099.4  384.15  6124.1  386.39  6255.4  386.66  6340.1  389.82
  6470.5  390.03  6540.7  393.65  6649.1  395.13  6654.2  396.56  6717.0  395.21
#Mann=5,-1,0
  4229.0   0.035       0  4986.5   0.035       0  5006.1   0.035       0
  5248.9    0.07       0  5612.2    0.05       0
Bank Sta=4986.5,5006.1
Exp/Cntr=0.3,0.1

Type RM Length L Ch R = 1,5521,325,325,325
BEGIN DESCRIPTION:
Mill Creek5520.768
END DESCRIPTION:
XS GIS Cut Line= 3
      2740843.39      6814925.06      2740835.14      6815661.11
      2740751.00      6817185.99
#Sta/Elev= 30
  4263.9  399.52  4288.3  396.42  4369.8  387.93  4445.7  382.28  4509.9  379.80
  4777.8  375.89  4789.9  376.35  4829.9  374.54  4875.7  375.09  4969.9  376.57
  4979.9  370.65  4980.1  369.44  4980.6  368.94  4999.7  369.44  5002.4  370.20
  5009.9  375.39  5019.9  376.59  5121.4  374.93  5160.1  375.70  5210.2  373.58
  5267.5  375.27  5365.4  376.14  5450.6  374.74  5493.3  375.38  5709.7  376.17
  5841.2  377.23  6021.4  383.04  6121.6  391.14  6311.9  401.54  6527.2  403.07
#Mann=12,-1,0
  4263.9    0.07       0  4288.3    0.16       0  4445.7    0.12       0
  4777.8   0.035       0  4875.7    0.16       0  4980.1    0.07       0
  4999.7    0.16       0  5121.4    0.12       0  5267.5    0.16       0
  5365.4    0.05       0  5493.3    0.16       0  5709.7    0.05       0
Bank Sta=4980.1,4999.7
Exp/Cntr=0.3,0.1