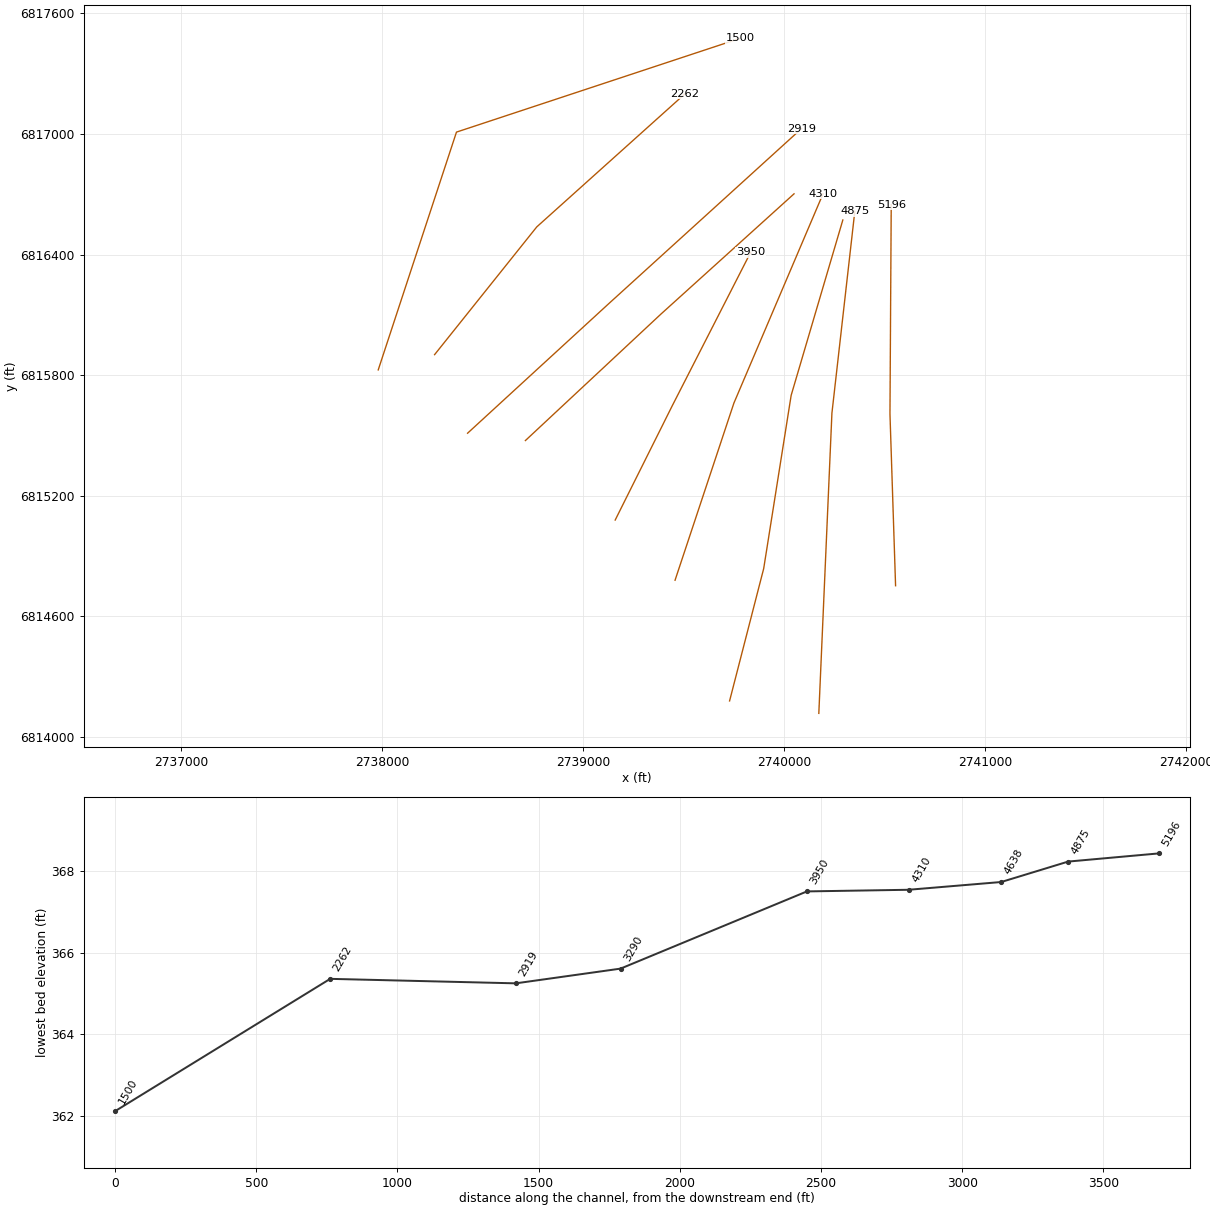
HEC-RAS study Mill Creek.prj: Mill Creek Base Level Engineering

--- Mill Creek.g01 (geometry) --- (continued)

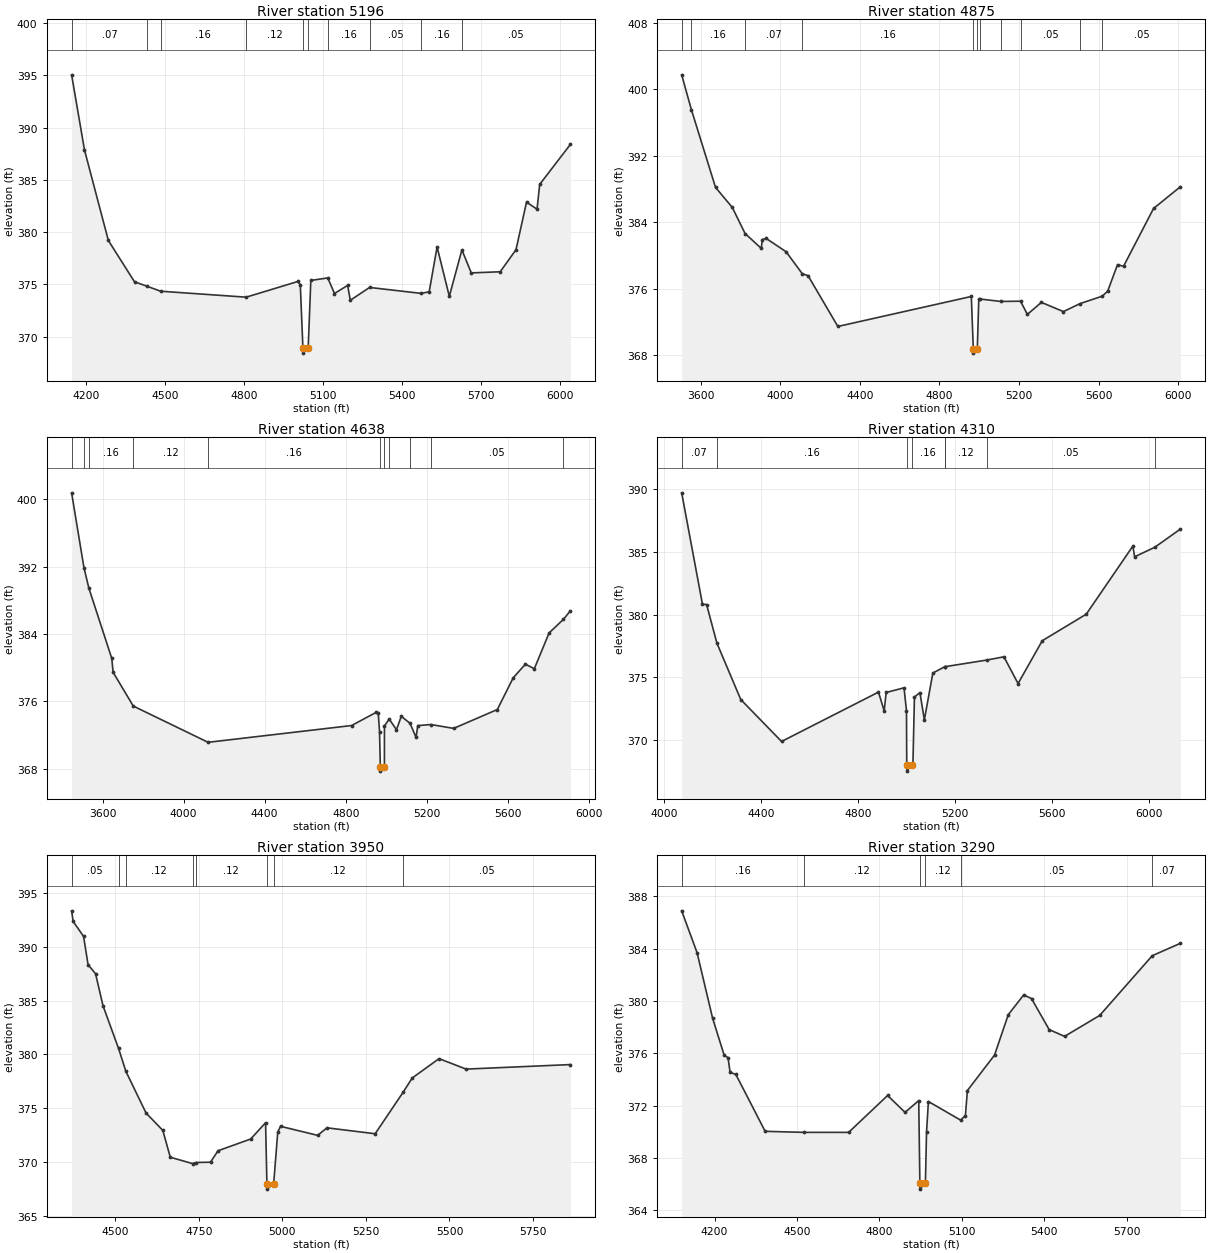
Type RM Length L Ch R = 1,5196,321,321,321
BEGIN DESCRIPTION:
Mill Creek4936.203
END DESCRIPTION:
XS GIS Cut Line= 3
      2740555.42      6814752.06      2740527.49      6815607.31
      2740533.77      6816647.79
#Sta/Elev= 30
  4144.3  395.04  4193.3  387.85  4284.0  379.20  4383.4  375.25  4432.7  374.81
  4482.4  374.35  4807.9  373.78  5004.3  375.28  5013.7  374.97  5023.6  368.93
  5024.1  368.43  5043.7  368.93  5053.7  375.38  5118.1  375.62  5143.7  374.13
  5193.7  374.91  5203.7  373.48  5277.0  374.71  5473.8  374.14  5503.7  374.30
  5533.7  378.58  5580.2  373.86  5628.0  378.30  5663.7  376.10  5773.7  376.21
  5833.7  378.32  5873.7  382.87  5913.7  382.19  5923.7  384.56  6040.5  388.39
#Mann=10,-1,0
  4144.3    0.07       0  4432.7    0.12       0  4482.4    0.16       0
  4807.9    0.12       0  5023.6    0.07       0  5043.7    0.12       0
  5118.1    0.16       0  5277.0    0.05       0  5473.8    0.16       0
  5628.0    0.05       0
Bank Sta=5023.6,5043.7
Exp/Cntr=0.3,0.1

Type RM Length L Ch R = 1,4875,237,237,237
BEGIN DESCRIPTION:
Mill Creek4722.204
END DESCRIPTION:
XS GIS Cut Line= 3
      2740173.54      6814117.07      2740238.72      6815610.95
      2740352.64      6816615.41
#Sta/Elev= 30
  3504.7  401.73  3553.3  397.55  3674.8  388.18  3758.9  385.77  3823.2  382.63
  3904.6  380.84  3909.6  381.89  3929.0  382.04  4029.1  380.44  4110.9  377.78
  4139.5  377.56  4289.4  371.44  4960.0  375.05  4970.0  368.73  4970.5  368.23
  4990.1  368.73  4997.5  374.71  5004.9  374.74  5108.5  374.45  5207.3  374.48
  5241.6  372.89  5312.0  374.34  5422.7  373.23  5507.3  374.20  5618.2  375.09
  5645.3  375.70  5694.5  378.88  5724.7  378.68  5875.6  385.64  6010.9  388.27
#Mann=11,-1,0
  3504.7   0.035       0  3553.3    0.16       0  3823.2    0.07       0
  4110.9    0.16       0  4970.0    0.07       0  4990.1    0.16       0
  5004.9    0.12       0  5108.5    0.16       0  5207.3    0.05       0
  5507.3    0.16       0  5618.2    0.05       0
Bank Sta=4970,4990.1
Exp/Cntr=0.3,0.1

Type RM Length L Ch R = 1,4638,328,328,328
BEGIN DESCRIPTION:
Mapping XS 69ba9c7d
END DESCRIPTION:
XS GIS Cut Line= 4
      2739729.53      6814178.93      2739899.25      6814837.59
      2740035.99      6815699.74      2740293.04      6816571.85
#Sta/Elev= 30
  3446.9  400.75  3507.7  391.89  3532.0  389.45  3645.2  381.10  3651.8  379.46
  3751.3  375.45  4120.6  371.15  4829.2  373.14  4950.7  374.71  4960.8  374.59
  4967.0  372.41  4971.0  368.23  4971.5  367.73  4991.1  368.23  4991.2  373.08
  5014.6  373.91  5050.7  372.64  5074.3  374.23  5117.4  373.41  5147.3  371.73
  5155.8  373.13  5220.2  373.26  5332.9  372.80  5548.5  375.04  5626.8  378.80
  5687.0  380.42  5731.1  379.88  5804.1  384.13  5874.8  385.74  5909.2  386.75
#Mann=11,-1,0
  3446.9    0.12       0  3507.7   0.035       0  3532.0    0.16       0
  3751.3    0.12       0  4120.6    0.16       0  4971.0    0.07       0
  4991.1    0.16       0  5014.6    0.12       0  5117.4    0.16       0
  5220.2    0.05       0  5874.8    0.07       0
Bank Sta=4971,4991.1
Exp/Cntr=0.3,0.1

Type RM Length L Ch R = 1,4310,360,360,360
BEGIN DESCRIPTION:
Mill Creek3830.938
END DESCRIPTION:
XS GIS Cut Line= 3
      2739458.20      6814779.45      2739750.96      6815660.69
      2740194.39      6816702.00
#Sta/Elev= 30
  4071.4  389.69  4157.3  380.82  4174.3  380.80  4216.9  377.73  4315.4  373.24
  4484.0  369.90  4884.4  373.83  4907.9  372.33  4916.0  373.80  4989.8  374.17
  5000.0  372.36  5001.1  368.04  5001.6  367.54  5021.3  368.04  5026.6  368.11
  5032.9  373.44  5055.6  373.79  5073.8  371.62  5109.0  375.35  5158.2  375.85
  5158.3  375.85  5331.8  376.38  5402.5  376.64  5460.9  374.51  5560.9  377.92
  5742.6  380.03  5935.1  385.45  5942.5  384.60  6025.9  385.36  6131.8  386.81
#Mann=8,-1,0
  4071.4    0.07       0  4216.9    0.16       0  5001.1    0.07       0
  5021.3    0.16       0  5158.2    0.05       0  5158.3    0.12       0
  5331.8    0.05       0  6025.9    0.07       0
Bank Sta=5001.1,5021.3
Exp/Cntr=0.3,0.1

Type RM Length L Ch R = 1,3950,660,660,660
BEGIN DESCRIPTION:
Mapping XS 29814c5c
END DESCRIPTION:
XS GIS Cut Line= 3
      2739160.46      6815078.96      2739443.94      6815646.78
      2739834.49      6816411.13
#Sta/Elev= 30
  4369.0  393.33  4373.5  392.35  4404.8  390.96  4418.3  388.33  4440.7  387.49
  4463.0  384.52  4509.5  380.56  4531.4  378.44  4591.7  374.57  4642.0  372.95
  4664.4  370.46  4731.0  369.87  4740.6  369.97  4784.8  370.00  4807.2  371.06
  4904.9  372.15  4949.6  373.66  4953.6  368.00  4954.1  367.50  4973.8  368.00
  4986.0  372.79  4994.3  373.33  5105.5  372.49  5133.3  373.19  5277.6  372.64
  5360.8  376.47  5388.7  377.82  5468.8  379.61  5549.8  378.64  5862.0  379.06
#Mann=8,-1,0
  4369.0    0.05       0  4509.5    0.16       0  4531.4    0.12       0
  4731.0    0.16       0  4740.6    0.12       0  4953.6    0.07       0
  4973.8    0.12       0  5360.8    0.05       0
Bank Sta=4953.6,4973.8
Exp/Cntr=0.3,0.1

Type RM Length L Ch R = 1,3290,371,371,371
BEGIN DESCRIPTION:
Mapping XS 22354631
END DESCRIPTION:
XS GIS Cut Line= 3
      2738713.69      6815474.46      2739388.25      6816103.86
      2740050.28      6816701.98
#Sta/Elev= 30
  4080.4  386.89  4136.4  383.69  4193.0  378.67  4235.0  375.85  4249.2  375.66
  4256.5  374.54  4277.5  374.38  4384.1  370.03  4525.3  369.95  4687.9  369.95
  4829.6  372.77  4893.1  371.48  4942.9  372.38  4947.0  366.11  4947.5  365.61
  4967.2  366.11  4971.3  369.98  4978.1  372.31  5094.9  370.89  5112.6  371.22
  5120.0  373.15  5218.7  375.86  5268.7  378.95  5324.8  380.46  5353.2  380.18
  5417.4  377.81  5473.5  377.29  5601.3  378.89  5792.6  383.46  5895.2  384.41
#Mann=6,-1,0
  4080.4    0.16       0  4525.3    0.12       0  4947.0    0.07       0
  4967.2    0.12       0  5094.9    0.05       0  5792.6    0.07       0
Bank Sta=4947,4967.2
Exp/Cntr=0.3,0.1

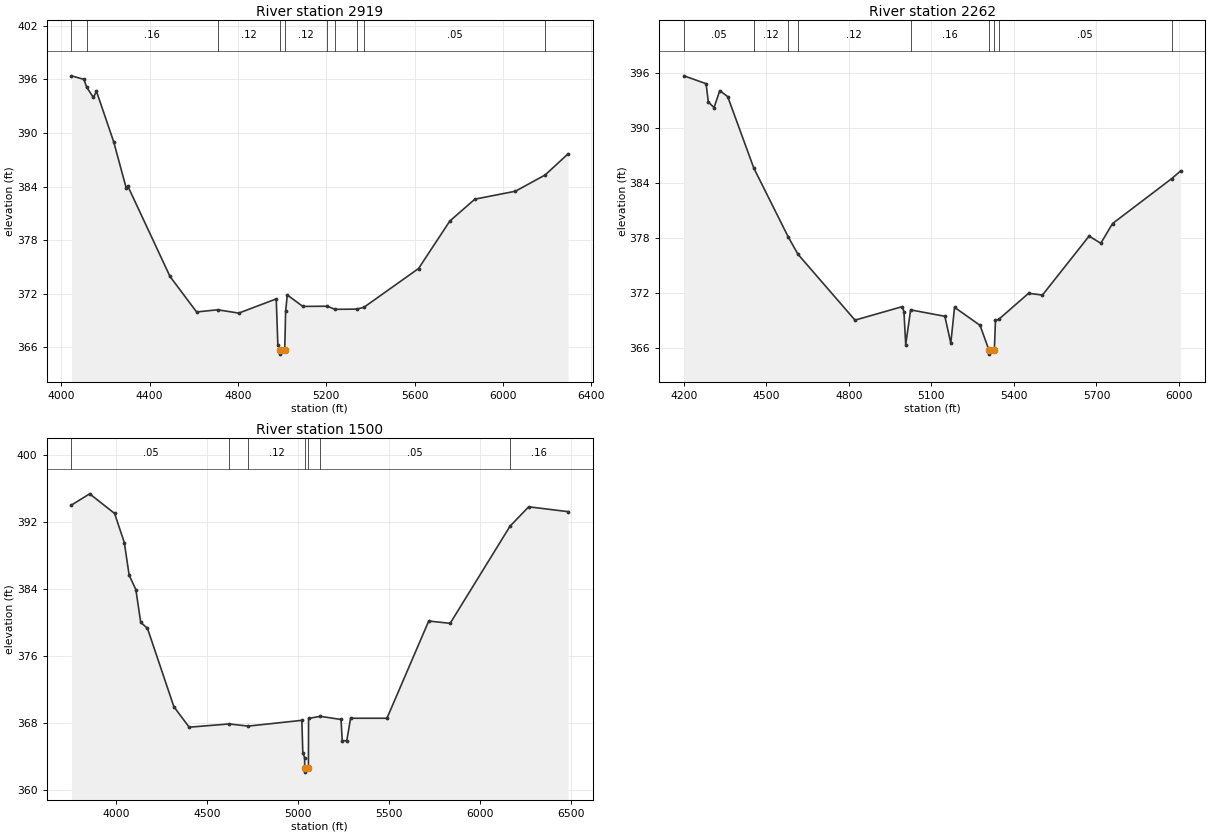
Type RM Length L Ch R = 1,2919,657,657,657
BEGIN DESCRIPTION:
Mill Creek2918.828
END DESCRIPTION:
XS GIS Cut Line= 3
      2738425.97      6815510.97      2739128.42      6816155.58
      2740087.20      6817026.38
#Sta/Elev= 30
  4046.6  396.39  4103.1  395.99  4115.1  395.13  4145.6  393.97  4159.8  394.65
  4237.5  389.02  4294.2  383.85  4301.6  384.05  4492.7  373.94  4613.0  369.97
  4708.7  370.21  4804.1  369.84  4973.7  371.43  4981.1  366.23  4992.0  365.75
  4992.5  365.25  5012.2  365.75  5016.2  370.04  5023.7  371.87  5094.0  370.59
  5205.0  370.61  5239.8  370.26  5339.0  370.29  5370.7  370.49  5618.1  374.83
  5759.6  380.14  5873.1  382.59  6056.9  383.48  6191.5  385.30  6295.2  387.66
#Mann=10,-1,0
  4046.6    0.05       0  4115.1    0.16       0  4708.7    0.12       0
  4992.0    0.07       0  5012.2    0.12       0  5205.0    0.16       0
  5239.8    0.05       0  5339.0    0.16       0  5370.7    0.05       0
  6191.5    0.07       0
Bank Sta=4992,5012.2
Exp/Cntr=0.3,0.1

Type RM Length L Ch R = 1,2262,762,762,762
BEGIN DESCRIPTION:
Mill Creek2261.8
END DESCRIPTION:
XS GIS Cut Line= 3
      2738261.90      6815901.89      2738770.23      6816537.43
      2739507.22      6817199.16
#Sta/Elev= 30
  4201.3  395.73  4281.6  394.87  4289.7  392.87  4310.5  392.27  4331.3  394.12
  4360.1  393.46  4455.0  385.66  4580.2  378.14  4615.4  376.26  4822.7  369.07
  4994.0  370.54  5000.4  370.01  5006.9  366.40  5024.7  370.19  5149.1  369.49
  5170.7  366.55  5184.3  370.47  5277.0  368.50  5308.6  365.86  5309.1  365.36
  5329.0  365.86  5333.0  369.04  5345.0  369.16  5453.4  372.00  5503.5  371.80
  5673.1  378.24  5715.7  377.46  5758.4  379.61  5973.6  384.52  6005.6  385.35
#Mann=9,-1,0
  4201.3    0.05       0  4455.0    0.12       0  4580.2    0.16       0
  4615.4    0.12       0  5024.7    0.16       0  5308.6    0.07       0
  5329.0    0.16       0  5345.0    0.05       0  5973.6    0.12       0
Bank Sta=5308.6,5329
Exp/Cntr=0.3,0.1

Type RM Length L Ch R = 1,1500,0,0,0
BEGIN DESCRIPTION:
Mill Creek1499.856
END DESCRIPTION:
XS GIS Cut Line= 3
      2737981.46      6815826.01      2738370.72      6817009.01
      2739782.00      6817475.58
#Sta/Elev= 30
  3754.6  394.04  3854.6  395.38  3991.5  393.04  4045.2  389.56  4071.7  385.67
  4108.8  383.92  4135.3  380.02  4172.4  379.31  4317.8  369.94  4402.0  367.49
  4622.5  367.88  4726.4  367.62  5021.8  368.31  5027.1  364.46  5037.2  363.83
  5037.4  362.62  5037.9  362.12  5057.9  362.62  5058.8  368.54  5123.4  368.79
  5237.3  368.41  5243.9  365.89  5268.9  365.87  5289.9  368.56  5490.0  368.56
  5719.8  380.18  5837.6  379.90  6166.9  391.51  6269.7  393.83  6486.4  393.25
#Mann=7,-1,0
  3754.6    0.05       0  4622.5    0.16       0  4726.4    0.12       0
  5037.4    0.07       0  5057.9    0.12       0  5123.4    0.05       0
  6166.9    0.16       0
Bank Sta=5037.4,5057.9
Exp/Cntr=0.3,0.1

Chan Stop Cuts=-1