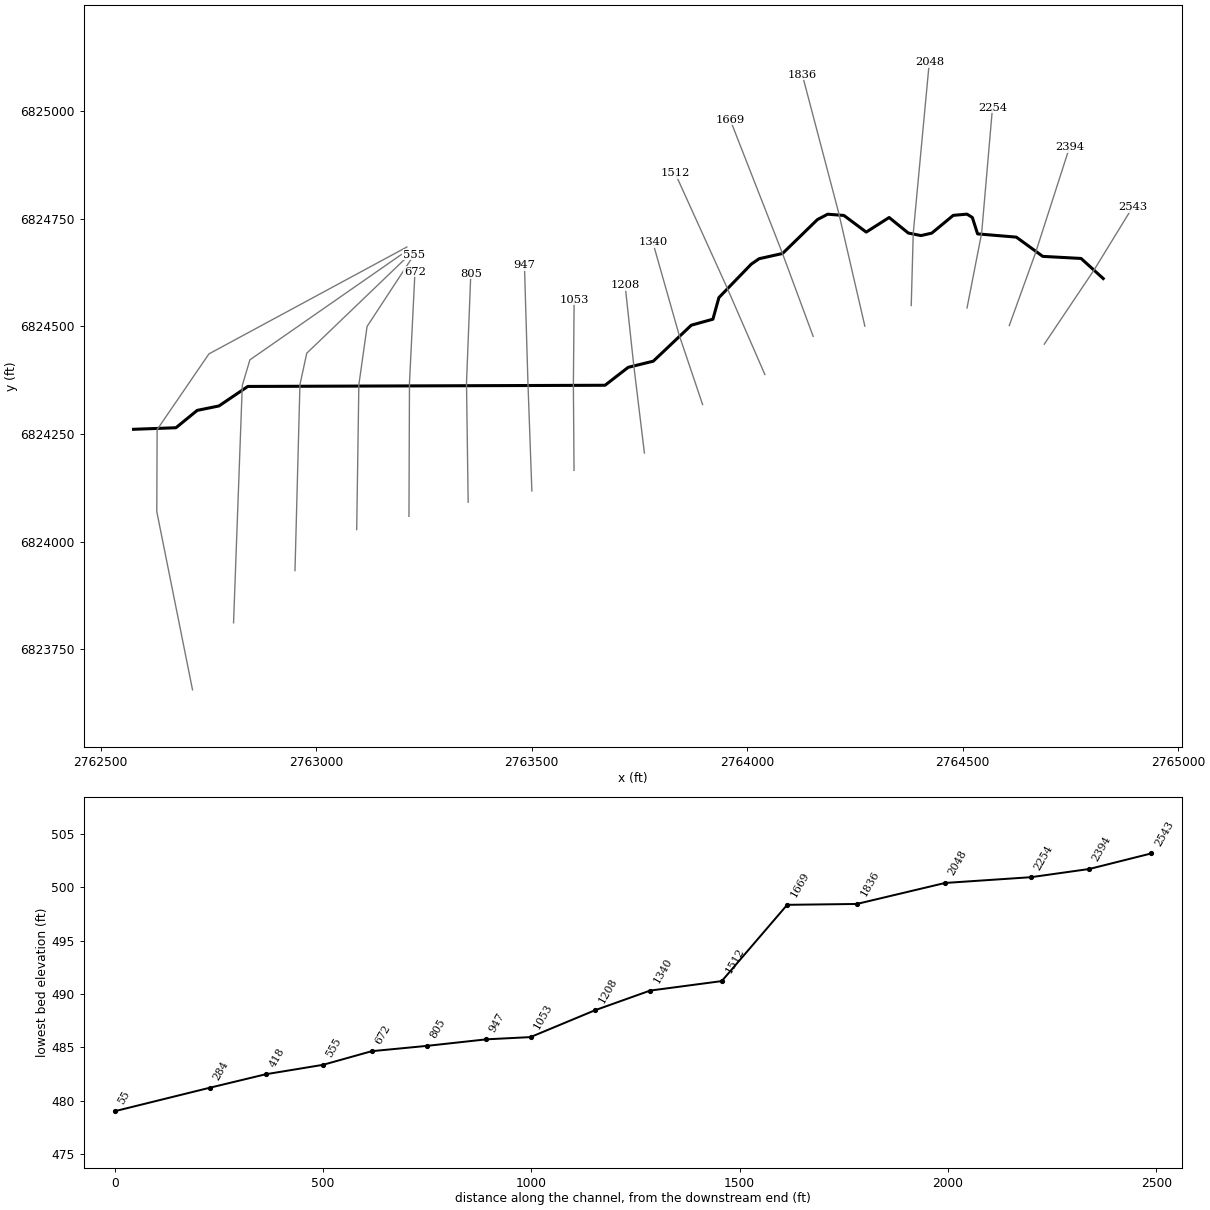
--- Mill Creek Trib A.prj (project) ---

Proj Title=Mill Creek Trib A Base Level Engineering
Current Plan=p01
Default Exp/Contr=0.3,0.1
English Units
Geom File=g01
Flow File=f01
Plan File=p01
BEGIN DESCRIPTION:
Mill Creek Trib A
END DESCRIPTION:

--- Mill Creek Trib A.p01 (plan) ---

Plan Title=Multiple Run
Short Identifier=Multiple
Geom File=g01
Flow File=f01
Subcritical Flow
K Sum by GR= 0
Std Step Tol= 0.01
Critical Tol= 0.01
Num of Std Step Trials= 20
Max Error Tol= 0.3
Flow Tol Ratio= 0.001
Split Flow NTrial= 30
Split Flow Tol= 0.02
Split Flow Ratio= 0.02
Log Output Level= 0
Friction Slope Method= 1
Unsteady Friction Slope Method= 2
Unsteady Bridges Friction Slope Method= 1
Parabolic Critical Depth
Global Vel Dist=  1 , 1 , 1
Global Log Level= 0
CheckData=True
Encroach Param= -1, 0, 0, 0
BEGIN DESCRIPTION:
Multiple Run
END DESCRIPTION:

--- Mill Creek Trib A.f01 (steady flow) ---

Flow Title=Multiple
Number of Profiles=7
Profile Names=10-year,25-year,50-year,1pct_min,100-year,1pct_plu,500-year
River Rch & RM= Mill Creek Trib ,Reach-1,2543
     588     804     983     599    1196    2386    1770
Boundary for River Rch & Prof#=Mill Creek Trib ,Reach-1,1
Up Type=0
Dn Type=3
Dn Slope=0.005
Boundary for River Rch & Prof#=Mill Creek Trib ,Reach-1,2
Up Type=0
Dn Type=3
Dn Slope=0.005
Boundary for River Rch & Prof#=Mill Creek Trib ,Reach-1,3
Up Type=0
Dn Type=3
Dn Slope=0.005
Boundary for River Rch & Prof#=Mill Creek Trib ,Reach-1,4
Up Type=0
Dn Type=3
Dn Slope=0.005
Boundary for River Rch & Prof#=Mill Creek Trib ,Reach-1,5
Up Type=0
Dn Type=3
Dn Slope=0.005
Boundary for River Rch & Prof#=Mill Creek Trib ,Reach-1,6
Up Type=0
Dn Type=3
Dn Slope=0.005
Boundary for River Rch & Prof#=Mill Creek Trib ,Reach-1,7
Up Type=0
Dn Type=3
Dn Slope=0.005

--- Mill Creek Trib A.g01 (geometry) ---

Geom Title=Existing Conditions

River Reach=Mill Creek Trib ,Reach-1
Reach XY= 30
      2764826.00      6824611.00      2764774.60      6824657.61
      2764685.69      6824662.45      2764624.34      6824707.12
      2764534.48      6824714.62      2764522.27      6824752.79
      2764509.86      6824760.47      2764478.06      6824757.70
      2764428.22      6824716.45      2764403.17      6824710.72
      2764373.70      6824716.64      2764329.23      6824752.68
      2764276.08      6824718.83      2764224.35      6824757.44
      2764186.64      6824760.35      2764162.80      6824747.84
      2764082.04      6824669.18      2764027.64      6824657.03
      2764009.30      6824644.36      2763934.28      6824566.77
      2763920.38      6824516.62      2763870.26      6824502.70
      2763782.05      6824419.16      2763723.83      6824404.86
      2763670.07      6824363.24      2762841.21      6824360.49
      2762774.27      6824315.19      2762723.81      6824304.91
      2762674.50      6824264.63      2762576.00      6824261.00

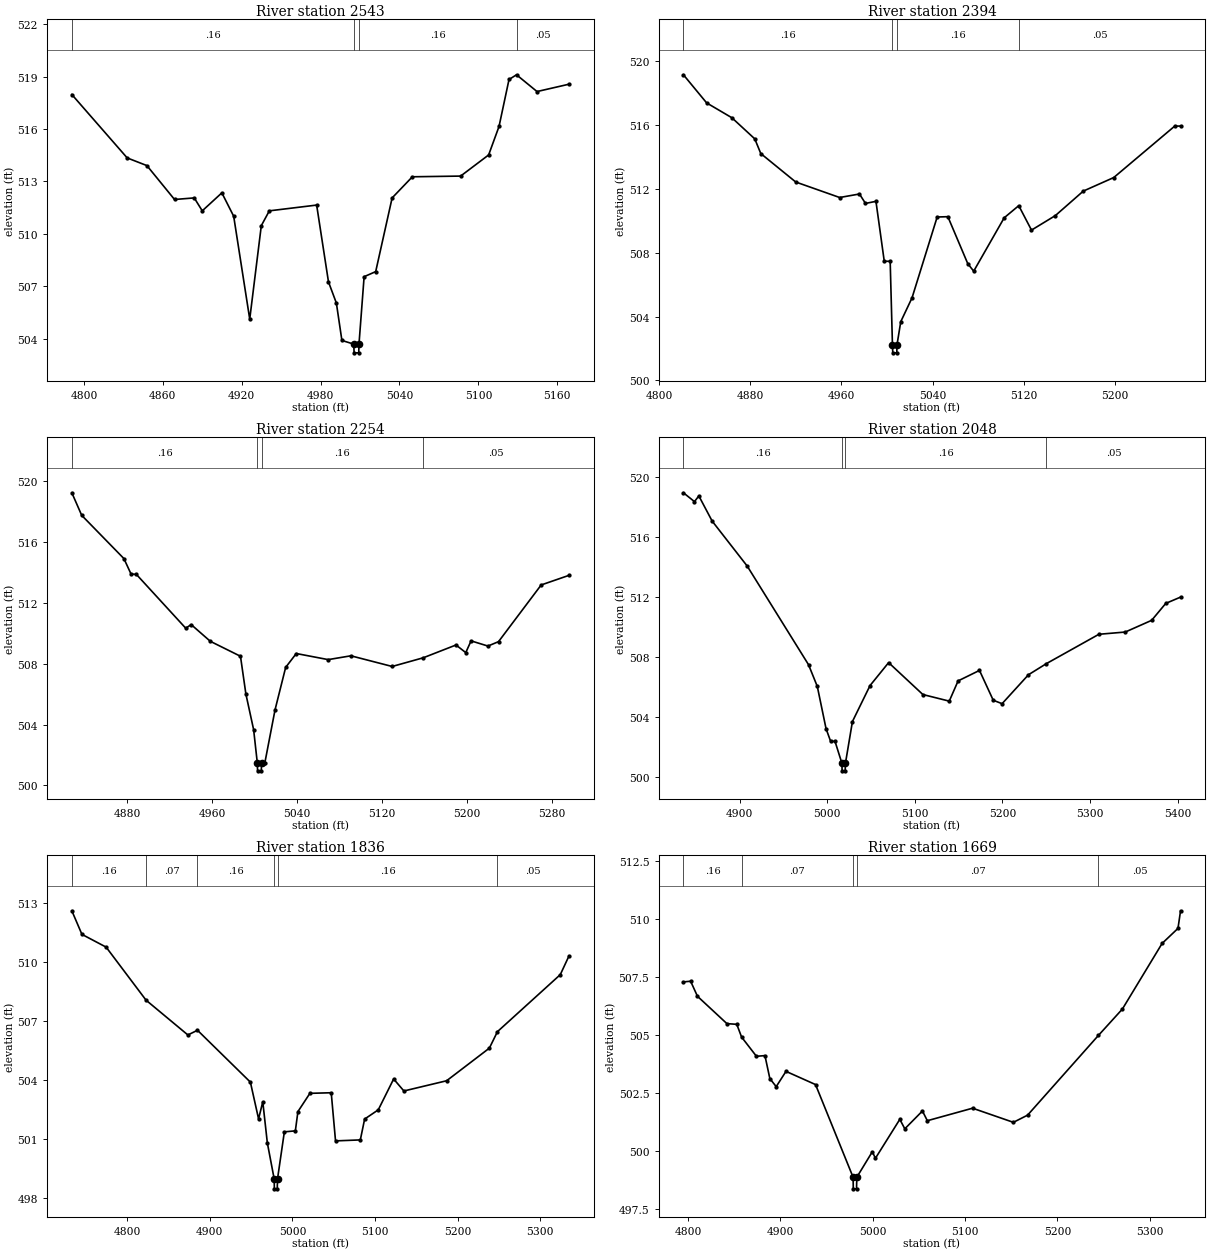
Type RM Length L Ch R = 1,2543,149,149,149
BEGIN DESCRIPTION:
Mill Creek Trib A2542.772
END DESCRIPTION:
XS GIS Cut Line= 3
      2764689.18      6824458.61      2764805.67      6824632.37
      2764893.95      6824776.37
#Sta/Elev= 30
  4790.8  517.98  4832.9  514.35  4847.9  513.91  4868.9  511.97  4883.9  512.06
  4890.0  511.32  4904.9  512.35  4913.9  511.01  4926.1  505.12  4934.9  510.47
  4941.0  511.32  4977.0  511.65  4986.0  507.25  4992.0  506.04  4996.2  503.90
  5005.2  503.69  5005.5  503.19  5009.0  503.19  5009.2  503.69  5013.1  507.55
  5021.9  507.84  5034.4  512.06  5049.8  513.27  5086.5  513.31  5107.8  514.52
  5115.7  516.15  5123.3  518.84  5129.0  519.11  5144.6  518.15  5168.9  518.57
#Mann=4,-1,0
  4790.8    0.16       0  5005.2    0.07       0  5009.2    0.16       0
  5129.0    0.05       0
Bank Sta=5005.2,5009.2
Exp/Cntr=0.3,0.1

Type RM Length L Ch R = 1,2394,140,140,140
BEGIN DESCRIPTION:
Mill Creek Trib A2394.33
END DESCRIPTION:
XS GIS Cut Line= 3
      2764608.00      6824501.82      2764668.57      6824669.59
      2764747.77      6824915.69
#Sta/Elev= 30
  4821.1  519.13  4841.5  517.37  4863.7  516.44  4883.8  515.12  4889.1  514.20
  4919.8  512.42  4958.4  511.45  4975.8  511.67  4981.1  511.08  4990.3  511.21
  4997.6  507.46  5002.8  507.46  5004.8  502.23  5005.1  501.73  5008.6  501.73
  5008.8  502.23  5012.1  503.68  5022.0  505.17  5044.1  510.23  5053.5  510.25
  5071.0  507.31  5076.2  506.84  5103.0  510.18  5115.8  510.94  5127.0  509.41
  5148.0  510.32  5172.5  511.85  5199.3  512.70  5252.9  515.92  5258.0  515.92
#Mann=4,-1,0
  4821.1    0.16       0  5004.8    0.07       0  5008.8    0.16       0
  5115.8    0.05       0
Bank Sta=5004.8,5008.8
Exp/Cntr=0.3,0.1

Type RM Length L Ch R = 1,2254,206,206,206
BEGIN DESCRIPTION:
Mill Creek Trib A2254.48
END DESCRIPTION:
XS GIS Cut Line= 3
      2764510.00      6824542.78      2764543.94      6824716.75
      2764569.02      6825007.12
#Sta/Elev= 30
  4827.6  519.21  4836.9  517.73  4876.7  514.89  4883.4  513.88  4888.5  513.85
  4935.0  510.32  4940.1  510.56  4958.2  509.46  4986.6  508.48  4991.7  506.00
  4999.0  503.66  5002.5  501.46  5002.7  500.96  5006.2  500.96  5006.5  501.46
  5009.5  501.46  5019.2  504.97  5029.2  507.75  5039.2  508.66  5069.3  508.26
  5090.7  508.51  5129.6  507.81  5158.9  508.38  5189.8  509.22  5199.0  508.72
  5204.0  509.49  5219.9  509.15  5229.9  509.44  5270.1  513.16  5296.3  513.79
#Mann=4,-1,0
  4827.6    0.16       0  5002.5    0.07       0  5006.5    0.16       0
  5158.9    0.05       0
Bank Sta=5002.5,5006.5
Exp/Cntr=0.3,0.1

Type RM Length L Ch R = 1,2048,212,212,212
BEGIN DESCRIPTION:
Mill Creek Trib A2047.78
END DESCRIPTION:
XS GIS Cut Line= 3
      2764380.51      6824548.23      2764385.21      6824716.32
      2764422.49      6825113.82
#Sta/Elev= 30
  4835.9  518.97  4848.5  518.38  4853.5  518.76  4868.7  517.08  4908.7  514.08
  4978.7  507.50  4988.7  506.05  4998.7  503.23  5003.9  502.39  5008.9  502.39
  5016.8  500.92  5017.0  500.42  5020.5  500.42  5020.8  500.92  5028.8  503.71
  5048.9  506.11  5070.1  507.64  5109.2  505.51  5139.3  505.07  5149.4  506.42
  5173.8  507.12  5189.5  505.13  5199.6  504.90  5229.7  506.83  5250.1  507.57
  5310.1  509.53  5340.2  509.68  5370.3  510.46  5386.4  511.59  5403.3  512.01
#Mann=4,-1,0
  4835.9    0.16       0  5016.8    0.07       0  5020.8    0.16       0
  5250.1    0.05       0
Bank Sta=5016.8,5020.8
Exp/Cntr=0.3,0.1

Type RM Length L Ch R = 1,1836,167,167,167
BEGIN DESCRIPTION:
Mill Creek Trib A1835.72
END DESCRIPTION:
XS GIS Cut Line= 3
      2764272.91      6824500.54      2764212.06      6824764.03
      2764127.77      6825084.09
#Sta/Elev= 30
  4733.2  512.60  4745.4  511.40  4774.7  510.75  4823.0  508.05  4873.6  506.28
  4885.2  506.52  4949.2  503.88  4959.1  502.01  4964.2  502.88  4969.7  500.79
  4978.0  498.95  4978.2  498.45  4981.7  498.45  4982.0  498.95  4990.3  501.35
  5003.6  501.40  5006.7  502.38  5021.2  503.31  5047.0  503.34  5052.2  500.89
  5082.2  500.94  5087.4  502.00  5103.9  502.47  5122.5  504.04  5134.9  503.43
  5186.6  503.95  5238.3  505.61  5248.1  506.45  5324.1  509.35  5334.6  510.30
#Mann=6,-1,0
  4733.2    0.16       0  4823.0    0.07       0  4885.2    0.16       0
  4978.0    0.07       0  4982.0    0.16       0  5248.1    0.05       0
Bank Sta=4978,4982
Exp/Cntr=0.3,0.1

Type RM Length L Ch R = 1,1669,157,157,157
BEGIN DESCRIPTION:
Mill Creek Trib A1668.97
END DESCRIPTION:
XS GIS Cut Line= 3
      2764152.98      6824476.79      2764080.55      6824672.48
      2763960.42      6824979.66
#Sta/Elev= 30
  4795.0  507.30  4802.8  507.33  4810.2  506.68  4842.1  505.50  4852.8  505.47
  4858.0  504.92  4874.1  504.09  4883.3  504.12  4888.6  503.13  4895.5  502.78
  4906.1  503.44  4938.1  502.87  4978.8  498.87  4979.0  498.37  4982.5  498.37
  4982.8  498.87  4999.6  499.97  5003.0  499.69  5029.4  501.37  5034.8  500.96
  5053.9  501.73  5059.2  501.31  5108.2  501.85  5152.4  501.24  5167.8  501.55
  5244.5  504.99  5270.5  506.13  5313.5  508.96  5330.7  509.61  5333.5  510.37
#Mann=5,-1,0
  4795.0    0.16       0  4858.0    0.07       0  4978.8    0.07       0
  4982.8    0.07       0  5244.5    0.05       0
Bank Sta=4978.8,4982.8
Exp/Cntr=0.3,0.1

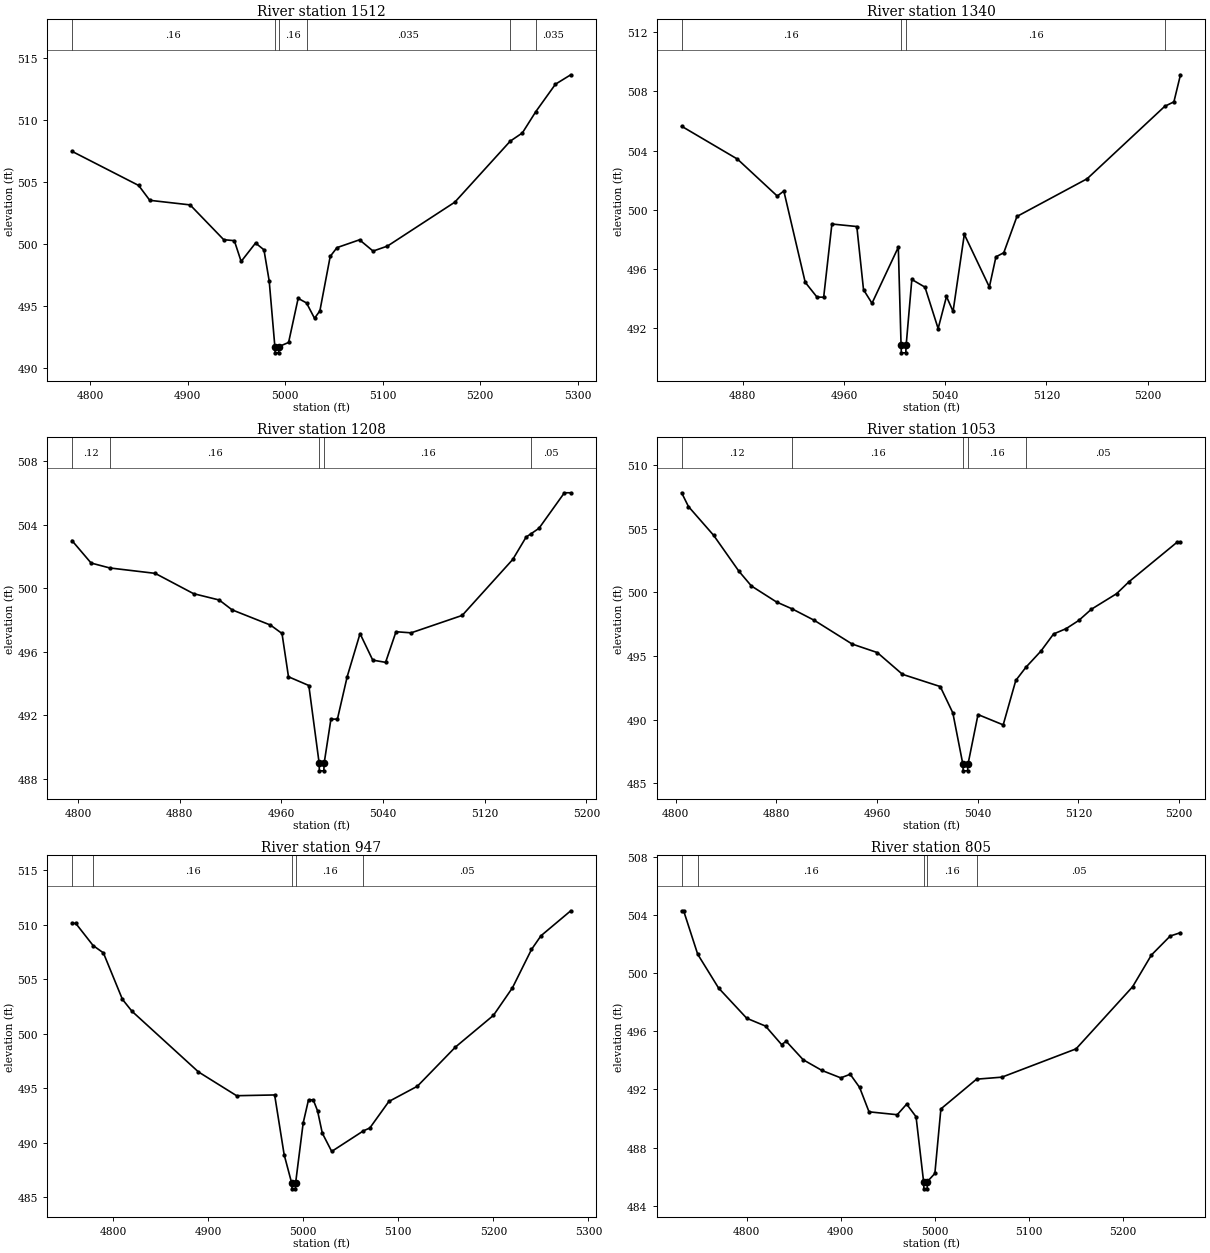
Type RM Length L Ch R = 1,1512,172,172,172
BEGIN DESCRIPTION:
Mill Creek Trib A1511.87
END DESCRIPTION:
XS GIS Cut Line= 3
      2764040.94      6824388.17      2763952.15      6824592.09
      2763832.52      6824855.81
#Sta/Elev= 30
  4781.0  507.50  4849.5  504.74  4860.9  503.54  4902.3  503.17  4936.8  500.36
  4947.7  500.28  4954.7  498.60  4969.5  500.09  4978.1  499.54  4983.5  497.02
  4989.3  491.72  4989.6  491.22  4993.1  491.22  4993.3  491.72  5003.4  492.06
  5013.2  495.62  5021.8  495.25  5030.0  494.01  5035.5  494.61  5046.1  499.01
  5053.1  499.72  5076.2  500.35  5090.1  499.44  5104.8  499.84  5174.0  503.39
  5230.9  508.32  5243.3  508.98  5257.1  510.70  5277.3  512.92  5293.0  513.68
#Mann=6,-1,0
  4781.0    0.16       0  4989.3    0.07       0  4993.3    0.16       0
  5021.8   0.035       0  5230.9    0.05       0  5257.1   0.035       0
Bank Sta=4989.3,4993.3
Exp/Cntr=0.3,0.1

Type RM Length L Ch R = 1,1340,132,132,132
BEGIN DESCRIPTION:
Mill Creek Trib A1339.87
END DESCRIPTION:
XS GIS Cut Line= 3
      2763896.48      6824318.41      2763841.79      6824480.71
      2763780.84      6824695.36
#Sta/Elev= 30
  4831.6  505.65  4875.7  503.43  4907.2  500.93  4912.4  501.27  4929.3  495.10
  4938.6  494.10  4943.9  494.09  4950.4  499.04  4970.1  498.87  4975.4  494.60
  4982.1  493.68  5002.9  497.47  5005.1  490.83  5005.3  490.33  5008.8  490.33
  5009.1  490.83  5013.6  495.29  5024.0  494.77  5034.4  491.97  5041.0  494.14
  5046.2  493.13  5055.1  498.34  5074.9  494.78  5080.1  496.82  5086.3  497.10
  5096.7  499.55  5152.2  502.10  5213.6  507.00  5220.8  507.30  5226.0  509.13
#Mann=4,-1,0
  4831.6    0.16       0  5005.1    0.07       0  5009.1    0.16       0
  5213.6   0.035       0
Bank Sta=5005.1,5009.1
Exp/Cntr=0.3,0.1

Type RM Length L Ch R = 1,1208,155,155,155
BEGIN DESCRIPTION:
Mill Creek Trib A1208.35
END DESCRIPTION:
XS GIS Cut Line= 3
      2763761.44      6824205.96      2763736.58      6824410.59
      2763716.59      6824595.88
#Sta/Elev= 30
  4795.2  503.01  4810.3  501.59  4825.0  501.28  4860.7  500.94  4890.9  499.66
  4911.1  499.26  4921.2  498.64  4951.4  497.68  4960.5  497.15  4965.6  494.42
  4981.6  493.87  4989.7  488.99  4989.9  488.49  4993.4  488.49  4993.7  488.99
  4999.0  491.75  5004.1  491.75  5011.8  494.43  5021.9  497.14  5031.9  495.47
  5042.0  495.33  5050.2  497.26  5062.1  497.19  5102.3  498.29  5142.1  501.82
  5152.6  503.23  5156.5  503.44  5162.7  503.78  5182.7  506.02  5187.7  506.02
#Mann=5,-1,0
  4795.2    0.12       0  4825.0    0.16       0  4989.7    0.07       0
  4993.7    0.16       0  5156.5    0.05       0
Bank Sta=4989.7,4993.7
Exp/Cntr=0.3,0.1

Type RM Length L Ch R = 1,1053,106,106,106
BEGIN DESCRIPTION:
Mill Creek Trib A1052.52
END DESCRIPTION:
XS GIS Cut Line= 3
      2763598.17      6824165.63      2763596.63      6824362.99
      2763598.38      6824561.81
#Sta/Elev= 30
  4804.8  507.81  4810.2  506.73  4830.2  504.47  4850.2  501.66  4860.2  500.49
  4880.2  499.23  4892.8  498.68  4910.2  497.79  4940.2  495.93  4960.2  495.26
  4980.2  493.55  5010.2  492.59  5020.2  490.52  5028.2  486.47  5028.4  485.97
  5031.9  485.97  5032.2  486.47  5040.2  490.39  5060.2  489.58  5070.2  493.07
  5078.2  494.10  5090.2  495.38  5100.2  496.72  5110.2  497.14  5120.2  497.78
  5130.2  498.66  5150.2  499.88  5160.2  500.83  5198.1  503.91  5201.0  503.91
#Mann=5,-1,0
  4804.8    0.12       0  4892.8    0.16       0  5028.2    0.07       0
  5032.2    0.16       0  5078.2    0.05       0
Bank Sta=5028.2,5032.2
Exp/Cntr=0.3,0.1

Type RM Length L Ch R = 1,947,142,142,142
BEGIN DESCRIPTION:
Mill Creek Trib A947.36
END DESCRIPTION:
XS GIS Cut Line= 3
      2763500.32      6824117.94      2763491.27      6824367.08
      2763483.06      6824642.25
#Sta/Elev= 30
  4756.8  510.11  4760.8  510.11  4779.1  508.07  4789.9  507.40  4809.9  503.14
  4819.9  502.05  4889.9  496.48  4930.0  494.30  4970.0  494.37  4980.0  488.89
  4988.0  486.26  4988.3  485.76  4991.8  485.76  4992.0  486.26  5000.0  491.80
  5005.6  493.92  5010.6  493.92  5015.1  492.92  5020.1  490.87  5030.0  489.19
  5063.4  491.08  5070.1  491.34  5090.1  493.77  5120.1  495.17  5160.1  498.76
  5200.1  501.67  5220.1  504.20  5240.1  507.71  5250.1  508.97  5281.4  511.26
#Mann=5,-1,0
  4756.8    0.12       0  4779.1    0.16       0  4988.0    0.07       0
  4992.0    0.16       0  5063.4    0.05       0
Bank Sta=4988,4992
Exp/Cntr=0.3,0.1

Type RM Length L Ch R = 1,805,133,133,133
BEGIN DESCRIPTION:
Mill Creek Trib A804.63
END DESCRIPTION:
XS GIS Cut Line= 3
      2763352.50      6824091.81      2763348.65      6824368.78
      2763358.62      6824621.89
#Sta/Elev= 30
  4730.8  504.32  4732.9  504.32  4747.9  501.32  4770.0  499.00  4800.0  496.91
  4820.0  496.37  4837.0  495.10  4842.0  495.32  4860.0  494.05  4880.0  493.31
  4900.0  492.80  4910.0  493.05  4920.0  492.14  4930.0  490.46  4960.0  490.26
  4970.0  490.99  4980.0  490.12  4988.0  485.65  4988.3  485.15  4991.8  485.15
  4992.0  485.65  5000.0  486.21  5006.4  490.66  5044.3  492.71  5071.3  492.85
  5150.1  494.80  5210.2  499.08  5230.2  501.27  5250.2  502.58  5261.1  502.81
#Mann=5,-1,0
  4730.8    0.12       0  4747.9    0.16       0  4988.0    0.07       0
  4992.0    0.16       0  5044.3    0.05       0
Bank Sta=4988,4992
Exp/Cntr=0.3,0.1

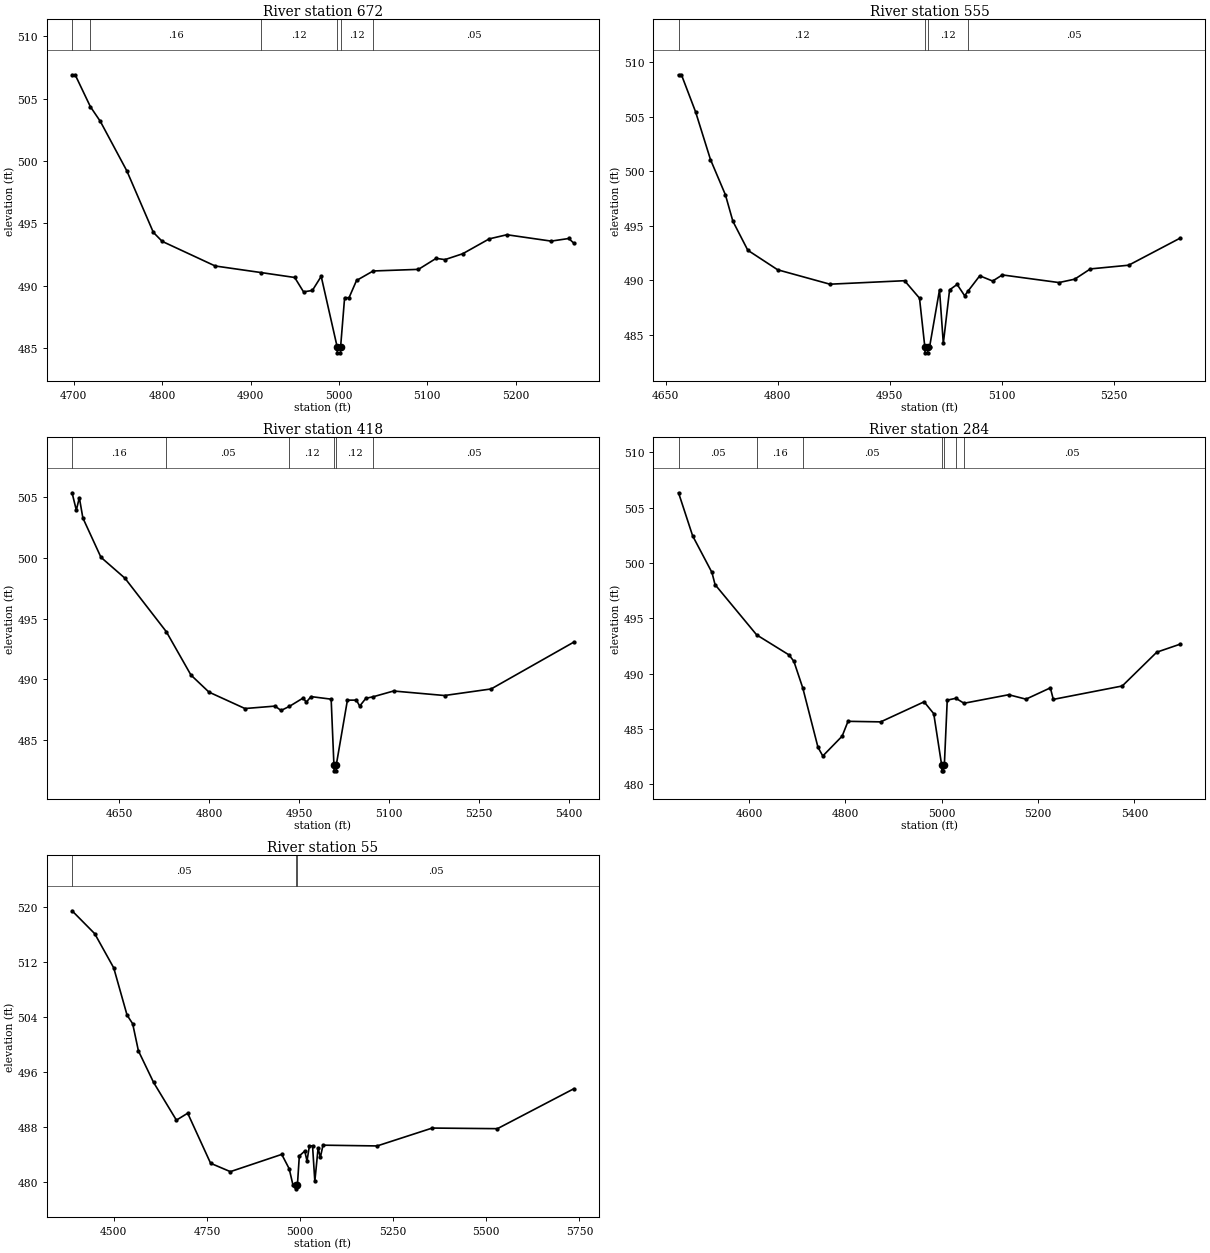
Type RM Length L Ch R = 1,672,117,117,117
BEGIN DESCRIPTION:
Mill Creek Trib A672.19
END DESCRIPTION:
XS GIS Cut Line= 3
      2763215.14      6824059.00      2763216.36      6824369.00
      2763229.10      6824626.68
#Sta/Elev= 30
  4698.0  506.90  4701.5  506.90  4718.7  504.35  4730.0  503.17  4760.0  499.21
  4790.0  494.29  4800.0  493.57  4860.0  491.60  4912.3  491.07  4950.0  490.68
  4960.0  489.53  4970.0  489.64  4980.0  490.77  4998.0  485.15  4998.3  484.65
  5001.8  484.65  5002.0  485.15  5006.5  489.06  5011.5  489.06  5020.0  490.44
  5038.8  491.20  5090.1  491.33  5110.1  492.21  5120.1  492.11  5140.2  492.58
  5170.2  493.77  5190.2  494.10  5240.3  493.59  5260.3  493.80  5266.0  493.42
#Mann=6,-1,0
  4698.0    0.12       0  4718.7    0.16       0  4912.3    0.12       0
  4998.0    0.07       0  5002.0    0.12       0  5038.8    0.05       0
Bank Sta=4998,5002
Exp/Cntr=0.3,0.1

Type RM Length L Ch R = 1,555,137,137,137
BEGIN DESCRIPTION:
Mill Creek Trib A554.7
END DESCRIPTION:
XS GIS Cut Line= 4
      2763093.89      6824028.24      2763098.88      6824364.39
      2763117.96      6824499.72      2763227.18      6824666.49
#Sta/Elev= 30
  4667.2  508.85  4671.1  508.85  4690.0  505.46  4710.0  501.08  4730.0  497.85
  4740.0  495.43  4760.0  492.77  4800.0  490.98  4870.0  489.66  4970.0  489.98
  4990.0  488.38  4997.2  483.87  4997.4  483.37  5000.9  483.37  5001.2  483.87
  5003.4  483.87  5016.8  489.14  5021.9  484.23  5030.3  489.14  5040.4  489.64
  5050.5  488.60  5054.7  489.00  5070.7  490.43  5088.0  489.95  5101.0  490.51
  5176.8  489.81  5197.9  490.12  5218.9  491.06  5270.2  491.40  5339.4  493.89
#Mann=4,-1,0
  4667.2    0.12       0  4997.2    0.07       0  5001.2    0.12       0
  5054.7    0.05       0
Bank Sta=4997.2,5001.2
Exp/Cntr=0.3,0.1

Type RM Length L Ch R = 1,418,134,134,134
BEGIN DESCRIPTION:
Mill Creek Trib A417.96
END DESCRIPTION:
XS GIS Cut Line= 4
      2762950.70      6823932.97      2762962.18      6824364.50
      2762978.03      6824437.63      2763215.80      6824665.87
#Sta/Elev= 30
  4571.8  505.34  4578.9  503.91  4583.9  504.94  4589.8  503.27  4619.9  500.04
  4659.9  498.32  4728.9  493.92  4769.9  490.36  4799.9  488.96  4859.9  487.61
  4910.0  487.81  4920.0  487.45  4934.0  487.79  4957.0  488.48  4962.0  488.13
  4970.0  488.59  5003.5  488.38  5008.1  482.99  5008.4  482.49  5011.9  482.49
  5012.1  482.99  5030.6  488.30  5045.5  488.30  5051.1  487.81  5061.3  488.45
  5073.7  488.58  5107.5  489.05  5192.4  488.68  5270.1  489.22  5407.9  493.07
#Mann=6,-1,0
  4571.8    0.16       0  4728.9    0.05       0  4934.0    0.12       0
  5008.1    0.07       0  5012.1    0.12       0  5073.7    0.05       0
Bank Sta=5008.1,5012.1
Exp/Cntr=0.3,0.1

Type RM Length L Ch R = 1,284,229,229,229
BEGIN DESCRIPTION:
Mill Creek Trib A283.71
END DESCRIPTION:
XS GIS Cut Line= 4
      2762808.15      6823811.76      2762828.46      6824362.96
      2762846.11      6824422.27      2763197.33      6824666.61
#Sta/Elev= 30
  4453.9  506.33  4483.2  502.44  4523.2  499.14  4529.7  498.04  4616.1  493.50
  4683.3  491.69  4693.3  491.11  4711.8  488.70  4743.3  483.35  4753.3  482.57
  4793.4  484.36  4805.6  485.70  4873.4  485.65  4963.5  487.46  4983.5  486.39
  5000.0  481.73  5000.2  481.23  5003.7  481.23  5004.0  481.73  5005.5  481.73
  5011.5  487.61  5029.4  487.78  5046.3  487.33  5139.1  488.10  5174.9  487.70
  5225.5  488.72  5231.6  487.68  5374.7  488.89  5446.3  491.94  5495.2  492.67
#Mann=7,-1,0
  4453.9    0.05       0  4616.1    0.16       0  4711.8    0.05       0
  5000.0    0.05       0  5004.0    0.05       0  5029.4    0.12       0
  5046.3    0.05       0
Bank Sta=5000,5004
Exp/Cntr=0.3,0.1

Type RM Length L Ch R = 1,55,0,0,0
BEGIN DESCRIPTION:
Mill Creek Trib A54.841
END DESCRIPTION:
XS GIS Cut Line= 5
      2762712.94      6823656.32      2762630.05      6824069.92
      2762630.84      6824260.30      2762751.00      6824436.00
      2763210.26      6824684.19
#Sta/Elev= 30
  4387.8  519.46  4448.6  516.13  4499.6  511.16  4535.4  504.29  4550.5  503.03
  4565.9  499.09  4606.7  494.49  4667.9  489.01  4698.2  490.02  4759.7  482.74
  4812.7  481.52  4950.7  484.03  4970.7  481.94  4980.7  479.60  4988.7  479.52
  4989.0  479.02  4992.7  479.52  4997.9  483.81  5012.5  484.51  5018.5  483.08
  5025.1  485.29  5033.4  485.26  5039.5  480.11  5048.3  484.93  5054.4  483.60
  5061.4  485.37  5206.8  485.26  5354.7  487.86  5529.7  487.77  5734.9  493.58
#Mann=3,-1,0
  4387.8    0.05       0  4988.7    0.05       0  4992.7    0.05       0
Bank Sta=4988.7,4992.7
Exp/Cntr=0.3,0.1

Chan Stop Cuts=-1