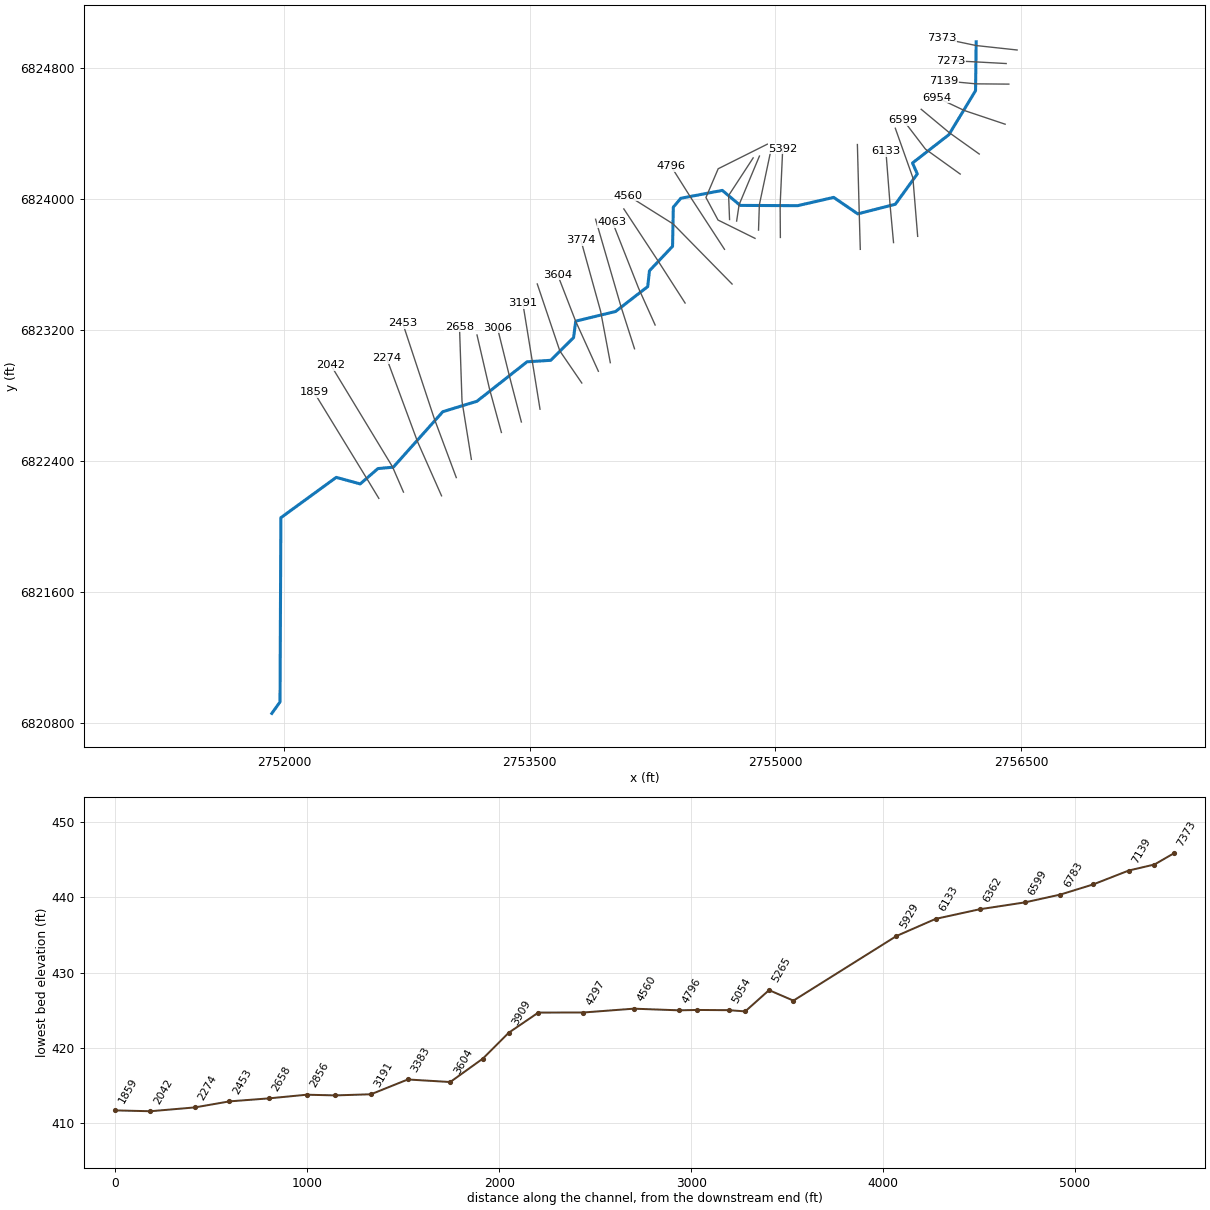
--- Mill Creek Trib C.prj (project) ---

Proj Title=Mill Creek Trib C Base Level Engineering
Current Plan=p01
Default Exp/Contr=0.3,0.1
English Units
Geom File=g01
Flow File=f01
Plan File=p01
Y Axis Title=Elevation
X Axis Title(PF)=Main Channel Distance
X Axis Title(XS)=Station
BEGIN DESCRIPTION:
Mill Creek Trib C
END DESCRIPTION:
DSS File=dss
DSS Export Rating Curves= 0
DSS Export Rating Curve Sorted= 0
DSS Export Volume Flow Curves= 0
DXF OffsetX= 0
DXF OffsetY= 0
DXF ScaleX= 1
DXF ScaleY= 10

--- Mill Creek Trib C.p01 (plan) ---

Plan Title=Multiple Run
Program Version=4.10
Short Identifier=Multiple Run
Geom File=g01
Flow File=f01
Subcritical Flow
K Sum by GR= 0
Std Step Tol= 0.01
Critical Tol= 0.01
Num of Std Step Trials= 20
Max Error Tol= 0.3
Flow Tol Ratio= 0.001
Split Flow NTrial= 30
Split Flow Tol= 0.02
Split Flow Ratio= 0.02
Log Output Level= 0
Friction Slope Method= 1
Unsteady Friction Slope Method= 2
Unsteady Bridges Friction Slope Method= 1
Parabolic Critical Depth
Global Vel Dist= 1 , 1 , 1
Global Log Level= 0
CheckData=True
Encroach Param=-1 ,0,0, 0
BEGIN DESCRIPTION:
Multiple Run
END DESCRIPTION:
Computation Interval=1HOUR
Output Interval=1HOUR
Run HTab= 0
Run UNet= 0
Run PostProcess= 0
Run WQNet= 0
UNET Theta= 1
UNET Theta Warmup= 1
UNET ZTol= 0.02
UNET ZSATol= 0.05
UNET MxIter= 20
UNET MaxInSteps= 0
UNET DtIC= 0
UNET DtMin= 0
UNET MaxCRTS= 20
UNET WFStab= 2
UNET SFStab= 1
UNET WFX= 1
UNET SFX= 1
UNET DSS MLevel= 4
UNET DZMax Abort= 100
UNET Convert EG Bridges= 0
UNET Use Existing IB Tables=-1
UNET Froude Reduction=False
UNET Froude Limit= 1
UNET Froude Power= 10
UNET Time Slicing=0,0, 5
UNET Junction Losses=0
Instantaneous Interval=1HOUR
DSS File=dss
Write IC File= 0
Write IC File at Sim End=0
Echo Input=False
Echo Parameters=False
Echo Output=False
Write Detailed= 0
WQ AD Non Conservative
WQ ULTIMATE=-1
WQ Max Comp Step=1HOUR
WQ Output Interval=15MIN
WQ Output Selected Increments= 0
WQ Output face flow=0
WQ Output face velocity=0
WQ Output face area=0
WQ Output face dispersion=0
WQ Output cell volume=0
WQ Output cell surface area=0
WQ Output cell continuity=0
WQ Output cumulative cell continuity=0
WQ Output face conc=0
WQ Output face dconc_dx=0
WQ Output face courant=0
WQ Output face peclet=0
WQ Output face adv mass=0
WQ Output face disp mass=0
WQ Output cell mass=0
WQ Output cell source sink temp=0
WQ Output cell source sink nsm=0
WQ Output MaxMinRange=-1
WQ Daily Max Min Mean=-1
WQ Daily Range=0
WQ Daily Time=0
WQ Create Restart=0
WQ Fixed Restart=0
WQ System Summary=0
WQ Use Fixed Temperature=0
Sorting and Armoring Iterations= 10
XS Update Threshold= 0.02
Hydraulics Update Threshold= 0.02
Energy Slope Method= 1
Volume Change Method= 0
XS Weighting Method= 0
Number of US Weighted Cross Sections= 1
Number of DS Weighted Cross Sections= 1
Upstream XS Weight=0.25
Main XS Weight=0.5
Downstream XS Weight=0.25
Number of DS XS's Weighted with US Boundary= 1
Upstream Boundary Weight= 1
Weight of XSs Associated with US Boundary= 0
Number of US XS's Weighted with DS Boundary= 1
Downstream Boundary Weight= 0.5
Weight of XSs Associated with DS Boundary= 0.5
Sediment Output Level= 4
Mass or Volume Output= 0
Output Increment Type= 1
Profile and TS Output Increment= 10
XS Output Flag= 0
XS Output Increment= 10
Disregard all LS=0
Disregard all Conn=0
Disregard all Breaches=0
Disregard all Pumps=0

--- Mill Creek Trib C.f01 (steady flow) ---

Flow Title=Multiple
Number of Profiles=7
Profile Names=10-year,25-year,50-year,1pct_min,100-year,1pct_plu,500-year
River Rch & RM= Mill Creek Trib ,Reach-1,7373
     585     795     967     586    1168    2331    1709
River Rch & RM= Mill Creek Trib ,Reach-1,4796
     882    1212    1486     905    1805    3602    2671
Boundary for River Rch & Prof#=Mill Creek Trib ,Reach-1,1
Up Type=0
Dn Type=3
Dn Slope=0.005
Boundary for River Rch & Prof#=Mill Creek Trib ,Reach-1,2
Up Type=0
Dn Type=3
Dn Slope=0.005
Boundary for River Rch & Prof#=Mill Creek Trib ,Reach-1,3
Up Type=0
Dn Type=3
Dn Slope=0.005
Boundary for River Rch & Prof#=Mill Creek Trib ,Reach-1,4
Up Type=0
Dn Type=3
Dn Slope=0.005
Boundary for River Rch & Prof#=Mill Creek Trib ,Reach-1,5
Up Type=0
Dn Type=3
Dn Slope=0.005
Boundary for River Rch & Prof#=Mill Creek Trib ,Reach-1,6
Up Type=0
Dn Type=3
Dn Slope=0.005
Boundary for River Rch & Prof#=Mill Creek Trib ,Reach-1,7
Up Type=0
Dn Type=3
Dn Slope=0.005

--- Mill Creek Trib C.g01 (geometry) ---

Geom Title=Existing Conditions
Program Version=4.10

River Reach=Mill Creek Trib ,Reach-1
Reach XY= 30
        2756226.        6824961.      2756222.25      6824662.55
       2756059.5      6824393.95      2755837.24        6824221.
      2755866.68      6824154.34      2755732.34      6823969.02
      2755503.13      6823910.61      2755356.01      6824011.06
      2755136.19      6823960.55      2754785.59      6823962.22
      2754676.09      6824053.72      2754423.17      6824005.79
      2754377.12      6823951.58      2754372.46      6823712.46
      2754231.55      6823563.37      2754220.74      6823466.47
      2754024.53      6823314.54      2753781.25      6823255.56
      2753768.12      6823154.88      2753628.44      6823016.47
      2753484.15      6823007.42      2753178.43      6822766.52
      2752969.94      6822702.86      2752667.66      6822364.17
      2752573.64      6822355.44      2752465.51      6822261.95
      2752319.27      6822301.85      2751981.18      6822055.56
      2751976.02      6820930.99        2751926.        6820861.

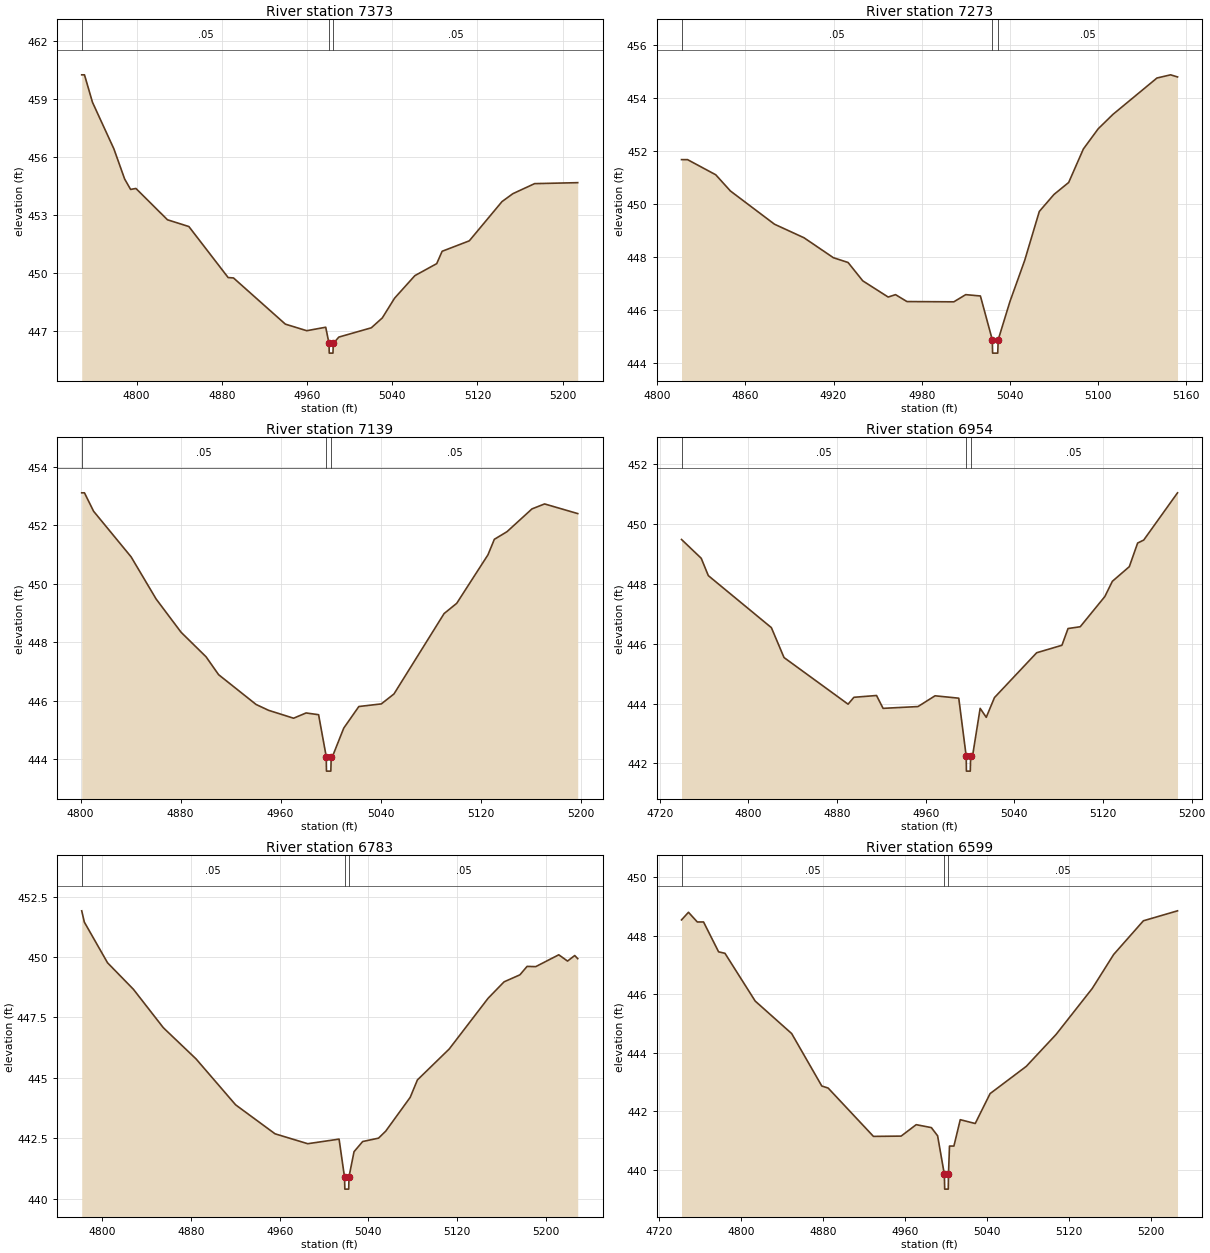
Type RM Length L Ch R = 1 ,7373    ,100,100,100
BEGIN DESCRIPTION:
Mill Creek Trib C7372.817
END DESCRIPTION:
XS GIS Cut Line= 3
      2756476.04        6824911.        2756226.      6824938.11
      2756016.38      6824982.16
#Sta/Elev= 30
  4748.5  460.27  4751.1  460.27  4758.6  458.85  4778.7  456.44  4788.8  454.88
  4794.4  454.34  4799.4  454.39    4829  452.77  4849.1  452.42    4886  449.78
    4891  449.76  4939.7  447.37  4959.8  447.03  4977.6  447.21  4980.7  446.37
  4980.9  445.87  4984.4  445.87  4984.7  446.37  4989.9   446.7  5020.4  447.18
  5030.7  447.69  5042.2  448.71  5061.3  449.88  5081.8   450.5  5086.9  451.14
  5112.4  451.68  5143.1  453.71  5153.3  454.12  5173.7  454.64  5214.2  454.69
#Mann= 3 ,-1 , 0
  4748.5     .05       0  4980.7     .05       0  4984.7     .05       0
Bank Sta=4980.7,4984.7
XS Rating Curve= 0 ,0
Exp/Cntr=0.3,0.1

Type RM Length L Ch R = 1 ,7273    ,134,134,134
BEGIN DESCRIPTION:
Mill Creek Trib C7272.89
END DESCRIPTION:
XS GIS Cut Line= 3
      2756409.26      6824828.27      2756227.16      6824838.14
      2756072.02      6824846.02
#Sta/Elev= 30
  4816.5  451.67  4820.6  451.67  4839.8   451.1  4849.8  450.49  4879.8  449.24
  4899.9  448.73  4919.9  447.98  4929.9   447.8  4939.9  447.11  4957.2   446.5
  4962.2  446.59    4970  446.33  5001.9  446.32    5010  446.59    5020  446.54
  5028.1  444.89  5028.3  444.39  5031.8  444.39  5032.1  444.89  5040.1  446.33
  5050.1  447.87  5060.1  449.72  5070.1  450.36  5080.1  450.81  5090.1  452.07
  5100.2  452.83  5110.2  453.37  5140.2  454.74  5149.5  454.86  5154.2  454.78
#Mann= 3 ,-1 , 0
  4816.5     .05       0  5028.1     .05       0  5032.1     .05       0
Bank Sta=5028.1,5032.1
XS Rating Curve= 0 ,0
Exp/Cntr=0.3,0.1

Type RM Length L Ch R = 1 ,7139    ,185,185,185
BEGIN DESCRIPTION:
Mill Creek Trib C7138.98
END DESCRIPTION:
XS GIS Cut Line= 3
      2756425.53      6824702.68       2756224.9       6824704.3
      2756029.61      6824722.77
#Sta/Elev= 30
  4800.9  453.11  4803.1  453.11  4810.4  452.48  4840.4  450.92  4860.4  449.48
  4880.4  448.34  4900.4   447.5  4910.4  446.89  4940.4  445.87  4950.4  445.67
  4970.4   445.4  4980.4  445.58  4990.4  445.52  4996.5  444.09  4996.7  443.59
  5000.2  443.59  5000.5  444.09  5001.5  444.09  5010.5  445.06  5022.6   445.8
  5040.6  445.89  5050.7  446.23  5090.8  448.98  5100.9  449.33  5125.9  450.99
    5131  451.52  5141.1  451.78  5161.1  452.56  5171.2  452.73  5197.7   452.4
#Mann= 3 ,-1 , 0
  4800.9     .05       0  4996.5     .05       0  5000.5     .05       0
Bank Sta=4996.5,5000.5
XS Rating Curve= 0 ,0
Exp/Cntr=0.3,0.1

Type RM Length L Ch R = 1 ,6954    ,171,171,171
BEGIN DESCRIPTION:
Mill Creek Trib C6953.82
END DESCRIPTION:
XS GIS Cut Line= 3
      2756402.87      6824457.94      2756153.89      6824541.51
      2755986.66      6824620.56
#Sta/Elev= 30
  4739.6  449.49  4757.4  448.86  4763.8  448.28  4820.7  446.54  4832.1  445.54
  4889.9  443.98  4895.2  444.21  4915.6  444.27  4921.5  443.84    4953   443.9
  4968.4  444.26  4989.8  444.18  4996.5  442.24  4996.7  441.74  5000.2  441.74
  5000.5  442.24  5002.2  442.24  5009.1  443.84  5014.6  443.54    5022   444.2
  5060.1   445.7  5082.9  445.95  5088.4  446.51  5099.4  446.57  5121.6  447.58
  5128.4  448.09  5143.7  448.58  5151.2  449.37  5156.7  449.47  5187.2  451.05
#Mann= 3 ,-1 , 0
  4739.6     .05       0  4996.5     .05       0  5000.5     .05       0
Bank Sta=4996.5,5000.5
XS Rating Curve= 0 ,0
Exp/Cntr=0.3,0.1

Type RM Length L Ch R = 1 ,6783    ,184,184,184
BEGIN DESCRIPTION:
Mill Creek Trib C6783.14
END DESCRIPTION:
XS GIS Cut Line= 3
      2756244.73      6824275.88      2756063.73      6824404.85
      2755890.39        6824549.
#Sta/Elev= 30
  4781.3  451.91  4783.7  451.44  4804.6  449.76    4828  448.66    4855  447.07
  4884.5  445.78  4920.2  443.88  4955.8  442.68  4985.3  442.27  5013.6  442.46
  5018.5  440.89  5018.8  440.39  5022.3  440.39  5022.5  440.89  5027.1  441.94
  5034.9  442.36  5049.2   442.5  5055.7  442.79  5077.8  444.19  5084.3  444.91
    5113  446.19  5148.1  448.29  5162.5  448.97  5176.8  449.26  5183.3  449.61
  5191.1   449.6  5211.9  450.09  5219.8  449.83  5226.3  450.06    5229  449.93
#Mann= 3 ,-1 , 0
  4781.3     .05       0  5018.5     .05       0  5022.5     .05       0
Bank Sta=5018.5,5022.5
XS Rating Curve= 0 ,0
Exp/Cntr=0.3,0.1

Type RM Length L Ch R = 1 ,6599    ,237,237,237
BEGIN DESCRIPTION:
Mill Creek Trib C6598.83
END DESCRIPTION:
XS GIS Cut Line= 3
      2756128.63      6824153.57       2755916.2      6824306.02
       2755781.1      6824482.84
#Sta/Elev= 30
  4741.8  448.54  4748.6   448.8  4757.2  448.47  4763.3  448.47    4778  447.45
  4784.2   447.4  4813.7  445.77  4849.3  444.66  4878.7  442.87  4884.9   442.8
  4929.1  441.15  4956.1  441.16  4970.8  441.55  4985.6  441.45  4991.7  441.17
  4998.3  439.85  4998.6  439.35  5002.1  439.35  5002.3  439.85  5003.3  440.82
  5007.6  440.82  5013.8  441.72  5028.4  441.59  5042.9  442.61  5078.2  443.54
  5107.3  444.63  5142.6   446.2  5163.5  447.36  5192.5  448.51  5225.8  448.85
#Mann= 3 ,-1 , 0
  4741.8     .05       0  4998.3     .05       0  5002.3     .05       0
Bank Sta=4998.3,5002.3
XS Rating Curve= 0 ,0
Exp/Cntr=0.3,0.1

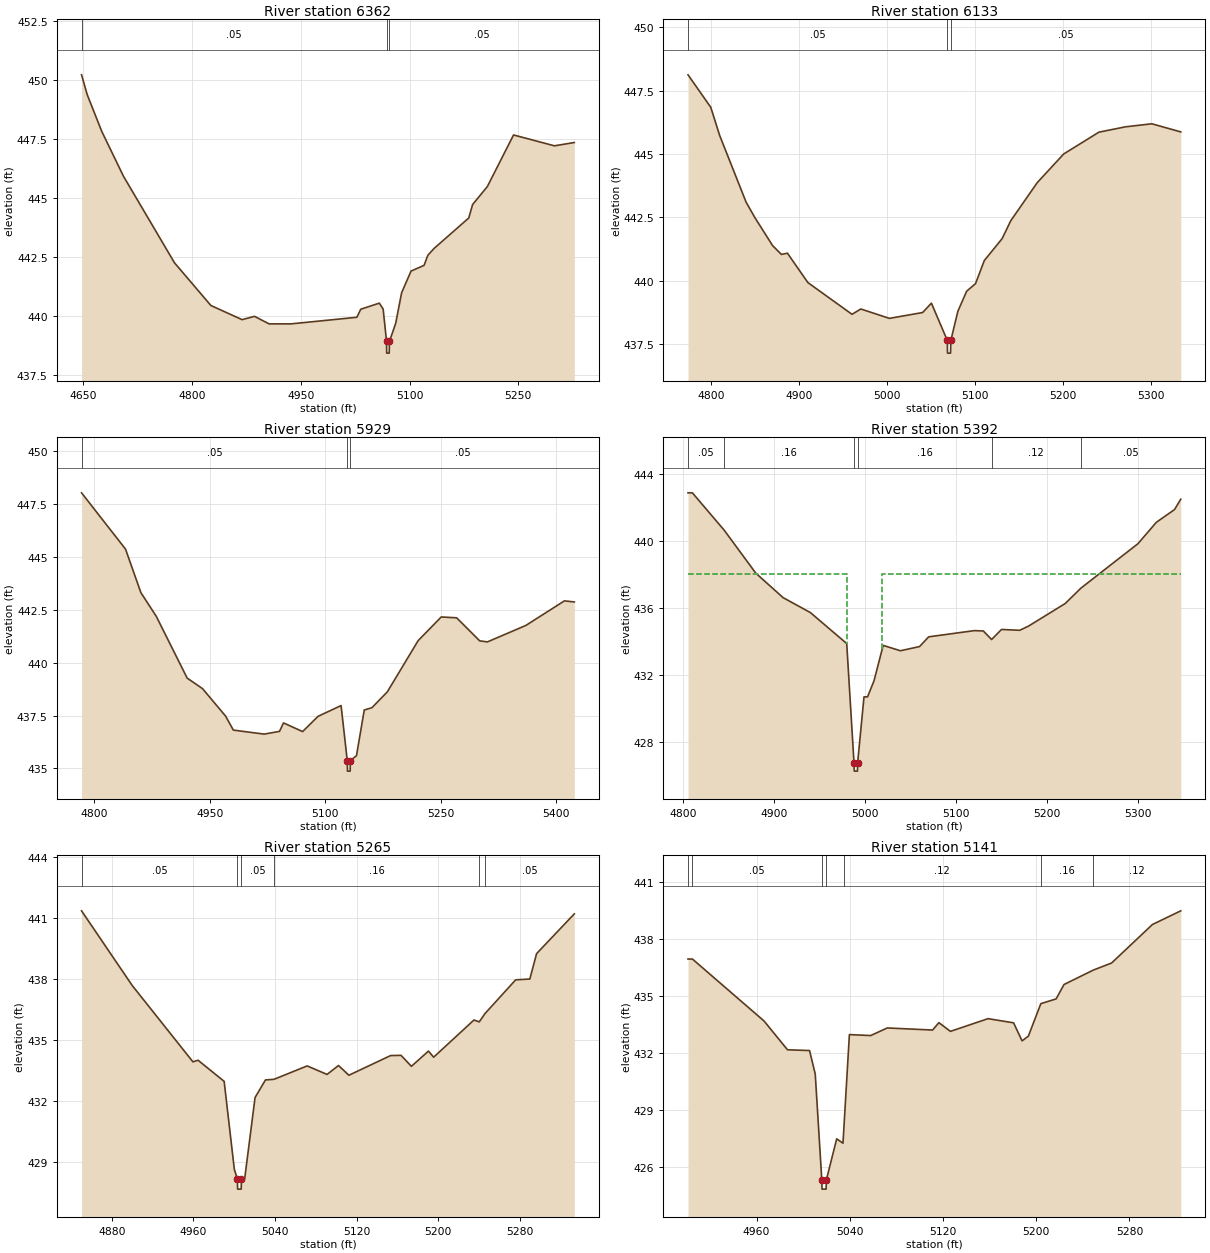
Type RM Length L Ch R = 1 ,6362    ,229,229,229
BEGIN DESCRIPTION:
Mill Creek Trib C6362.44
END DESCRIPTION:
XS GIS Cut Line= 3
      2755868.88      6823773.19      2755839.61      6824130.97
      2755732.31      6824433.21
#Sta/Elev= 30
  4647.5  450.23  4655.3  449.39  4675.4  447.83  4705.5  445.92  4775.7  442.26
  4825.9  440.45  4868.9  439.85  4886.1  439.99  4906.2  439.67  4936.3  439.67
  5027.3  439.95  5032.6  440.29  5058.2  440.55  5063.5   440.3  5068.2  438.93
  5068.4  438.43  5071.9  438.43  5072.2  438.93  5080.8  439.69    5089  440.99
    5102  441.91  5119.9  442.15  5125.2  442.58  5133.8  442.87  5181.6  444.16
  5186.9  444.73  5207.2  445.49  5243.4  447.68  5299.8  447.22  5327.2  447.36
#Mann= 3 ,-1 , 0
  4647.5     .05       0  5068.2     .05       0  5072.2     .05       0
Bank Sta=5068.2,5072.2
XS Rating Curve= 0 ,0
Exp/Cntr=0.3,0.1

Type RM Length L Ch R = 1 ,6133    ,204,204,204
BEGIN DESCRIPTION:
Mill Creek Trib C6133.16
END DESCRIPTION:
XS GIS Cut Line= 3
      2755721.52      6823735.19      2755700.55      6823963.29
      2755674.89      6824293.83
#Sta/Elev= 30
  4773.4  448.12  4799.3  446.84  4809.4  445.73  4839.5   443.1  4849.5  442.49
  4869.6  441.39  4879.7  441.04  4886.5  441.09  4909.8  439.93    4960  438.68
    4970  438.89  5002.5  438.52  5040.3  438.75  5050.3  439.12  5068.4  437.65
  5068.6  437.15  5072.1  437.15  5072.4  437.65  5080.4   438.8  5090.4  439.59
  5100.5  439.89  5110.5   440.8  5130.7  441.66  5140.6  442.37  5170.7  443.87
  5200.8     445  5240.9  445.86    5271  446.07  5301.1  446.19    5334  445.87
#Mann= 3 ,-1 , 0
  4773.4     .05       0  5068.4     .05       0  5072.4     .05       0
Bank Sta=5068.4,5072.4
XS Rating Curve= 0 ,0
Exp/Cntr=0.3,0.1

Type RM Length L Ch R = 1 ,5929    ,537,537,537
BEGIN DESCRIPTION:
Mill Creek Trib C5928.8
END DESCRIPTION:
XS GIS Cut Line= 3
      2755518.58      6823693.89      2755512.09      6823915.86
      2755500.84      6824333.85
#Sta/Elev= 30
  4783.3  448.03  4840.4  445.37  4860.4  443.31  4880.4  442.19  4920.5  439.27
  4940.5  438.77  4970.5  437.47  4980.5  436.81  5020.5  436.62  5040.5  436.75
  5045.7  437.15  5070.5  436.74  5090.5  437.46  5120.5  437.97  5128.5  435.37
  5128.8  434.87  5132.3  434.87  5132.5  435.37  5140.5   435.6  5150.6  437.76
  5160.6  437.87  5180.6  438.62  5220.6  441.04  5250.6  442.16  5270.6  442.12
  5300.6  441.03  5310.6  440.98  5360.6  441.76  5410.6  442.92  5423.5  442.87
#Mann= 3 ,-1 , 0
  4783.3     .05       0  5128.5     .05       0  5132.5     .05       0
Bank Sta=5128.5,5132.5
XS Rating Curve= 0 ,0
Exp/Cntr=0.3,0.1

Type RM Length L Ch R = 1 ,5392    ,127,127,127
BEGIN DESCRIPTION:
Mill Creek Trib C5392.33
END DESCRIPTION:
XS GIS Cut Line= 3
      2755030.65      6823766.47      2755029.17      6823963.89
      2755044.95       6824307.9
#Sta/Elev= 30
  4805.5  442.86  4810.3  442.86  4845.3  440.63    4880  438.07    4910  436.61
    4940  435.72    4980  433.87    4988  426.76  4988.3  426.26  4991.8  426.26
    4992  426.76    4999  430.69  5002.9  430.69    5010  431.65  5020.1  433.76
    5039  433.44  5060.1  433.69  5070.1  434.27  5120.2  434.64  5130.2  434.62
  5139.3  434.11  5150.2  434.71  5170.2  434.66  5180.2  434.92  5220.3  436.26
  5237.4  437.17  5300.3  439.83  5320.4   441.1  5340.4  441.86  5347.3  442.48
#Mann= 6 ,-1 , 0
  4805.5     .05       0  4845.3     .16       0    4988     .07       0
    4992     .16       0  5139.3     .12       0  5237.4     .05       0
#XS Ineff= 2 , 0
       0    4980     438    5019       0     438
Permanent Ineff=
       F       F
Bank Sta=4988,4992
XS Rating Curve= 0 ,0
Exp/Cntr=0.3,0.1

Type RM Length L Ch R = 1 ,5265    ,124,124,124
BEGIN DESCRIPTION:
Mill Creek Trib C5265.32
END DESCRIPTION:
XS GIS Cut Line= 3
      2754897.27      6823811.32      2754902.34      6823966.01
      2754970.32      6824287.22
#Sta/Elev= 30
  4850.3  441.37    4900  437.69  4959.5  433.93  4964.5  434.01  4990.1  432.97
  5000.1  428.63  5003.1  428.16  5003.3  427.66  5006.8  427.66  5007.1  428.16
  5010.2  428.16  5020.4  432.17  5030.6  433.04    5039  433.07  5071.5  433.73
    5091  433.31  5102.2  433.75  5112.4  433.27  5153.3  434.24  5163.5  434.25
  5173.7  433.71  5190.4  434.46  5195.5  434.16    5235  435.99  5240.2   435.9
  5245.7   436.3  5275.9  437.97  5289.8  438.01  5296.4  439.26  5333.4  441.22
#Mann= 6 ,-1 , 0
  4850.3     .05       0  5003.1     .05       0  5007.1     .05       0
    5039     .16       0  5240.2     .12       0  5245.7     .05       0
Bank Sta=5003.1,5007.1
XS Rating Curve= 0 ,0
Exp/Cntr=0.3,0.1

Type RM Length L Ch R = 1 ,5141    ,87,87,87
BEGIN DESCRIPTION:
Mill Creek Trib C5141.21
END DESCRIPTION:
XS GIS Cut Line= 3
      2754763.65      6823866.54      2754778.85      6823966.91
      2754902.83      6824263.42
#Sta/Elev= 30
  4901.2  436.95    4905  436.95  4966.4  433.69  4986.6  432.17  5005.5  432.13
  5010.4  430.89    5016  425.33  5016.2  424.83  5019.7  424.83    5020  425.33
  5028.8  427.48  5034.2  427.25  5034.7  427.77  5039.7  432.97    5058  432.92
  5072.2  433.32  5111.1  433.21  5116.5   433.6  5126.4  433.14  5158.7  433.81
  5180.6  433.59  5187.9  432.64  5193.3  432.89    5204   434.6  5217.1  434.85
  5223.9  435.61  5249.1  436.37  5264.7  436.74  5299.8  438.77  5324.1  439.49
#Mann= 7 ,-1 , 0
  4901.2     .16       0    4905     .05       0    5016     .05       0
    5020     .05       0  5034.7     .12       0    5204     .16       0
  5249.1     .12       0
Bank Sta=5016,5020
XS Rating Curve= 0 ,0
Exp/Cntr=0.3,0.1

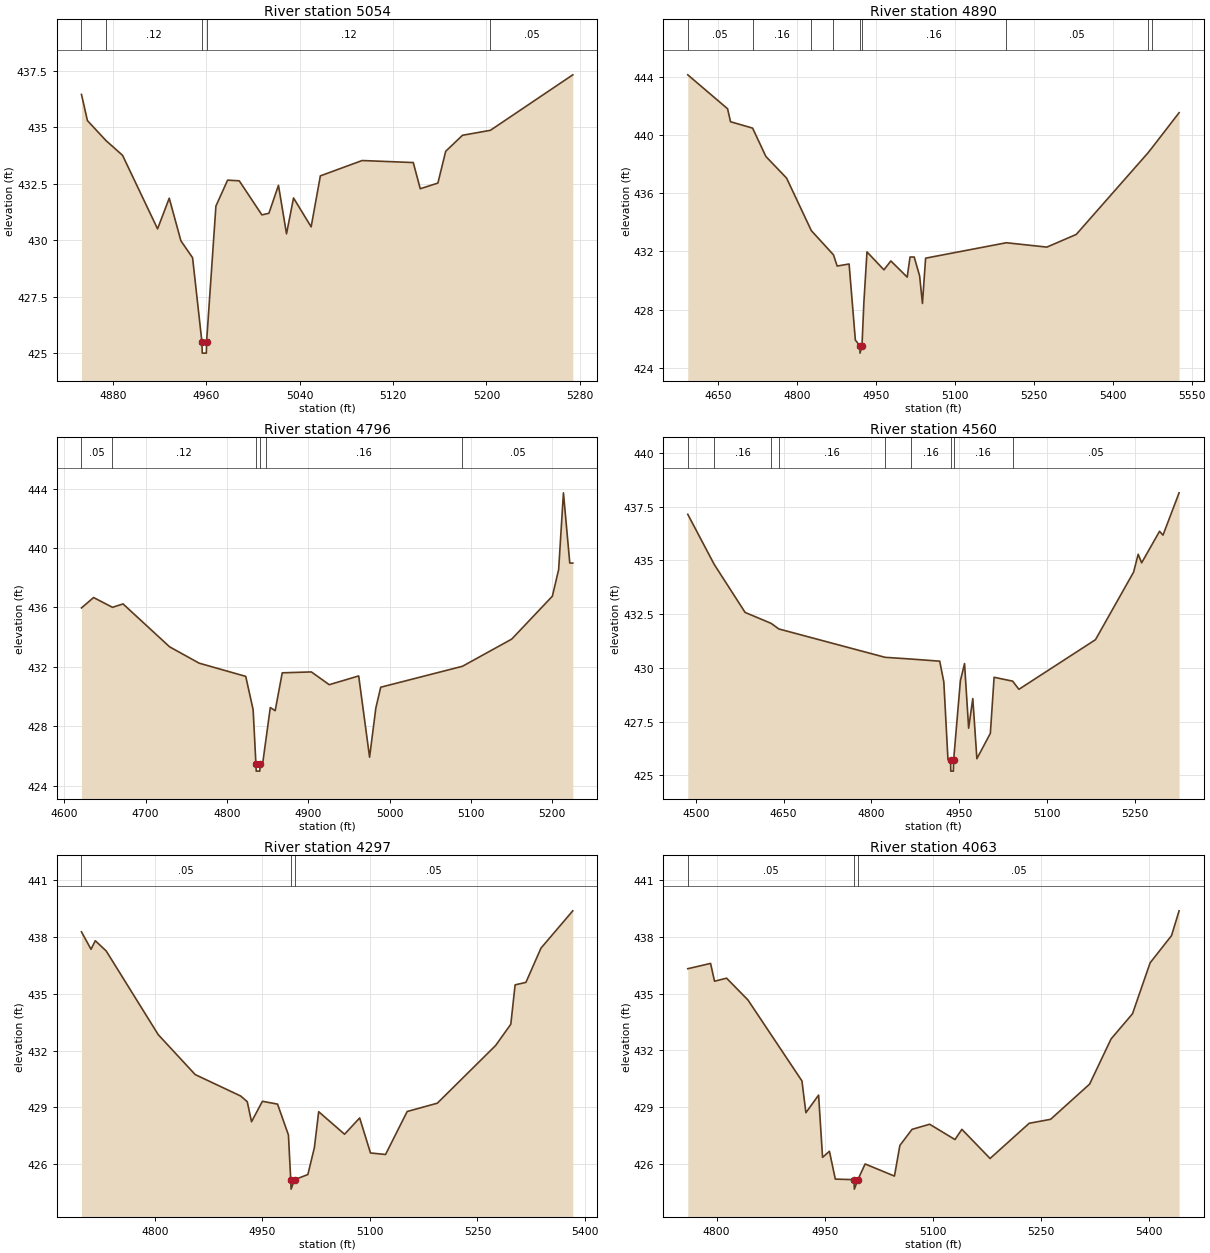
Type RM Length L Ch R = 1 ,5054    ,164,164,164
BEGIN DESCRIPTION:
Mill Creek Trib C5054.32
END DESCRIPTION:
XS GIS Cut Line= 3
      2754720.43      6823875.87      2754714.67       6824022.5
      2754864.56      6824252.17
#Sta/Elev= 30
    4853  436.46  4858.1   435.3  4873.9  434.42  4888.2  433.76  4918.2   430.5
  4928.2  431.86  4938.2  429.97  4948.2  429.22  4956.2  425.49  4956.5  424.99
    4960  424.99  4960.2  425.49  4968.2  431.51  4978.2  432.66  4988.2  432.63
  5007.6  431.12  5013.6  431.19  5021.8  432.43  5028.7  430.28  5034.7  431.87
  5049.8  430.59  5057.7  432.85  5093.5  433.53  5137.3  433.44  5143.3  432.28
  5158.4  432.53  5165.1  433.94  5179.5  434.65  5203.4  434.87    5274  437.33
#Mann= 5 ,-1 , 0
    4853     .16       0  4873.9     .12       0  4956.2     .07       0
  4960.2     .12       0  5203.4     .05       0
Bank Sta=4956.2,4960.2
XS Rating Curve= 0 ,0
Exp/Cntr=0.3,0.1

Type RM Length L Ch R = 1 ,4890    ,94,94,94
BEGIN DESCRIPTION:
Mill Creek Trib C4889.823
END DESCRIPTION:
XS GIS Cut Line= 5
      2754875.99        6823761.      2754650.11      6823872.77
      2754576.29       6824010.4        2754651.        6824186.
      2754950.96      6824335.98
#Sta/Elev= 30
  4591.8  444.13  4667.5   441.8  4673.1  440.91  4715.1  440.47  4740.4  438.52
  4779.7  437.04  4826.8  433.43  4868.9  431.77  4875.9     431  4898.6  431.14
  4910.5  425.92  4919.1  425.52  4919.3  425.02  4923.1  425.52  4926.7  428.49
  4932.6  431.97  4964.9  430.74    4978  431.35  5009.1  430.24  5014.5  431.62
  5022.4  431.62  5032.7  430.33  5038.1  428.43  5044.1  431.54  5197.7   432.6
  5274.7   432.3  5330.6  433.17    5467  438.77  5474.9  439.13  5526.2  441.53
#Mann= 9 ,-1 , 0
  4591.8     .05       0  4715.1     .16       0  4826.8     .12       0
  4868.9     .16       0  4919.1     .07       0  4923.1     .16       0
  5197.7     .05       0    5467     .12       0  5474.9     .05       0
Bank Sta=4919.1,4923.1
XS Rating Curve= 0 ,0
Exp/Cntr=0.3,0.1

Type RM Length L Ch R = 1 ,4796    ,236,236,236
BEGIN DESCRIPTION:
Mill Creek Trib C4796.24
END DESCRIPTION:
XS GIS Cut Line= 3
      2754689.49      6823694.09      2754481.88      6824012.87
      2754362.63      6824202.23
#Sta/Elev= 30
  4621.1  435.96    4636  436.66  4659.2     436  4672.2  436.23  4729.5  433.34
  4765.8  432.24  4823.1  431.35  4832.2   429.1  4835.6  425.47    4836  424.97
  4840.4  424.97  4840.8  425.47  4844.2   425.6  4847.5  426.92  4853.3  429.25
  4859.3  429.04    4868  431.59  4903.8  431.65  4925.8  430.79    4962  431.38
  4975.4  425.91  4983.1  429.22  4989.1  430.62  5089.6  432.03  5150.2  433.86
  5200.2  436.75  5207.9  438.54  5213.8  443.71  5221.6  438.98  5225.3  438.98
#Mann= 6 ,-1 , 0
  4621.1     .05       0  4659.2     .12       0  4835.6     .07       0
  4840.8     .12       0  4847.5     .16       0  5089.6     .05       0
Bank Sta=4835.6,4840.8
XS Rating Curve= 0 ,0
Exp/Cntr=0.3,0.1

Type RM Length L Ch R = 1 ,4560    ,263,263,263
BEGIN DESCRIPTION:
Mill Creek Trib C4560.35
END DESCRIPTION:
XS GIS Cut Line= 3
      2754735.82      6823482.15      2754375.61      6823849.24
      2754100.21      6824022.19
#Sta/Elev= 30
  4486.2  437.15  4531.3  434.82  4584.2  432.58  4628.7  432.07  4641.9  431.81
  4823.3  430.49  4867.4  430.41  4916.7  430.31  4923.7  429.34  4930.8  425.72
  4935.2  425.69  4935.6  425.19    4940  425.19  4940.4  425.69    4952   429.4
  4959.1   430.2  4966.1  427.19  4973.2  428.57  4980.2  425.77  5003.2  426.95
  5009.6  429.56  5041.3  429.38    5052     429  5182.8  431.31    5248  434.46
  5255.8  435.29  5261.7  434.89  5292.3  436.36  5298.2  436.18  5325.7  438.15
#Mann= 9 ,-1 , 0
  4486.2     .05       0  4531.3     .16       0  4628.7     .05       0
  4641.9     .16       0  4823.3     .05       0  4867.4     .16       0
  4935.2     .07       0  4940.4     .16       0  5041.3     .05       0
Bank Sta=4935.2,4940.4
XS Rating Curve= 0 ,0
Exp/Cntr=0.3,0.1

Type RM Length L Ch R = 1 ,4297    ,234,234,234
BEGIN DESCRIPTION:
Mill Creek Trib C4296.71
END DESCRIPTION:
XS GIS Cut Line= 3
      2754449.06       6823366.1      2754282.55      6823625.31
      2754075.01      6823940.66
#Sta/Elev= 30
  4697.4  438.27  4710.7  437.35  4716.7   437.8  4731.9  437.26  4804.5  432.84
  4856.1  430.73  4919.5   429.6  4928.7   429.3  4934.7  428.24  4949.9  429.32
    4971  429.17  4986.2  427.54  4989.4  425.18  4989.9  424.68  4994.8  425.18
  5013.3  425.45  5022.4  426.87  5028.4  428.77  5064.5  427.58  5085.6  428.44
  5100.7  426.59  5121.7  426.51  5151.9  428.78    5194  429.22  5275.4  432.27
  5296.5  433.39  5302.5  435.47  5317.6   435.6  5338.6  437.41    5383  439.38
#Mann= 3 ,-1 , 0
  4697.4     .05       0  4989.4     .05       0  4994.8     .05       0
Bank Sta=4989.4,4994.8
XS Rating Curve= 0 ,0
Exp/Cntr=0.3,0.1

Type RM Length L Ch R = 1 ,4063    ,154,154,154
BEGIN DESCRIPTION:
Mill Creek Trib C4062.62
END DESCRIPTION:
XS GIS Cut Line= 3
      2754266.08      6823231.92      2754165.08      6823456.38
      2754005.36      6823861.18
#Sta/Elev= 30
    4760  436.32  4791.6   436.6  4797.1  435.66  4813.8  435.82  4843.4  434.67
  4918.3  430.39  4923.8  428.71  4941.4  429.64  4946.9  426.35  4956.4  426.67
  4964.6   425.2  4990.5  425.17    4991  424.67  4995.9  425.17  5005.9     426
  5046.6  425.36  5054.1  426.98    5071  427.83  5095.4   428.1  5130.5  427.29
  5140.1  427.83  5179.2  426.29  5233.4  428.15  5263.1  428.36  5317.2  430.22
    5347  432.61  5376.7  433.94  5401.1  436.63  5430.8  438.07  5441.3  439.38
#Mann= 3 ,-1 , 0
    4760     .05       0  4990.5     .05       0  4995.9     .05       0
Bank Sta=4990.5,4995.9
XS Rating Curve= 0 ,0
Exp/Cntr=0.3,0.1

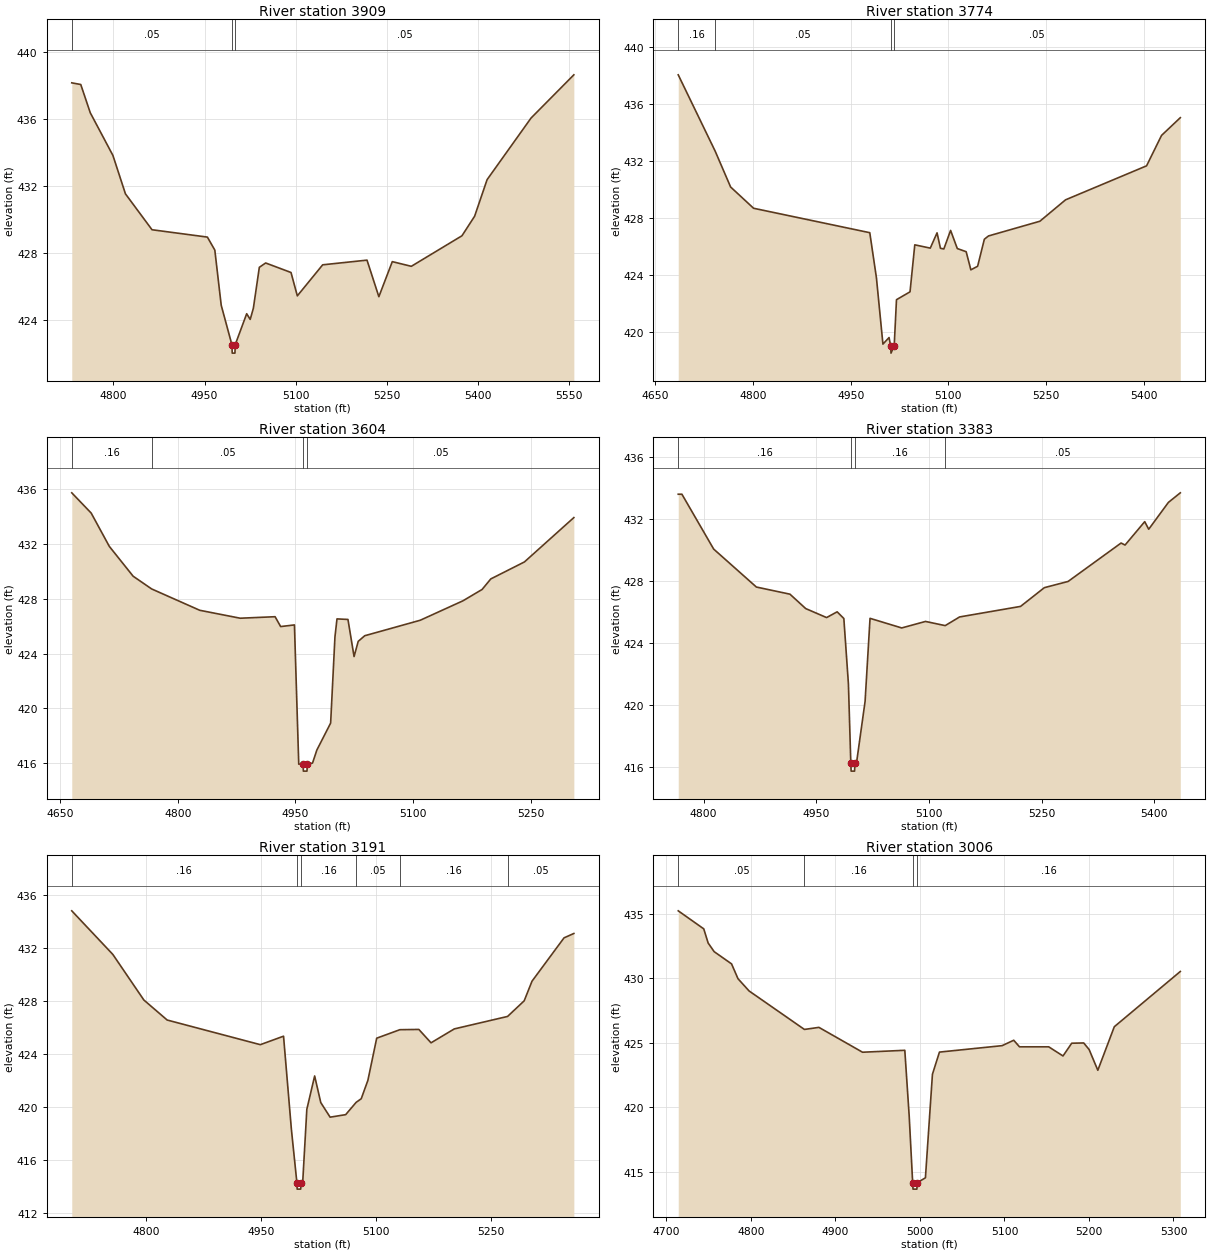
Type RM Length L Ch R = 1 ,3909    ,135,135,135
BEGIN DESCRIPTION:
Mill Creek Trib C3908.69
END DESCRIPTION:
XS GIS Cut Line= 3
      2754140.22      6823086.92      2754057.55      6823344.67
      2753902.53       6823877.7
#Sta/Elev= 30
  4731.5  438.18  4746.3  438.08  4761.9  436.39  4799.2  433.83  4819.8  431.53
  4863.5  429.38  4954.6  428.94  4966.8  428.16  4977.3  424.86  4994.9  422.49
  4995.4  421.99  4999.9  421.99  5000.3  422.49  5019.2  424.35    5025  424.01
  5030.2  424.68    5040  427.13  5050.4  427.39  5092.1  426.82  5102.5  425.42
  5144.2  427.28  5217.1  427.56  5236.6  425.37  5258.7  427.47    5290  427.19
  5373.3  429.02  5394.1  430.19  5414.6  432.38  5486.9  436.07  5557.3  438.66
#Mann= 3 ,-1 , 0
  4731.5     .05       0  4994.9     .05       0  5000.3     .05       0
Bank Sta=4994.9,5000.3
XS Rating Curve= 0 ,0
Exp/Cntr=0.3,0.1

Type RM Length L Ch R = 1 ,3774    ,170,170,170
BEGIN DESCRIPTION:
Mill Creek Trib C3773.8
END DESCRIPTION:
XS GIS Cut Line= 3
      2753992.35      6823001.95      2753933.31      6823315.69
      2753812.53       6823750.9
#Sta/Elev= 30
  4685.3  438.02  4742.2  432.66  4765.7  430.17    4801  428.68  4979.4  426.97
  4989.6  423.82  4999.6  419.17    5009  419.63  5011.5  419.04    5012  418.54
  5016.9  419.04  5020.4  422.28  5041.2  422.83  5048.5  426.12  5072.3  425.89
  5082.7  426.96  5087.9  425.88  5093.1  425.83  5103.5  427.13  5113.8  425.86
  5127.4  425.64  5134.6  424.37    5145  424.62  5155.3  426.51  5161.6  426.74
  5240.5  427.77    5280  429.27  5404.4  431.65  5427.4  433.78  5456.2  435.02
#Mann= 4 ,-1 , 0
  4685.3     .16       0  4742.2     .05       0  5011.5     .05       0
  5016.9     .05       0
Bank Sta=5011.5,5016.9
XS Rating Curve= 0 ,0
Exp/Cntr=0.3,0.1

Type RM Length L Ch R = 1 ,3604    ,221,221,221
BEGIN DESCRIPTION:
Mill Creek Trib C3603.69
END DESCRIPTION:
XS GIS Cut Line= 3
       2753919.5      6822949.64      2753779.74      6823257.98
      2753670.48      6823539.81
#Sta/Elev= 30
  4664.5  435.75  4689.3  434.27  4712.4  431.84  4742.8  429.66  4766.4  428.73
  4827.8  427.17  4879.5  426.59    4924   426.7  4931.1  425.98  4948.7   426.1
  4954.2  415.93  4959.7  415.92  4960.1  415.42  4964.7  415.42  4965.1  415.92
  4971.8  416.01  4977.3  416.96  4994.9  418.93  5000.4  425.22    5003  426.54
    5017   426.5  5024.8  423.79  5030.1   424.9  5038.4  425.31  5109.2  426.44
  5163.7  427.86  5188.2  428.69  5199.3  429.46  5242.2   430.7  5305.3  433.94
#Mann= 4 ,-1 , 0
  4664.5     .16       0  4766.4     .05       0  4959.7     .05       0
  4965.1     .05       0
Bank Sta=4959.7,4965.1
XS Rating Curve= 0 ,0
Exp/Cntr=0.3,0.1

Type RM Length L Ch R = 1 ,3383    ,192,192,192
BEGIN DESCRIPTION:
Mill Creek Trib C3383.47
END DESCRIPTION:
XS GIS Cut Line= 3
      2753818.32      6822877.94      2753684.25      6823073.82
      2753546.47      6823482.65
#Sta/Elev= 30
  4766.1  433.63    4771  433.63  4813.3  430.09  4870.2  427.64  4914.9  427.18
  4935.9  426.25  4963.7  425.67  4977.8  426.04  4986.7  425.61  4992.8  421.39
    4996  416.26  4996.4  415.76    5001  415.76  5001.4  416.26  5003.5  416.26
    5015  420.26  5021.6  425.62  5063.8     425  5095.5  425.42  5121.7  425.15
  5140.9  425.71  5222.1  426.39  5253.8   427.6  5285.4     428    5356  430.48
  5361.3  430.35  5387.5  431.86  5392.8  431.37    5419   433.1  5434.9  433.72
#Mann= 4 ,-1 , 0
  4766.1     .16       0    4996     .07       0  5001.4     .16       0
  5121.7     .05       0
Bank Sta=4996,5001.4
XS Rating Curve= 0 ,0
Exp/Cntr=0.3,0.1

Type RM Length L Ch R = 1 ,3191    ,185,185,185
BEGIN DESCRIPTION:
Mill Creek Trib C3190.53
END DESCRIPTION:
XS GIS Cut Line= 3
      2753563.28      6822718.09      2753515.29      6823015.62
      2753458.33      6823364.93
#Sta/Elev= 30
  4702.8  434.79  4756.4   431.5  4796.9  428.06  4827.3  426.55  4948.9  424.69
  4979.2  425.33  4989.4  418.33  4996.6  414.29    4997  413.79  5001.6  413.79
  5002.1  414.29  5004.2  414.29  5009.6  419.81  5019.8  422.33  5027.8  420.32
    5040  419.22  5060.3  419.41    5074  420.34  5080.6  420.61  5089.3     422
  5100.8  425.18    5131  425.82  5155.8  425.84  5171.7  424.83  5202.1  425.88
  5271.6  426.82  5293.3     428  5303.5  429.48  5345.3  432.75  5358.1  433.08
#Mann= 6 ,-1 , 0
  4702.8     .16       0  4996.6     .07       0  5002.1     .16       0
    5074     .05       0    5131     .16       0  5271.6     .05       0
Bank Sta=4996.6,5002.1
XS Rating Curve= 0 ,0
Exp/Cntr=0.3,0.1

Type RM Length L Ch R = 1 ,3006    ,150,150,150
BEGIN DESCRIPTION:
Mill Creek Trib C3005.54
END DESCRIPTION:
XS GIS Cut Line= 3
      2753449.43       6822639.9      2753376.49      6822920.04
      2753303.19      6823215.71
#Sta/Elev= 30
    4714  435.25  4744.2  433.85  4749.4  432.75  4756.5  432.08  4777.1  431.13
  4784.7  429.98  4797.8  429.03  4863.3  426.04  4880.5   426.2  4932.1  424.27
  4982.1  424.42  4987.3  419.31  4991.4  414.14  4991.8  413.64  4996.4  413.64
  4996.9  414.14  5006.5  414.52  5014.8  422.56  5023.1  424.28  5097.2  424.78
    5111   425.2  5117.8  424.69  5152.4  424.69  5169.3  423.98  5179.6  424.97
  5193.8  424.99  5200.2  424.48  5210.5  422.87    5230  426.25  5308.1  430.54
#Mann= 4 ,-1 , 0
    4714     .05       0  4863.3     .16       0  4991.4     .07       0
  4996.9     .16       0
Bank Sta=4991.4,4996.9
XS Rating Curve= 0 ,0
Exp/Cntr=0.3,0.1

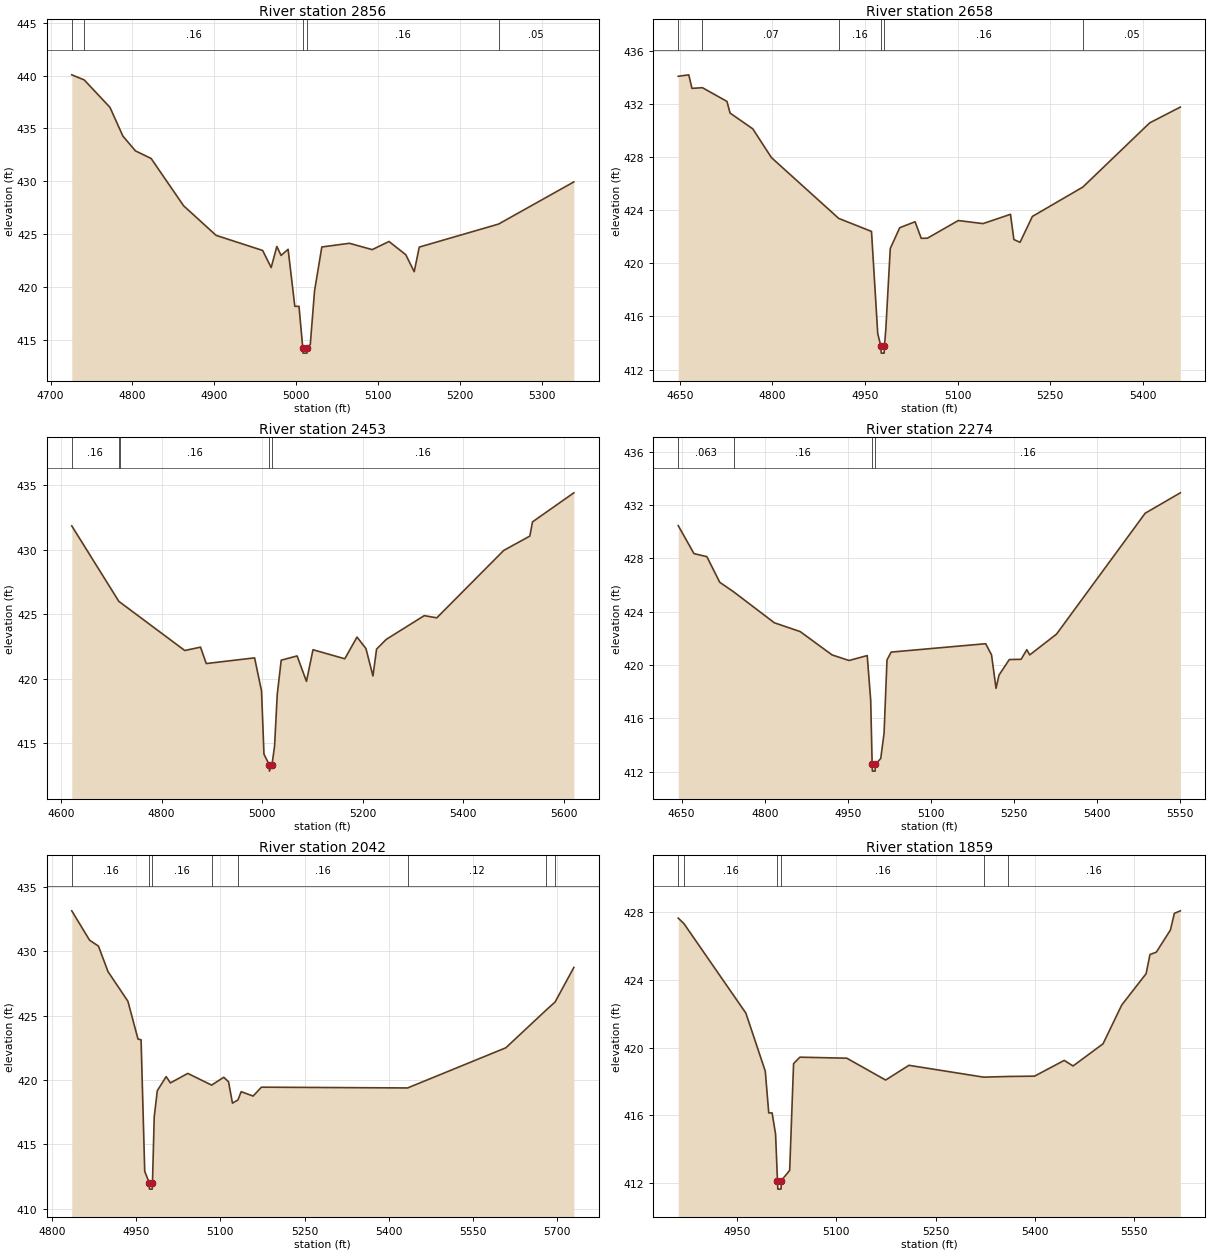
Type RM Length L Ch R = 1 ,2856    ,198,198,198
BEGIN DESCRIPTION:
Mill Creek Trib C2855.81
END DESCRIPTION:
XS GIS Cut Line= 3
       2753327.5      6822575.94      2753254.91      6822841.76
       2753178.6      6823171.08
#Sta/Elev= 30
  4725.9  440.08  4741.1   439.6  4772.6     437  4788.3  434.29  4803.7  432.88
  4822.9  432.16  4862.6  427.68  4902.3  424.88  4959.2  423.45  4969.6  421.83
  4976.5  423.83  4981.7  422.98  4990.3  423.56  4998.5  418.16  5003.6  418.16
  5008.2  414.23  5008.6  413.73  5013.3  413.73  5013.7  414.23  5017.4  414.55
  5022.6  419.62  5031.5  423.78  5065.2  424.13  5093.1  423.53  5113.6   424.3
  5134.1  423.05  5144.4  421.44  5150.6  423.77  5247.5  425.95  5339.5  429.94
#Mann= 5 ,-1 , 0
  4725.9     .05       0  4741.1     .16       0  5008.2     .07       0
  5013.7     .16       0  5247.5     .05       0
Bank Sta=5008.2,5013.7
XS Rating Curve= 0 ,0
Exp/Cntr=0.3,0.1

Type RM Length L Ch R = 1 ,2658    ,205,205,205
BEGIN DESCRIPTION:
Mill Creek Trib C2657.8
END DESCRIPTION:
XS GIS Cut Line= 3
      2753144.15      6822411.79      2753087.06       6822766.3
      2753071.66      6823220.56
#Sta/Elev= 30
  4647.4   434.1  4664.5  434.21  4669.6  433.19  4686.6  433.24  4726.3  432.21
  4731.4  431.33  4768.2  430.14  4798.5  427.97  4907.5  423.39  4960.6  422.41
  4970.7  414.71  4975.9  413.74  4976.4  413.24  4981.1  413.24  4981.5  413.74
  4983.8  415.05    4991  421.12  5006.3  422.69  5031.2  423.14  5041.2  421.89
  5051.2   421.9  5101.2  423.23  5141.3     423  5185.8   423.7  5191.3   421.8
  5201.3  421.59  5221.3  423.54    5303  425.75  5411.4  430.59    5461  431.78
#Mann= 6 ,-1 , 0
  4647.4     .16       0  4686.6     .07       0  4907.5     .16       0
  4975.9     .07       0  4981.5     .16       0    5303     .05       0
Bank Sta=4975.9,4981.5
XS Rating Curve= 0 ,0
Exp/Cntr=0.3,0.1

Type RM Length L Ch R = 1 ,2453    ,179,179,179
BEGIN DESCRIPTION:
Mill Creek Trib C2453.08
END DESCRIPTION:
XS GIS Cut Line= 3
      2753052.04      6822300.44      2752917.63      6822660.89
      2752724.94      6823243.35
#Sta/Elev= 30
  4621.5  431.83  4715.2  425.98  4717.7  425.91  4846.2  422.18  4877.5  422.44
  4888.9  421.17    4985  421.61  4998.8  419.04  5003.6  414.16    5014  413.34
  5014.5  412.84  5019.6  413.34  5024.7  414.77    5030  418.77  5037.9  421.43
  5069.5  421.76  5088.1  419.79  5101.1  422.24  5164.3  421.54  5188.6  423.22
  5206.4  422.33  5220.3  420.21  5227.5  422.29  5246.7  423.04  5322.3  424.88
  5347.2  424.71  5480.3  429.93  5532.2  431.04  5537.5  432.14  5619.7  434.39
#Mann= 5 ,-1 , 0
  4621.5     .16       0  4715.2     .07       0  4717.7     .16       0
    5014     .07       0  5019.6     .16       0
Bank Sta=5014,5019.6
XS Rating Curve= 0 ,0
Exp/Cntr=0.3,0.1

Type RM Length L Ch R = 1 ,2274    ,232,232,232
BEGIN DESCRIPTION:
Mill Creek Trib C2274.12
END DESCRIPTION:
XS GIS Cut Line= 3
      2752962.11      6822189.18      2752815.18      6822520.73
      2752626.48      6823030.47
#Sta/Elev= 30
  4643.9  430.46  4672.3  428.36  4695.6  428.13  4718.8  426.21  4744.3  425.48
  4817.4  423.17    4864  422.51  4921.5  420.76  4952.2  420.34    4985  420.71
  4991.3  417.35  4993.9  412.54  4994.4  412.04  4999.2  412.04  4999.7  412.54
  5009.4  412.99  5015.4  414.88  5020.7  420.38  5028.2  420.97  5198.8   421.6
  5209.4  420.76  5217.5  418.25  5222.8  419.24  5241.4  420.41  5262.8  420.43
    5273  421.15  5278.3  420.76  5326.7  422.32  5486.7  431.39  5550.1  432.92
#Mann= 4 ,-1 , 0
  4643.9    .063       0  4744.3     .16       0  4993.9     .07       0
  4999.7     .16       0
Bank Sta=4993.9,4999.7
XS Rating Curve= 0 ,0
Exp/Cntr=0.3,0.1

Type RM Length L Ch R = 1 ,2042    ,183,183,183
BEGIN DESCRIPTION:
Mill Creek Trib C2042.37
END DESCRIPTION:
XS GIS Cut Line= 3
       2752729.7      6822211.87      2752662.74      6822366.16
      2752286.54      6822986.75
#Sta/Elev= 30
  4835.5  433.15  4867.2  430.87    4883  430.41    4900  428.43  4935.4  426.13
  4953.4  423.19  4958.9  423.13  4965.4  412.91  4973.4  412.03  4973.8  411.53
  4978.7  411.53  4979.2  412.03  4982.3  417.14  4987.8  419.18  5003.6  420.27
  5011.1  419.78  5042.1  420.52  5084.5  419.61  5106.1  420.22  5114.6  419.87
  5121.6  418.21  5131.4  418.46  5137.1   419.1  5158.4  418.76  5173.1  419.45
  5433.4  419.39  5608.3  422.51  5680.6  425.46  5695.9  426.06  5729.4  428.75
#Mann= 8 ,-1 , 0
  4835.5     .16       0  4973.4     .07       0  4979.2     .16       0
  5084.5     .12       0  5131.4     .16       0  5433.4     .12       0
  5680.6     .16       0  5695.9     .12       0
Bank Sta=4973.4,4979.2
XS Rating Curve= 0 ,0
Exp/Cntr=0.3,0.1

Type RM Length L Ch R = 1 ,1859    ,244,244,244
BEGIN DESCRIPTION:
Mill Creek Trib C1858.89
END DESCRIPTION:
XS GIS Cut Line= 3
      2752579.18      6822173.68      2752505.71      6822294.82
      2752184.31      6822820.47
#Sta/Elev= 30
  4861.7  427.64  4870.4  427.31  4963.8  422.03  4993.1   418.6  4998.3  416.14
  5003.4  416.14  5008.6  414.89  5011.5  412.14    5012  411.64  5016.9  411.64
  5017.3  412.14  5029.9  412.75  5035.8  419.05  5045.3  419.43  5116.1  419.37
  5174.7  418.08  5209.9  418.95  5322.7  418.25  5359.3  418.29  5399.5  418.31
  5444.3  419.24  5457.6  418.91  5502.9  420.22  5531.1  422.51  5567.9  424.36
  5573.7  425.49  5583.3  425.63  5604.6  426.94  5610.5  427.92  5619.5  428.07
#Mann= 6 ,-1 , 0
  4861.7    .063       0  4870.4     .16       0  5011.5     .07       0
  5017.3     .16       0  5322.7     .12       0  5359.3     .16       0
Bank Sta=5011.5,5017.3
XS Rating Curve= 0 ,0
Exp/Cntr=0.3,0.1