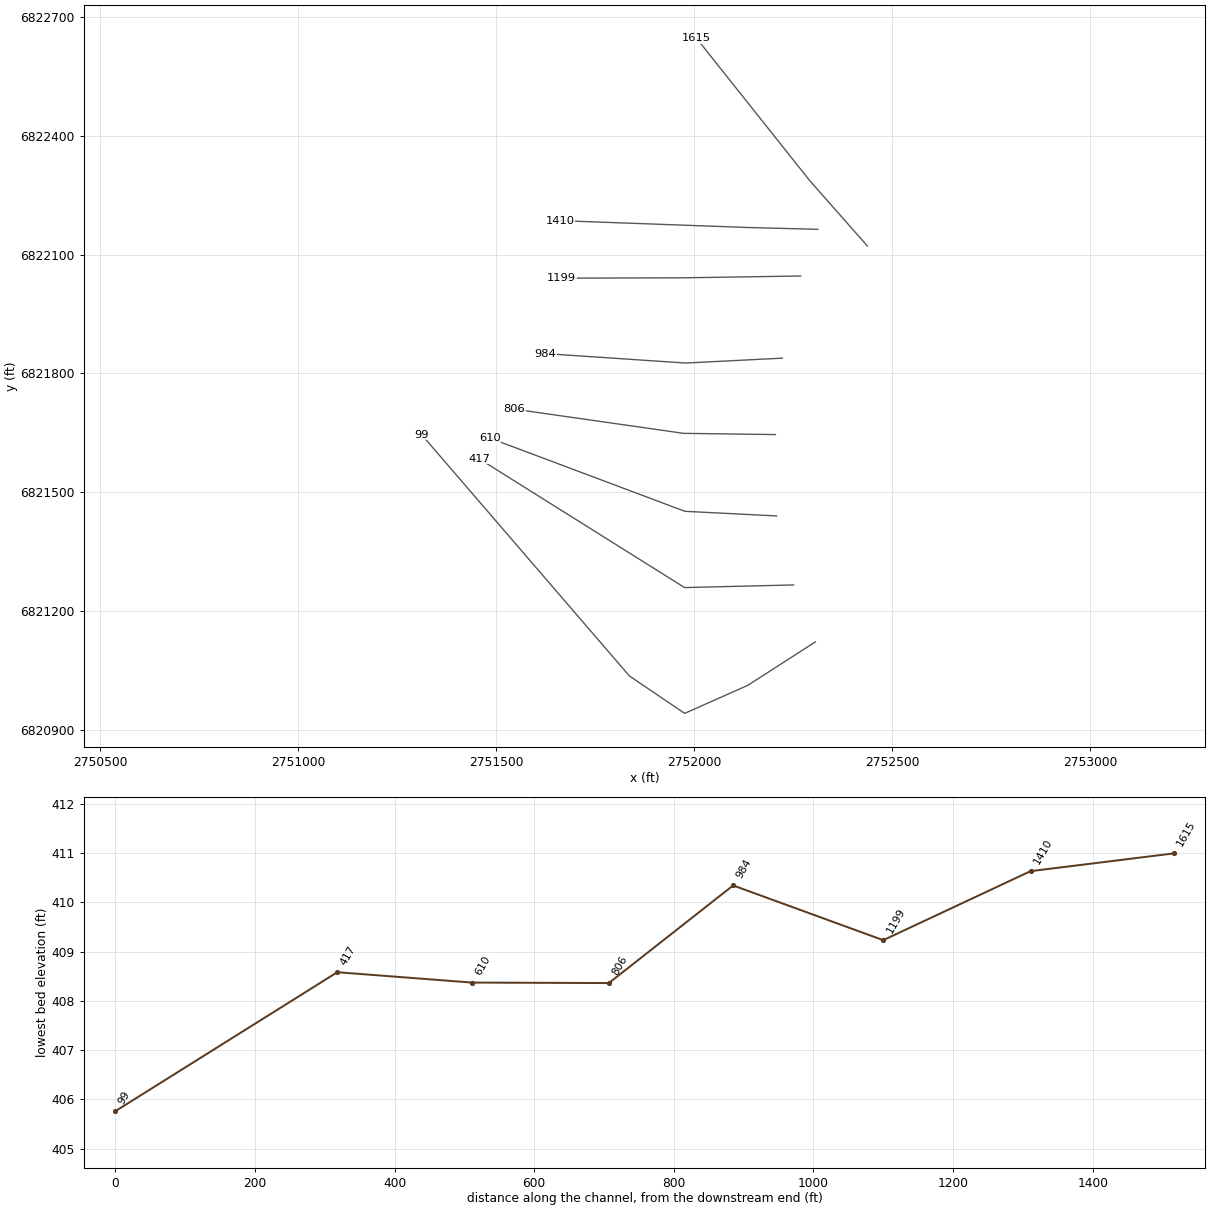
HEC-RAS study Mill Creek Trib C.prj: Mill Creek Trib C Base Level Engineering

--- Mill Creek Trib C.g01 (geometry) --- (continued)

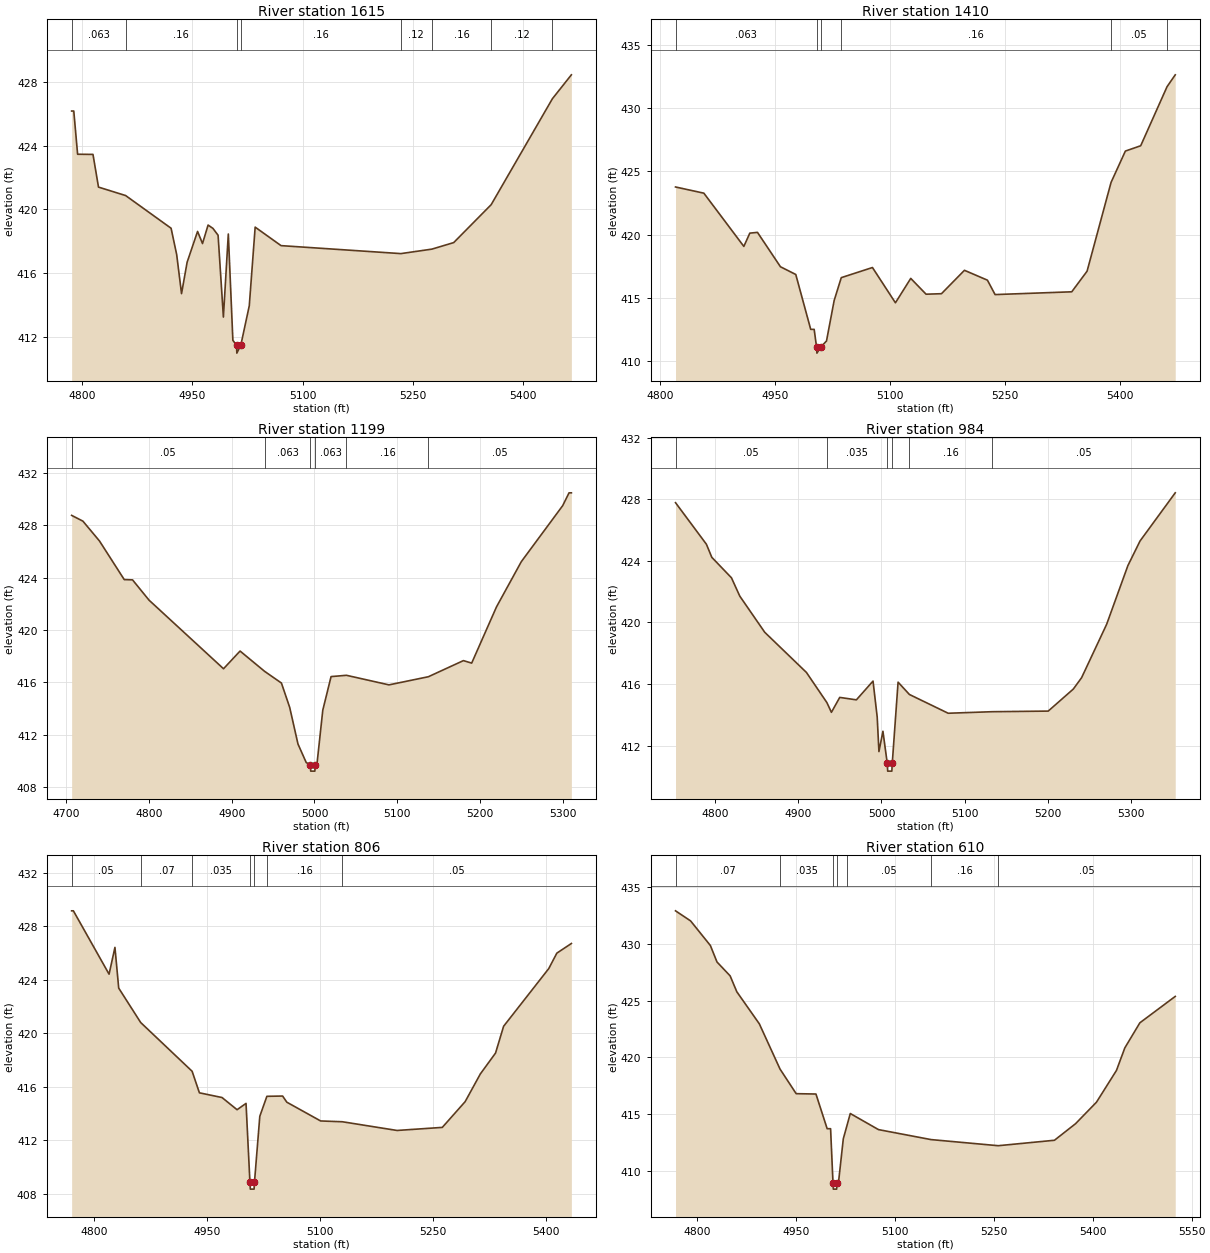
Type RM Length L Ch R = 1 ,1615    ,205,205,205
BEGIN DESCRIPTION:
Mill Creek Trib C1615.26
END DESCRIPTION:
XS GIS Cut Line= 3
       2752437.9       6822121.7      2752292.78      6822286.21
      2752006.41      6822646.24
#Sta/Elev= 30
    4786  426.17  4788.9  426.17  4794.1  423.46    4815  423.45  4822.5   421.4
  4859.4  420.87  4921.2  418.82  4928.8  417.17  4935.4  414.72    4943  416.69
  4957.2  418.62  4963.9  417.86  4971.5  419.02  4978.1  418.81  4985.1  418.38
  4992.3  413.25    4999  418.46  5005.2  411.79  5010.2  411.49  5010.6  410.99
    5016  411.49  5027.5  413.96  5035.5  418.89  5070.7  417.73  5233.6  417.23
  5275.7  417.51  5305.4  417.92  5356.4   420.3  5439.6  426.94  5465.4  428.44
#Mann= 8 ,-1 , 0
    4786    .063       0  4859.4     .16       0  5010.2     .07       0
    5016     .16       0  5233.6     .12       0  5275.7     .16       0
  5356.4     .12       0  5439.6     .05       0
Bank Sta=5010.2,5016
XS Rating Curve= 0 ,0
Exp/Cntr=0.3,0.1

Type RM Length L Ch R = 1 ,1410    ,211,211,211
BEGIN DESCRIPTION:
Mill Creek Trib C1409.54
END DESCRIPTION:
XS GIS Cut Line= 3
      2752312.98      6822163.74      2752132.09      6822168.46
      2751660.96      6822185.66
#Sta/Elev= 30
    4820  423.77    4857  423.28  4909.2  419.07    4917  420.12    4927  420.18
    4957  417.46    4977  416.85  4996.5  412.51    5001  412.51  5004.1  411.13
  5004.6  410.63  5009.9  411.13  5017.1  411.59  5027.1  414.79  5036.4   416.6
  5077.1   417.4  5107.1  414.61  5127.1  416.54  5147.1  415.29  5167.2  415.33
  5197.2  417.18  5227.2   416.4  5237.2  415.26  5337.3  415.48  5357.3  417.11
  5388.6  424.13  5407.3  426.61  5427.3  427.03  5461.7   431.7  5472.4  432.64
#Mann= 6 ,-1 , 0
    4820    .063       0  5004.1    .063       0  5009.9    .063       0
  5036.4     .16       0  5388.6     .05       0  5461.7    .063       0
Bank Sta=5004.1,5009.9
XS Rating Curve= 0 ,0
Exp/Cntr=0.3,0.1

Type RM Length L Ch R = 1 ,1199    ,215,215,215
BEGIN DESCRIPTION:
Mill Creek Trib C1199.17
END DESCRIPTION:
XS GIS Cut Line= 3
      2752269.58       6822045.8       2751975.3      6822041.28
      2751665.51       6822040.3
#Sta/Elev= 30
  4706.5  428.74  4720.1   428.3  4740.1  426.79  4770.1  423.84  4780.1  423.82
  4800.1  422.27  4890.1  417.04  4910.1  418.39  4939.8  416.84  4960.1  415.95
  4970.1  414.09  4980.1   411.3  4990.1  409.88    4995  409.73  4995.5  409.23
  5000.5  409.23    5001  409.73    5003  409.73  5010.1  413.88  5020.1  416.44
  5038.7  416.54  5090.1  415.81  5137.7  416.43  5180.1  417.66  5190.1  417.47
  5220.1  421.76  5250.1  425.21  5300.1  429.48  5307.8  430.46  5310.6  430.46
#Mann= 6 ,-1 , 0
  4706.5     .05       0  4939.8    .063       0    4995    .063       0
    5001    .063       0  5038.7     .16       0  5137.7     .05       0
Bank Sta=4995,5001
XS Rating Curve= 0 ,0
Exp/Cntr=0.3,0.1

Type RM Length L Ch R = 1 ,984     ,178,178,178
BEGIN DESCRIPTION:
Mill Creek Trib C983.94
END DESCRIPTION:
XS GIS Cut Line= 3
      2752223.07      6821838.28      2751978.99      6821825.89
      2751623.78      6821849.79
#Sta/Elev= 30
  4752.6  427.78  4789.7  425.08  4796.2  424.23  4819.8   422.9  4829.8  421.71
  4859.8  419.36  4909.9  416.75  4934.5  414.79  4939.9  414.16  4949.9  415.13
  4969.9  414.97  4989.9  416.19  4994.9  413.86    4997  411.61  5001.8  412.93
    5007  410.84  5007.5  410.34  5012.5  410.34    5013  410.84    5020  416.12
  5033.6  415.32  5080.2   414.1    5133   414.2  5200.4  414.24  5230.5  415.67
  5240.5  416.41  5270.6  419.88  5296.1  423.69  5310.7  425.29    5353  428.42
#Mann= 6 ,-1 , 0
  4752.6     .05       0  4934.5    .035       0    5007    .035       0
    5013    .035       0  5033.6     .16       0    5133     .05       0
Bank Sta=5007,5013
XS Rating Curve= 0 ,0
Exp/Cntr=0.3,0.1

Type RM Length L Ch R = 1 ,806     ,196,196,196
BEGIN DESCRIPTION:
Mill Creek Trib C806.09
END DESCRIPTION:
XS GIS Cut Line= 3
      2752205.67       6821645.2      2751974.09      6821648.26
      2751546.34      6821709.37
#Sta/Elev= 30
  4770.3  429.14  4772.6  429.14    4820  424.41  4827.8  426.41  4832.8  423.37
    4862   420.8  4930.3  417.16    4940  415.55    4970   415.2    4990  414.29
  5001.9  414.76  5007.1  408.86  5007.6  408.36  5012.6  408.36  5013.1  408.86
  5020.2   413.8  5029.6  415.29  5050.5  415.31  5056.1  414.85    5101  413.45
  5129.9  413.39  5202.5  412.74  5262.6  412.97  5292.9  414.89  5313.1  416.96
  5333.3  418.52    5344  420.52    5404  424.83  5414.7  425.98    5434   426.7
#Mann= 7 ,-1 , 0
  4770.3     .05       0    4862     .07       0  4930.3    .035       0
  5007.1    .035       0  5013.1    .035       0  5029.6     .16       0
  5129.9     .05       0
Bank Sta=5007.1,5013.1
XS Rating Curve= 0 ,0
Exp/Cntr=0.3,0.1

Type RM Length L Ch R = 1 ,610     ,193,193,193
BEGIN DESCRIPTION:
Mill Creek Trib C609.57
END DESCRIPTION:
XS GIS Cut Line= 3
      2752208.83      6821439.62      2751977.01      6821451.34
      2751484.37       6821636.2
#Sta/Elev= 30
  4766.8  432.92  4789.7  432.03  4819.7  429.86  4829.7  428.41  4849.7  427.18
  4859.8  425.78    4894  422.95  4925.4  418.96  4949.9  416.79  4979.9  416.76
  4996.9   413.7  5002.1   413.7  5005.8  408.87  5006.3  408.37  5011.3  408.37
  5011.8  408.87  5014.1  408.95  5021.4  412.81  5026.5  413.88    5032  415.04
  5074.8  413.62  5154.5  412.74  5256.5   412.2  5341.8  412.68  5373.8  414.14
  5405.6  416.04  5435.9  418.84  5448.6  420.83  5471.4  423.04  5525.1  425.37
#Mann= 7 ,-1 , 0
  4766.8     .07       0  4925.4    .035       0  5005.8    .035       0
  5011.8    .035       0  5026.5     .05       0  5154.5     .16       0
  5256.5     .05       0
Bank Sta=5005.8,5011.8
XS Rating Curve= 0 ,0
Exp/Cntr=0.3,0.1

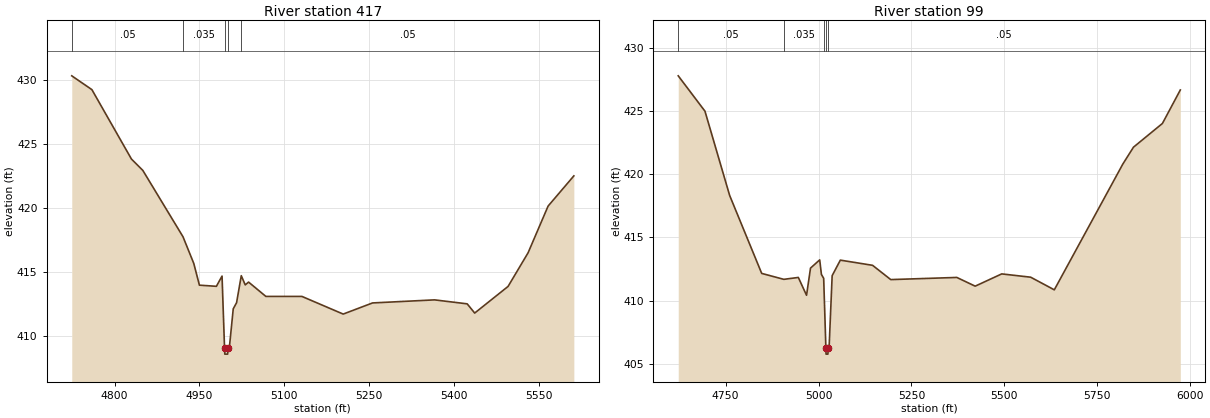
Type RM Length L Ch R = 1 ,417     ,318,318,318
BEGIN DESCRIPTION:
Mill Creek Trib C416.6
END DESCRIPTION:
XS GIS Cut Line= 3
       2752251.6      6821265.31      2751976.16      6821258.66
      2751457.48      6821583.83
#Sta/Elev= 30
  4724.3  430.33  4759.9  429.25  4829.9  423.82  4849.9  422.94    4921  417.75
    4940  415.67    4950  413.97    4980  413.88    4990  414.68  4994.4  409.08
  4994.9  408.58  4999.9  408.58  5000.4  409.08  5002.9  409.08  5009.8  412.12
  5015.7   412.6    5024  414.71    5031  413.99  5036.9  414.21  5067.5  413.09
  5131.2  413.09  5204.2  411.71  5256.1  412.58  5365.7  412.82  5423.4  412.51
  5436.7  411.79  5495.7  413.87  5531.1   416.5  5566.5  420.15    5612  422.51
#Mann= 5 ,-1 , 0
  4724.3     .05       0    4921    .035       0  4994.4    .035       0
  5000.4    .035       0    5024     .05       0
Bank Sta=4994.4,5000.4
XS Rating Curve= 0 ,0
Exp/Cntr=0.3,0.1

Type RM Length L Ch R = 1 ,99      ,0,0,0
BEGIN DESCRIPTION:
Mill Creek Trib C98.695
END DESCRIPTION:
XS GIS Cut Line= 5
      2752306.45      6821121.31      2752135.64      6821011.54
      2751976.36      6820940.85      2751836.65      6821035.49
      2751311.82      6821645.03
#Sta/Elev= 30
  4622.7  427.79  4694.6  424.99    4761  418.32  4847.2  412.15  4906.7  411.68
  4945.7  411.83  4967.8  410.42  4978.5  412.57  5003.2  413.22  5007.8  412.07
  5013.9  411.76  5015.7  410.08  5019.8  406.26  5020.3  405.76  5025.3  405.76
  5025.8  406.26  5028.8   406.5  5036.7  411.97  5058.7   413.2  5145.4  412.79
  5194.3  411.66    5372  411.83  5421.4  411.14  5492.7  412.11  5570.6  411.85
  5634.2  410.85  5818.6  420.81  5847.1  422.14    5925  424.02  5973.1  426.67
#Mann= 5 ,-1 , 0
  4622.7     .05       0  4906.7    .035       0  5015.7     .05       0
  5019.8    .035       0  5025.8     .05       0
Bank Sta=5019.8,5025.8
XS Rating Curve= 0 ,0
Exp/Cntr=0.3,0.1

Chan Stop Cuts=-1
Use User Specified Reach Order=0
Composite Channel Slope=5