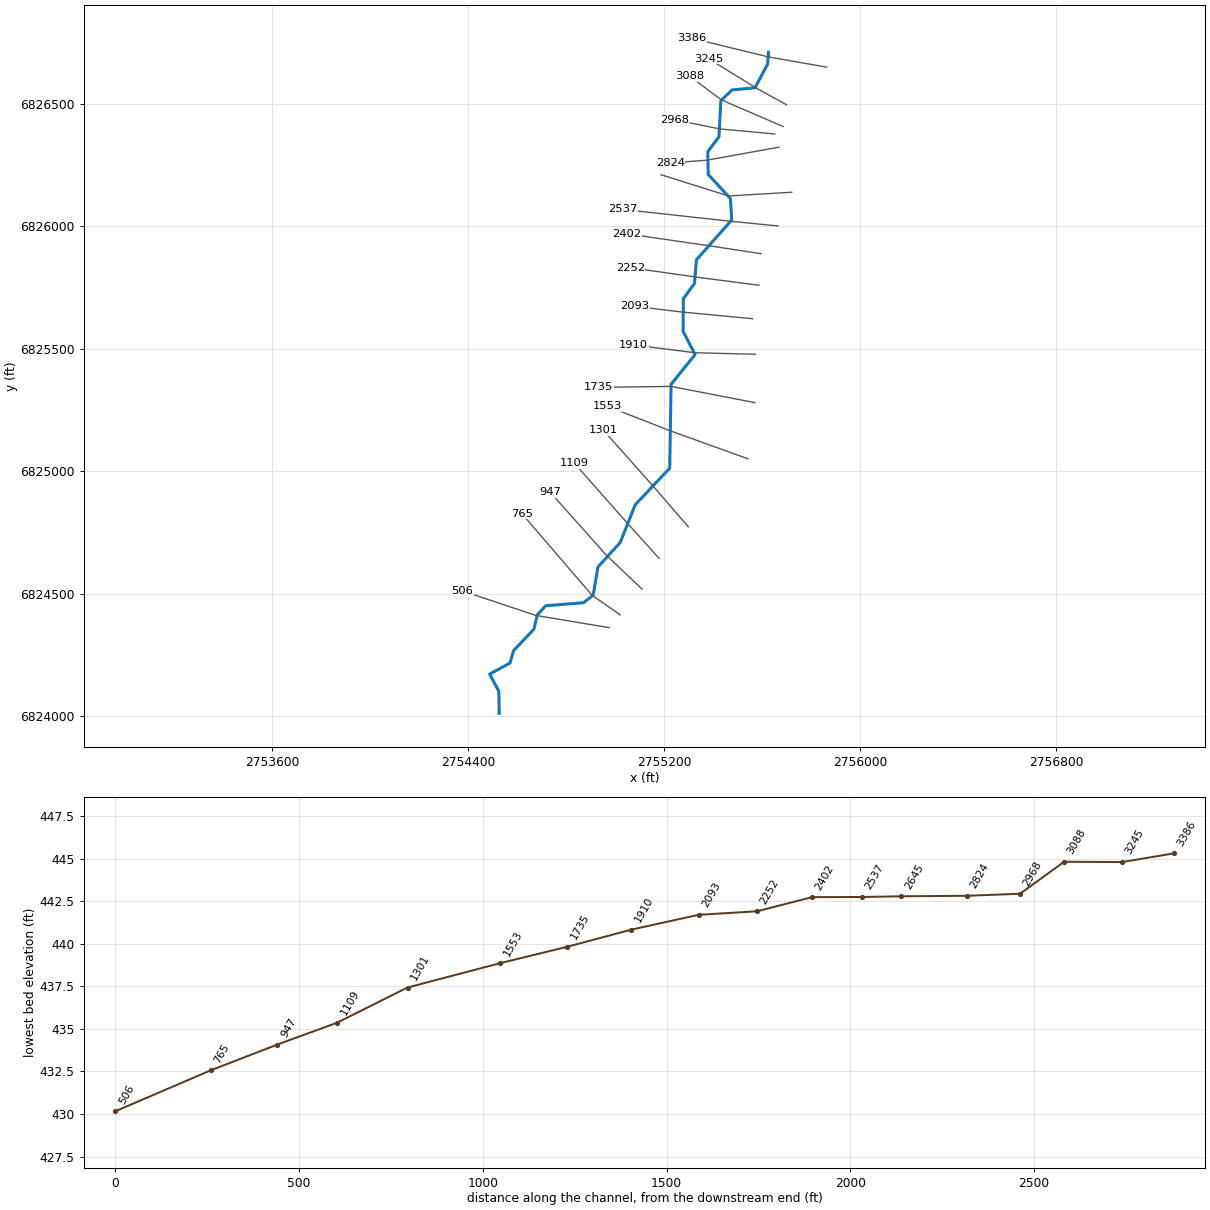
--- Mill Creek Trib C1.prj (project) ---

Proj Title=Mill Creek Trib C1 Base Level Engineering
Current Plan=p01
Default Exp/Contr=0.3,0.1
English Units
Geom File=g01
Flow File=f01
Plan File=p01
BEGIN DESCRIPTION:
Mill Creek Trib C1
END DESCRIPTION:

--- Mill Creek Trib C1.p01 (plan) ---

Plan Title=Multiple Run
Short Identifier=Multiple
Geom File=g01
Flow File=f01
Subcritical Flow
K Sum by GR= 0
Std Step Tol= 0.01
Critical Tol= 0.01
Num of Std Step Trials= 20
Max Error Tol= 0.3
Flow Tol Ratio= 0.001
Split Flow NTrial= 30
Split Flow Tol= 0.02
Split Flow Ratio= 0.02
Log Output Level= 0
Friction Slope Method= 1
Unsteady Friction Slope Method= 2
Unsteady Bridges Friction Slope Method= 1
Parabolic Critical Depth
Global Vel Dist=  1 , 1 , 1
Global Log Level= 0
CheckData=True
Encroach Param= -1, 0, 0, 0
BEGIN DESCRIPTION:
Multiple Run
END DESCRIPTION:

--- Mill Creek Trib C1.f01 (steady flow) ---

Flow Title=Multiple
Number of Profiles=7
Profile Names=10-year,25-year,50-year,1pct_min,100-year,1pct_plu,500-year
River Rch & RM= Mill Creek Trib ,Reach-1,3386
     422     558     666     396     790    1577    1114
Boundary for River Rch & Prof#=Mill Creek Trib ,Reach-1,1
Up Type=0
Dn Type=3
Dn Slope=0.005
Boundary for River Rch & Prof#=Mill Creek Trib ,Reach-1,2
Up Type=0
Dn Type=3
Dn Slope=0.005
Boundary for River Rch & Prof#=Mill Creek Trib ,Reach-1,3
Up Type=0
Dn Type=3
Dn Slope=0.005
Boundary for River Rch & Prof#=Mill Creek Trib ,Reach-1,4
Up Type=0
Dn Type=3
Dn Slope=0.005
Boundary for River Rch & Prof#=Mill Creek Trib ,Reach-1,5
Up Type=0
Dn Type=3
Dn Slope=0.005
Boundary for River Rch & Prof#=Mill Creek Trib ,Reach-1,6
Up Type=0
Dn Type=3
Dn Slope=0.005
Boundary for River Rch & Prof#=Mill Creek Trib ,Reach-1,7
Up Type=0
Dn Type=3
Dn Slope=0.005

--- Mill Creek Trib C1.g01 (geometry) ---

Geom Title=Existing Conditions

River Reach=Mill Creek Trib ,Reach-1
Reach XY= 30
      2755626.00      6826711.00      2755622.42      6826662.44
      2755570.58      6826566.22      2755477.32      6826557.46
      2755431.35      6826513.73      2755423.61      6826366.53
      2755378.16      6826305.02      2755379.47      6826212.50
      2755470.59      6826113.42      2755475.76      6826026.22
      2755331.52      6825863.43      2755323.64      6825766.98
      2755278.25      6825705.06      2755277.23      6825571.50
      2755326.04      6825476.34      2755228.07      6825355.14
      2755222.46      6825012.46      2755081.83      6824863.30
      2755020.15      6824708.71      2754929.63      6824609.50
      2754909.73      6824493.78      2754870.35      6824462.98
      2754715.88      6824450.65      2754681.74      6824413.58
      2754667.81      6824354.98      2754584.30      6824266.74
      2754570.32      6824216.62      2754487.00      6824171.36
      2754524.59      6824101.51      2754526.00      6824011.00

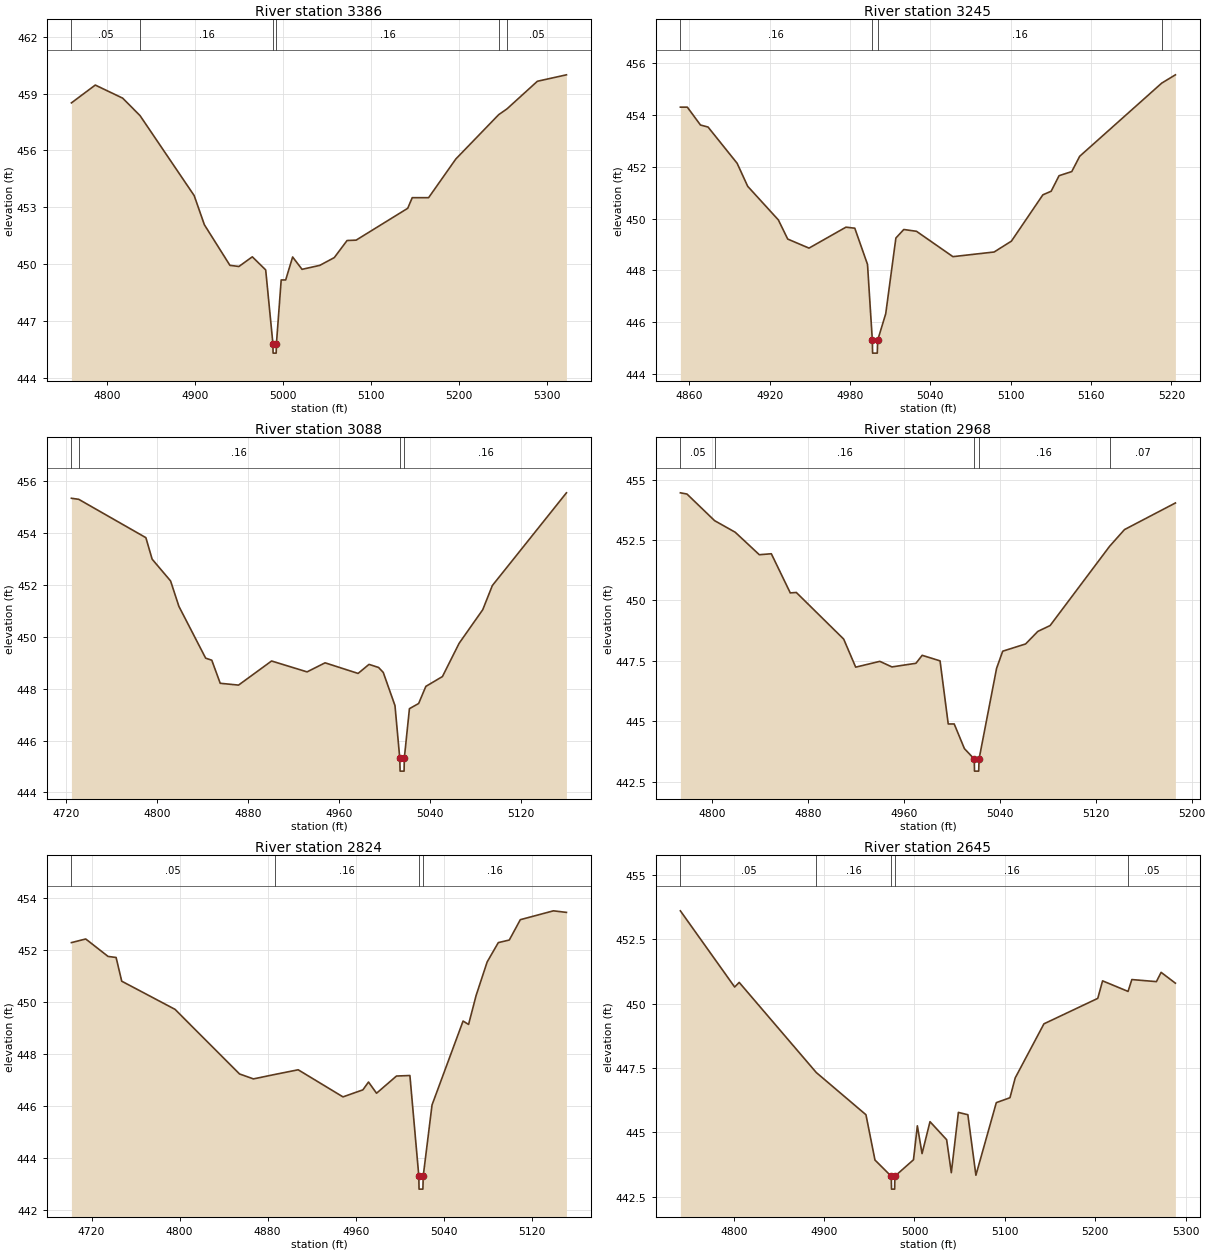
Type RM Length L Ch R = 1,3386,141,141,141
BEGIN DESCRIPTION:
Mill Creek Trib C13386.294
END DESCRIPTION:
XS GIS Cut Line= 3
      2755863.31      6826650.56      2755626.42      6826692.07
      2755313.96      6826768.18
#Sta/Elev= 30
  4759.5  458.51  4786.6  459.45  4817.7  458.76  4837.4  457.84  4898.9  453.62
  4910.5  452.08  4939.5  449.94  4949.7  449.88  4964.9  450.39  4980.1  449.70
  4988.3  445.81  4988.5  445.31  4992.0  445.31  4992.3  445.81  4997.7  449.17
  5002.8  449.17  5010.7  450.38  5021.4  449.73  5041.6  449.94  5058.0  450.35
  5072.5  451.25  5082.8  451.27  5141.4  452.95  5146.5  453.51  5165.1  453.51
  5196.0  455.55  5244.7  457.89  5254.0  458.19  5288.6  459.65  5321.6  459.99
#Mann=6,-1,0
  4759.5    0.05       0  4837.4    0.16       0  4988.3    0.07       0
  4992.3    0.16       0  5244.7    0.07       0  5254.0    0.05       0
Bank Sta=4988.3,4992.3
Exp/Cntr=0.3,0.1

Type RM Length L Ch R = 1,3245,157,157,157
BEGIN DESCRIPTION:
Mill Creek Trib C13245.26
END DESCRIPTION:
XS GIS Cut Line= 3
      2755700.04      6826496.52      2755571.18      6826567.85
      2755381.68      6826684.49
#Sta/Elev= 30
  4853.2  454.31  4858.4  454.31  4868.2  453.62  4873.9  453.54  4895.6  452.14
  4903.5  451.25  4926.4  449.95  4933.4  449.21  4949.3  448.86  4976.9  449.67
  4983.5  449.63  4993.0  448.23  4996.6  445.30  4996.8  444.80  5000.3  444.80
  5000.6  445.30  5006.6  446.32  5014.2  449.25  5020.1  449.58  5029.6  449.51
  5056.8  448.53  5087.6  448.71  5100.5  449.13  5124.0  450.92  5130.2  451.06
  5136.1  451.66  5145.6  451.82  5151.5  452.41  5212.8  455.24  5223.0  455.56
#Mann=4,-1,0
  4853.2    0.16       0  4996.6    0.07       0  5000.6    0.16       0
  5212.8    0.07       0
Bank Sta=4996.6,5000.6
Exp/Cntr=0.3,0.1

Type RM Length L Ch R = 1,3088,120,120,120
BEGIN DESCRIPTION:
Mill Creek Trib C13088.49
END DESCRIPTION:
XS GIS Cut Line= 3
      2755686.00      6826407.87      2755433.53      6826516.89
      2755305.51      6826612.52
#Sta/Elev= 30
  4724.8  455.35  4731.2  455.31  4790.2  453.83  4795.7  453.00  4811.9  452.16
  4819.2  451.18  4842.7  449.18  4848.1  449.10  4855.5  448.21  4871.6  448.14
  4900.6  449.07  4931.8  448.65  4947.6  449.00  4976.6  448.59  4986.2  448.94
  4994.6  448.82  4998.7  448.63  5009.0  447.35  5013.2  445.32  5013.5  444.82
  5017.0  444.82  5017.2  445.32  5021.7  447.23  5029.8  447.43  5036.1  448.09
  5050.7  448.47  5065.3  449.75  5086.1  451.05  5094.5  451.98  5159.6  455.56
#Mann=4,-1,0
  4724.8    0.05       0  4731.2    0.16       0  5013.2    0.07       0
  5017.2    0.16       0
Bank Sta=5013.2,5017.2
Exp/Cntr=0.3,0.1

Type RM Length L Ch R = 1,2968,144,144,144
BEGIN DESCRIPTION:
Mill Creek Trib C12968.42
END DESCRIPTION:
XS GIS Cut Line= 3
      2755651.52      6826377.57      2755427.59      6826398.11
      2755243.66      6826435.22
#Sta/Elev= 30
  4773.9  454.45  4779.4  454.40  4802.4  453.30  4819.6  452.82  4839.7  451.89
  4849.7  451.93  4865.5  450.31  4870.5  450.33  4910.0  448.40  4920.0  447.24
  4940.1  447.48  4950.2  447.25  4970.2  447.40  4975.4  447.73  4990.3  447.50
  4997.1  444.89  5002.1  444.89  5010.6  443.87  5018.8  443.44  5019.0  442.94
  5022.5  442.94  5022.8  443.44  5037.4  447.19  5042.5  447.90  5061.6  448.20
  5071.8  448.72  5082.0  448.96  5131.6  452.24  5144.0  452.93  5186.4  454.03
#Mann=5,-1,0
  4773.9    0.05       0  4802.4    0.16       0  5018.8    0.07       0
  5022.8    0.16       0  5131.6    0.07       0
Bank Sta=5018.8,5022.8
Exp/Cntr=0.3,0.1

Type RM Length L Ch R = 1,2824,179,179,179
BEGIN DESCRIPTION:
Mill Creek Trib C12824.46
END DESCRIPTION:
XS GIS Cut Line= 3
      2755668.75      6826323.61      2755375.35      6826270.60
      2755224.24      6826259.14
#Sta/Elev= 30
  4701.7  452.28  4714.7  452.42  4735.0  451.75  4742.3  451.71  4747.4  450.80
  4795.8  449.72  4854.4  447.24  4867.1  447.05  4886.4  447.22  4907.7  447.40
  4948.4  446.36  4966.5  446.63  4971.6  446.93  4978.9  446.50  4997.0  447.16
  5009.2  447.18  5017.3  443.32  5017.5  442.82  5021.0  442.82  5021.3  443.32
  5029.3  446.05  5057.5  449.27  5062.5  449.14  5069.4  450.26  5079.4  451.54
  5089.5  452.28  5099.5  452.38  5109.5  453.16  5139.6  453.50  5151.4  453.44
#Mann=4,-1,0
  4701.7    0.05       0  4886.4    0.16       0  5017.3    0.07       0
  5021.3    0.16       0
Bank Sta=5017.3,5021.3
Exp/Cntr=0.3,0.1

Type RM Length L Ch R = 1,2645,108,108,108
BEGIN DESCRIPTION:
Mill Creek Trib C12644.66
END DESCRIPTION:
XS GIS Cut Line= 3
      2755721.00      6826139.58      2755463.41      6826124.23
      2755186.86      6826211.03
#Sta/Elev= 30
  4740.9  453.60  4801.0  450.64  4806.0  450.82  4891.3  447.32  4946.3  445.68
  4956.3  443.92  4974.3  443.29  4974.6  442.79  4978.1  442.79  4978.3  443.29
  4998.9  443.93  5003.2  445.25  5008.4  444.17  5017.2  445.41  5035.6  444.71
  5040.8  443.43  5048.6  445.77  5059.1  445.68  5068.0  443.33  5090.6  446.15
  5105.7  446.34  5111.5  447.11  5143.3  449.21  5202.9  450.20  5208.2  450.88
  5236.4  450.47  5240.6  450.93  5267.8  450.85  5273.0  451.21  5288.8  450.79
#Mann=5,-1,0
  4740.9    0.05       0  4891.3    0.16       0  4974.3    0.07       0
  4978.3    0.16       0  5236.4    0.05       0
Bank Sta=4974.3,4978.3
Exp/Cntr=0.3,0.1

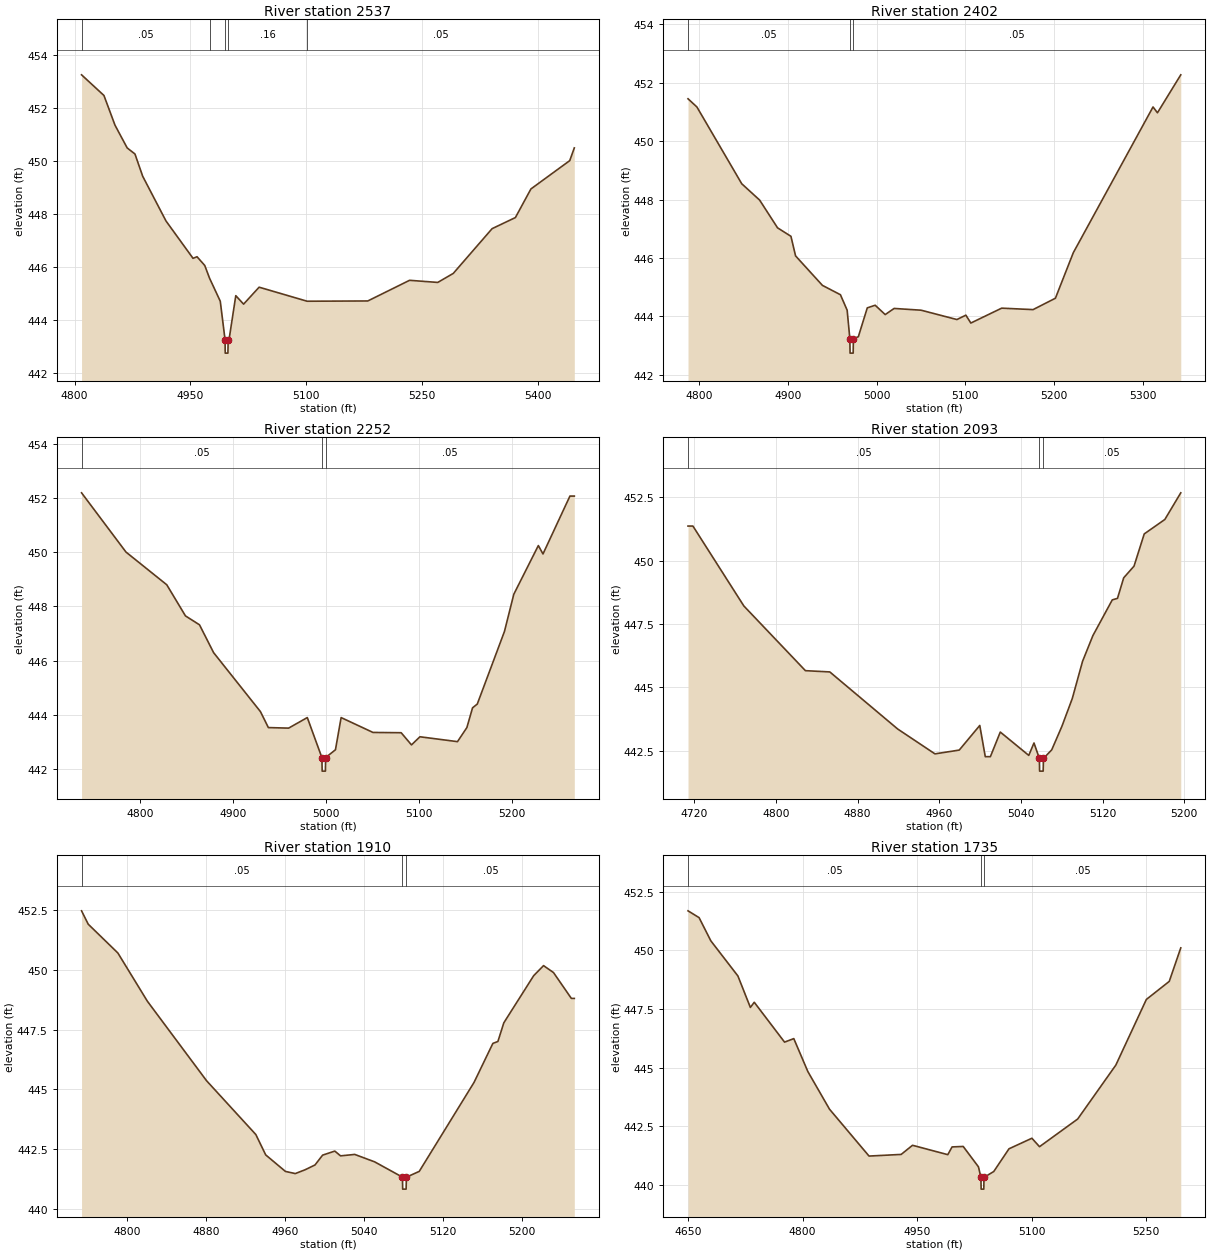
Type RM Length L Ch R = 1,2537,135,135,135
BEGIN DESCRIPTION:
Mill Creek Trib C12536.98
END DESCRIPTION:
XS GIS Cut Line= 3
      2755664.85      6826001.83      2755474.75      6826020.60
      2755030.15      6826069.45
#Sta/Elev= 30
  4809.1  453.26  4838.1  452.48  4852.4  451.36  4868.2  450.50  4878.3  450.27
  4888.3  449.43  4918.5  447.74  4953.5  446.33  4958.7  446.39  4968.7  446.06
  4974.9  445.58  4988.8  444.71  4995.0  443.25  4995.2  442.75  4998.7  442.75
  4999.0  443.25  5000.1  443.25  5008.9  444.92  5019.0  444.60  5039.1  445.24
  5101.3  444.71  5179.9  444.72  5234.0  445.50  5270.5  445.42  5290.6  445.76
  5340.9  447.45  5371.1  447.87  5391.2  448.95  5441.5  450.02  5447.4  450.50
#Mann=5,-1,0
  4809.1    0.05       0  4974.9    0.16       0  4995.0    0.07       0
  4999.0    0.16       0  5101.3    0.05       0
Bank Sta=4995,4999
Exp/Cntr=0.3,0.1

Type RM Length L Ch R = 1,2402,150,150,150
BEGIN DESCRIPTION:
Mill Creek Trib C12401.6
END DESCRIPTION:
XS GIS Cut Line= 3
      2755595.88      6825888.46      2755383.46      6825920.97
      2755046.09      6825969.93
#Sta/Elev= 30
  4787.1  451.45  4797.1  451.17  4847.7  448.54  4867.9  447.98  4888.1  447.03
  4903.2  446.74  4908.4  446.07  4938.7  445.06  4959.0  444.74  4966.6  444.21
  4969.6  443.24  4969.9  442.74  4973.4  442.74  4973.6  443.24  4979.2  443.30
  4989.3  444.29  4998.2  444.38  5009.5  444.06  5019.6  444.27  5050.0  444.21
  5090.4  443.89  5100.5  444.04  5106.1  443.77  5140.9  444.28  5176.3  444.23
  5201.5  444.62  5221.7  446.18  5311.6  451.17  5316.6  450.97  5342.9  452.27
#Mann=3,-1,0
  4787.1    0.05       0  4969.6    0.05       0  4973.6    0.05       0
Bank Sta=4969.6,4973.6
Exp/Cntr=0.3,0.1

Type RM Length L Ch R = 1,2252,159,159,159
BEGIN DESCRIPTION:
Mill Creek Trib C12252.09
END DESCRIPTION:
XS GIS Cut Line= 3
      2755586.90      6825759.65      2755325.93      6825793.58
      2755061.58      6825831.33
#Sta/Elev= 30
  4737.0  452.20  4784.8  450.01  4828.7  448.80  4848.8  447.65  4863.9  447.32
  4879.1  446.29  4929.5  444.11  4938.0  443.52  4959.8  443.50  4979.9  443.89
  4995.6  442.41  4995.9  441.91  4999.4  441.91  4999.6  442.41  5010.2  442.70
  5016.3  443.89  5050.6  443.34  5080.9  443.33  5092.0  442.88  5101.1  443.18
  5141.5  443.00  5151.6  443.52  5157.7  444.25  5162.8  444.39  5192.0  447.07
  5202.1  448.45  5228.5  450.25  5233.5  449.94  5262.5  452.08  5267.2  452.08
#Mann=3,-1,0
  4737.0    0.05       0  4995.6    0.05       0  4999.6    0.05       0
Bank Sta=4995.6,4999.6
Exp/Cntr=0.3,0.1

Type RM Length L Ch R = 1,2093,183,183,183
BEGIN DESCRIPTION:
Mill Creek Trib C12092.52
END DESCRIPTION:
XS GIS Cut Line= 3
      2755560.49      6825622.97      2755270.24      6825650.57
      2755080.49      6825673.61
#Sta/Elev= 30
  4713.8  451.36  4718.6  451.36  4768.5  448.21  4828.8  445.66  4852.7  445.61
  4919.2  443.36  4955.7  442.38  4979.5  442.53  4999.6  443.50  5005.0  442.27
  5010.0  442.27  5019.7  443.24  5047.6  442.32  5052.7  442.81  5058.0  442.20
  5058.2  441.70  5061.7  441.70  5062.0  442.20  5070.1  442.54  5080.1  443.47
  5090.2  444.56  5100.3  446.03  5110.4  447.04  5129.4  448.45  5134.5  448.51
  5140.6  449.32  5150.7  449.78  5160.7  451.05  5180.9  451.62  5196.5  452.67
#Mann=3,-1,0
  4713.8    0.05       0  5058.0    0.05       0  5062.0    0.05       0
Bank Sta=5058,5062
Exp/Cntr=0.3,0.1

Type RM Length L Ch R = 1,1910,175,175,175
BEGIN DESCRIPTION:
Mill Creek Trib C11910.01
END DESCRIPTION:
XS GIS Cut Line= 3
      2755572.78      6825477.80      2755325.72      6825483.93
      2755075.09      6825515.95
#Sta/Elev= 30
  4753.6  452.46  4760.4  451.90  4790.4  450.70  4820.4  448.68  4880.4  445.36
  4930.4  443.11  4940.4  442.26  4960.4  441.57  4970.4  441.48  4980.4  441.64
  4990.4  441.84  4998.1  442.25  5010.5  442.42  5016.3  442.22  5030.7  442.28
  5050.9  441.97  5079.1  441.33  5079.3  440.83  5082.8  440.83  5083.1  441.33
  5096.1  441.57  5151.7  445.29  5170.8  446.92  5175.9  447.00  5181.9  447.78
  5212.2  449.75  5222.2  450.17  5232.3  449.88  5250.4  448.80  5253.4  448.80
#Mann=3,-1,0
  4753.6    0.05       0  5079.1    0.05       0  5083.1    0.05       0
Bank Sta=5079.1,5083.1
Exp/Cntr=0.3,0.1

Type RM Length L Ch R = 1,1735,182,182,182
BEGIN DESCRIPTION:
Mill Creek Trib C11735.12
END DESCRIPTION:
XS GIS Cut Line= 3
      2755570.25      6825280.31      2755227.64      6825346.47
      2754930.90      6825342.73
#Sta/Elev= 30
  4649.9  451.69  4664.4  451.40  4679.8  450.41  4715.3  448.91  4731.6  447.57
  4736.7  447.79  4776.4  446.09  4788.5  446.24  4807.0  444.83  4835.3  443.23
  4887.1  441.23  4929.2  441.30  4944.1  441.69  4990.3  441.29  4995.9  441.62
  5010.5  441.64  5030.5  440.77  5033.7  440.32  5034.0  439.82  5037.5  439.82
  5037.7  440.32  5050.5  440.57  5070.5  441.54  5100.5  441.99  5110.5  441.63
  5160.5  442.81  5210.5  445.11  5250.5  447.91  5280.5  448.68  5295.6  450.11
#Mann=3,-1,0
  4649.9    0.05       0  5033.7    0.05       0  5037.7    0.05       0
Bank Sta=5033.7,5037.7
Exp/Cntr=0.3,0.1

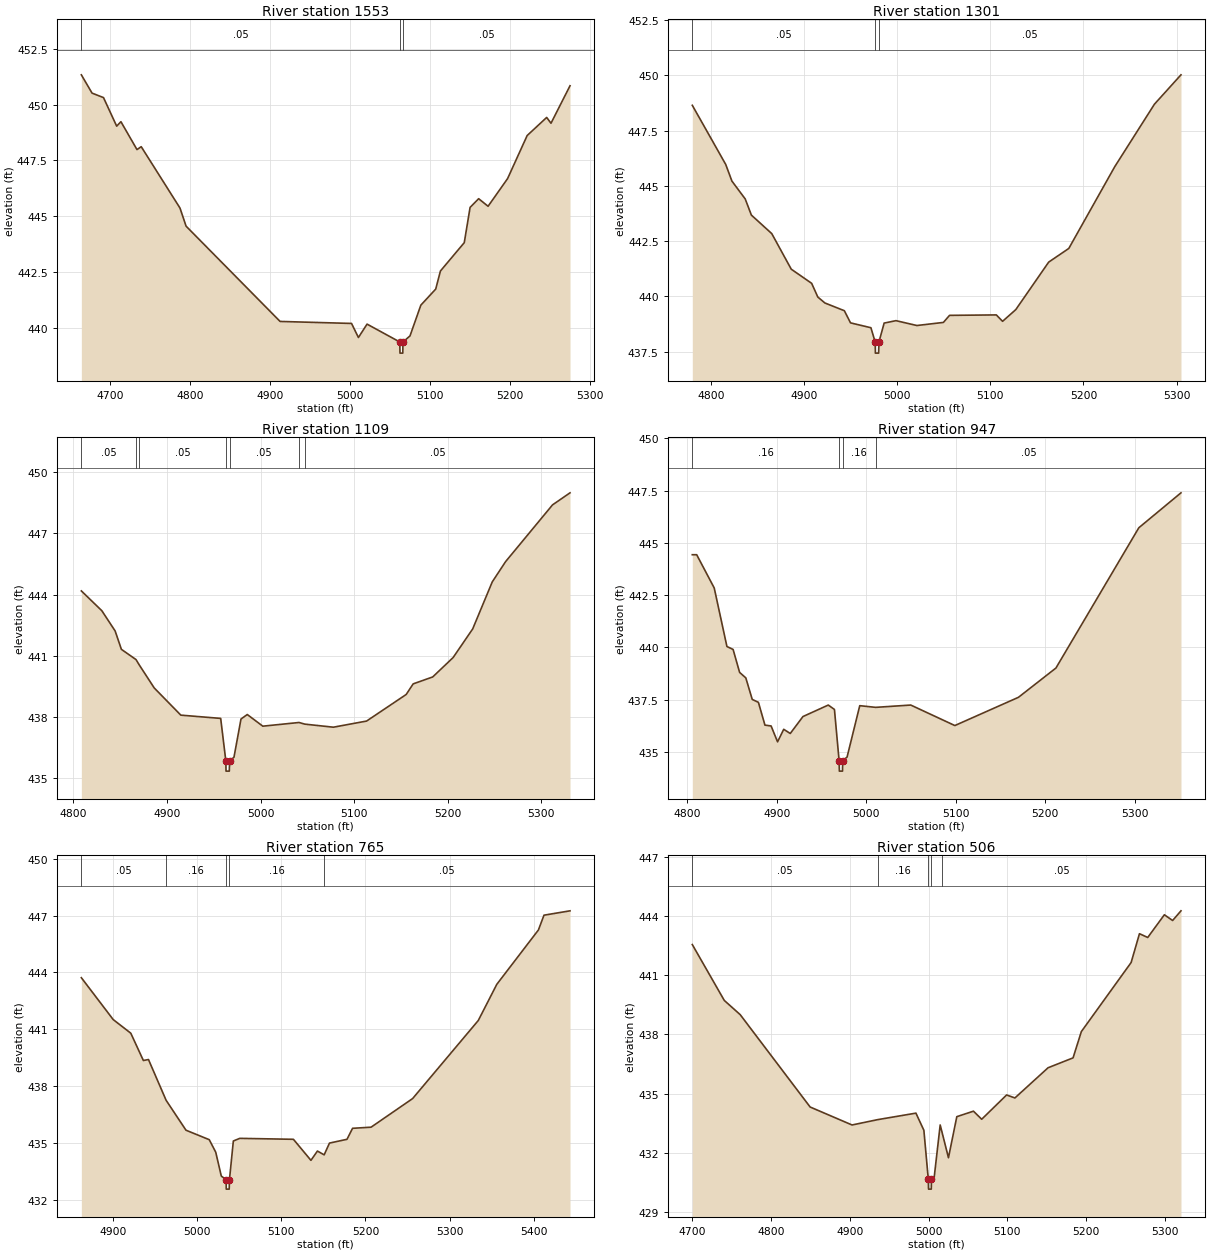
Type RM Length L Ch R = 1,1553,252,252,252
BEGIN DESCRIPTION:
Mill Creek Trib C11553.18
END DESCRIPTION:
XS GIS Cut Line= 3
      2755542.09      6825050.89      2755224.04      6825165.26
      2754969.57      6825264.97
#Sta/Elev= 30
  4664.1  451.33  4677.5  450.51  4691.8  450.31  4708.3  449.03  4713.6  449.23
  4733.7  447.98  4739.0  448.11  4787.5  445.36  4795.1  444.55  4912.7  440.28
  5002.1  440.19  5010.7  439.56  5021.5  440.16  5062.4  439.36  5062.7  438.86
  5066.2  438.86  5066.4  439.36  5075.2  439.63  5088.8  441.01  5107.4  441.73
  5113.3  442.54  5143.1  443.81  5150.4  445.39  5161.1  445.78  5172.9  445.44
  5197.3  446.68  5221.8  448.61  5246.2  449.42  5251.6  449.16  5275.4  450.84
#Mann=3,-1,0
  4664.1    0.05       0  5062.4    0.05       0  5066.4    0.05       0
Bank Sta=5062.4,5066.4
Exp/Cntr=0.3,0.1

Type RM Length L Ch R = 1,1301,192,192,192
BEGIN DESCRIPTION:
Mill Creek Trib C11300.61
END DESCRIPTION:
XS GIS Cut Line= 3
      2755298.28      6824773.22      2755153.11      6824941.15
      2754951.82      6825166.98
#Sta/Elev= 30
  4780.2  448.65  4816.1  445.97  4822.7  445.22  4837.0  444.41  4843.6  443.68
  4865.5  442.84  4886.4  441.23  4908.3  440.59  4914.9  439.97  4922.5  439.70
  4943.4  439.35  4950.0  438.80  4971.9  438.58  4976.5  437.93  4976.7  437.43
  4980.2  437.43  4980.5  437.93  4986.1  438.79  4998.8  438.90  5021.2  438.68
  5049.7  438.82  5056.3  439.14  5106.5  439.16  5113.2  438.87  5127.4  439.40
  5162.7  441.55  5184.3  442.17  5233.6  445.87  5276.2  448.70  5304.7  450.03
#Mann=3,-1,0
  4780.2    0.05       0  4976.5    0.05       0  4980.5    0.05       0
Bank Sta=4976.5,4980.5
Exp/Cntr=0.3,0.1

Type RM Length L Ch R = 1,1109,162,162,162
BEGIN DESCRIPTION:
Mill Creek Trib C11109.39
END DESCRIPTION:
XS GIS Cut Line= 3
      2755179.40      6824643.94      2755049.52      6824787.97
      2754831.94      6825033.77
#Sta/Elev= 30
  4808.5  444.18  4830.4  443.21  4844.6  442.22  4851.3  441.32  4866.9  440.82
  4870.2  440.57  4886.4  439.43  4914.8  438.10  4957.4  437.94  4962.9  435.86
  4963.1  435.36  4966.6  435.36  4966.9  435.86  4971.6  436.04  4979.1  437.91
  4985.8  438.13  5002.4  437.56  5041.1  437.74  5047.3  437.66  5077.8  437.51
  5113.3  437.81  5155.6  439.11  5163.1  439.63  5184.0  439.97  5205.8  440.92
  5226.7  442.32  5247.6  444.62  5261.8  445.61  5312.0  448.39  5330.7  448.98
#Mann=7,-1,0
  4808.5    0.05       0  4866.9    0.16       0  4870.2    0.05       0
  4962.9    0.05       0  4966.9    0.05       0  5041.1    0.16       0
  5047.3    0.05       0
Bank Sta=4962.9,4966.9
Exp/Cntr=0.3,0.1

Type RM Length L Ch R = 1,947,182,182,182
BEGIN DESCRIPTION:
Mill Creek Trib C1946.56
END DESCRIPTION:
XS GIS Cut Line= 3
      2755108.96      6824519.25      2754964.53      6824656.02
      2754733.39      6824915.35
#Sta/Elev= 30
  4805.5  444.43  4810.4  444.43  4830.0  442.84  4844.2  440.04  4851.1  439.90
  4858.4  438.80  4865.3  438.54  4872.5  437.51  4879.4  437.37  4886.7  436.28
  4893.6  436.24  4900.8  435.48  4907.7  436.08  4915.0  435.88  4929.2  436.69
  4957.5  437.24  4964.4  437.03  4969.6  434.58  4969.9  434.08  4973.4  434.08
  4973.6  434.58  4978.5  434.75  4992.7  437.21  5010.5  437.13  5049.7  437.24
  5099.0  436.26  5170.1  437.61  5212.0  439.01  5304.7  445.72  5351.8  447.39
#Mann=4,-1,0
  4805.5    0.16       0  4969.6    0.07       0  4973.6    0.16       0
  5010.5    0.05       0
Bank Sta=4969.6,4973.6
Exp/Cntr=0.3,0.1

Type RM Length L Ch R = 1,765,259,259,259
BEGIN DESCRIPTION:
Mill Creek Trib C1765.03
END DESCRIPTION:
XS GIS Cut Line= 3
      2755020.36      6824413.22      2754905.27      6824493.52
      2754618.62      6824826.89
#Sta/Elev= 30
  4862.8  443.72  4900.6  441.51  4921.5  440.79  4936.4  439.35  4942.5  439.40
  4963.4  437.25  4987.0  435.67  5014.6  435.17  5022.3  434.51  5028.9  433.25
  5034.6  433.06  5034.8  432.56  5038.3  432.56  5038.6  433.06  5043.2  435.10
  5050.8  435.24  5114.5  435.19  5135.3  434.08  5143.0  434.57  5151.0  434.37
  5157.3  434.99  5178.1  435.19  5184.7  435.77  5206.7  435.83  5256.0  437.34
  5333.9  441.46  5355.9  443.37  5405.3  446.24  5411.9  447.02  5442.8  447.25
#Mann=5,-1,0
  4862.8    0.05       0  4963.4    0.16       0  5034.6    0.07       0
  5038.6    0.16       0  5151.0    0.05       0
Bank Sta=5034.6,5038.6
Exp/Cntr=0.3,0.1

Type RM Length L Ch R = 1,506,0,0,0
BEGIN DESCRIPTION:
Mill Creek Trib C1505.946
END DESCRIPTION:
XS GIS Cut Line= 3
      2754976.02      6824361.00      2754676.00      6824411.00
      2754375.99      6824511.00
#Sta/Elev= 30
  4700.1  442.55  4740.7  439.72  4760.9  439.00  4849.7  434.32  4902.9  433.41
  4935.4  433.68  4984.0  434.01  4994.1  433.14  4999.7  430.66  5000.0  430.16
  5003.5  430.16  5003.7  430.66  5006.9  430.66  5014.8  433.41  5016.9  433.08
  5025.3  431.75  5035.9  433.83  5057.0  434.11  5067.5  433.70  5099.1  434.93
  5109.7  434.78  5151.8  436.31  5183.5  436.81  5194.0  438.14  5257.2  441.64
  5267.8  443.10  5278.3  442.91  5299.4  444.06  5309.9  443.77  5320.5  444.26
#Mann=5,-1,0
  4700.1    0.05       0  4935.4    0.16       0  4999.7    0.07       0
  5003.7    0.16       0  5016.9    0.05       0
Bank Sta=4999.7,5003.7
Exp/Cntr=0.3,0.1

Chan Stop Cuts=-1