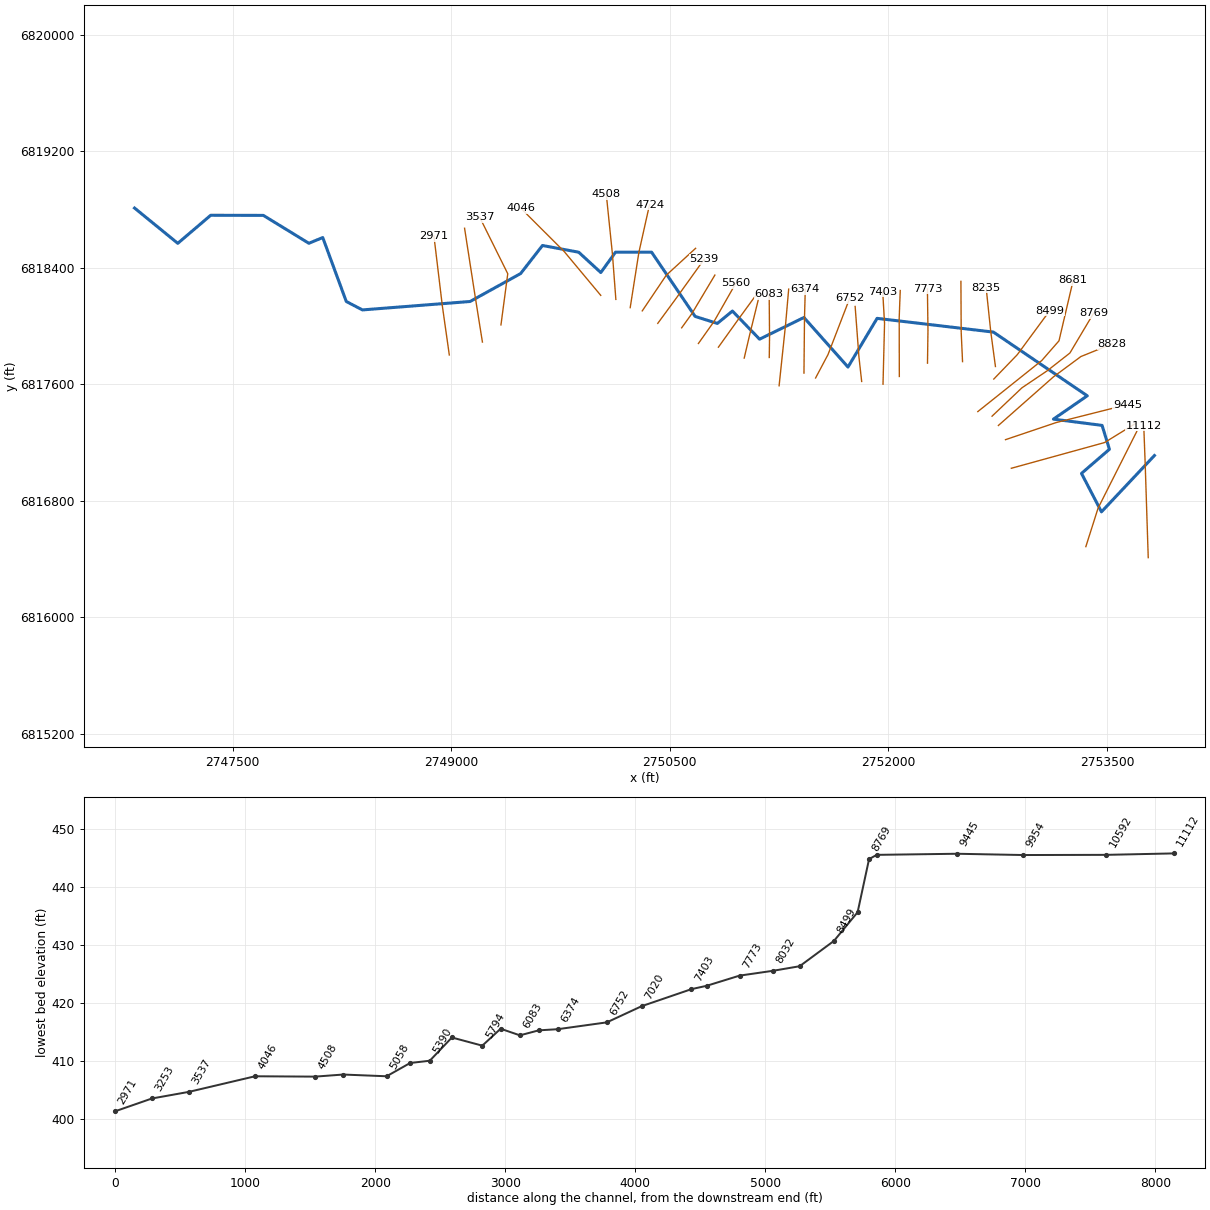
--- Mill Creek Trib D.prj (project) ---

Proj Title=Mill Creek Trib D Base Level Engineering
Current Plan=p01
Default Exp/Contr=0.3,0.1
English Units
Geom File=g01
Flow File=f01
Plan File=p01
BEGIN DESCRIPTION:
Mill Creek Trib D
END DESCRIPTION:

--- Mill Creek Trib D.p01 (plan) ---

Plan Title=Multiple Run
Short Identifier=Multiple
Geom File=g01
Flow File=f01
Subcritical Flow
K Sum by GR= 0
Std Step Tol= 0.01
Critical Tol= 0.01
Num of Std Step Trials= 20
Max Error Tol= 0.3
Flow Tol Ratio= 0.001
Split Flow NTrial= 30
Split Flow Tol= 0.02
Split Flow Ratio= 0.02
Log Output Level= 0
Friction Slope Method= 1
Unsteady Friction Slope Method= 2
Unsteady Bridges Friction Slope Method= 1
Parabolic Critical Depth
Global Vel Dist=  1 , 1 , 1
Global Log Level= 0
CheckData=True
Encroach Param= -1, 0, 0, 0
BEGIN DESCRIPTION:
Multiple Run
END DESCRIPTION:

--- Mill Creek Trib D.f01 (steady flow) ---

Flow Title=Multiple
Number of Profiles=7
Profile Names=10-year,25-year,50-year,1pct_min,100-year,1pct_plu,500-year
River Rch & RM= Mill Creek Trib ,Reach-1,11112
     369     481     568     334     667    1331     920
River Rch & RM= Mill Creek Trib ,Reach-1,3537
     606     814     983     590    1176    2347    1689
Boundary for River Rch & Prof#=Mill Creek Trib ,Reach-1,1
Up Type=0
Dn Type=3
Dn Slope=0.005
Boundary for River Rch & Prof#=Mill Creek Trib ,Reach-1,2
Up Type=0
Dn Type=3
Dn Slope=0.005
Boundary for River Rch & Prof#=Mill Creek Trib ,Reach-1,3
Up Type=0
Dn Type=3
Dn Slope=0.005
Boundary for River Rch & Prof#=Mill Creek Trib ,Reach-1,4
Up Type=0
Dn Type=3
Dn Slope=0.005
Boundary for River Rch & Prof#=Mill Creek Trib ,Reach-1,5
Up Type=0
Dn Type=3
Dn Slope=0.005
Boundary for River Rch & Prof#=Mill Creek Trib ,Reach-1,6
Up Type=0
Dn Type=3
Dn Slope=0.005
Boundary for River Rch & Prof#=Mill Creek Trib ,Reach-1,7
Up Type=0
Dn Type=3
Dn Slope=0.005

--- Mill Creek Trib D.g01 (geometry) ---

Geom Title=Existing Conditions

River Reach=Mill Creek Trib ,Reach-1
Reach XY= 30
      2753826.00      6817111.00      2753462.61      6816724.41
      2753325.44      6816988.21      2753517.15      6817154.05
      2753466.81      6817318.04      2753132.87      6817361.00
      2753365.18      6817521.31      2752720.74      6817958.91
      2751922.58      6818053.19      2751722.78      6817718.83
      2751420.30      6818059.09      2751115.93      6817910.16
      2750929.58      6818103.50      2750826.10      6818018.34
      2750673.57      6818066.52      2750374.97      6818507.54
      2750127.43      6818507.93      2750026.21      6818367.98
      2749874.54      6818507.46      2749625.90      6818553.68
      2749476.00      6818361.00      2749129.31      6818169.07
      2748390.08      6818111.22      2748279.31      6818169.02
      2748117.79      6818608.17      2748022.61      6818568.83
      2747710.11      6818760.45      2747348.66      6818761.22
      2747122.84      6818568.56      2746826.00      6818811.00

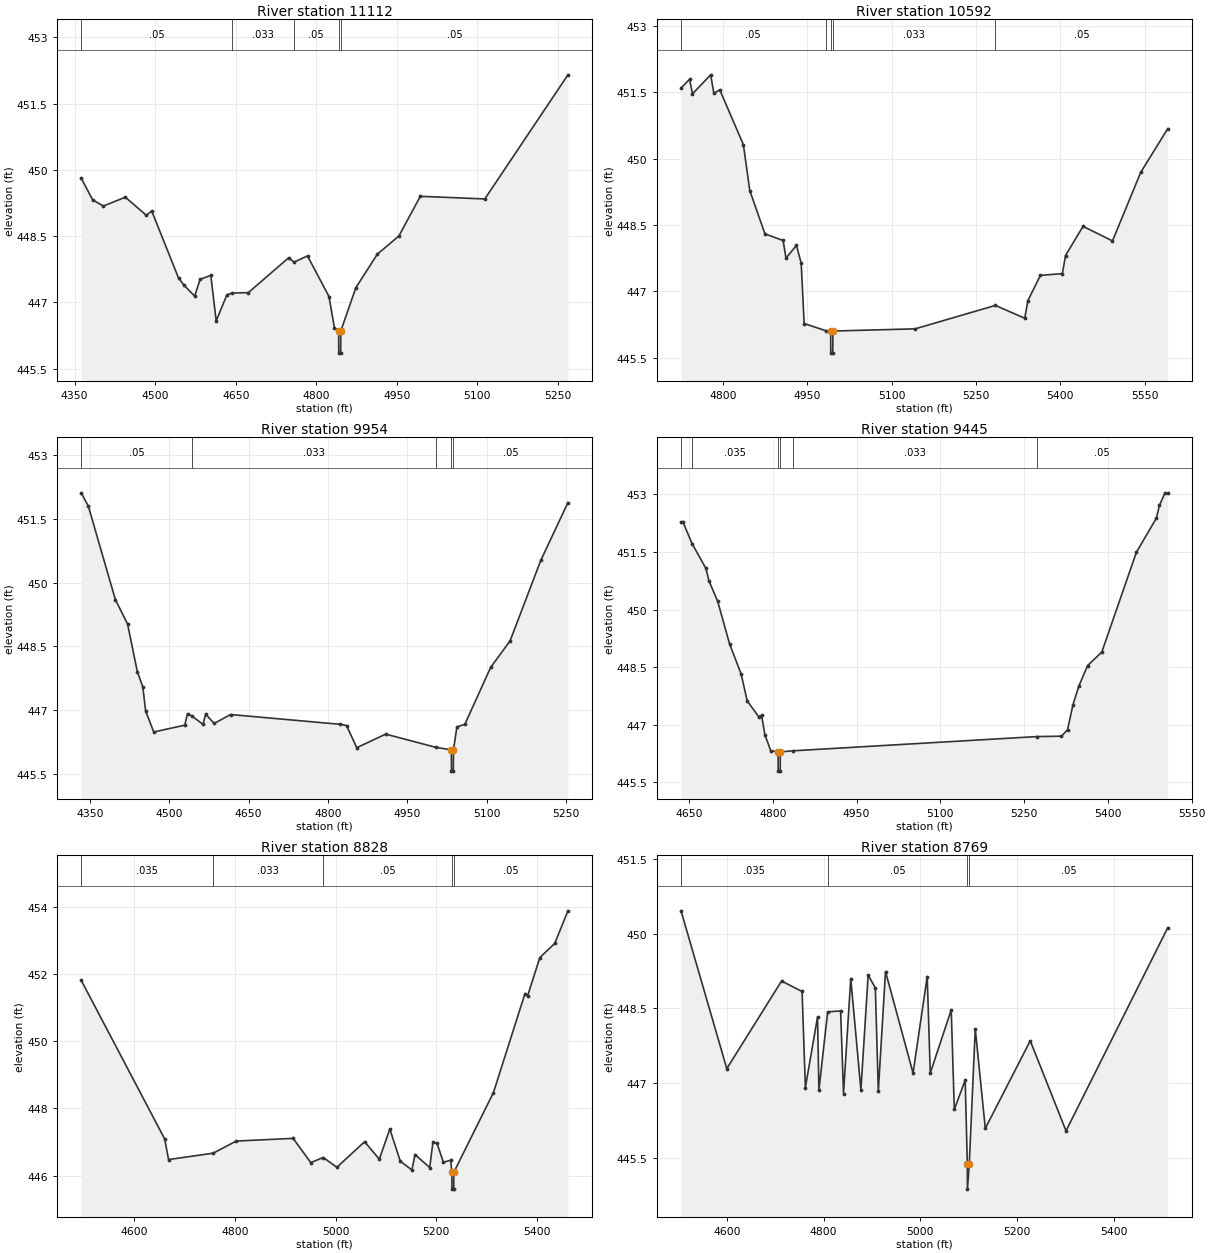
Type RM Length L Ch R = 1,11112,520,520,520
BEGIN DESCRIPTION:
Mill Creek Trib D11111.869
END DESCRIPTION:
XS GIS Cut Line= 3
      2753783.53      6816409.86      2753762.85      6817047.22
      2753752.78      6817315.73
#Sta/Elev= 30
  4362.3  449.81  4383.5  449.32  4403.5  449.18  4444.4  449.38  4483.5  448.97
  4493.5  449.07  4543.5  447.55  4553.5  447.39  4573.6  447.14  4583.6  447.52
  4603.6  447.61  4613.6  446.58  4633.6  447.17  4643.4  447.21  4673.6  447.22
  4748.7  448.01  4758.4  447.91  4783.7  448.05  4823.7  447.13  4833.7  446.43
  4841.7  446.35  4841.9  445.85  4845.4  445.85  4845.7  446.35  4873.7  447.33
  4913.7  448.09  4953.8  448.50  4993.8  449.40  5113.9  449.34  5268.7  452.15
#Mann=5,-1,0
  4362.3    0.05       0  4643.4   0.033       0  4758.4    0.05       0
  4841.7    0.05       0  4845.7    0.05       0
Bank Sta=4841.7,4845.7
Exp/Cntr=0.3,0.1

Type RM Length L Ch R = 1,10592,638,638,638
BEGIN DESCRIPTION:
Mill Creek Trib D10591.91
END DESCRIPTION:
XS GIS Cut Line= 3
      2753355.24      6816485.22      2753439.24      6816749.57
      2753704.38      6817275.54
#Sta/Elev= 30
  4724.9  451.60  4740.1  451.80  4745.3  451.47  4777.6  451.90  4783.4  451.48
  4793.9  451.56  4835.9  450.32  4847.3  449.28  4874.3  448.30  4906.6  448.15
  4911.8  447.75  4930.3  448.04  4938.8  447.64  4944.1  446.27  4982.1  446.11
  4991.3  446.10  4991.5  445.60  4995.0  445.60  4995.3  446.10  5141.7  446.15
  5284.5  446.68  5336.8  446.39  5342.4  446.79  5364.7  447.36  5403.8  447.40
  5409.4  447.81  5440.6  448.47  5493.0  448.14  5543.2  449.69  5591.3  450.68
#Mann=5,-1,0
  4724.9    0.05       0  4982.1   0.033       0  4991.3   0.033       0
  4995.3   0.033       0  5284.5    0.05       0
Bank Sta=4991.3,4995.3
Exp/Cntr=0.3,0.1

Type RM Length L Ch R = 1,9954,509,509,509
BEGIN DESCRIPTION:
Mill Creek Trib D9954.29
END DESCRIPTION:
XS GIS Cut Line= 3
      2752843.83      6817023.52      2753483.47      6817200.05
      2753701.98      6817334.66
#Sta/Elev= 30
  4333.6  452.11  4347.2  451.79  4398.1  449.60  4421.1  449.03  4439.6  447.91
  4450.0  447.55  4455.4  446.98  4470.7  446.49  4529.3  446.65  4534.5  446.92
  4542.3  446.87  4563.7  446.67  4568.9  446.91  4584.8  446.69  4615.9  446.90
  4823.4  446.67  4835.3  446.64  4854.5  446.12  4909.2  446.44  5003.9  446.13
  5033.4  446.07  5033.6  445.57  5037.1  445.57  5037.4  446.07  5043.9  446.61
  5058.9  446.67  5107.8  448.01  5144.4  448.63  5202.4  450.52  5253.8  451.88
#Mann=5,-1,0
  4333.6    0.05       0  4542.3   0.033       0  5003.9    0.05       0
  5033.4   0.033       0  5037.4    0.05       0
Bank Sta=5033.4,5037.4
Exp/Cntr=0.3,0.1

Type RM Length L Ch R = 1,9445,617,617,617
BEGIN DESCRIPTION:
Mill Creek Trib D9445.18
END DESCRIPTION:
XS GIS Cut Line= 3
      2752803.78      6817219.98      2753151.56      6817337.49
      2753640.39      6817461.03
#Sta/Elev= 30
  4635.8  452.27  4639.6  452.27  4655.8  451.71  4680.4  451.07  4685.7  450.75
  4701.5  450.21  4722.6  449.11  4743.4  448.32  4754.3  447.62  4774.8  447.21
  4780.1  447.24  4785.9  446.74  4796.5  446.32  4809.6  446.29  4809.8  445.79
  4813.3  445.79  4813.6  446.29  4836.8  446.32  5272.6  446.69  5316.9  446.70
  5327.8  446.87  5337.5  447.52  5347.9  448.00  5363.7  448.54  5389.1  448.89
  5451.0  451.49  5486.8  452.38  5492.3  452.71  5502.2  453.04  5507.1  453.04
#Mann=6,-1,0
  4635.8    0.05       0  4655.8   0.035       0  4809.6   0.033       0
  4813.6   0.035       0  4836.8   0.033       0  5272.6    0.05       0
Bank Sta=4809.6,4813.6
Exp/Cntr=0.3,0.1

Type RM Length L Ch R = 1,8828,59,59,59
BEGIN DESCRIPTION:
Mill Creek Trib D8828.19
END DESCRIPTION:
XS GIS Cut Line= 4
      2752755.09      6817317.50      2753132.94      6817651.36
      2753321.42      6817791.01      2753533.27      6817876.67
#Sta/Elev= 30
  4494.3  451.81  4660.2  447.09  4667.8  446.48  4756.6  446.67  4802.4  447.03
  4915.4  447.11  4950.5  446.39  4975.2  446.54  5002.4  446.25  5057.5  447.01
  5086.8  446.49  5107.6  447.39  5128.4  446.43  5151.5  446.17  5157.7  446.63
  5186.9  446.24  5193.2  446.99  5201.5  446.96  5214.0  446.40  5228.6  446.46
  5230.8  446.10  5231.1  445.60  5234.6  445.60  5234.8  446.10  5313.5  448.47
  5376.3  451.42  5381.7  451.36  5405.8  452.49  5435.4  452.91  5461.6  453.88
#Mann=5,-1,0
  4494.3   0.035       0  4756.6   0.033       0  4975.2    0.05       0
  5230.8    0.05       0  5234.8    0.05       0
Bank Sta=5230.8,5234.8
Exp/Cntr=0.3,0.1

Type RM Length L Ch R = 1,8769,88,88,88
BEGIN DESCRIPTION:
Mill Creek Trib D8768.67
END DESCRIPTION:
XS GIS Cut Line= 5
      2752711.64      6817381.39      2752916.45      6817575.99
      2753092.21      6817694.54      2753245.86      6817815.16
      2753408.08      6818087.67
#Sta/Elev= 30
  4505.1  450.46  4599.8  447.29  4713.1  449.05  4755.6  448.84  4762.4  446.91
  4787.6  448.33  4790.4  446.86  4808.5  448.43  4835.3  448.45  4841.3  446.79
  4856.3  449.10  4877.3  446.86  4892.3  449.17  4907.2  448.91  4913.3  446.84
  4928.2  449.24  4985.2  447.20  5014.5  449.14  5020.8  447.20  5064.2  448.47
  5070.6  446.47  5093.1  447.06  5097.5  445.37  5097.7  444.87  5101.5  445.37
  5113.9  448.09  5134.7  446.09  5227.7  447.85  5301.7  446.04  5512.1  450.12
#Mann=4,-1,0
  4505.1   0.035       0  4808.5    0.05       0  5097.5    0.05       0
  5101.5    0.05       0
Bank Sta=5097.5,5101.5
Exp/Cntr=0.3,0.1

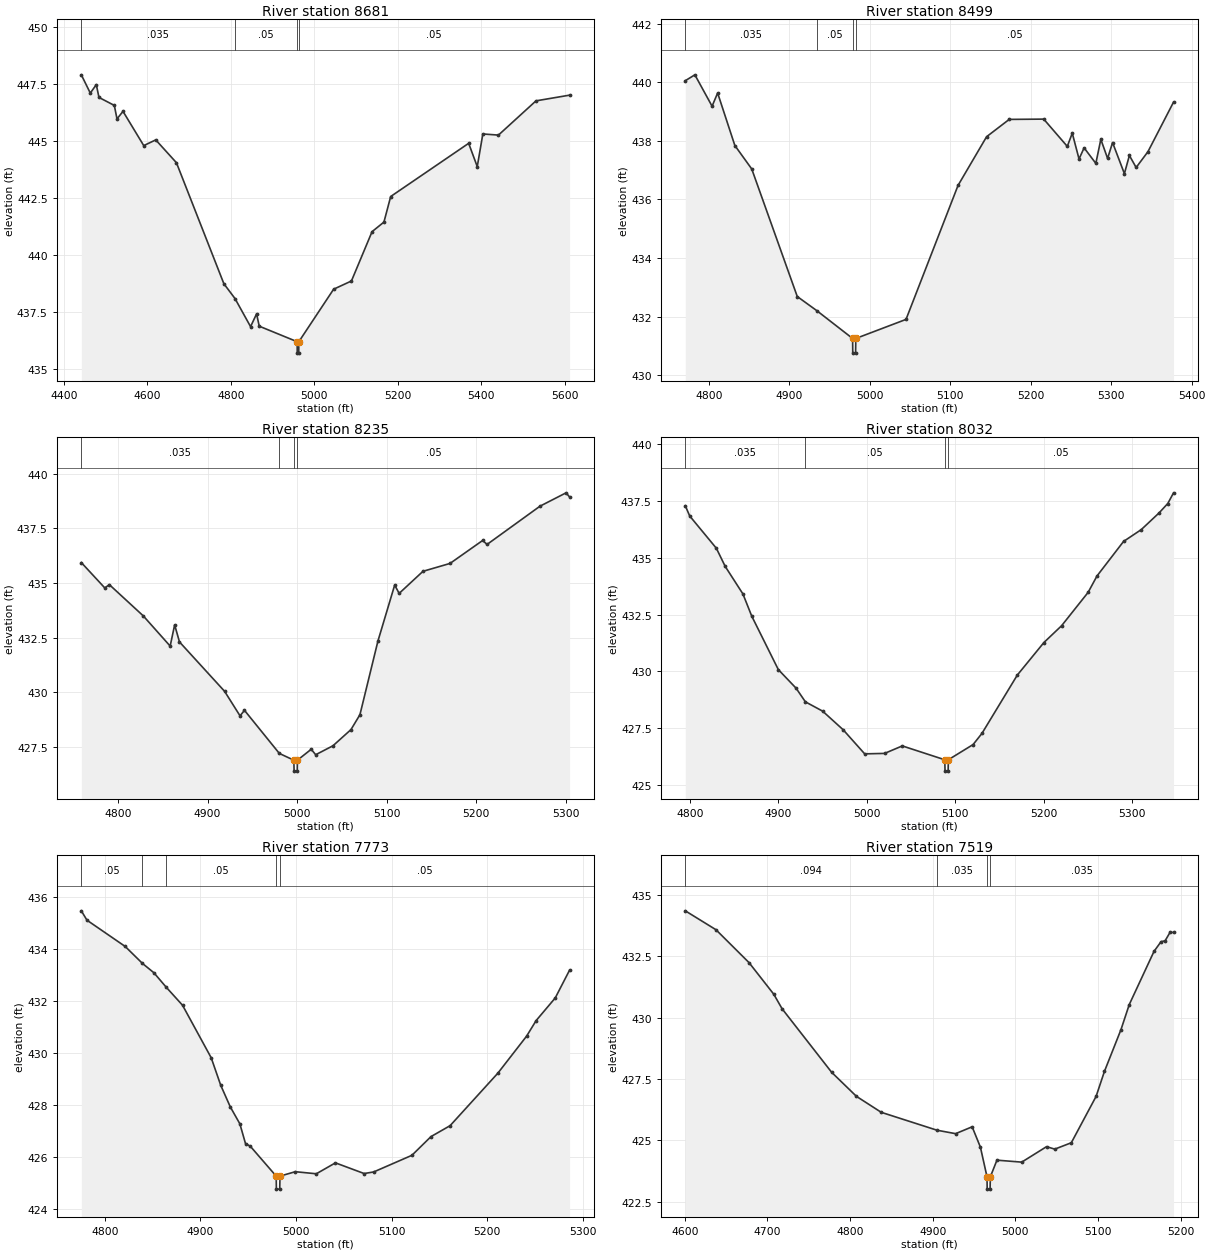
Type RM Length L Ch R = 1,8681,182,182,182
BEGIN DESCRIPTION:
Mill Creek Trib D8680.59
END DESCRIPTION:
XS GIS Cut Line= 4
      2752613.90      6817412.84      2753053.04      6817763.73
      2753171.06      6817899.07      2753268.86      6818316.49
#Sta/Elev= 30
  4441.7  447.90  4463.2  447.10  4477.6  447.47  4484.0  446.91  4520.8  446.56
  4527.2  445.97  4541.6  446.30  4591.3  444.80  4620.1  445.05  4669.7  444.05
  4783.4  438.75  4810.1  438.10  4847.4  436.87  4861.8  437.43  4868.2  436.89
  4959.1  436.21  4959.3  435.71  4962.8  435.71  4963.1  436.21  5046.5  438.51
  5089.2  438.87  5138.6  441.03  5167.1  441.45  5183.3  442.57  5370.2  444.90
  5390.8  443.88  5404.2  445.31  5441.6  445.26  5531.6  446.76  5612.1  447.01
#Mann=4,-1,0
  4441.7   0.035       0  4810.1    0.05       0  4959.1    0.05       0
  4963.1    0.05       0
Bank Sta=4959.1,4963.1
Exp/Cntr=0.3,0.1

Type RM Length L Ch R = 1,8499,264,264,264
BEGIN DESCRIPTION:
Mill Creek Trib D8499.37
END DESCRIPTION:
XS GIS Cut Line= 3
      2752723.68      6817636.46      2752884.99      6817803.99
      2753107.03      6818105.49
#Sta/Elev= 30
  4770.5  440.05  4782.4  440.25  4803.8  439.18  4810.7  439.63  4832.1  437.84
  4853.1  437.04  4909.7  432.69  4933.9  432.21  4978.5  431.26  4978.7  430.76
  4982.2  430.76  4982.5  431.26  5044.9  431.91  5109.6  436.48  5145.1  438.14
  5173.2  438.73  5216.1  438.74  5245.4  437.81  5251.6  438.26  5260.0  437.38
  5266.3  437.76  5280.9  437.23  5287.1  438.05  5295.5  437.40  5301.7  437.94
  5316.4  436.88  5322.6  437.50  5331.0  437.09  5345.7  437.63  5377.5  439.32
#Mann=4,-1,0
  4770.5   0.035       0  4933.9    0.05       0  4978.5    0.05       0
  4982.5    0.05       0
Bank Sta=4978.5,4982.5
Exp/Cntr=0.3,0.1

Type RM Length L Ch R = 1,8235,203,203,203
BEGIN DESCRIPTION:
Mill Creek Trib D8234.76
END DESCRIPTION:
XS GIS Cut Line= 3
      2752734.81      6817722.39      2752702.52      6817963.23
      2752671.00      6818263.79
#Sta/Elev= 30
  4759.0  435.93  4785.2  434.77  4790.3  434.92  4828.2  433.49  4858.2  432.11
  4863.2  433.08  4868.6  432.30  4919.0  430.04  4936.2  428.92  4941.2  429.17
  4980.1  427.20  4996.3  426.89  4996.6  426.39  5000.1  426.39  5000.3  426.89
  5015.7  427.39  5020.7  427.14  5040.0  427.55  5060.1  428.29  5070.1  428.97
  5090.2  432.34  5108.9  434.90  5113.9  434.52  5140.5  435.53  5170.7  435.89
  5207.1  436.94  5212.1  436.76  5271.2  438.51  5300.3  439.12  5304.2  438.93
#Mann=4,-1,0
  4759.0   0.035       0  4980.1    0.05       0  4996.3    0.05       0
  5000.3    0.05       0
Bank Sta=4996.3,5000.3
Exp/Cntr=0.3,0.1

Type RM Length L Ch R = 1,8032,259,259,259
BEGIN DESCRIPTION:
Mill Creek Trib D8031.67
END DESCRIPTION:
XS GIS Cut Line= 3
      2752509.06      6817755.98      2752499.69      6817960.93
      2752497.91      6818307.46
#Sta/Elev= 30
  4795.0  437.29  4800.0  436.84  4830.1  435.42  4840.1  434.62  4860.1  433.41
  4870.1  432.43  4900.1  430.08  4920.2  429.26  4930.7  428.66  4950.2  428.25
  4973.4  427.43  4997.7  426.37  5020.2  426.39  5040.2  426.72  5088.2  426.11
  5088.5  425.61  5092.0  425.61  5092.2  426.11  5120.2  426.78  5130.2  427.27
  5170.2  429.84  5200.2  431.27  5220.2  432.01  5250.2  433.48  5260.2  434.20
  5290.2  435.72  5310.2  436.24  5330.2  436.97  5340.2  437.39  5346.7  437.86
#Mann=4,-1,0
  4795.0   0.035       0  4930.7    0.05       0  5088.2    0.05       0
  5092.2    0.05       0
Bank Sta=5088.2,5092.2
Exp/Cntr=0.3,0.1

Type RM Length L Ch R = 1,7773,254,254,254
BEGIN DESCRIPTION:
Mill Creek Trib D7773.21
END DESCRIPTION:
XS GIS Cut Line= 3
      2752268.46      6817745.14      2752271.80      6817972.09
      2752267.88      6818255.99
#Sta/Elev= 30
  4775.4  435.47  4781.3  435.11  4821.3  434.10  4839.3  433.45  4851.3  433.09
  4864.3  432.53  4881.3  431.84  4911.3  429.82  4921.3  428.76  4931.3  427.93
  4941.3  427.28  4947.2  426.52  4952.2  426.42  4979.3  425.27  4979.5  424.77
  4983.0  424.77  4983.3  425.27  4999.3  425.44  5021.3  425.36  5041.3  425.78
  5071.3  425.37  5081.3  425.43  5121.3  426.07  5141.3  426.79  5161.3  427.21
  5211.3  429.23  5241.3  430.65  5251.3  431.25  5271.3  432.12  5286.3  433.19
#Mann=5,-1,0
  4775.4    0.05       0  4839.3   0.035       0  4864.3    0.05       0
  4979.3    0.05       0  4983.3    0.05       0
Bank Sta=4979.3,4983.3
Exp/Cntr=0.3,0.1

Type RM Length L Ch R = 1,7519,116,116,116
BEGIN DESCRIPTION:
Mill Creek Trib D7519.09
END DESCRIPTION:
XS GIS Cut Line= 3
      2752075.14      6817653.92      2752074.25      6818055.64
      2752081.45      6818244.58
#Sta/Elev= 30
  4600.6  434.35  4637.7  433.58  4677.7  432.24  4707.7  430.95  4717.7  430.36
  4777.7  427.77  4807.7  426.79  4837.7  426.14  4905.2  425.41  4927.7  425.27
  4947.7  425.55  4957.7  424.72  4965.7  423.51  4965.9  423.01  4969.4  423.01
  4969.7  423.51  4977.7  424.19  5007.7  424.11  5037.7  424.74  5047.7  424.64
  5067.7  424.90  5097.7  426.79  5107.8  427.81  5127.8  429.51  5137.8  430.53
  5167.8  432.70  5176.2  433.09  5181.2  433.13  5187.1  433.47  5191.4  433.47
#Mann=4,-1,0
  4600.6   0.094       0  4905.2   0.035       0  4965.7   0.035       0
  4969.7   0.035       0
Bank Sta=4965.7,4969.7
Exp/Cntr=0.3,0.1

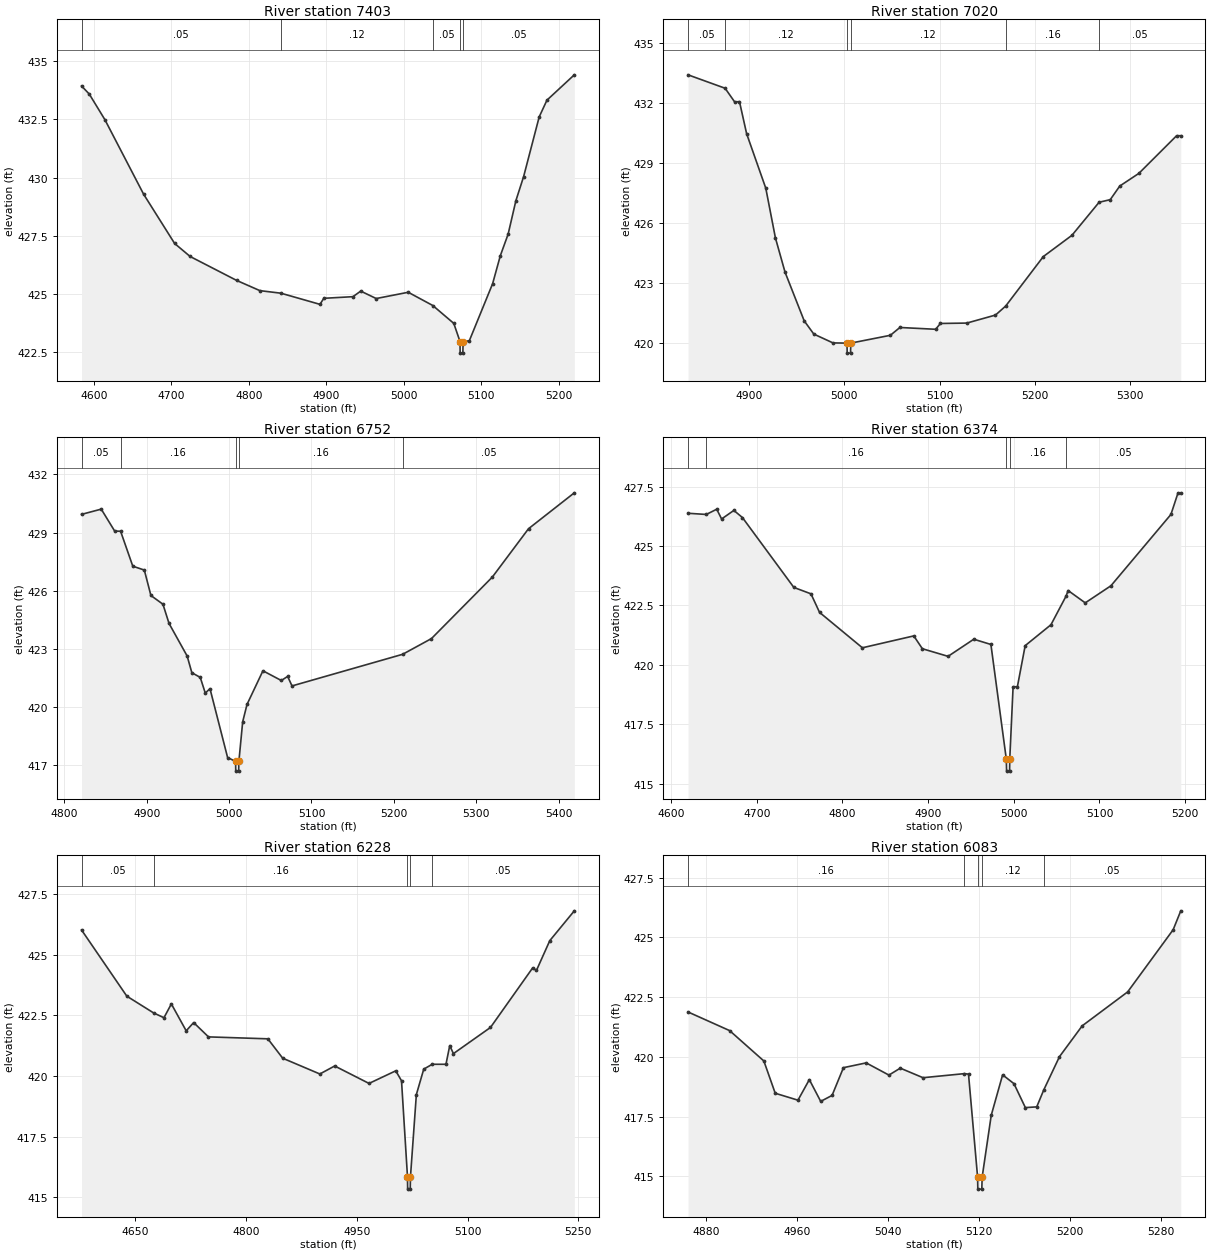
Type RM Length L Ch R = 1,7403,383,383,383
BEGIN DESCRIPTION:
Mill Creek Trib D7403.25
END DESCRIPTION:
XS GIS Cut Line= 3
      2751963.21      6817600.95      2751973.71      6818018.57
      2751961.10      6818236.26
#Sta/Elev= 30
  4584.1  433.94  4594.1  433.59  4614.2  432.49  4664.2  429.28  4704.2  427.16
  4724.2  426.60  4784.2  425.57  4814.2  425.13  4841.3  425.02  4891.7  424.54
  4896.7  424.80  4934.3  424.87  4944.3  425.11  4964.3  424.79  5005.6  425.06
  5037.3  424.49  5064.4  423.72  5072.4  422.94  5072.6  422.44  5076.1  422.44
  5076.4  422.94  5084.4  422.97  5114.5  425.43  5124.5  426.64  5134.5  427.56
  5144.5  429.00  5154.5  430.04  5174.6  432.61  5184.6  433.33  5219.9  434.42
#Mann=5,-1,0
  4584.1    0.05       0  4841.3    0.12       0  5037.3    0.05       0
  5072.4    0.07       0  5076.4    0.05       0
Bank Sta=5072.4,5076.4
Exp/Cntr=0.3,0.1

Type RM Length L Ch R = 1,7020,268,268,268
BEGIN DESCRIPTION:
Mill Creek Trib D7019.63
END DESCRIPTION:
XS GIS Cut Line= 3
      2751816.67      6817619.85      2751797.88      6817789.15
      2751771.89      6818134.84
#Sta/Elev= 30
  4836.1  433.39  4875.0  432.72  4885.0  432.04  4890.1  432.05  4897.6  430.45
  4917.7  427.73  4927.8  425.25  4937.9  423.54  4958.0  421.11  4968.1  420.45
  4988.2  420.01  5002.9  420.00  5003.1  419.50  5006.6  419.50  5006.9  420.00
  5048.4  420.39  5058.4  420.78  5095.9  420.69  5100.9  420.98  5128.6  421.00
  5158.7  421.40  5169.4  421.85  5208.9  424.32  5238.9  425.38  5267.4  427.03
  5279.1  427.16  5289.1  427.84  5309.1  428.47  5348.7  430.35  5353.1  430.35
#Mann=6,-1,0
  4836.1    0.05       0  4875.0    0.12       0  5002.9    0.07       0
  5006.9    0.12       0  5169.4    0.16       0  5267.4    0.05       0
Bank Sta=5002.9,5006.9
Exp/Cntr=0.3,0.1

Type RM Length L Ch R = 1,6752,378,378,378
BEGIN DESCRIPTION:
Mill Creek Trib D6750.94
END DESCRIPTION:
XS GIS Cut Line= 3
      2751500.43      6817643.70      2751585.80      6817804.81
      2751735.22      6818192.91
#Sta/Elev= 30
  4820.9  429.94  4844.8  430.21  4861.1  429.08  4868.3  429.07  4883.1  427.27
  4897.1  427.07  4905.1  425.76  4919.7  425.31  4927.1  424.32  4949.1  422.64
  4954.8  421.78  4965.0  421.54  4971.1  420.73  4976.8  420.96  4998.2  417.41
  5007.9  417.21  5008.1  416.71  5011.6  416.71  5011.9  417.21  5016.5  419.25
  5021.8  420.15  5041.1  421.88  5063.4  421.38  5071.1  421.59  5076.4  421.10
  5210.7  422.73  5245.7  423.54  5319.6  426.71  5363.5  429.20  5419.1  431.05
#Mann=5,-1,0
  4820.9    0.05       0  4868.3    0.16       0  5007.9    0.07       0
  5011.9    0.16       0  5210.7    0.05       0
Bank Sta=5007.9,5011.9
Exp/Cntr=0.3,0.1

Type RM Length L Ch R = 1,6374,146,146,146
BEGIN DESCRIPTION:
Mill Creek Trib D6408.15
END DESCRIPTION:
XS GIS Cut Line= 3
      2751420.62      6817677.48      2751424.28      6818057.66
      2751429.71      6818252.49
#Sta/Elev= 30
  4619.8  426.38  4641.1  426.33  4653.3  426.55  4659.0  426.14  4673.3  426.50
  4683.3  426.20  4743.3  423.26  4763.3  422.99  4773.3  422.21  4823.3  420.72
  4883.3  421.22  4893.3  420.68  4923.3  420.36  4953.3  421.08  4973.3  420.86
  4991.3  416.03  4991.6  415.53  4995.1  415.53  4995.3  416.03  4999.2  419.08
  5004.2  419.08  5013.3  420.81  5043.4  421.69  5061.1  422.90  5063.4  423.13
  5083.4  422.61  5113.4  423.33  5183.4  426.33  5191.7  427.24  5194.9  427.24
#Mann=5,-1,0
  4619.8    0.05       0  4641.1    0.16       0  4991.3    0.07       0
  4995.3    0.16       0  5061.1    0.05       0
Bank Sta=4991.3,4995.3
Exp/Cntr=0.3,0.1

Type RM Length L Ch R = 1,6228,145,145,145
BEGIN DESCRIPTION:
Mill Creek Trib D6255.01
END DESCRIPTION:
XS GIS Cut Line= 3
      2751249.98      6817590.06      2751294.39      6818010.52
      2751315.74      6818254.09
#Sta/Elev= 30
  4577.2  426.02  4638.5  423.29  4674.7  422.60  4688.8  422.40  4698.8  422.97
  4718.9  421.86  4729.0  422.20  4749.1  421.61  4829.5  421.53  4849.6  420.73
  4899.9  420.08  4920.0  420.41  4966.5  419.69  5002.7  420.21  5010.5  419.80
  5018.6  415.83  5018.8  415.33  5022.3  415.33  5022.6  415.83  5030.6  419.23
  5040.6  420.28  5052.1  420.48  5070.7  420.48  5075.8  421.25  5080.8  420.92
  5131.0  422.00  5188.2  424.46  5193.2  424.35  5211.3  425.58  5244.5  426.81
#Mann=5,-1,0
  4577.2    0.05       0  4674.7    0.16       0  5018.6    0.07       0
  5022.6    0.16       0  5052.1    0.05       0
Bank Sta=5018.6,5022.6
Exp/Cntr=0.3,0.1

Type RM Length L Ch R = 1,6083,148,148,148
BEGIN DESCRIPTION:
Mill Creek Trib D6082.93
END DESCRIPTION:
XS GIS Cut Line= 3
      2751182.40      6817784.35      2751184.49      6817926.00
      2751181.84      6818217.73
#Sta/Elev= 30
  4863.9  421.88  4900.5  421.10  4930.6  419.83  4940.6  418.48  4960.6  418.19
  4970.6  419.05  4980.6  418.14  4990.6  418.39  5000.6  419.55  5020.6  419.75
  5040.6  419.24  5050.6  419.53  5070.6  419.13  5106.9  419.30  5110.6  419.28
  5118.6  414.97  5118.8  414.47  5122.3  414.47  5122.6  414.97  5130.6  417.56
  5140.6  419.25  5150.6  418.88  5160.6  417.88  5170.6  417.91  5176.8  418.62
  5190.6  420.01  5210.6  421.30  5250.6  422.72  5290.6  425.32  5297.3  426.11
#Mann=5,-1,0
  4863.9    0.16       0  5106.9    0.12       0  5118.6    0.07       0
  5122.6    0.12       0  5176.8    0.05       0
Bank Sta=5118.6,5122.6
Exp/Cntr=0.3,0.1

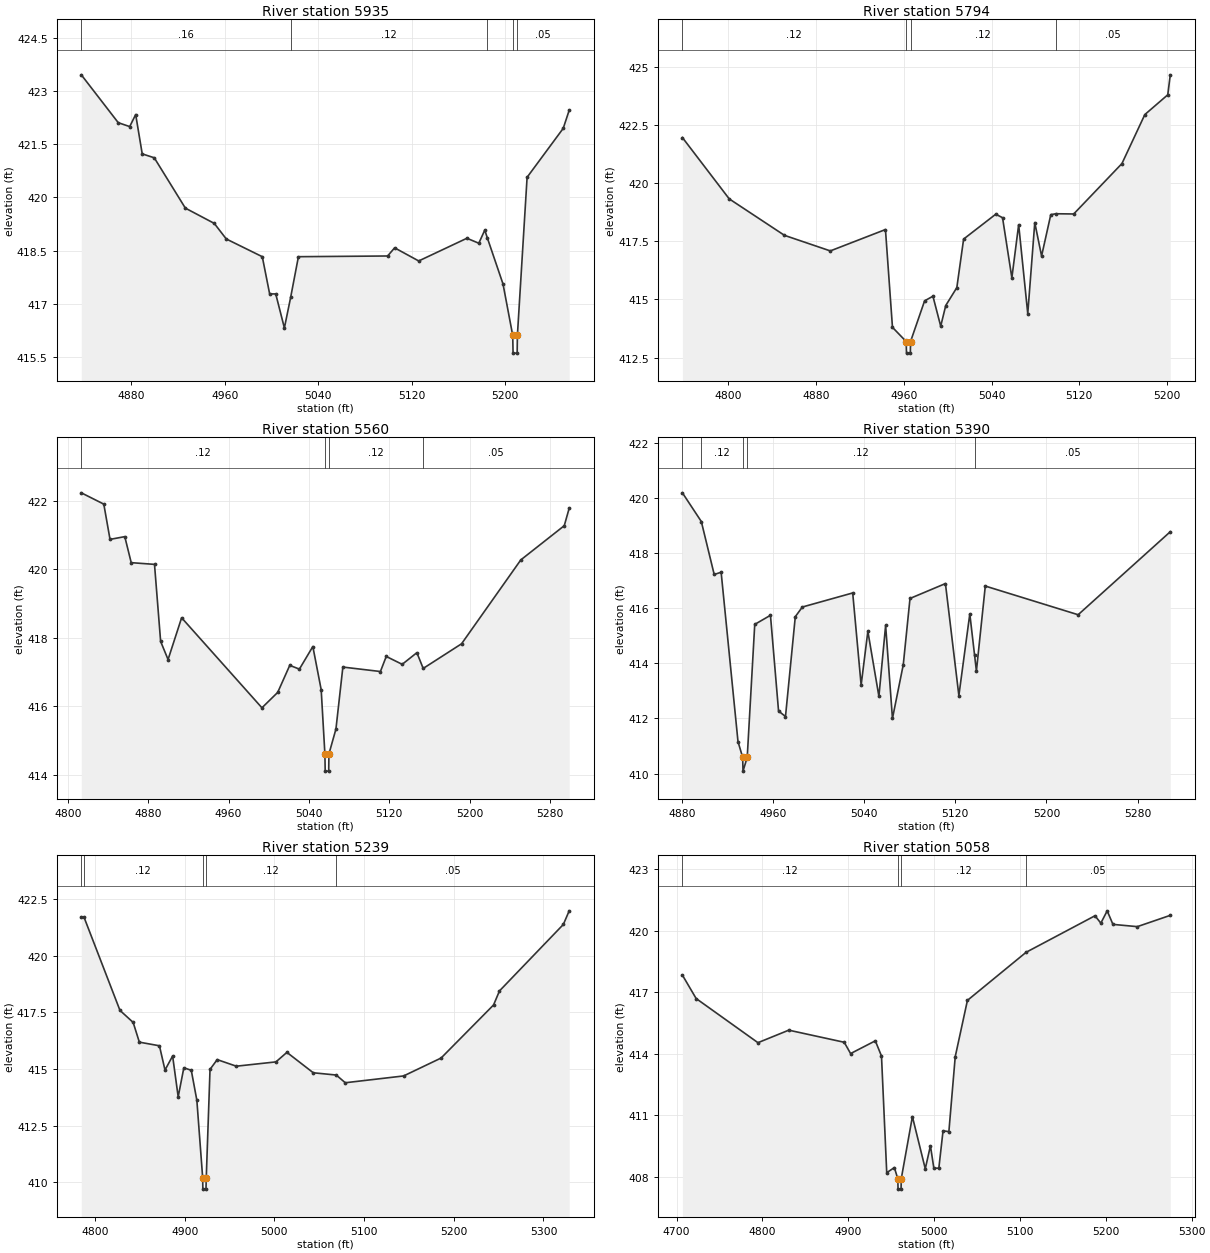
Type RM Length L Ch R = 1,5935,141,141,141
BEGIN DESCRIPTION:
Mill Creek Trib D5934.71
END DESCRIPTION:
XS GIS Cut Line= 3
      2751010.50      6817780.27      2751047.47      6817938.28
      2751108.25      6818185.95
#Sta/Elev= 30
  4837.3  423.46  4868.9  422.11  4878.7  422.00  4883.8  422.34  4889.4  421.23
  4899.7  421.12  4926.3  419.70  4951.0  419.27  4961.3  418.83  4992.1  418.33
  4998.4  417.28  5003.6  417.28  5011.0  416.32  5016.4  417.19  5023.0  418.33
  5099.3  418.35  5105.3  418.58  5125.9  418.21  5167.1  418.85  5177.3  418.71
  5182.4  419.08  5184.7  418.85  5198.0  417.56  5206.3  416.11  5206.6  415.61
  5210.1  415.61  5210.3  416.11  5218.6  420.57  5249.5  421.95  5254.6  422.46
#Mann=5,-1,0
  4837.3    0.16       0  5016.4    0.12       0  5184.7    0.05       0
  5206.3    0.07       0  5210.3    0.05       0
Bank Sta=5206.3,5210.3
Exp/Cntr=0.3,0.1

Type RM Length L Ch R = 1,5794,234,234,234
BEGIN DESCRIPTION:
Mill Creek Trib D5794.29
END DESCRIPTION:
XS GIS Cut Line= 3
      2750833.35      6817855.17      2750975.23      6818053.44
      2751093.70      6818216.06
#Sta/Elev= 30
  4758.0  421.97  4800.7  419.33  4851.1  417.76  4892.9  417.09  4943.2  418.01
  4949.6  413.80  4962.1  413.19  4962.4  412.69  4965.9  412.69  4966.1  413.19
  4978.9  414.94  4986.5  415.14  4993.6  413.85  4998.2  414.74  5008.3  415.51
  5014.5  417.60  5043.8  418.67  5050.0  418.52  5058.5  415.93  5064.7  418.22
  5073.0  414.39  5079.4  418.31  5085.6  416.87  5094.0  418.65  5098.6  418.69
  5114.9  418.68  5158.9  420.85  5179.8  422.96  5200.7  423.81  5203.0  424.67
#Mann=4,-1,0
  4758.0    0.12       0  4962.1    0.07       0  4966.1    0.12       0
  5098.6    0.05       0
Bank Sta=4962.1,4966.1
Exp/Cntr=0.3,0.1

Type RM Length L Ch R = 1,5560,170,170,170
BEGIN DESCRIPTION:
Mill Creek Trib D5560.24
END DESCRIPTION:
XS GIS Cut Line= 3
      2750696.06      6817880.49      2750803.73      6818032.41
      2750951.96      6818292.88
#Sta/Elev= 30
  4813.3  422.23  4835.7  421.90  4841.9  420.87  4856.6  420.95  4863.0  420.19
  4886.2  420.14  4892.3  417.89  4899.7  417.36  4913.2  418.58  4993.2  415.95
  5008.9  416.40  5020.9  417.19  5030.5  417.08  5043.9  417.74  5052.2  416.48
  5055.9  414.60  5056.2  414.10  5059.7  414.10  5059.9  414.60  5066.9  415.33
  5073.8  417.14  5111.2  417.01  5117.0  417.45  5132.9  417.22  5147.5  417.56
  5153.8  417.10  5192.0  417.82  5251.0  420.27  5294.3  421.27  5299.2  421.78
#Mann=4,-1,0
  4813.3    0.12       0  5055.9    0.07       0  5059.9    0.12       0
  5153.8    0.05       0
Bank Sta=5055.9,5059.9
Exp/Cntr=0.3,0.1

Type RM Length L Ch R = 1,5390,151,151,151
BEGIN DESCRIPTION:
Mill Creek Trib D5390.34
END DESCRIPTION:
XS GIS Cut Line= 3
      2750581.23      6817988.20      2750650.91      6818085.10
      2750809.17      6818350.44
#Sta/Elev= 30
  4880.4  420.18  4897.0  419.14  4908.3  417.22  4914.4  417.30  4929.2  411.16
  4933.3  410.59  4933.6  410.09  4937.3  410.59  4943.9  415.41  4957.7  415.74
  4964.8  412.27  4970.9  412.07  4979.5  415.69  4985.7  416.04  5029.9  416.55
  5037.3  413.21  5043.2  415.16  5052.9  412.80  5058.8  415.37  5064.8  412.00
  5074.3  413.95  5080.2  416.35  5111.3  416.89  5123.1  412.83  5132.7  415.79
  5136.9  414.29  5138.5  413.72  5146.3  416.80  5227.8  415.76  5308.7  418.77
#Mann=5,-1,0
  4880.4    0.16       0  4897.0    0.12       0  4933.3    0.07       0
  4937.3    0.12       0  5136.9    0.05       0
Bank Sta=4933.3,4937.3
Exp/Cntr=0.3,0.1

Type RM Length L Ch R = 1,5239,181,181,181
BEGIN DESCRIPTION:
Mill Creek Trib D5239.3
END DESCRIPTION:
XS GIS Cut Line= 3
      2750417.26      6818018.82      2750543.96      6818191.62
      2750735.99      6818459.53
#Sta/Elev= 30
  4784.8  421.69  4787.8  421.69  4827.9  417.58  4842.6  417.05  4849.5  416.18
  4871.9  416.02  4878.1  414.95  4886.6  415.57  4892.8  413.77  4899.1  415.05
  4907.4  414.94  4913.6  413.62  4920.1  410.20  4920.3  409.70  4923.8  409.70
  4924.1  410.20  4928.3  414.98  4936.3  415.41  4957.6  415.12  5001.8  415.31
  5014.0  415.73  5043.4  414.83  5069.0  414.73  5079.1  414.39  5144.1  414.69
  5185.9  415.48  5244.4  417.82  5251.0  418.44  5322.2  421.37  5328.7  421.97
#Mann=5,-1,0
  4784.8    0.16       0  4787.8    0.12       0  4920.1    0.07       0
  4924.1    0.12       0  5069.0    0.05       0
Bank Sta=4920.1,4924.1
Exp/Cntr=0.3,0.1

Type RM Length L Ch R = 1,5058,334,334,334
BEGIN DESCRIPTION:
Mill Creek Trib D5057.52
END DESCRIPTION:
XS GIS Cut Line= 3
      2750310.84      6818104.61      2750475.47      6818349.30
      2750676.80      6818534.24
#Sta/Elev= 30
  4706.8  417.83  4722.8  416.69  4794.8  414.54  4830.7  415.15  4895.3  414.56
  4902.7  414.01  4931.5  414.63  4938.7  413.89  4944.8  408.21  4953.7  408.46
  4957.7  407.91  4958.0  407.41  4961.5  407.41  4961.7  407.91  4974.7  410.94
  4989.7  408.40  4995.7  409.52  4999.7  408.43  5005.5  408.43  5010.4  410.25
  5017.2  410.21  5024.6  413.86  5038.8  416.60  5107.1  418.94  5187.4  420.72
  5194.2  420.36  5201.6  420.96  5208.3  420.30  5236.7  420.19  5275.1  420.74
#Mann=4,-1,0
  4706.8    0.12       0  4957.7    0.07       0  4961.7    0.12       0
  5107.1    0.05       0
Bank Sta=4957.7,4961.7
Exp/Cntr=0.3,0.1

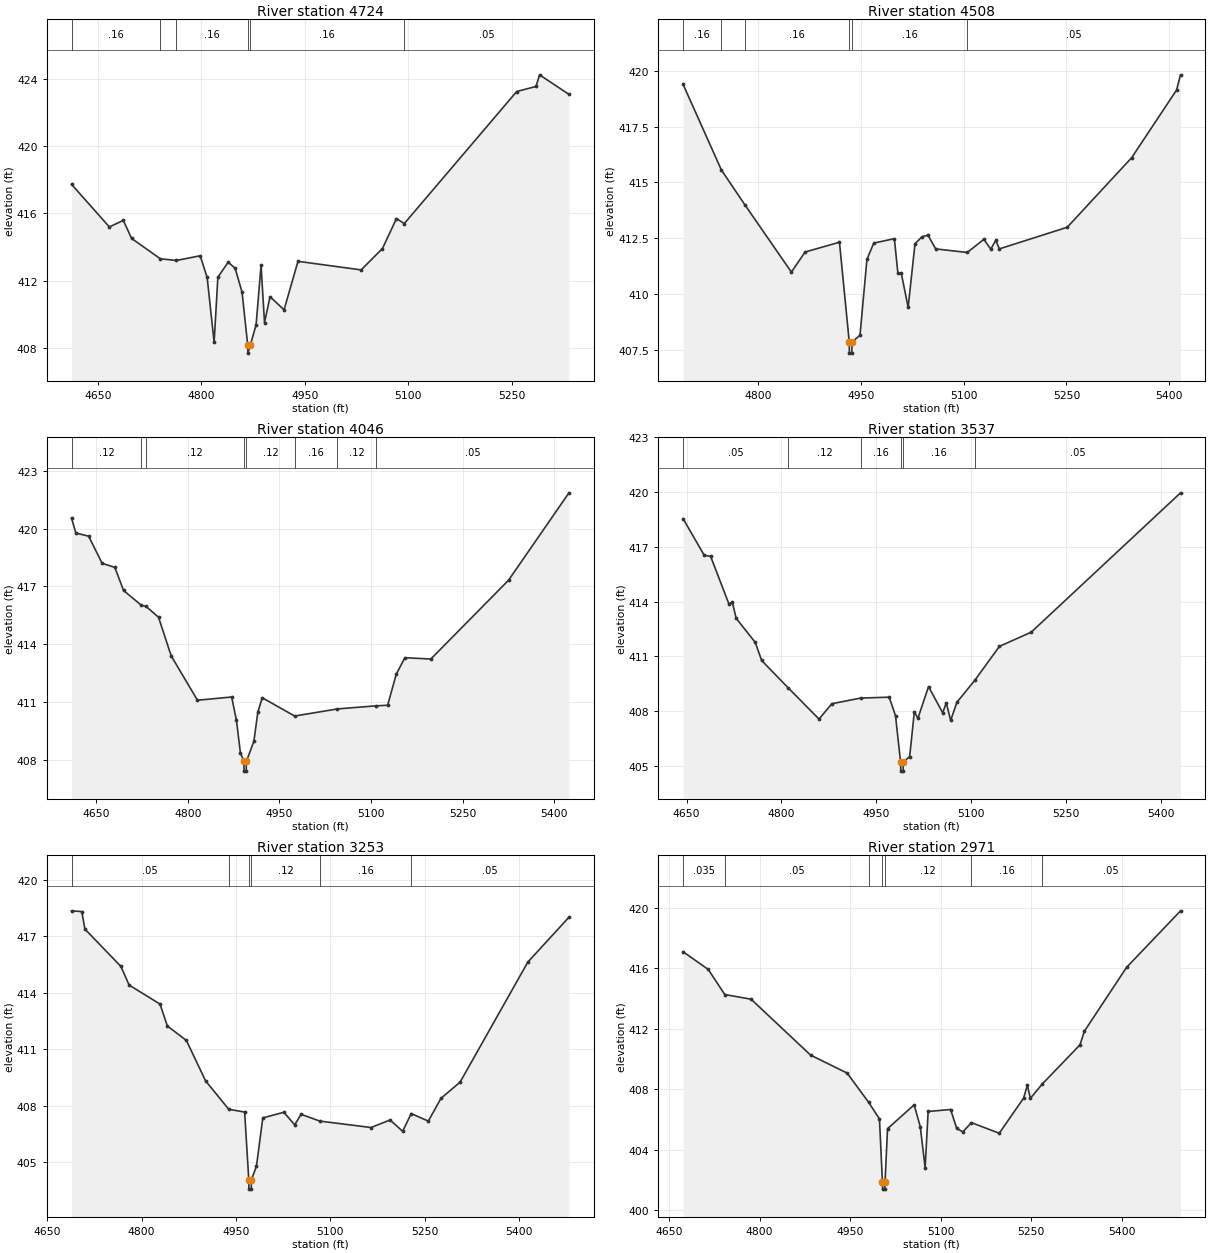
Type RM Length L Ch R = 1,4724,216,216,216
BEGIN DESCRIPTION:
Mill Creek Trib D4724.21
END DESCRIPTION:
XS GIS Cut Line= 3
      2750227.98      6818126.89      2750287.89      6818507.57
      2750360.85      6818834.87
#Sta/Elev= 30
  4612.1  417.73  4666.9  415.20  4687.1  415.59  4699.1  414.52  4740.8  413.31
  4764.1  413.21  4798.5  413.49  4808.6  412.20  4818.7  408.35  4824.1  412.21
  4839.0  413.11  4849.1  412.75  4859.2  411.32  4867.3  408.21  4867.6  407.71
  4871.3  408.21  4879.5  409.39  4886.7  412.92  4891.7  409.52  4899.7  411.06
  4920.0  410.28  4940.2  413.16  5031.7  412.65  5062.6  413.92  5082.9  415.70
  5094.2  415.40  5257.1  423.24  5285.1  423.54  5290.2  424.23  5332.8  423.07
#Mann=6,-1,0
  4612.1    0.16       0  4740.8    0.12       0  4764.1    0.16       0
  4867.3    0.07       0  4871.3    0.16       0  5094.2    0.05       0
Bank Sta=4867.3,4871.3
Exp/Cntr=0.3,0.1

Type RM Length L Ch R = 1,4508,462,462,462
BEGIN DESCRIPTION:
Mill Creek Trib D4508.04
END DESCRIPTION:
XS GIS Cut Line= 3
      2750129.58      6818183.40      2750105.87      6818496.25
      2750063.69      6818906.74
#Sta/Elev= 30
  4690.2  419.39  4746.0  415.56  4780.5  413.99  4848.3  410.98  4868.3  411.88
  4918.5  412.32  4932.8  407.85  4933.0  407.35  4936.5  407.35  4936.8  407.85
  4948.5  408.15  4958.6  411.55  4968.6  412.28  4998.7  412.48  5003.8  410.93
  5008.8  410.93  5018.8  409.40  5028.8  412.25  5038.9  412.56  5047.7  412.64
  5059.0  412.02  5105.2  411.86  5129.4  412.45  5139.4  412.01  5146.9  412.41
  5151.9  412.02  5251.1  412.99  5345.3  416.11  5410.8  419.14  5416.6  419.82
#Mann=6,-1,0
  4690.2    0.16       0  4746.0    0.12       0  4780.5    0.16       0
  4932.8    0.07       0  4936.8    0.16       0  5105.2    0.05       0
Bank Sta=4932.8,4936.8
Exp/Cntr=0.3,0.1

Type RM Length L Ch R = 1,4046,509,509,509
BEGIN DESCRIPTION:
Mill Creek Trib D4045.846
END DESCRIPTION:
XS GIS Cut Line= 3
      2750025.98      6818211.02      2749776.00      6818511.00
      2749475.97      6818811.03
#Sta/Elev= 30
  4609.5  420.55  4616.6  419.77  4637.5  419.61  4659.6  418.20  4680.4  417.99
  4694.7  416.79  4723.9  416.02  4731.7  415.96  4752.0  415.40  4772.8  413.39
  4815.8  411.09  4871.8  411.26  4879.6  410.05  4886.1  408.37  4891.9  407.91
  4892.1  407.41  4895.6  407.41  4895.9  407.91  4908.2  408.96  4914.7  410.48
  4921.9  411.22  4975.0  410.27  5045.1  410.64  5108.2  410.80  5127.3  410.83
  5141.4  412.44  5155.6  413.30  5198.0  413.23  5325.3  417.32  5424.3  421.86
#Mann=8,-1,0
  4609.5    0.12       0  4723.9    0.16       0  4731.7    0.12       0
  4891.9    0.07       0  4895.9    0.12       0  4975.0    0.16       0
  5045.1    0.12       0  5108.2    0.05       0
Bank Sta=4891.9,4895.9
Exp/Cntr=0.3,0.1

Type RM Length L Ch R = 1,3537,284,284,284
BEGIN DESCRIPTION:
Mill Creek Trib D3536.72
END DESCRIPTION:
XS GIS Cut Line= 3
      2749340.93      6818007.87      2749387.59      6818359.69
      2749195.56      6818746.66
#Sta/Elev= 30
  4644.4  418.54  4677.8  416.54  4687.9  416.48  4717.1  413.85  4722.1  413.99
  4728.3  413.09  4758.5  411.77  4768.6  410.78  4810.6  409.28  4859.4  407.57
  4879.6  408.41  4925.1  408.72  4970.4  408.77  4980.4  407.75  4988.4  405.22
  4988.7  404.72  4992.4  404.72  4992.6  405.22  5002.8  405.52  5010.2  407.98
  5015.8  407.61  5032.6  409.35  5055.1  407.91  5060.6  408.46  5067.7  407.50
  5077.5  408.49  5106.0  409.70  5144.7  411.55  5195.1  412.33  5431.3  419.96
#Mann=6,-1,0
  4644.4    0.05       0  4810.6    0.12       0  4925.1    0.16       0
  4988.4    0.07       0  4992.6    0.16       0  5106.0    0.05       0
Bank Sta=4988.4,4992.6
Exp/Cntr=0.3,0.1

Type RM Length L Ch R = 1,3253,282,282,282
BEGIN DESCRIPTION:
Mill Creek Trib D3253.39
END DESCRIPTION:
XS GIS Cut Line= 3
      2749213.65      6817890.53      2749164.27      6818201.05
      2749091.19      6818672.09
#Sta/Elev= 30
  4688.5  418.35  4704.8  418.31  4709.8  417.38  4767.0  415.40  4780.1  414.41
  4829.2  413.40  4840.9  412.24  4871.2  411.47  4901.6  409.33  4938.5  407.82
  4963.8  407.67  4970.4  404.08  4970.6  403.58  4974.3  403.58  4974.6  404.08
  4982.6  404.80  4992.7  407.36  5026.2  407.66  5043.4  406.99  5053.5  407.55
  5083.5  407.19  5164.8  406.85  5195.1  407.25  5215.1  406.65  5228.7  407.59
  5255.9  407.19  5276.1  408.40  5306.5  409.26  5414.2  415.63  5479.6  418.01
#Mann=6,-1,0
  4688.5    0.05       0  4938.5    0.12       0  4970.4    0.07       0
  4974.6    0.12       0  5083.5    0.16       0  5228.7    0.05       0
Bank Sta=4970.4,4974.6
Exp/Cntr=0.3,0.1

Type RM Length L Ch R = 1,2971,275,275,275
BEGIN DESCRIPTION:
Mill Creek Trib D2970.55
END DESCRIPTION:
XS GIS Cut Line= 3
      2748986.44      6817801.87      2748938.65      6818138.47
      2748880.87      6818619.24
#Sta/Elev= 30
  4673.3  417.09  4714.9  415.92  4742.3  414.26  4785.9  413.95  4884.5  410.25
  4945.1  409.06  4980.6  407.13  4998.6  406.03  5003.5  401.88  5003.8  401.38
  5007.6  401.38  5007.9  401.88  5012.0  405.38  5056.1  406.96  5066.2  405.52
  5074.3  402.80  5079.3  406.52  5116.5  406.65  5126.6  405.40  5136.7  405.17
  5151.0  405.78  5197.1  405.08  5237.4  407.40  5243.7  408.26  5248.7  407.39
  5268.0  408.32  5330.9  410.93  5338.1  411.83  5408.1  416.06  5497.5  419.80
#Mann=7,-1,0
  4673.3   0.035       0  4742.3    0.05       0  4980.6    0.12       0
  5003.5    0.07       0  5007.9    0.12       0  5151.0    0.16       0
  5268.0    0.05       0
Bank Sta=5003.5,5007.9
Exp/Cntr=0.3,0.1