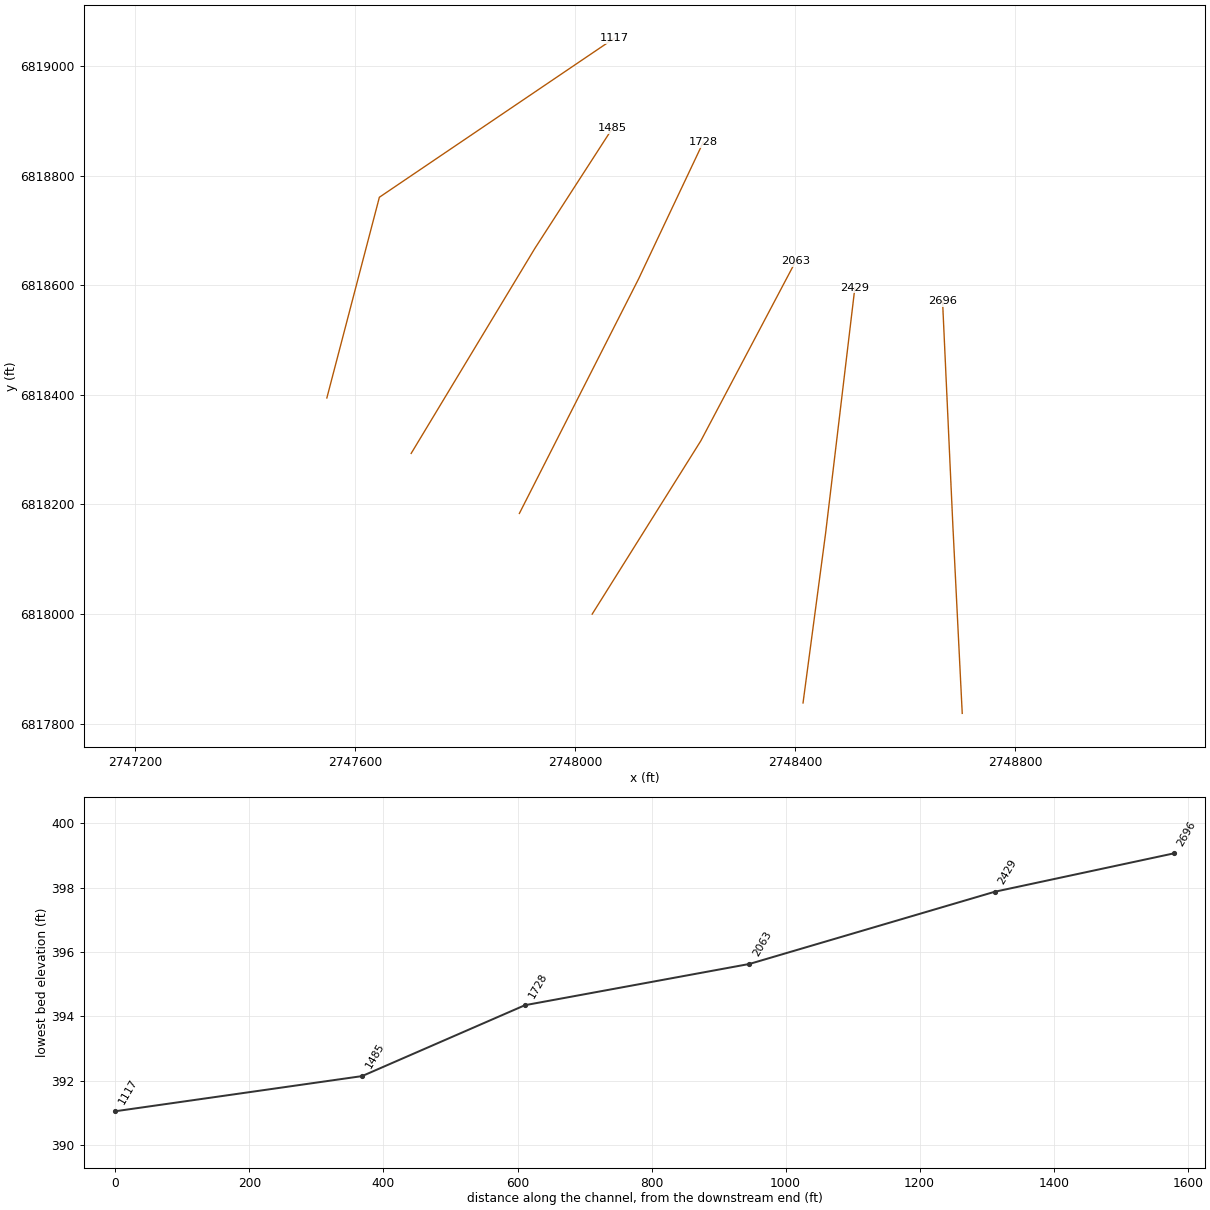
HEC-RAS study Mill Creek Trib D.prj: Mill Creek Trib D Base Level Engineering

--- Mill Creek Trib D.g01 (geometry) --- (continued)

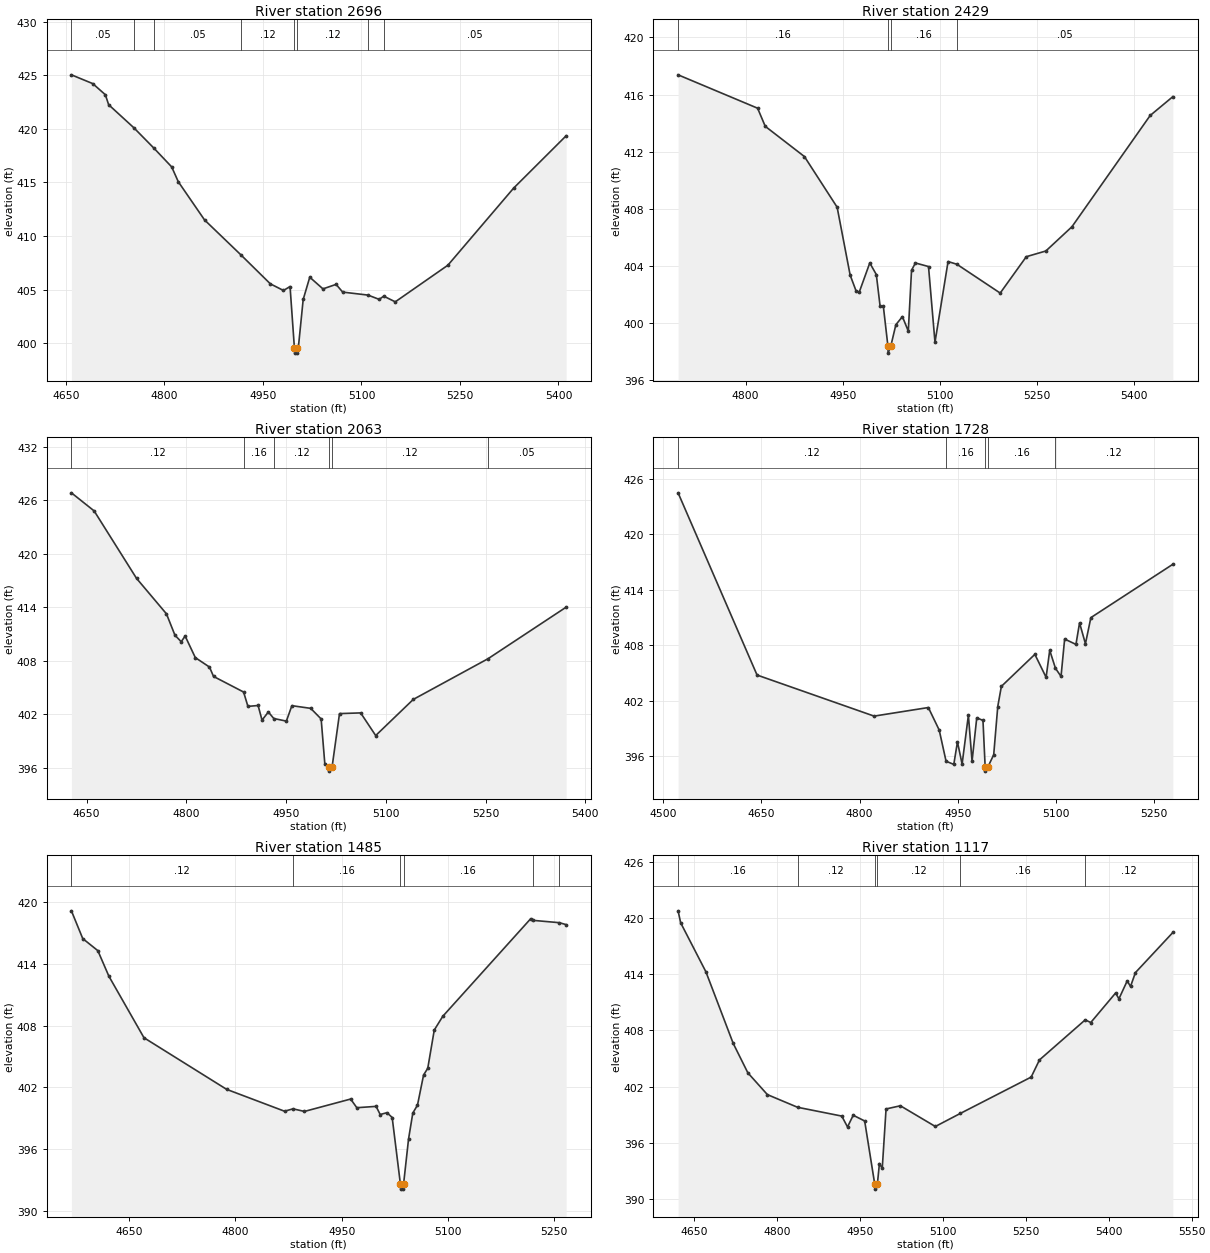
Type RM Length L Ch R = 1,2696,267,267,267
BEGIN DESCRIPTION:
Mill Creek Trib D2696.42
END DESCRIPTION:
XS GIS Cut Line= 3
      2748703.77      6817818.51      2748686.65      6818163.58
      2748668.03      6818570.96
#Sta/Elev= 30
  4658.4  425.05  4690.9  424.23  4710.1  423.19  4715.1  422.26  4753.4  420.11
  4784.2  418.19  4811.1  416.45  4821.1  415.07  4861.1  411.50  4916.4  408.24
  4961.3  405.53  4981.3  404.91  4991.3  405.28  4997.9  399.56  4998.2  399.06
  5002.0  399.06  5002.3  399.56  5003.9  399.56  5011.3  404.07  5021.3  406.15
  5041.4  405.06  5061.4  405.48  5071.4  404.76  5110.0  404.48  5127.0  404.08
  5133.9  404.38  5151.5  403.85  5231.6  407.27  5331.7  414.47  5411.7  419.36
#Mann=8,-1,0
  4658.4    0.05       0  4753.4   0.035       0  4784.2    0.05       0
  4916.4    0.12       0  4997.9    0.07       0  5002.3    0.12       0
  5110.0    0.16       0  5133.9    0.05       0
Bank Sta=4997.9,5002.3
Exp/Cntr=0.3,0.1

Type RM Length L Ch R = 1,2429,366,366,366
BEGIN DESCRIPTION:
Mill Creek Trib D2429.11
END DESCRIPTION:
XS GIS Cut Line= 3
      2748414.44      6817837.56      2748455.49      6818147.63
      2748508.66      6818595.71
#Sta/Elev= 30
  4695.7  417.38  4818.5  415.04  4830.3  413.77  4890.8  411.65  4941.3  408.10
  4961.4  403.34  4970.4  402.25  4975.4  402.14  4991.7  404.19  5001.8  403.38
  5007.7  401.14  5012.7  401.14  5019.7  398.37  5020.0  397.87  5024.2  398.37
  5032.0  399.86  5042.1  400.43  5051.2  399.41  5056.2  403.68  5062.2  404.19
  5082.4  403.94  5092.4  398.63  5112.6  404.29  5126.2  404.10  5193.1  402.08
  5233.4  404.63  5263.6  405.03  5303.9  406.73  5424.7  414.53  5459.7  415.85
#Mann=4,-1,0
  4695.7    0.16       0  5019.7    0.07       0  5024.2    0.16       0
  5126.2    0.05       0
Bank Sta=5019.7,5024.2
Exp/Cntr=0.3,0.1

Type RM Length L Ch R = 1,2063,335,335,335
BEGIN DESCRIPTION:
Mill Creek Trib D2062.95
END DESCRIPTION:
XS GIS Cut Line= 3
      2748031.22      6817999.73      2748228.71      6818316.23
      2748401.29      6818644.46
#Sta/Elev= 30
  4627.2  426.84  4661.4  424.81  4725.1  417.25  4770.1  413.27  4782.9  410.87
  4792.3  410.14  4798.2  410.78  4813.5  408.36  4834.8  407.30  4840.9  406.25
  4886.1  404.50  4892.6  402.89  4907.9  402.99  4913.8  401.35  4923.3  402.26
  4931.5  401.53  4950.4  401.24  4958.7  402.97  4987.0  402.67  5002.7  401.48
  5008.2  396.47  5014.7  396.13  5015.0  395.63  5019.2  396.13  5030.3  402.08
  5062.1  402.16  5084.7  399.62  5141.2  403.67  5253.7  408.24  5371.1  414.02
#Mann=6,-1,0
  4627.2    0.12       0  4886.1    0.16       0  4931.5    0.12       0
  5014.7    0.07       0  5019.2    0.12       0  5253.7    0.05       0
Bank Sta=5014.7,5019.2
Exp/Cntr=0.3,0.1

Type RM Length L Ch R = 1,1728,243,243,243
BEGIN DESCRIPTION:
Mill Creek Trib D1727.75
END DESCRIPTION:
XS GIS Cut Line= 3
      2747898.92      6818183.62      2748115.75      6818612.25
      2748233.23      6818861.83
#Sta/Elev= 30
  4522.6  424.50  4643.3  404.76  4822.2  400.31  4905.1  401.24  4921.7  398.80
  4932.2  395.42  4944.0  395.08  4949.6  397.52  4956.7  395.11  4966.3  400.41
  4971.9  395.42  4979.1  400.13  4988.6  399.84  4991.9  394.85  4992.2  394.35
  4996.4  394.85  5005.0  396.12  5011.2  401.35  5016.7  403.53  5067.9  407.00
  5085.1  404.51  5090.6  407.44  5099.4  405.49  5107.9  404.61  5113.4  408.66
  5130.7  408.08  5136.2  410.41  5145.2  408.15  5153.5  410.98  5278.8  416.76
#Mann=5,-1,0
  4522.6    0.12       0  4932.2    0.16       0  4991.9    0.07       0
  4996.4    0.16       0  5099.4    0.12       0
Bank Sta=4991.9,4996.4
Exp/Cntr=0.3,0.1

Type RM Length L Ch R = 1,1485,368,368,368
BEGIN DESCRIPTION:
Mill Creek Trib D1484.77
END DESCRIPTION:
XS GIS Cut Line= 3
      2747702.25      6818293.21      2747926.98      6818667.46
      2748068.38      6818887.51
#Sta/Elev= 30
  4568.6  419.12  4584.6  416.43  4605.9  415.26  4621.5  412.78  4671.0  406.82
  4787.6  401.82  4869.3  399.70  4881.3  399.93  4897.4  399.68  4962.6  400.88
  4971.3  400.04  4998.5  400.17  5004.3  399.38  5013.9  399.56  5021.2  399.09
  5032.8  392.65  5033.1  392.15  5037.0  392.15  5037.3  392.65  5044.3  397.01
  5050.3  399.52  5056.9  400.29  5065.5  403.21  5071.4  403.86  5080.6  407.57
  5092.6  408.90  5216.7  418.36  5219.4  418.20  5257.1  417.97  5266.7  417.78
#Mann=6,-1,0
  4568.6    0.12       0  4881.3    0.16       0  5032.8    0.07       0
  5037.3    0.16       0  5219.4    0.12       0  5257.1    0.16       0
Bank Sta=5032.8,5037.3
Exp/Cntr=0.3,0.1

Type RM Length L Ch R = 1,1117,0,0,0
BEGIN DESCRIPTION:
Mill Creek Trib D1116.617
END DESCRIPTION:
XS GIS Cut Line= 3
      2747549.03      6818394.52      2747644.48      6818761.00
      2748071.14      6819051.20
#Sta/Elev= 30
  4621.3  420.74  4626.0  419.46  4671.6  414.24  4721.0  406.60  4747.5  403.46
  4782.8  401.14  4837.3  399.79  4917.3  398.85  4927.7  397.69  4938.0  398.94
  4958.7  398.33  4977.0  391.56  4977.4  391.06  4981.6  391.56  4985.4  393.79
  4990.5  393.27  4997.4  399.61  5023.3  399.95  5086.5  397.74  5131.6  399.13
  5259.8  403.01  5274.8  404.84  5357.5  409.11  5367.6  408.83  5412.4  411.97
  5418.5  411.36  5433.4  413.26  5439.5  412.68  5448.3  414.15  5516.0  418.43
#Mann=6,-1,0
  4621.3    0.16       0  4837.3    0.12       0  4977.0    0.07       0
  4981.6    0.12       0  5131.6    0.16       0  5357.5    0.12       0
Bank Sta=4977,4981.6
Exp/Cntr=0.3,0.1

Chan Stop Cuts=-1