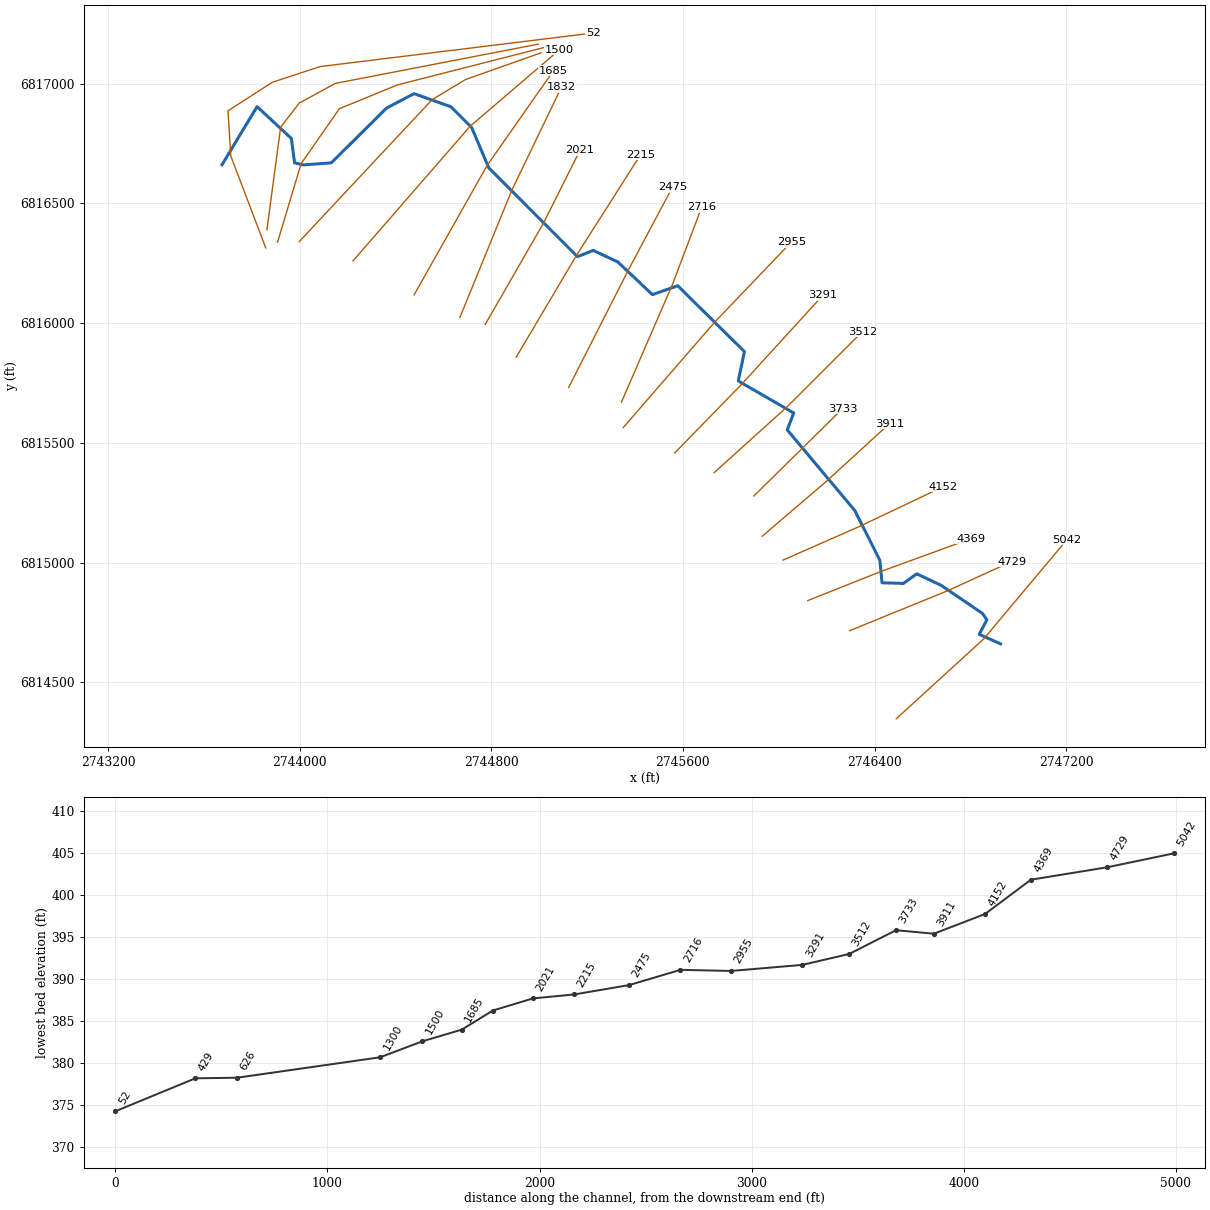
--- Mill Creek Trib E.prj (project) ---

Proj Title=Mill Creek Trib E Base Level Engineering
Current Plan=p01
Default Exp/Contr=0.3,0.1
English Units
Geom File=g01
Flow File=f01
Plan File=p01
BEGIN DESCRIPTION:
Mill Creek Trib E
END DESCRIPTION:

--- Mill Creek Trib E.p01 (plan) ---

Plan Title=Multiple Run
Short Identifier=Multiple
Geom File=g01
Flow File=f01
Subcritical Flow
K Sum by GR= 0
Std Step Tol= 0.01
Critical Tol= 0.01
Num of Std Step Trials= 20
Max Error Tol= 0.3
Flow Tol Ratio= 0.001
Split Flow NTrial= 30
Split Flow Tol= 0.02
Split Flow Ratio= 0.02
Log Output Level= 0
Friction Slope Method= 1
Unsteady Friction Slope Method= 2
Unsteady Bridges Friction Slope Method= 1
Parabolic Critical Depth
Global Vel Dist=  1 , 1 , 1
Global Log Level= 0
CheckData=True
Encroach Param= -1, 0, 0, 0
BEGIN DESCRIPTION:
Multiple Run
END DESCRIPTION:

--- Mill Creek Trib E.f01 (steady flow) ---

Flow Title=Multiple
Number of Profiles=7
Profile Names=10-year,25-year,50-year,1pct_min,100-year,1pct_plu,500-year
River Rch & RM= Mill Creek Trib ,Reach-1,5042
     466     618     740     441     880    1756    1245
Boundary for River Rch & Prof#=Mill Creek Trib ,Reach-1,1
Up Type=0
Dn Type=3
Dn Slope=0.005
Boundary for River Rch & Prof#=Mill Creek Trib ,Reach-1,2
Up Type=0
Dn Type=3
Dn Slope=0.005
Boundary for River Rch & Prof#=Mill Creek Trib ,Reach-1,3
Up Type=0
Dn Type=3
Dn Slope=0.005
Boundary for River Rch & Prof#=Mill Creek Trib ,Reach-1,4
Up Type=0
Dn Type=3
Dn Slope=0.005
Boundary for River Rch & Prof#=Mill Creek Trib ,Reach-1,5
Up Type=0
Dn Type=3
Dn Slope=0.005
Boundary for River Rch & Prof#=Mill Creek Trib ,Reach-1,6
Up Type=0
Dn Type=3
Dn Slope=0.005
Boundary for River Rch & Prof#=Mill Creek Trib ,Reach-1,7
Up Type=0
Dn Type=3
Dn Slope=0.005

--- Mill Creek Trib E.g01 (geometry) ---

Geom Title=Existing Conditions

River Reach=Mill Creek Trib ,Reach-1
Reach XY= 30
      2746926.00      6814661.00      2746836.87      6814700.76
      2746868.55      6814761.21      2746850.36      6814787.98
      2746678.28      6814905.18      2746576.01      6814953.47
      2746520.42      6814913.44      2746431.11      6814915.96
      2746422.14      6815009.33      2746317.86      6815217.06
      2746035.32      6815554.35      2746062.50      6815624.69
      2745831.01      6815758.46      2745856.70      6815881.03
      2745578.29      6816155.88      2745472.59      6816118.82
      2745328.29      6816255.19      2745225.91      6816303.22
      2745159.33      6816277.39      2744789.62      6816647.79
      2744717.87      6816817.07      2744632.07      6816902.87
      2744477.72      6816957.66      2744362.79      6816897.38
      2744132.19      6816668.80      2744015.33      6816660.25
      2743979.01      6816668.94      2743965.46      6816770.74
      2743822.42      6816903.52      2743676.00      6816661.00

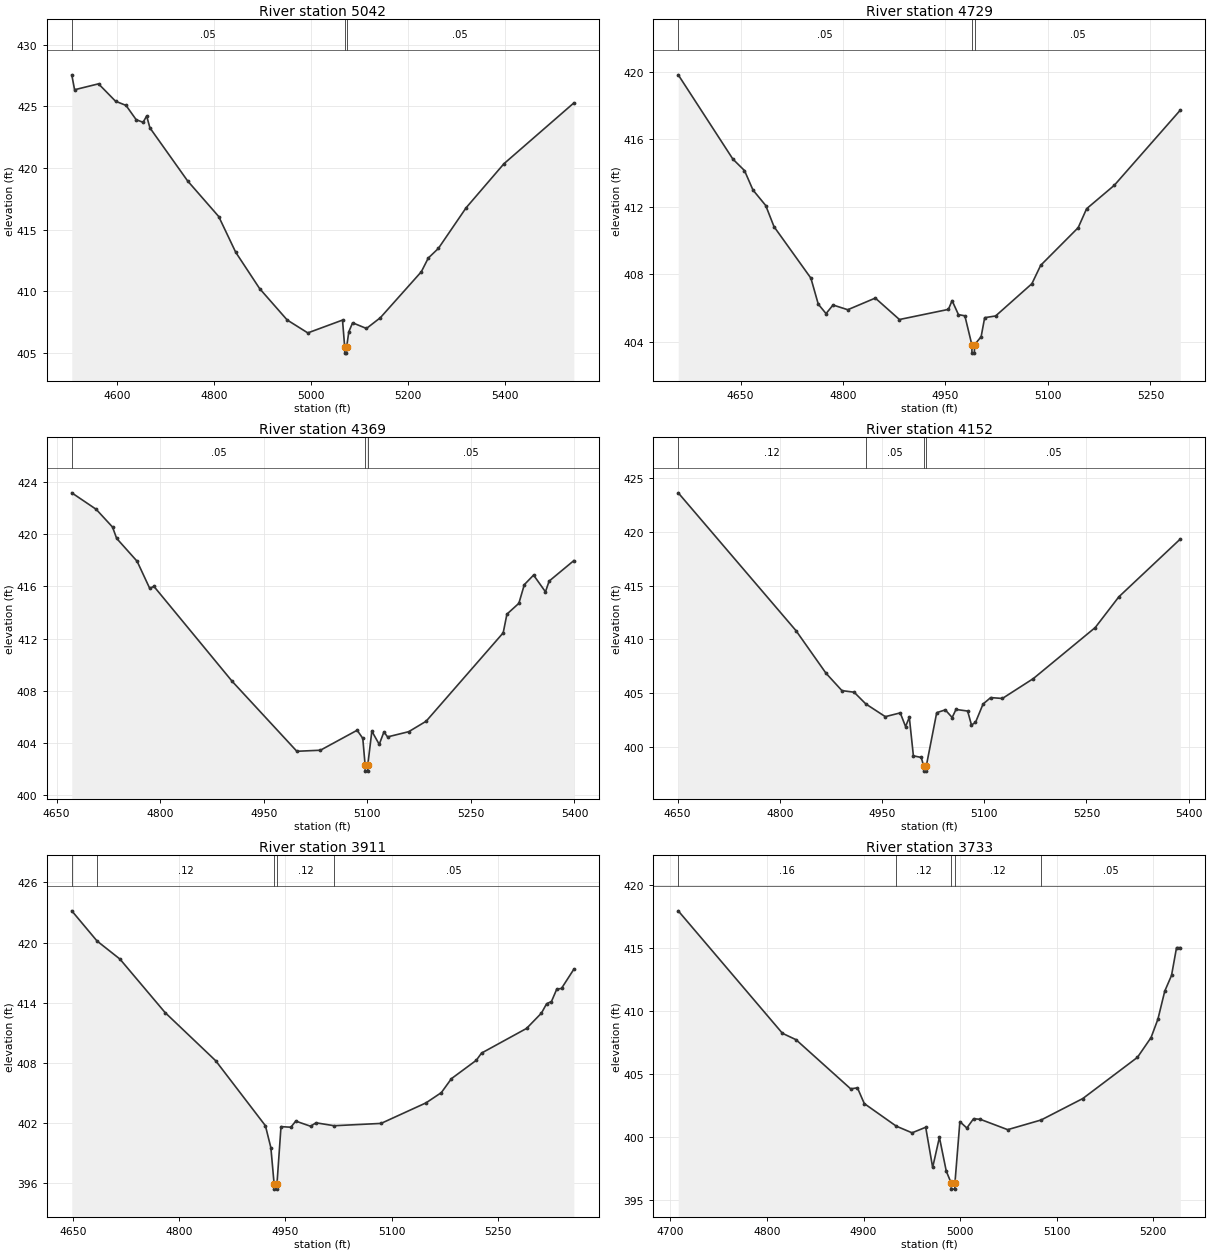
Type RM Length L Ch R = 1,5042,313,313,313
BEGIN DESCRIPTION:
Mill Creek Trib E5042.325
END DESCRIPTION:
XS GIS Cut Line= 3
      2746490.61      6814348.49      2746854.66      6814680.78
      2747203.53      6815096.61
#Sta/Elev= 30
  4507.1  427.56  4512.9  426.35  4562.3  426.83  4597.4  425.42  4619.0  425.08
  4640.0  423.92  4654.2  423.71  4661.6  424.22  4668.3  423.26  4746.0  418.96
  4810.2  416.07  4845.3  413.17  4894.7  410.22  4951.4  407.68  4994.0  406.63
  5065.6  407.67  5070.1  405.49  5070.3  404.99  5073.8  404.99  5074.1  405.49
  5078.6  406.72  5086.4  407.45  5115.0  406.99  5143.6  407.86  5228.2  411.59
  5242.5  412.70  5263.3  413.48  5320.6  416.78  5398.6  420.35  5542.8  425.28
#Mann=3,-1,0
  4507.1    0.05       0  5070.1    0.05       0  5074.1    0.05       0
Bank Sta=5070.1,5074.1
Exp/Cntr=0.3,0.1

Type RM Length L Ch R = 1,4729,360,360,360
BEGIN DESCRIPTION:
Mill Creek Trib E4729.14
END DESCRIPTION:
XS GIS Cut Line= 3
      2746296.17      6814716.11      2746702.40      6814881.71
      2746971.99      6815004.68
#Sta/Elev= 30
  4558.8  419.82  4638.8  414.83  4655.8  414.15  4668.2  413.00  4686.9  412.08
  4699.0  410.83  4753.0  407.78  4763.8  406.24  4775.2  405.68  4785.4  406.19
  4807.0  405.91  4847.3  406.60  4882.6  405.33  4954.3  405.93  4959.7  406.45
  4969.0  405.62  4978.4  405.55  4988.6  403.84  4988.8  403.34  4992.3  403.34
  4992.6  403.84  5002.2  404.31  5007.4  405.44  5023.4  405.54  5076.5  407.45
  5089.4  408.54  5144.3  410.77  5156.6  411.89  5197.2  413.28  5293.8  417.73
#Mann=3,-1,0
  4558.8    0.05       0  4988.6    0.05       0  4992.6    0.05       0
Bank Sta=4988.6,4992.6
Exp/Cntr=0.3,0.1

Type RM Length L Ch R = 1,4369,217,217,217
BEGIN DESCRIPTION:
Mill Creek Trib E4369.23
END DESCRIPTION:
XS GIS Cut Line= 3
      2746121.14      6814841.80      2746426.97      6814963.43
      2746800.78      6815099.67
#Sta/Elev= 30
  4672.1  423.17  4707.4  421.91  4731.1  420.55  4737.1  419.68  4766.7  417.93
  4785.0  415.85  4791.0  416.01  4904.3  408.74  4998.0  403.38  5032.1  403.46
  5085.3  404.99  5093.5  404.37  5096.8  402.36  5097.1  401.86  5100.6  401.86
  5100.8  402.36  5106.6  404.92  5117.3  403.91  5124.1  404.86  5129.4  404.48
  5160.0  404.88  5185.2  405.68  5296.8  412.45  5302.2  413.88  5319.5  414.71
  5327.4  416.14  5340.8  416.87  5358.0  415.59  5363.3  416.41  5399.1  417.98
#Mann=3,-1,0
  4672.1    0.05       0  5096.8    0.05       0  5100.8    0.05       0
Bank Sta=5096.8,5100.8
Exp/Cntr=0.3,0.1

Type RM Length L Ch R = 1,4152,241,241,241
BEGIN DESCRIPTION:
Mill Creek Trib E4152.09
END DESCRIPTION:
XS GIS Cut Line= 3
      2746017.79      6815010.75      2746336.46      6815150.89
      2746687.50      6815317.76
#Sta/Elev= 30
  4651.0  423.62  4823.8  410.82  4867.9  406.86  4891.2  405.25  4909.1  405.10
  4926.3  404.01  4954.9  402.83  4976.8  403.18  4984.6  401.91  4990.1  402.77
  4996.1  399.19  5007.6  399.04  5011.1  398.27  5011.4  397.77  5014.9  397.77
  5015.1  398.27  5030.3  403.20  5042.9  403.46  5053.0  402.75  5058.6  403.50
  5075.7  403.35  5081.3  402.06  5087.2  402.29  5098.3  404.00  5109.5  404.60
  5126.7  404.52  5172.2  406.37  5263.0  411.11  5297.6  413.96  5387.8  419.33
#Mann=4,-1,0
  4651.0    0.12       0  4926.3    0.05       0  5011.1    0.05       0
  5015.1    0.05       0
Bank Sta=5011.1,5015.1
Exp/Cntr=0.3,0.1

Type RM Length L Ch R = 1,3911,178,178,178
BEGIN DESCRIPTION:
Mill Creek Trib E3911.42
END DESCRIPTION:
XS GIS Cut Line= 3
      2745930.91      6815110.40      2746196.77      6815337.61
      2746461.60      6815579.81
#Sta/Elev= 30
  4648.5  423.17  4684.2  420.16  4716.5  418.36  4780.2  413.03  4851.6  408.23
  4921.8  401.75  4929.5  399.56  4934.1  395.93  4934.3  395.43  4937.8  395.43
  4938.1  395.93  4943.8  401.66  4957.7  401.60  4964.6  402.21  4985.5  401.70
  4993.2  402.04  5018.8  401.75  5085.0  401.98  5148.5  404.03  5170.1  405.05
  5184.3  406.44  5219.4  408.27  5226.8  408.99  5290.4  411.45  5311.3  412.97
  5318.7  413.91  5325.5  414.13  5332.9  415.35  5339.7  415.44  5357.1  417.35
#Mann=5,-1,0
  4648.5    0.16       0  4684.2    0.12       0  4934.1    0.07       0
  4938.1    0.12       0  5018.8    0.05       0
Bank Sta=4934.1,4938.1
Exp/Cntr=0.3,0.1

Type RM Length L Ch R = 1,3733,221,221,221
BEGIN DESCRIPTION:
Mill Creek Trib E3733.12
END DESCRIPTION:
XS GIS Cut Line= 3
      2745896.04      6815278.43      2746107.20      6815486.13
      2746266.63      6815643.21
#Sta/Elev= 30
  4708.1  417.94  4816.0  408.22  4830.1  407.71  4886.7  403.81  4893.7  403.89
  4900.8  402.64  4933.9  400.85  4950.3  400.32  4964.4  400.76  4971.6  397.57
  4978.6  399.96  4985.7  397.28  4990.7  396.35  4991.0  395.85  4994.5  395.85
  4994.7  396.35  4999.8  401.21  5007.0  400.70  5014.0  401.44  5021.0  401.39
  5049.3  400.57  5084.0  401.34  5127.1  403.04  5183.7  406.31  5197.8  407.88
  5204.9  409.34  5212.0  411.57  5219.0  412.81  5224.2  415.02  5228.1  415.02
#Mann=5,-1,0
  4708.1    0.16       0  4933.9    0.12       0  4990.7    0.07       0
  4994.7    0.12       0  5084.0    0.05       0
Bank Sta=4990.7,4994.7
Exp/Cntr=0.3,0.1

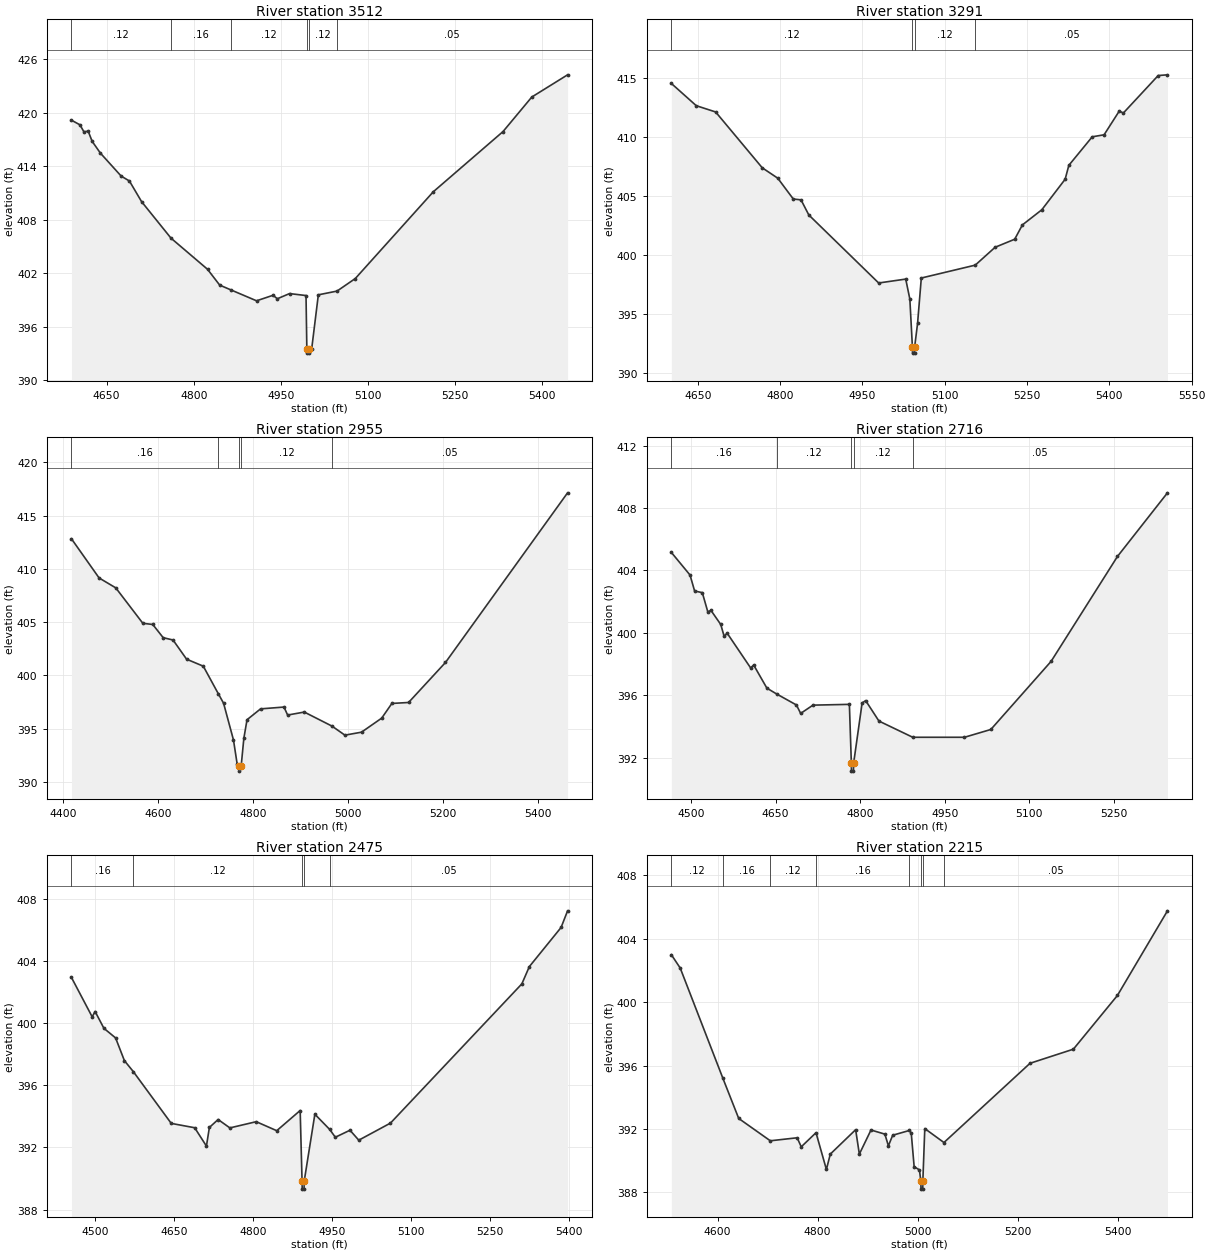
Type RM Length L Ch R = 1,3512,221,221,221
BEGIN DESCRIPTION:
Mill Creek Trib E3511.7
END DESCRIPTION:
XS GIS Cut Line= 3
      2745730.55      6815375.82      2746034.89      6815650.65
      2746349.34      6815964.72
#Sta/Elev= 30
  4589.4  419.15  4604.0  418.63  4610.8  417.85  4618.2  417.92  4625.0  416.78
  4639.2  415.46  4675.0  412.88  4689.2  412.33  4710.2  410.01  4760.8  405.92
  4823.7  402.43  4844.7  400.65  4864.5  400.10  4908.2  398.89  4936.6  399.51
  4944.0  399.12  4965.0  399.70  4993.4  399.48  4994.8  393.52  4995.1  393.02
  4998.6  393.02  4998.8  393.52  5003.2  393.52  5014.6  399.56  5046.8  399.98
  5078.3  401.39  5212.6  411.12  5332.8  417.88  5382.3  421.75  5443.9  424.24
#Mann=6,-1,0
  4589.4    0.12       0  4760.8    0.16       0  4864.5    0.12       0
  4994.8    0.07       0  4998.8    0.12       0  5046.8    0.05       0
Bank Sta=4994.8,4998.8
Exp/Cntr=0.3,0.1

Type RM Length L Ch R = 1,3291,336,336,336
BEGIN DESCRIPTION:
Mill Creek Trib E3291.38
END DESCRIPTION:
XS GIS Cut Line= 3
      2745565.33      6815457.52      2745845.18      6815744.81
      2746184.38      6816116.28
#Sta/Elev= 30
  4601.8  414.52  4647.2  412.64  4682.5  412.11  4767.4  407.39  4795.7  406.51
  4824.0  404.75  4838.1  404.68  4852.3  403.40  4979.6  397.65  5028.9  397.98
  5036.4  396.29  5041.1  392.22  5041.4  391.72  5044.9  391.72  5045.1  392.22
  5050.5  394.24  5057.3  398.07  5155.6  399.16  5191.8  400.67  5227.5  401.35
  5241.5  402.56  5276.9  403.84  5319.4  406.42  5326.2  407.60  5368.8  410.01
  5390.4  410.18  5418.1  412.19  5425.5  412.02  5489.0  415.19  5505.9  415.25
#Mann=4,-1,0
  4601.8    0.12       0  5041.1    0.07       0  5045.1    0.12       0
  5155.6    0.05       0
Bank Sta=5041.1,5045.1
Exp/Cntr=0.3,0.1

Type RM Length L Ch R = 1,2955,239,239,239
BEGIN DESCRIPTION:
Mill Creek Trib E2955.26
END DESCRIPTION:
XS GIS Cut Line= 3
      2745351.07      6815564.10      2745733.10      6816004.50
      2746052.30      6816338.07
#Sta/Elev= 30
  4417.4  412.83  4475.6  409.15  4510.7  408.22  4567.7  404.89  4588.6  404.78
  4610.5  403.54  4631.3  403.32  4659.8  401.52  4695.0  400.86  4726.4  398.29
  4737.7  397.38  4758.6  393.92  4766.2  391.70  4770.8  391.50  4771.1  391.00
  4774.8  391.50  4780.4  394.08  4787.1  395.83  4815.6  396.85  4864.9  397.02
  4872.6  396.27  4907.7  396.55  4966.0  395.23  4993.2  394.38  5028.2  394.66
  5070.7  395.98  5092.1  397.36  5127.3  397.45  5205.0  401.21  5462.1  417.15
#Mann=5,-1,0
  4417.4    0.16       0  4726.4    0.12       0  4770.8    0.05       0
  4774.8    0.12       0  4966.0    0.05       0
Bank Sta=4770.8,4774.8
Exp/Cntr=0.3,0.1

Type RM Length L Ch R = 1,2716,241,241,241
BEGIN DESCRIPTION:
Mill Creek Trib E2715.64
END DESCRIPTION:
XS GIS Cut Line= 3
      2745343.57      6815670.61      2745556.74      6816162.35
      2745678.42      6816483.94
#Sta/Elev= 30
  4465.2  405.15  4498.3  403.70  4506.4  402.68  4520.1  402.57  4529.9  401.33
  4535.3  401.44  4552.8  400.53  4558.8  399.77  4564.2  399.97  4605.7  397.75
  4611.2  397.93  4634.6  396.45  4651.7  396.08  4687.0  395.37  4694.5  394.83
  4716.3  395.36  4780.9  395.41  4784.4  391.63  4784.6  391.13  4788.1  391.13
  4788.4  391.63  4803.5  395.50  4809.8  395.65  4833.3  394.34  4893.3  393.30
  4985.0  393.30  5031.8  393.80  5138.7  398.17  5256.3  404.89  5345.0  408.97
#Mann=5,-1,0
  4465.2    0.16       0  4651.7    0.12       0  4784.4    0.05       0
  4788.4    0.12       0  4893.3    0.05       0
Bank Sta=4784.4,4788.4
Exp/Cntr=0.3,0.1

Type RM Length L Ch R = 1,2475,260,260,260
BEGIN DESCRIPTION:
Mill Creek Trib E2474.95
END DESCRIPTION:
XS GIS Cut Line= 3
      2745123.07      6815731.16      2745371.57      6816220.26
      2745556.38      6816567.65
#Sta/Elev= 30
  4454.7  402.94  4494.0  400.41  4499.6  400.75  4516.3  399.67  4538.5  399.05
  4555.2  397.59  4572.2  396.88  4644.2  393.55  4688.7  393.27  4711.0  392.09
  4716.6  393.29  4733.2  393.80  4755.5  393.26  4805.6  393.66  4844.5  393.08
  4889.0  394.38  4892.6  389.82  4892.9  389.32  4896.4  389.32  4896.6  389.82
  4916.9  394.14  4944.8  393.17  4955.8  392.66  4983.6  393.11  5000.3  392.47
  5060.5  393.57  5310.0  402.53  5324.2  403.64  5384.5  406.16  5396.8  407.23
#Mann=5,-1,0
  4454.7    0.16       0  4572.2    0.12       0  4892.6    0.05       0
  4896.6    0.12       0  4944.8    0.05       0
Bank Sta=4892.6,4896.6
Exp/Cntr=0.3,0.1

Type RM Length L Ch R = 1,2215,194,194,194
BEGIN DESCRIPTION:
Mill Creek Trib E2214.64
END DESCRIPTION:
XS GIS Cut Line= 3
      2744903.91      6815857.50      2745156.86      6816284.39
      2745423.22      6816702.92
#Sta/Elev= 30
  4507.4  402.99  4525.1  402.15  4610.0  395.23  4642.1  392.66  4705.3  391.25
  4759.0  391.44  4767.2  390.87  4796.7  391.76  4817.5  389.44  4825.3  390.41
  4876.0  391.95  4883.4  390.41  4906.7  391.93  4934.5  391.67  4941.5  390.93
  4950.1  391.60  4983.3  391.90  4987.2  391.74  4993.0  389.62  5003.6  389.41
  5006.4  388.70  5006.7  388.20  5010.2  388.20  5010.4  388.70  5014.3  392.02
  5052.6  391.14  5224.8  396.14  5311.5  397.03  5399.6  400.42  5499.7  405.76
#Mann=8,-1,0
  4507.4    0.12       0  4610.0    0.16       0  4705.3    0.12       0
  4796.7    0.16       0  4983.3    0.12       0  5006.4    0.07       0
  5010.4    0.12       0  5052.6    0.05       0
Bank Sta=5006.4,5010.4
Exp/Cntr=0.3,0.1

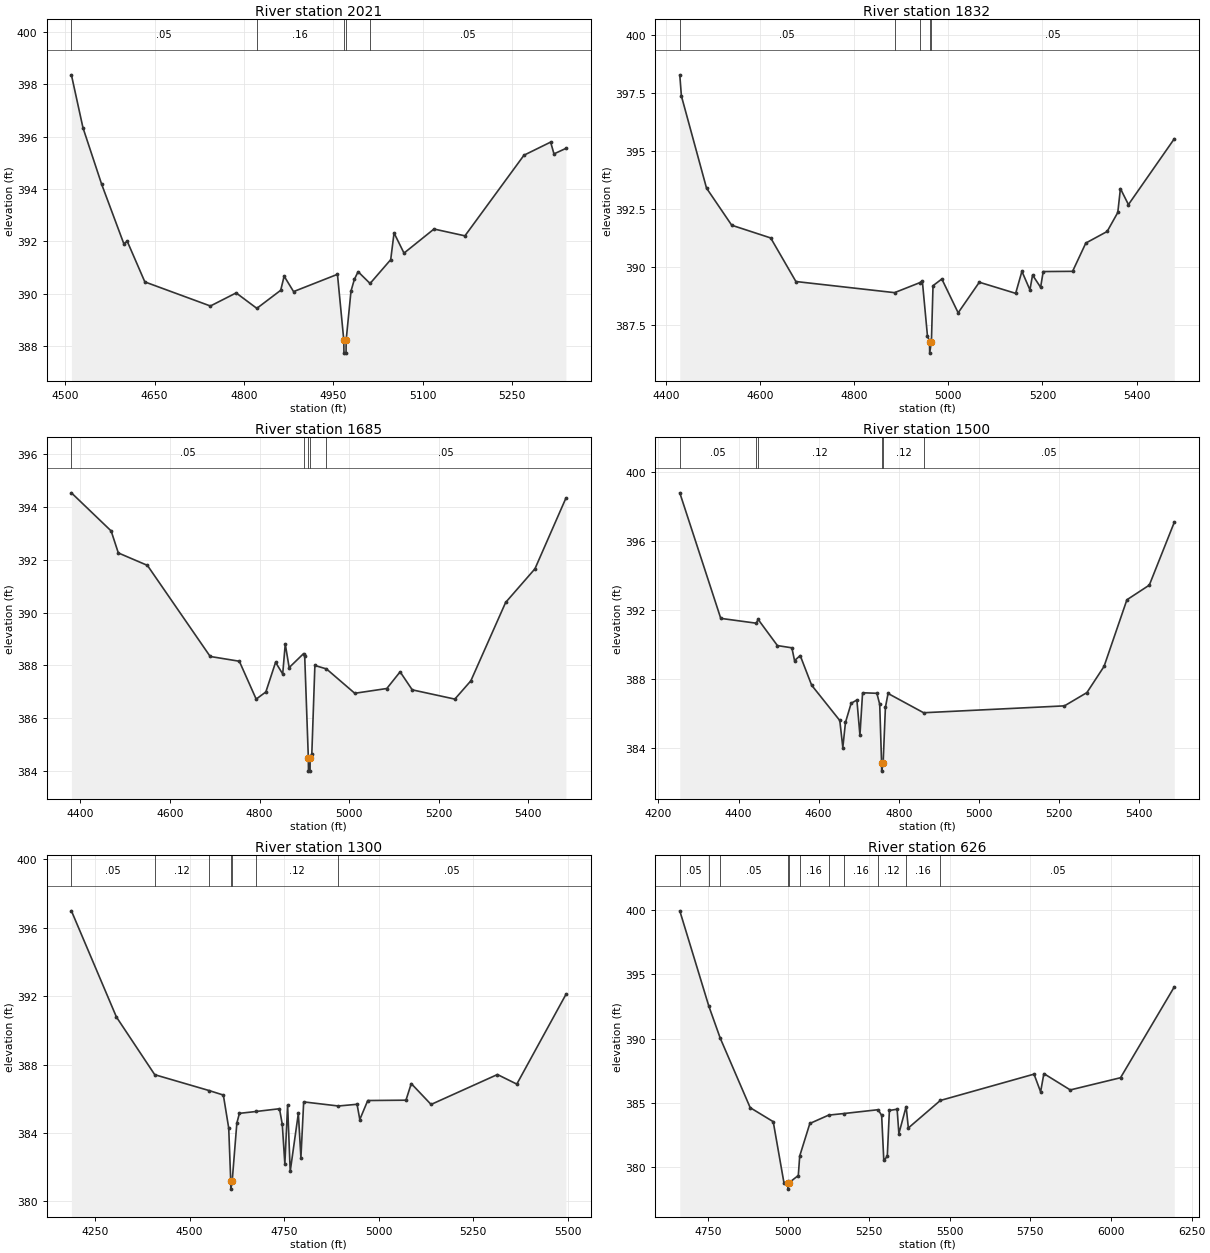
Type RM Length L Ch R = 1,2021,189,189,189
BEGIN DESCRIPTION:
Mill Creek Trib E2021.1
END DESCRIPTION:
XS GIS Cut Line= 3
      2744774.67      6815994.15      2745018.16      6816417.80
      2745170.76      6816722.37
#Sta/Elev= 30
  4510.6  398.36  4530.0  396.34  4561.2  394.19  4598.5  391.91  4604.3  392.00
  4633.8  390.45  4743.7  389.53  4786.9  390.03  4821.6  389.44  4861.6  390.13
  4867.4  390.67  4883.2  390.08  4956.8  390.74  4967.4  388.23  4967.7  387.73
  4971.2  387.73  4971.4  388.23  4979.5  390.10  4985.2  390.55  4991.4  390.84
  5011.5  390.39  5046.1  391.30  5051.7  392.32  5068.4  391.55  5118.7  392.47
  5170.6  392.21  5269.6  395.29  5314.3  395.79  5319.9  395.34  5339.9  395.55
#Mann=5,-1,0
  4510.6    0.05       0  4821.6    0.16       0  4967.4    0.07       0
  4971.4    0.16       0  5011.5    0.05       0
Bank Sta=4967.4,4971.4
Exp/Cntr=0.3,0.1

Type RM Length L Ch R = 1,1832,147,147,147
BEGIN DESCRIPTION:
Mill Creek Trib E1832.15
END DESCRIPTION:
XS GIS Cut Line= 3
      2744669.22      6816024.13      2744886.23      6816555.35
      2745092.81      6816984.60
#Sta/Elev= 30
  4429.7  398.30  4433.1  397.39  4486.5  393.41  4540.0  391.81  4622.8  391.26
  4676.3  389.38  4885.8  388.90  4939.3  389.33  4944.8  389.41  4955.6  387.05
  4960.1  386.79  4960.4  386.29  4964.1  386.79  4967.5  389.20  4986.2  389.49
  5020.9  388.03  5065.8  389.35  5143.0  388.87  5156.3  389.82  5173.3  389.02
  5178.9  389.66  5196.0  389.13  5201.5  389.81  5263.9  389.82  5292.0  391.04
  5337.3  391.54  5359.9  392.36  5365.5  393.39  5382.5  392.70  5479.9  395.54
#Mann=5,-1,0
  4429.7    0.05       0  4885.8    0.16       0  4939.3    0.05       0
  4960.1    0.05       0  4964.1    0.05       0
Bank Sta=4960.1,4964.1
Exp/Cntr=0.3,0.1

Type RM Length L Ch R = 1,1685,185,185,185
BEGIN DESCRIPTION:
Mill Creek Trib E1684.93
END DESCRIPTION:
XS GIS Cut Line= 3
      2744477.87      6816117.85      2744782.51      6816657.65
      2745059.68      6817053.90
#Sta/Elev= 30
  4380.2  394.52  4468.9  393.08  4484.9  392.25  4549.8  391.78  4689.9  388.34
  4754.9  388.16  4792.5  386.73  4814.1  387.00  4835.8  388.12  4851.7  387.68
  4857.4  388.81  4866.1  387.92  4898.4  388.45  4900.8  388.35  4908.9  384.51
  4909.2  384.01  4912.7  384.01  4912.9  384.51  4916.7  384.67  4923.5  388.00
  4949.3  387.87  5012.5  386.95  5084.0  387.13  5113.7  387.76  5140.7  387.08
  5235.8  386.73  5271.5  387.42  5349.1  390.38  5414.5  391.65  5483.6  394.32
#Mann=5,-1,0
  4380.2    0.05       0  4898.4    0.12       0  4908.9    0.05       0
  4912.9    0.12       0  4949.3    0.05       0
Bank Sta=4908.9,4912.9
Exp/Cntr=0.3,0.1

Type RM Length L Ch R = 1,1500,200,200,200
BEGIN DESCRIPTION:
Mill Creek Trib E1499.9
END DESCRIPTION:
XS GIS Cut Line= 3
      2744223.03      6816259.77      2744712.41      6816822.22
      2745084.09      6817140.23
#Sta/Elev= 30
  4253.2  398.79  4355.5  391.50  4444.1  391.22  4448.8  391.44  4497.0  389.92
  4533.1  389.79  4539.7  389.05  4553.9  389.34  4582.4  387.62  4652.7  385.57
  4660.3  384.00  4666.9  385.46  4681.1  386.57  4695.4  386.76  4703.0  384.71
  4709.6  387.18  4745.3  387.15  4752.4  386.51  4757.0  383.13  4757.3  382.63
  4761.0  383.13  4766.6  386.33  4773.2  387.14  4862.0  386.02  5213.7  386.42
  5269.7  387.19  5312.5  388.71  5369.6  392.58  5425.5  393.43  5487.9  397.08
#Mann=6,-1,0
  4253.2    0.05       0  4444.1    0.16       0  4448.8    0.12       0
  4757.0    0.05       0  4761.0    0.12       0  4862.0    0.05       0
Bank Sta=4757,4761
Exp/Cntr=0.3,0.1

Type RM Length L Ch R = 1,1300,674,674,674
BEGIN DESCRIPTION:
Mill Creek Trib E1299.68
END DESCRIPTION:
XS GIS Cut Line= 4
      2743998.41      6816340.17      2744553.19      6816932.71
      2744692.32      6817016.57      2745007.22      6817128.01
#Sta/Elev= 30
  4187.2  396.99  4306.4  390.78  4407.7  387.41  4551.9  386.48  4589.2  386.22
  4603.4  384.29  4608.7  381.22  4609.0  380.72  4612.7  381.22  4624.9  384.58
  4631.7  385.15  4676.3  385.26  4737.7  385.42  4745.1  384.51  4751.9  382.19
  4759.2  385.64  4766.1  381.76  4787.6  385.15  4794.4  382.56  4801.7  385.82
  4893.6  385.58  4942.9  385.68  4950.2  384.79  4971.2  385.90  5072.3  385.92
  5086.3  386.89  5138.7  385.67  5314.3  387.42  5365.5  386.86  5495.4  392.10
#Mann=7,-1,0
  4187.2    0.05       0  4407.7    0.12       0  4551.9    0.16       0
  4608.7    0.05       0  4612.7    0.16       0  4676.3    0.12       0
  4893.6    0.05       0
Bank Sta=4608.7,4612.7
Exp/Cntr=0.3,0.1

Type RM Length L Ch R = 1,626,197,197,197
BEGIN DESCRIPTION:
Mill Creek Trib E625.73
END DESCRIPTION:
XS GIS Cut Line= 5
      2743908.03      6816337.97      2744006.07      6816665.05
      2744165.97      6816894.87      2744408.38      6816994.19
      2745037.42      6817154.71
#Sta/Elev= 30
  4663.4  399.95  4753.2  392.55  4788.6  390.05  4881.6  384.63  4953.0  383.54
  4986.1  378.80  4998.1  378.79  4998.4  378.29  5002.1  378.79  5030.7  379.35
  5035.1  380.87  5066.5  383.40  5124.8  384.05  5170.8  384.17  5277.7  384.47
  5289.0  384.04  5295.7  380.52  5306.5  380.84  5313.0  384.41  5337.0  384.51
  5342.4  382.61  5364.9  384.71  5371.8  383.05  5470.9  385.19  5761.3  387.24
  5781.7  385.86  5791.8  387.28  5873.6  386.01  6029.4  386.96  6196.0  394.03
#Mann=11,-1,0
  4663.4    0.05       0  4753.2    0.16       0  4788.6    0.05       0
  4998.1    0.05       0  5002.1    0.05       0  5035.1    0.16       0
  5124.8    0.05       0  5170.8    0.16       0  5277.7    0.12       0
  5364.9    0.16       0  5470.9    0.05       0
Bank Sta=4998.1,5002.1
Exp/Cntr=0.3,0.1

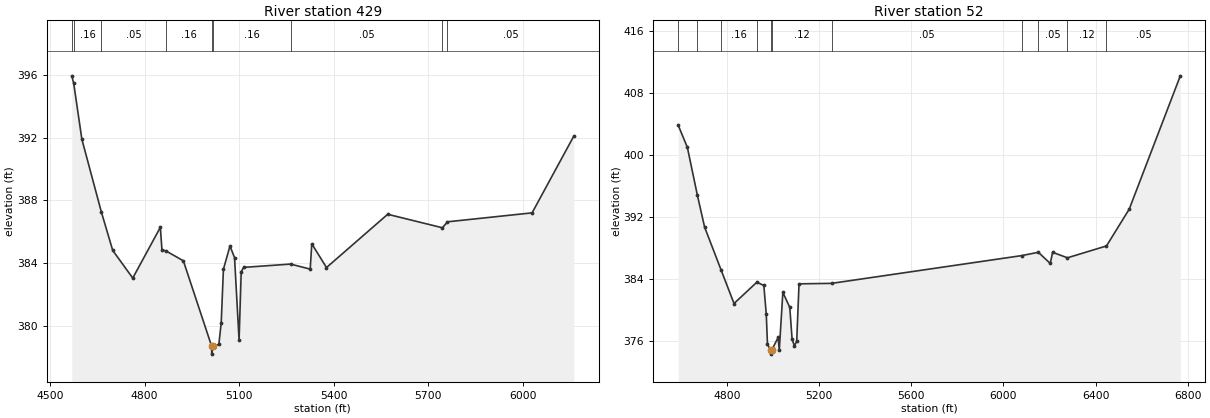
Type RM Length L Ch R = 1,429,377,377,377
BEGIN DESCRIPTION:
Mill Creek Trib E428.66
END DESCRIPTION:
XS GIS Cut Line= 5
      2743863.50      6816389.14      2743920.88      6816818.30
      2743999.33      6816918.89      2744148.81      6817000.39
      2744996.09      6817164.40
#Sta/Elev= 30
  4568.7  395.93  4574.8  395.46  4600.8  391.89  4662.7  387.26  4698.7  384.82
  4762.3  383.06  4849.9  386.29  4854.9  384.87  4869.2  384.77  4922.9  384.16
  5012.8  378.72  5013.0  378.22  5016.8  378.72  5035.6  378.84  5043.1  380.21
  5050.1  383.62  5070.9  385.10  5085.4  384.36  5099.8  379.11  5106.6  383.47
  5114.3  383.74  5263.2  383.95  5325.6  383.63  5330.6  385.24  5377.3  383.73
  5571.6  387.12  5745.4  386.26  5761.4  386.64  6030.0  387.21  6162.5  392.10
#Mann=9,-1,0
  4568.7    0.05       0  4574.8    0.16       0  4662.7    0.05       0
  4869.2    0.16       0  5012.8    0.07       0  5016.8    0.16       0
  5263.2    0.05       0  5745.4    0.12       0  5761.4    0.05       0
Bank Sta=5012.8,5016.8
Exp/Cntr=0.3,0.1

Type RM Length L Ch R = 1,52,0,0,0
BEGIN DESCRIPTION:
Mill Creek Trib E51.893
END DESCRIPTION:
XS GIS Cut Line= 6
      2743858.61      6816313.96      2743712.70      6816697.65
      2743701.00      6816886.00      2743886.18      6817005.20
      2744084.93      6817070.56      2745225.96      6817211.00
#Sta/Elev= 30
  4589.5  403.83  4629.1  400.98  4672.4  394.82  4704.0  390.68  4776.2  385.10
  4831.5  380.83  4930.2  383.57  4960.8  383.17  4971.4  379.47  4976.7  375.56
  4990.9  374.80  4991.1  374.30  4994.9  374.80  5022.9  376.45  5027.9  374.82
  5043.4  382.27  5073.5  380.32  5083.5  376.21  5093.5  375.37  5103.5  375.97
  5113.6  383.37  5254.5  383.43  6079.0  387.01  6151.8  387.44  6203.6  386.00
  6213.7  387.44  6278.0  386.73  6447.5  388.26  6546.2  393.01  6767.8  410.21
#Mann=11,-1,0
  4589.5    0.05       0  4672.4    0.12       0  4776.2    0.16       0
  4930.2    0.12       0  4990.9    0.07       0  4994.9    0.12       0
  5254.5    0.05       0  6079.0    0.12       0  6151.8    0.05       0
  6278.0    0.12       0  6447.5    0.05       0
Bank Sta=4990.9,4994.9
Exp/Cntr=0.3,0.1

Chan Stop Cuts=-1