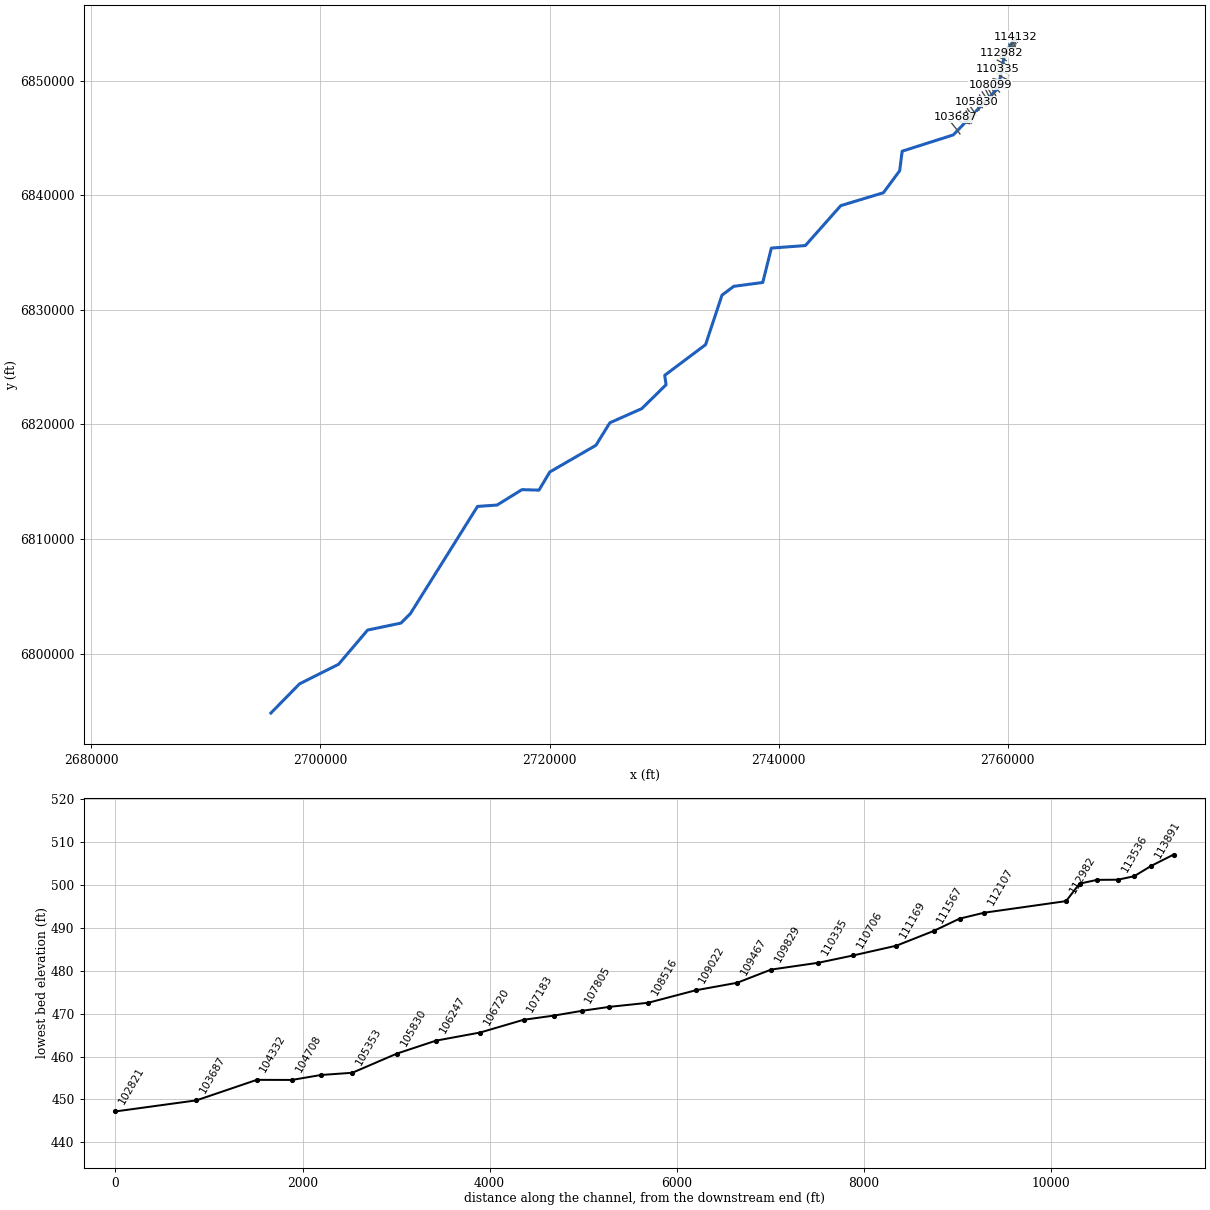
--- North Twin Creek.prj (project) ---

Proj Title=North Twin Creek Base Level Engineering
Current Plan=p01
Default Exp/Contr=0.3,0.1
English Units
Geom File=g01
Flow File=f01
Plan File=p01
BEGIN DESCRIPTION:
North Twin Creek
END DESCRIPTION:

--- North Twin Creek.p01 (plan) ---

Plan Title=Multiple Run
Short Identifier=Multiple
Geom File=g01
Flow File=f01
Subcritical Flow
K Sum by GR= 0
Std Step Tol= 0.01
Critical Tol= 0.01
Num of Std Step Trials= 20
Max Error Tol= 0.3
Flow Tol Ratio= 0.001
Split Flow NTrial= 30
Split Flow Tol= 0.02
Split Flow Ratio= 0.02
Log Output Level= 0
Friction Slope Method= 1
Unsteady Friction Slope Method= 2
Unsteady Bridges Friction Slope Method= 1
Parabolic Critical Depth
Global Vel Dist=  1 , 1 , 1
Global Log Level= 0
CheckData=True
Encroach Param= -1, 0, 0, 0
BEGIN DESCRIPTION:
Multiple Run
END DESCRIPTION:

--- North Twin Creek.f01 (steady flow) ---

Flow Title=Multiple
Number of Profiles=7
Profile Names=10-year,25-year,50-year,1pct_min,100-year,1pct_plu,500-year
River Rch & RM= North Twin Creek,Reach-1,114132
     515     686     823     491     980    1956    1393
River Rch & RM= North Twin Creek,Reach-1,112107
     707     958    1163     701    1399    2792    2031
River Rch & RM= North Twin Creek,Reach-1,105353
     911    1251    1532     931    1858    3707    2741
River Rch & RM= North Twin Creek,Reach-1,102821
    1491    2094    2604    1605    3202    6388    4855
River Rch & RM= North Twin Creek,Reach-1,99902
    1674    2348    2918    1795    3581    7145    5409
River Rch & RM= North Twin Creek,Reach-1,88603
    1729    2424    3011    1850    3692    7366    5569
River Rch & RM= North Twin Creek,Reach-1,82554
    1856    2610    3248    1999    3989    7959    6038
River Rch & RM= North Twin Creek,Reach-1,79213
    1938    2725    3391    2087    4165    8309    6302
River Rch & RM= North Twin Creek,Reach-1,76435
    4289    6199    7854    4903    9782   19519   15181
River Rch & RM= North Twin Creek,Reach-1,71185
    4298    6209    7865    4908    9793   19539   15189
River Rch & RM= North Twin Creek,Reach-1,70093
    4425    6399    8112    5065   10107   20165   15695
River Rch & RM= North Twin Creek,Reach-1,69697
    4426    6392    8094    5049   10073   20098   15608
River Rch & RM= North Twin Creek,Reach-1,67102
    4289    6191    7835    4884    9745   19443   15084
River Rch & RM= North Twin Creek,Reach-1,63807
    4424    6369    8048    5009    9993   19939   15413
River Rch & RM= North Twin Creek,Reach-1,60277
    4333    6243    7892    4913    9802   19557   15131
River Rch & RM= North Twin Creek,Reach-1,58127
    4376    6306    7973    4963    9903   19759   15290
River Rch & RM= North Twin Creek,Reach-1,57702
    4322    6215    7846    4877    9731   19415   14977
River Rch & RM= North Twin Creek,Reach-1,54591
    4396    6324    7986    4965    9906   19766   15254
River Rch & RM= North Twin Creek,Reach-1,53713
    5515    7990   10139    6332   12633   25207   19623
River Rch & RM= North Twin Creek,Reach-1,52600
    4435    6383    8061    5013   10002   19957   15407
River Rch & RM= North Twin Creek,Reach-1,50893
    5552    8039   10197    6365   12699   25339   19706
River Rch & RM= North Twin Creek,Reach-1,48060
    5669    8212   10419    6505   12979   25897   20149
River Rch & RM= North Twin Creek,Reach-1,45617
    6071    8802   11174    6979   13925   27785   21635
River Rch & RM= North Twin Creek,Reach-1,41027
    6121    8872   11261    7032   14032   27997   21792
River Rch & RM= North Twin Creek,Reach-1,37361
    6116    8860   11242    7018   14002   27938   21729
River Rch & RM= North Twin Creek,Reach-1,35572
    6143    8896   11285    7042   14052   28036   21792
River Rch & RM= North Twin Creek,Reach-1,34705
    6505    9432   11975    7478   14921   29772   23172
River Rch & RM= North Twin Creek,Reach-1,31432
    6491    9396   11917    7434   14832   29594   22982
River Rch & RM= North Twin Creek,Reach-1,29060
    6532    9450   11978    7468   14901   29731   23062
River Rch & RM= North Twin Creek,Reach-1,24768
    6509    9382   11863    7376   14716   29363   22652
River Rch & RM= North Twin Creek,Reach-1,16875
    6624    9551   12079    7512   14989   29907   23082
River Rch & RM= North Twin Creek,Reach-1,16371
   10068   14659   18671   11687   23319   46527   36357
River Rch & RM= North Twin Creek,Reach-1,14053
   10091   14673   18672   11676   23297   46483   36251
River Rch & RM= North Twin Creek,Reach-1,10699
    9968   14467   18386   11482   22909   45710   35550
River Rch & RM= North Twin Creek,Reach-1,7603
    9908   14360   18232   11374   22695   45283   35147
River Rch & RM= North Twin Creek,Reach-1,4490
    9720   14052   17809   11090   22127   44148   34139
Boundary for River Rch & Prof#=North Twin Creek,Reach-1,1
Up Type=0
Dn Type=3
Dn Slope=0.005
Boundary for River Rch & Prof#=North Twin Creek,Reach-1,2
Up Type=0
Dn Type=3
Dn Slope=0.005
Boundary for River Rch & Prof#=North Twin Creek,Reach-1,3
Up Type=0
Dn Type=3
Dn Slope=0.005
Boundary for River Rch & Prof#=North Twin Creek,Reach-1,4
Up Type=0
Dn Type=3
Dn Slope=0.005
Boundary for River Rch & Prof#=North Twin Creek,Reach-1,5
Up Type=0
Dn Type=3
Dn Slope=0.005
Boundary for River Rch & Prof#=North Twin Creek,Reach-1,6
Up Type=0
Dn Type=3
Dn Slope=0.005
Boundary for River Rch & Prof#=North Twin Creek,Reach-1,7
Up Type=0
Dn Type=3
Dn Slope=0.005

--- North Twin Creek.g01 (geometry) ---

Geom Title=Existing Conditions

River Reach=North Twin Creek,Reach-1
Reach XY= 30
      2760776.00      6853911.00      2759729.45      6852359.75
      2759173.05      6849368.98      2755242.71      6845277.21
      2750780.76      6843855.43      2750567.23      6842154.23
      2749146.20      6840230.61      2745419.91      6839102.86
      2742332.45      6835618.61      2739362.78      6835397.88
      2738612.61      6832397.31      2736081.63      6832059.27
      2735048.23      6831284.71      2733622.92      6826968.68
      2730051.53      6824288.15      2730172.92      6823469.30
      2728046.47      6821380.63      2725262.37      6820147.54
      2724046.13      6818180.77      2720016.01      6815850.96
      2719078.87      6814266.23      2717590.94      6814310.64
      2715414.42      6812962.39      2713712.43      6812847.53
      2707846.39      6803480.84      2707026.00      6802661.00
      2704119.94      6802052.86      2701576.00      6799061.00
      2698169.94      6797352.86      2695676.00      6794811.00

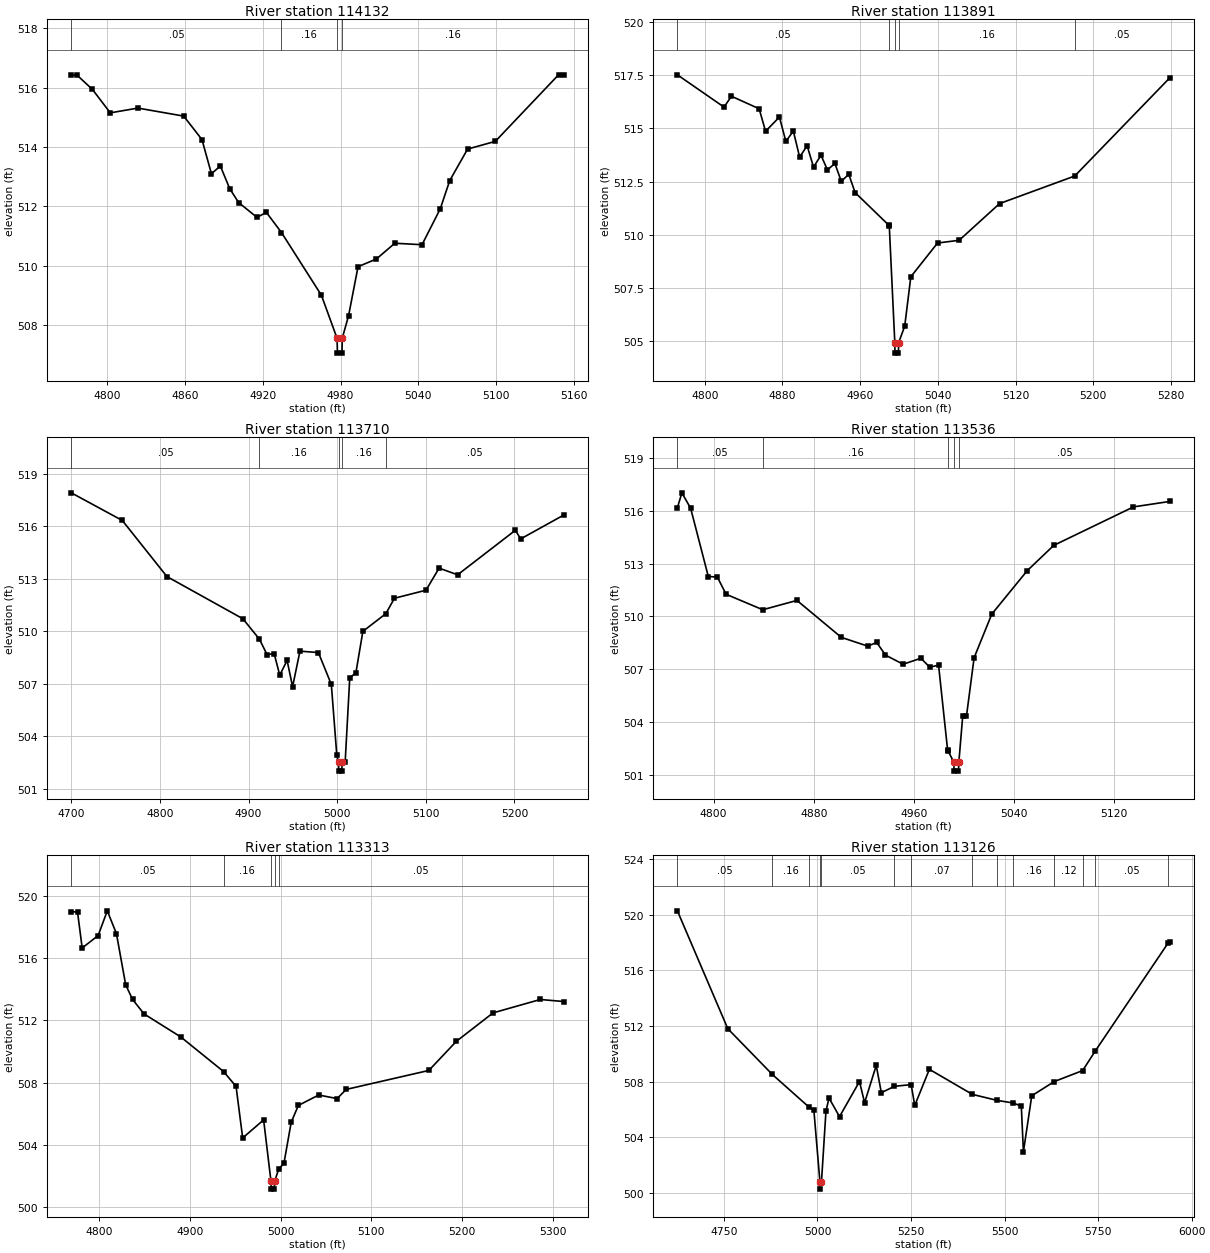
Type RM Length L Ch R = 1,114132,241,241,241
BEGIN DESCRIPTION:
North Twin Creek113971.393
END DESCRIPTION:
XS GIS Cut Line= 3
      2760907.06      6853569.21      2760749.82      6853734.18
      2760645.49      6853845.13
#Sta/Elev= 30
  4772.1  516.42  4776.5  516.42  4788.4  515.94  4802.2  515.15  4823.6  515.31
  4858.9  515.04  4873.0  514.25  4880.3  513.10  4887.2  513.36  4894.4  512.60
  4901.3  512.13  4915.5  511.63  4922.7  511.80  4934.4  511.12  4965.2  509.01
  4977.3  507.56  4977.6  507.06  4981.1  507.06  4981.3  507.56  4986.2  508.32
  4993.5  509.97  5007.7  510.23  5021.9  510.76  5042.9  510.71  5057.0  511.92
  5064.3  512.87  5078.1  513.93  5099.5  514.19  5148.3  516.43  5152.3  516.43
#Mann=4,-1,0
  4772.1    0.05       0  4934.4    0.16       0  4977.3    0.07       0
  4981.3    0.16       0
Bank Sta=4977.3,4981.3
Exp/Cntr=0.3,0.1

Type RM Length L Ch R = 1,113891,181,181,181
BEGIN DESCRIPTION:
Mapping XS bb1608fa
END DESCRIPTION:
XS GIS Cut Line= 3
      2760839.24      6853386.11      2760687.29      6853564.23
      2760520.55      6853780.36
#Sta/Elev= 30
  4771.8  517.53  4819.8  516.01  4827.5  516.52  4856.0  515.93  4862.6  514.87
  4876.9  515.54  4883.5  514.39  4891.2  514.88  4897.7  513.65  4905.4  514.19
  4912.0  513.18  4919.7  513.74  4926.3  513.05  4934.0  513.35  4940.6  512.51
  4948.3  512.84  4954.8  511.98  4989.3  510.45  4990.0  510.42  4995.7  504.91
  4995.9  504.41  4999.4  504.41  4999.7  504.91  5005.9  505.68  5012.2  508.01
  5039.7  509.60  5062.0  509.73  5103.6  511.46  5181.0  512.76  5278.9  517.39
#Mann=5,-1,0
  4771.8    0.05       0  4989.3    0.16       0  4995.7    0.07       0
  4999.7    0.16       0  5181.0    0.05       0
Bank Sta=4995.7,4999.7
Exp/Cntr=0.3,0.1

Type RM Length L Ch R = 1,113710,174,174,174
BEGIN DESCRIPTION:
Mapping XS 98093080
END DESCRIPTION:
XS GIS Cut Line= 3
      2760720.65      6853235.17      2760536.32      6853477.42
      2760390.11      6853681.68
#Sta/Elev= 30
  4700.0  517.90  4757.6  516.32  4807.9  513.12  4893.6  510.71  4912.2  509.55
  4920.9  508.66  4928.9  508.72  4935.2  507.49  4943.5  508.33  4949.7  506.83
  4958.0  508.86  4978.8  508.78  4993.4  506.96  4999.6  502.91  5001.5  502.51
  5001.8  502.01  5005.3  502.01  5005.5  502.51  5009.0  502.51  5014.2  507.34
  5021.1  507.62  5029.0  509.99  5054.9  511.00  5064.6  511.88  5100.2  512.34
  5115.0  513.60  5135.9  513.22  5201.0  515.76  5207.1  515.27  5255.6  516.63
#Mann=5,-1,0
  4700.0    0.05       0  4912.2    0.16       0  5001.5    0.07       0
  5005.5    0.16       0  5054.9    0.05       0
Bank Sta=5001.5,5005.5
Exp/Cntr=0.3,0.1

Type RM Length L Ch R = 1,113536,223,223,223
BEGIN DESCRIPTION:
North Twin Creek113532.709
END DESCRIPTION:
XS GIS Cut Line= 3
      2760593.54      6853193.46      2760433.85      6853357.44
      2760317.25      6853473.34
#Sta/Elev= 30
  4771.1  516.18  4774.7  517.03  4781.7  516.15  4795.8  512.27  4803.0  512.24
  4810.0  511.26  4839.3  510.38  4866.6  510.91  4902.0  508.81  4923.1  508.31
  4930.3  508.52  4937.3  507.80  4951.4  507.28  4965.6  507.62  4972.7  507.11
  4979.7  507.23  4986.9  502.42  4987.5  502.33  4991.9  501.70  4992.1  501.20
  4995.6  501.20  4995.9  501.70  4999.0  504.33  5002.0  504.33  5008.1  507.65
  5022.2  510.13  5050.5  512.60  5071.7  514.04  5135.4  516.23  5164.4  516.54
#Mann=5,-1,0
  4771.1    0.05       0  4839.3    0.16       0  4987.5    0.05       0
  4991.9    0.05       0  4995.9    0.05       0
Bank Sta=4991.9,4995.9
Exp/Cntr=0.3,0.1

Type RM Length L Ch R = 1,113313,187,187,187
BEGIN DESCRIPTION:
Mapping XS 52ba7b1f
END DESCRIPTION:
XS GIS Cut Line= 3
      2760635.16      6853104.42      2760403.87      6853143.13
      2760099.04      6853190.53
#Sta/Elev= 30
  4769.2  519.00  4776.1  518.97  4781.2  516.66  4798.8  517.46  4808.9  519.05
  4819.0  517.58  4829.2  514.29  4836.8  513.35  4849.5  512.42  4890.0  510.94
  4937.3  508.71  4950.9  507.76  4958.2  504.45  4981.3  505.61  4989.4  501.66
  4989.7  501.16  4993.2  501.16  4993.4  501.66  4998.0  502.46  5003.7  502.82
  5011.7  505.46  5019.6  506.54  5042.0  507.21  5062.3  506.98  5072.4  507.57
  5163.5  508.79  5193.8  510.66  5234.3  512.49  5286.4  513.35  5312.2  513.22
#Mann=5,-1,0
  4769.2    0.05       0  4937.3    0.16       0  4989.4    0.05       0
  4993.4    0.16       0  4998.0    0.05       0
Bank Sta=4989.4,4993.4
Exp/Cntr=0.3,0.1

Type RM Length L Ch R = 1,113126,144,144,144
BEGIN DESCRIPTION:
North Twin Creek113064.062
END DESCRIPTION:
XS GIS Cut Line= 3
      2760660.70      6853023.34      2760286.40      6853021.10
      2759444.82      6852598.78
#Sta/Elev= 30
  4625.7  520.28  4760.4  511.81  4879.4  508.52  4978.4  506.15  4990.4  505.96
  5006.7  500.78  5007.0  500.28  5010.7  500.78  5022.8  505.91  5031.0  506.82
  5059.0  505.49  5112.3  508.01  5126.0  506.49  5157.1  509.17  5170.7  507.21
  5205.8  507.67  5250.4  507.79  5260.0  506.29  5299.1  508.89  5413.9  507.09
  5479.6  506.66  5523.4  506.47  5544.8  506.24  5550.4  502.96  5572.7  506.99
  5632.8  508.01  5708.7  508.80  5742.2  510.20  5937.9  518.00  5941.6  518.01
#Mann=14,-1,0
  4625.7    0.05       0  4879.4    0.16       0  4978.4    0.05       0
  5006.7    0.05       0  5010.7    0.05       0  5205.8    0.16       0
  5250.4    0.07       0  5413.9    0.16       0  5479.6   0.063       0
  5523.4    0.16       0  5632.8    0.12       0  5708.7   0.063       0
  5742.2    0.05       0  5937.9   0.063       0
Bank Sta=5006.7,5010.7
Exp/Cntr=0.3,0.1

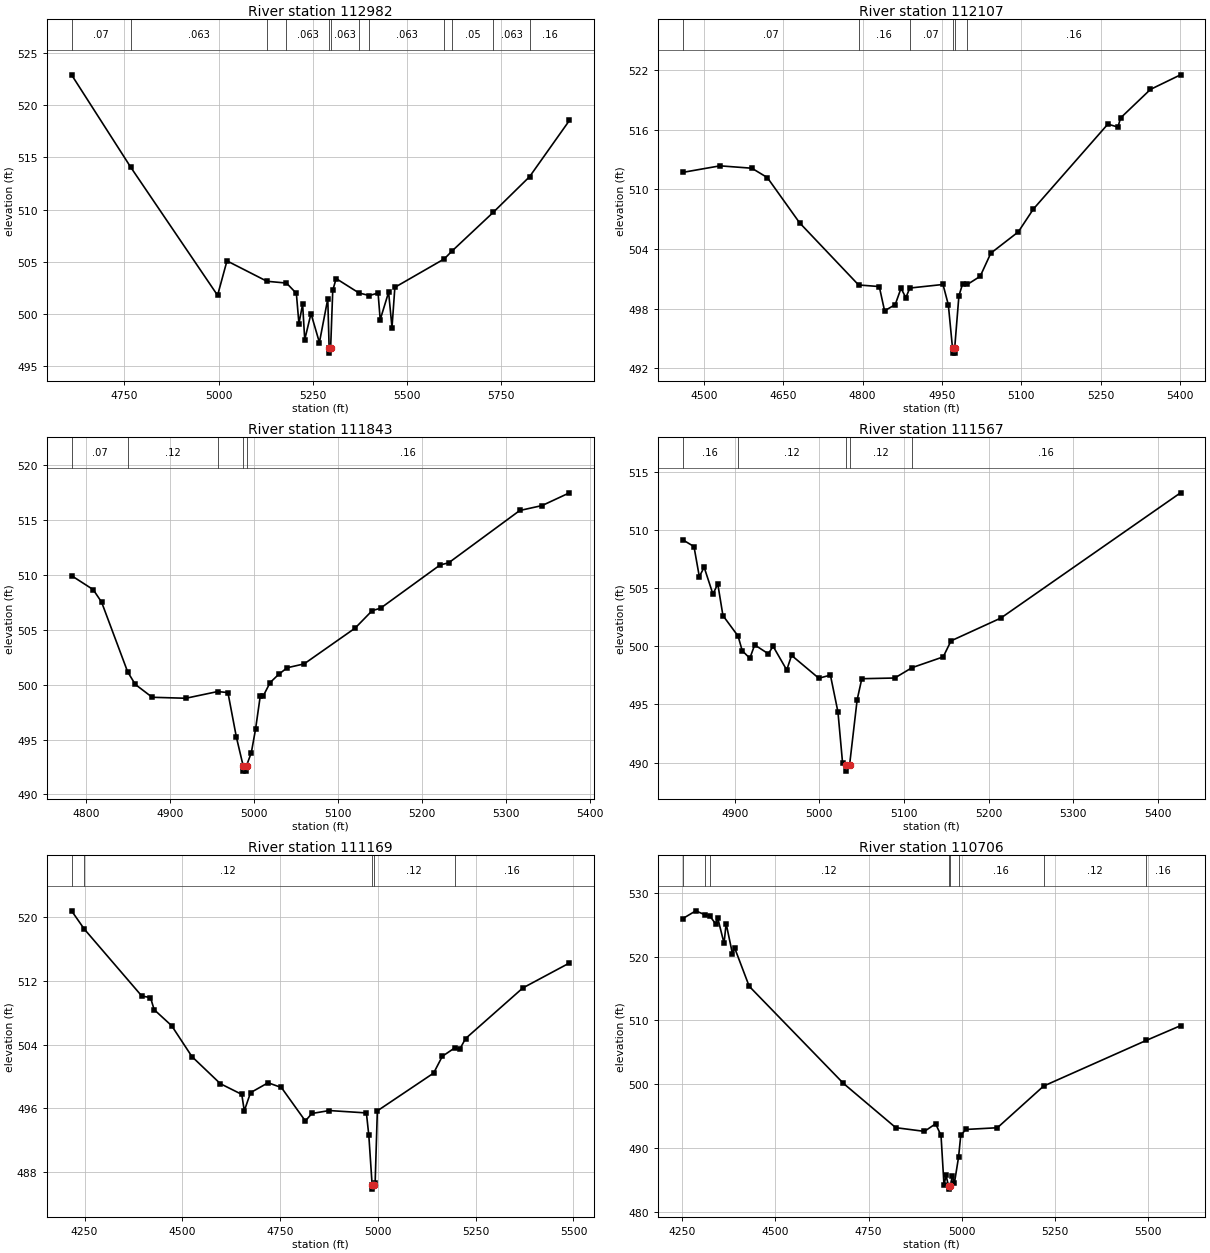
Type RM Length L Ch R = 1,112982,875,875,875
BEGIN DESCRIPTION:
North Twin Creek112594.805
END DESCRIPTION:
XS GIS Cut Line= 3
      2760665.48      6852890.11      2760275.94      6852879.12
      2759446.79      6852456.81
#Sta/Elev= 30
  4610.3  522.94  4767.3  514.06  4997.5  501.76  5022.4  505.07  5128.5  503.11
  5180.2  502.94  5206.4  501.95  5213.2  499.05  5223.0  500.91  5228.6  497.50
  5245.2  500.01  5267.5  497.23  5289.7  501.42  5293.3  496.71  5293.6  496.21
  5297.3  496.71  5302.9  502.24  5311.9  503.37  5372.3  501.99  5399.8  501.74
  5423.1  501.98  5428.7  499.42  5451.0  502.06  5460.0  498.67  5467.6  502.53
  5598.6  505.26  5619.3  506.02  5729.0  509.75  5824.9  513.16  5930.5  518.56
#Mann=12,-1,0
  4610.3    0.07       0  4767.3   0.063       0  5128.5    0.07       0
  5180.2   0.063       0  5293.3   0.063       0  5297.3   0.063       0
  5372.3    0.07       0  5399.8   0.063       0  5598.6    0.07       0
  5619.3    0.05       0  5729.0   0.063       0  5824.9    0.16       0
Bank Sta=5293.3,5297.3
Exp/Cntr=0.3,0.1

Type RM Length L Ch R = 1,112107,264,264,264
BEGIN DESCRIPTION:
Mapping XS 52cf641e
END DESCRIPTION:
XS GIS Cut Line= 3
      2760266.37      6852399.42      2759725.55      6852355.04
      2759329.37      6852314.31
#Sta/Elev= 30
  4459.8  511.70  4530.4  512.36  4590.6  512.12  4619.8  511.18  4680.9  506.62
  4792.3  500.37  4831.4  500.21  4841.4  497.77  4861.5  498.39  4872.5  500.04
  4881.6  499.09  4889.1  500.06  4951.8  500.42  4961.9  498.38  4969.8  494.01
  4970.1  493.51  4973.6  493.51  4973.9  494.01  4981.9  499.28  4988.8  500.46
  4998.1  500.43  5022.1  501.24  5042.2  503.57  5094.1  505.71  5122.6  508.01
  5263.4  516.56  5282.4  516.26  5287.4  517.18  5343.8  520.05  5400.7  521.52
#Mann=6,-1,0
  4459.8    0.07       0  4792.3    0.16       0  4889.1    0.07       0
  4969.8    0.07       0  4973.9    0.07       0  4998.1    0.16       0
Bank Sta=4969.8,4973.9
Exp/Cntr=0.3,0.1

Type RM Length L Ch R = 1,111843,276,276,276
BEGIN DESCRIPTION:
Mapping XS 08110c3d
END DESCRIPTION:
XS GIS Cut Line= 3
      2759901.69      6852086.58      2759674.33      6852107.00
      2759313.86      6852165.73
#Sta/Elev= 30
  4782.2  509.93  4808.0  508.66  4818.0  507.52  4849.1  501.16  4858.2  500.02
  4878.3  498.85  4918.4  498.76  4956.3  499.37  4968.6  499.28  4978.7  495.21
  4986.7  492.62  4986.9  492.12  4990.5  492.12  4990.8  492.62  4996.5  493.81
  5001.5  495.93  5007.1  498.94  5010.5  498.94  5018.9  500.19  5029.0  500.93
  5039.2  501.54  5059.4  501.89  5120.2  505.15  5140.5  506.74  5150.6  506.97
  5221.6  510.91  5231.7  511.10  5316.5  515.87  5343.1  516.32  5375.7  517.48
#Mann=5,-1,0
  4782.2    0.07       0  4849.1    0.12       0  4956.3    0.16       0
  4986.7    0.07       0  4990.8    0.16       0
Bank Sta=4986.7,4990.8
Exp/Cntr=0.3,0.1

Type RM Length L Ch R = 1,111567,398,398,398
BEGIN DESCRIPTION:
Mapping XS a93f390f
END DESCRIPTION:
XS GIS Cut Line= 3
      2759867.71      6851766.22      2759718.10      6851848.30
      2759341.43      6852028.72
#Sta/Elev= 30
  4838.4  509.19  4851.8  508.60  4858.1  506.01  4863.8  506.82  4874.2  504.50
  4879.9  505.39  4886.0  502.66  4903.9  500.89  4908.8  499.63  4917.8  498.98
  4923.5  500.13  4939.6  499.37  4945.3  500.01  4961.4  497.97  4967.1  499.23
  4999.3  497.26  5013.0  497.53  5021.9  494.36  5027.4  489.94  5031.5  489.76
  5031.8  489.26  5035.6  489.76  5044.6  495.41  5050.1  497.22  5089.0  497.28
  5109.4  498.17  5146.3  499.10  5155.5  500.48  5214.3  502.44  5426.7  513.23
#Mann=5,-1,0
  4838.4    0.16       0  4903.9    0.12       0  5031.5    0.07       0
  5035.6    0.12       0  5109.4    0.16       0
Bank Sta=5031.5,5035.6
Exp/Cntr=0.3,0.1

Type RM Length L Ch R = 1,111169,463,463,463
BEGIN DESCRIPTION:
Mapping XS ba1a702c
END DESCRIPTION:
XS GIS Cut Line= 3
      2760224.57      6851226.81      2759521.95      6851581.14
      2759090.02      6851803.91
#Sta/Elev= 30
  4216.8  520.82  4249.4  518.52  4396.3  510.11  4418.6  509.91  4428.0  508.39
  4472.8  506.37  4524.6  502.49  4597.1  499.09  4652.0  497.74  4658.4  495.67
  4674.4  497.96  4719.2  499.20  4753.2  498.61  4814.5  494.40  4831.2  495.34
  4875.8  495.71  4970.6  495.41  4976.8  492.58  4985.3  486.33  4985.5  485.83
  4989.4  486.33  4992.9  486.54  4998.6  495.67  5142.5  500.42  5164.7  502.53
  5196.9  503.60  5209.0  503.40  5224.2  504.76  5370.5  511.12  5489.7  514.26
#Mann=5,-1,0
  4216.8    0.16       0  4249.4    0.12       0  4985.3    0.07       0
  4989.4    0.12       0  5196.9    0.16       0
Bank Sta=4985.3,4989.4
Exp/Cntr=0.3,0.1

Type RM Length L Ch R = 1,110706,371,371,371
BEGIN DESCRIPTION:
North Twin Creek110813.073
END DESCRIPTION:
XS GIS Cut Line= 3
      2760247.61      6850835.47      2759576.15      6851166.01
      2759023.09      6851361.50
#Sta/Elev= 30
  4251.6  525.93  4286.8  527.16  4310.5  526.56  4324.9  526.31  4340.2  525.11
  4345.7  526.03  4362.6  522.07  4368.2  525.17  4385.1  520.44  4390.7  521.40
  4430.0  515.34  4682.7  500.12  4823.1  493.18  4899.9  492.60  4929.9  493.79
  4944.4  491.96  4952.4  484.18  4957.9  485.69  4964.5  484.05  4964.8  483.55
  4968.9  484.05  4974.8  485.56  4980.4  484.53  4991.5  488.59  4997.3  491.97
  5010.8  492.90  5095.6  493.17  5219.5  499.70  5494.6  506.85  5586.6  509.16
#Mann=8,-1,0
  4251.6    0.12       0  4310.5    0.16       0  4324.9    0.12       0
  4964.5    0.07       0  4968.9    0.12       0  4991.5    0.16       0
  5219.5    0.12       0  5494.6    0.16       0
Bank Sta=4964.5,4968.9
Exp/Cntr=0.3,0.1

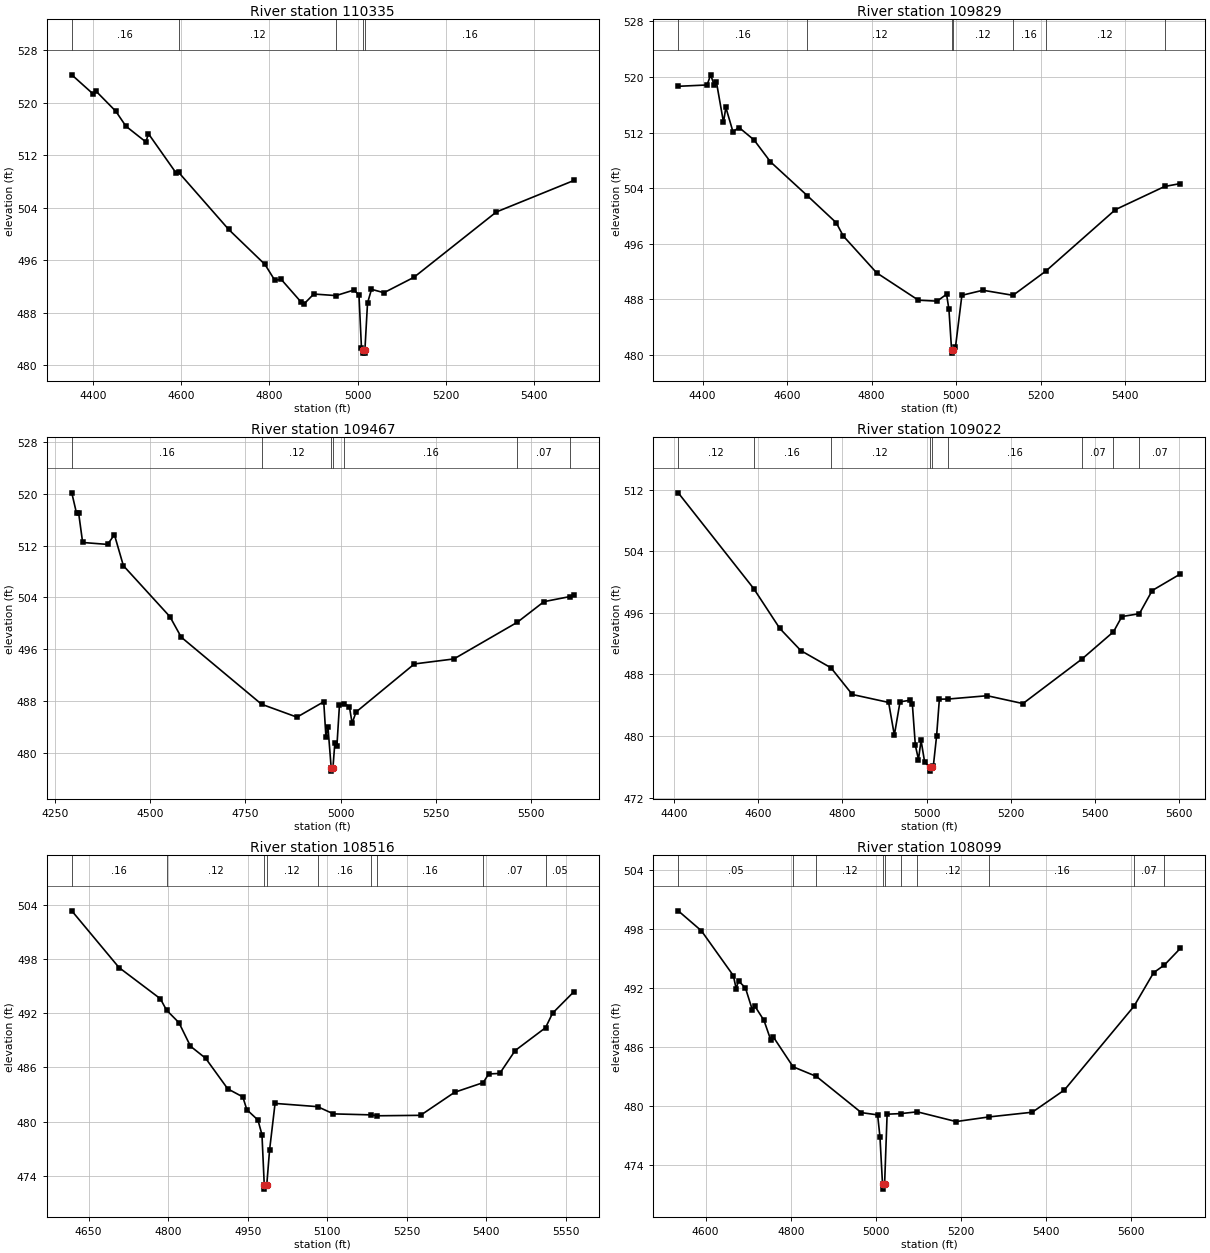
Type RM Length L Ch R = 1,110335,506,506,506
BEGIN DESCRIPTION:
North Twin Creek110335.123
END DESCRIPTION:
XS GIS Cut Line= 3
      2760111.76      6850533.43      2759526.00      6850811.00
      2759084.20      6851022.71
#Sta/Elev= 30
  4351.9  524.28  4400.8  521.33  4406.3  521.83  4451.8  518.72  4474.6  516.45
  4520.0  514.04  4525.6  515.31  4588.3  509.32  4594.4  509.39  4707.5  500.71
  4789.8  495.37  4812.0  492.97  4826.8  493.08  4872.2  489.60  4878.4  489.35
  4900.5  490.86  4950.9  490.62  4991.5  491.47  5002.9  490.73  5008.6  482.63
  5012.0  482.35  5012.3  481.85  5016.1  481.85  5016.4  482.35  5022.3  489.48
  5031.3  491.58  5059.5  491.06  5127.5  493.41  5314.3  503.37  5490.0  508.17
#Mann=5,-1,0
  4351.9    0.16       0  4594.4    0.12       0  4950.9    0.16       0
  5012.0    0.07       0  5016.4    0.16       0
Bank Sta=5012,5016.4
Exp/Cntr=0.3,0.1

Type RM Length L Ch R = 1,109829,362,362,362
BEGIN DESCRIPTION:
North Twin Creek109892.105
END DESCRIPTION:
XS GIS Cut Line= 3
      2760054.39      6850056.30      2759468.52      6850354.94
      2759047.80      6850678.58
#Sta/Elev= 30
  4342.4  518.66  4410.7  518.85  4419.2  520.31  4427.3  518.86  4432.9  519.24
  4449.5  513.48  4455.1  515.62  4471.8  512.14  4486.5  512.72  4521.8  510.94
  4560.7  507.79  4647.7  502.93  4716.3  499.03  4733.0  497.12  4812.0  491.82
  4910.8  487.88  4955.3  487.74  4977.5  488.74  4983.1  486.57  4989.4  480.76
  4989.7  480.26  4993.9  480.76  4998.6  481.12  5013.8  488.58  5063.6  489.31
  5134.8  488.58  5212.0  492.04  5377.2  500.91  5493.6  504.24  5530.8  504.66
#Mann=7,-1,0
  4342.4    0.16       0  4647.7    0.12       0  4989.4    0.07       0
  4993.9    0.12       0  5134.8    0.16       0  5212.0    0.12       0
  5493.6    0.16       0
Bank Sta=4989.4,4993.9
Exp/Cntr=0.3,0.1

Type RM Length L Ch R = 1,109467,445,445,445
BEGIN DESCRIPTION:
North Twin Creek109410.815
END DESCRIPTION:
XS GIS Cut Line= 3
      2759962.18      6849770.91      2759315.14      6850051.36
      2758719.68      6850189.62
#Sta/Elev= 30
  4294.8  520.13  4307.3  516.97  4312.7  517.06  4323.3  512.47  4388.7  512.17
  4406.6  513.67  4430.1  508.89  4552.2  501.02  4581.8  497.86  4792.5  487.51
  4885.3  485.52  4955.5  487.89  4961.2  482.50  4966.6  483.99  4975.0  477.69
  4975.3  477.19  4979.6  477.69  4984.6  481.52  4990.1  481.14  4996.8  487.47
  5009.4  487.57  5022.7  487.16  5029.9  484.58  5040.2  486.31  5193.2  493.73
  5296.8  494.50  5463.1  500.16  5533.0  503.34  5600.8  504.12  5611.3  504.43
#Mann=7,-1,0
  4294.8    0.16       0  4792.5    0.12       0  4975.0    0.07       0
  4979.6    0.12       0  5009.4    0.16       0  5463.1    0.07       0
  5600.8    0.05       0
Bank Sta=4975,4979.6
Exp/Cntr=0.3,0.1

Type RM Length L Ch R = 1,109022,506,506,506
BEGIN DESCRIPTION:
North Twin Creek108967.488
END DESCRIPTION:
XS GIS Cut Line= 3
      2759757.48      6849313.89      2759284.50      6849666.92
      2758814.37      6850044.21
#Sta/Elev= 30
  4409.8  511.60  4589.2  499.15  4651.2  493.97  4701.2  491.09  4772.7  488.86
  4823.4  485.39  4909.7  484.36  4923.3  480.11  4936.8  484.44  4959.7  484.63
  4966.0  484.21  4973.2  478.79  4980.6  476.94  4986.8  479.42  4995.2  476.64
  5007.1  475.93  5007.5  475.43  5011.8  475.93  5015.9  476.06  5023.7  480.00
  5030.3  484.78  5051.6  484.80  5143.9  485.23  5228.9  484.21  5369.5  490.02
  5444.0  493.54  5464.0  495.52  5505.5  495.89  5536.0  498.90  5602.8  501.05
#Mann=9,-1,0
  4409.8    0.12       0  4589.2    0.16       0  4772.7    0.12       0
  5007.1    0.07       0  5011.8    0.12       0  5051.6    0.16       0
  5369.5    0.07       0  5444.0    0.16       0  5505.5    0.07       0
Bank Sta=5007.1,5011.8
Exp/Cntr=0.3,0.1

Type RM Length L Ch R = 1,108516,417,417,417
BEGIN DESCRIPTION:
North Twin Creek108510.14
END DESCRIPTION:
XS GIS Cut Line= 3
      2759280.29      6849019.64      2759026.00      6849311.00
      2758684.45      6849755.01
#Sta/Elev= 30
  4618.1  503.34  4707.2  497.06  4785.1  493.61  4796.9  492.34  4820.2  490.96
  4842.0  488.35  4870.5  487.02  4912.3  483.63  4940.7  482.74  4948.3  481.32
  4969.2  480.18  4976.8  478.56  4981.1  473.03  4981.4  472.53  4985.9  473.03
  4991.1  476.83  5001.5  482.02  5081.7  481.66  5111.7  480.86  5182.8  480.75
  5193.7  480.65  5275.8  480.70  5340.1  483.25  5394.0  484.32  5404.4  485.28
  5425.3  485.34  5454.3  487.87  5511.6  490.40  5524.9  492.01  5565.0  494.38
#Mann=9,-1,0
  4618.1    0.16       0  4796.9    0.12       0  4981.1    0.07       0
  4985.9    0.12       0  5081.7    0.16       0  5182.8    0.12       0
  5193.7    0.16       0  5394.0    0.07       0  5511.6    0.05       0
Bank Sta=4981.1,4985.9
Exp/Cntr=0.3,0.1

Type RM Length L Ch R = 1,108099,294,294,294
BEGIN DESCRIPTION:
North Twin Creek108098.535
END DESCRIPTION:
XS GIS Cut Line= 3
      2758996.65      6848607.40      2758776.00      6849011.00
      2758454.22      6849654.57
#Sta/Elev= 30
  4535.7  499.87  4590.1  497.84  4665.2  493.28  4671.7  491.97  4677.4  492.74
  4693.5  492.04  4709.6  489.82  4715.3  490.21  4737.2  488.72  4753.3  486.70
  4759.0  487.05  4805.5  484.01  4860.3  483.03  4965.8  479.35  5004.1  479.12
  5009.6  476.88  5015.6  472.07  5015.9  471.57  5020.5  472.07  5026.4  479.19
  5058.4  479.25  5097.3  479.43  5188.5  478.44  5265.3  478.91  5367.4  479.39
  5442.9  481.65  5606.4  490.17  5652.5  493.58  5678.0  494.37  5715.2  496.05
#Mann=10,-1,0
  4535.7    0.05       0  4805.5    0.16       0  4860.3    0.12       0
  5015.6    0.07       0  5020.5    0.12       0  5058.4    0.16       0
  5097.3    0.12       0  5265.3    0.16       0  5606.4    0.07       0
  5678.0    0.05       0
Bank Sta=5015.6,5020.5
Exp/Cntr=0.3,0.1

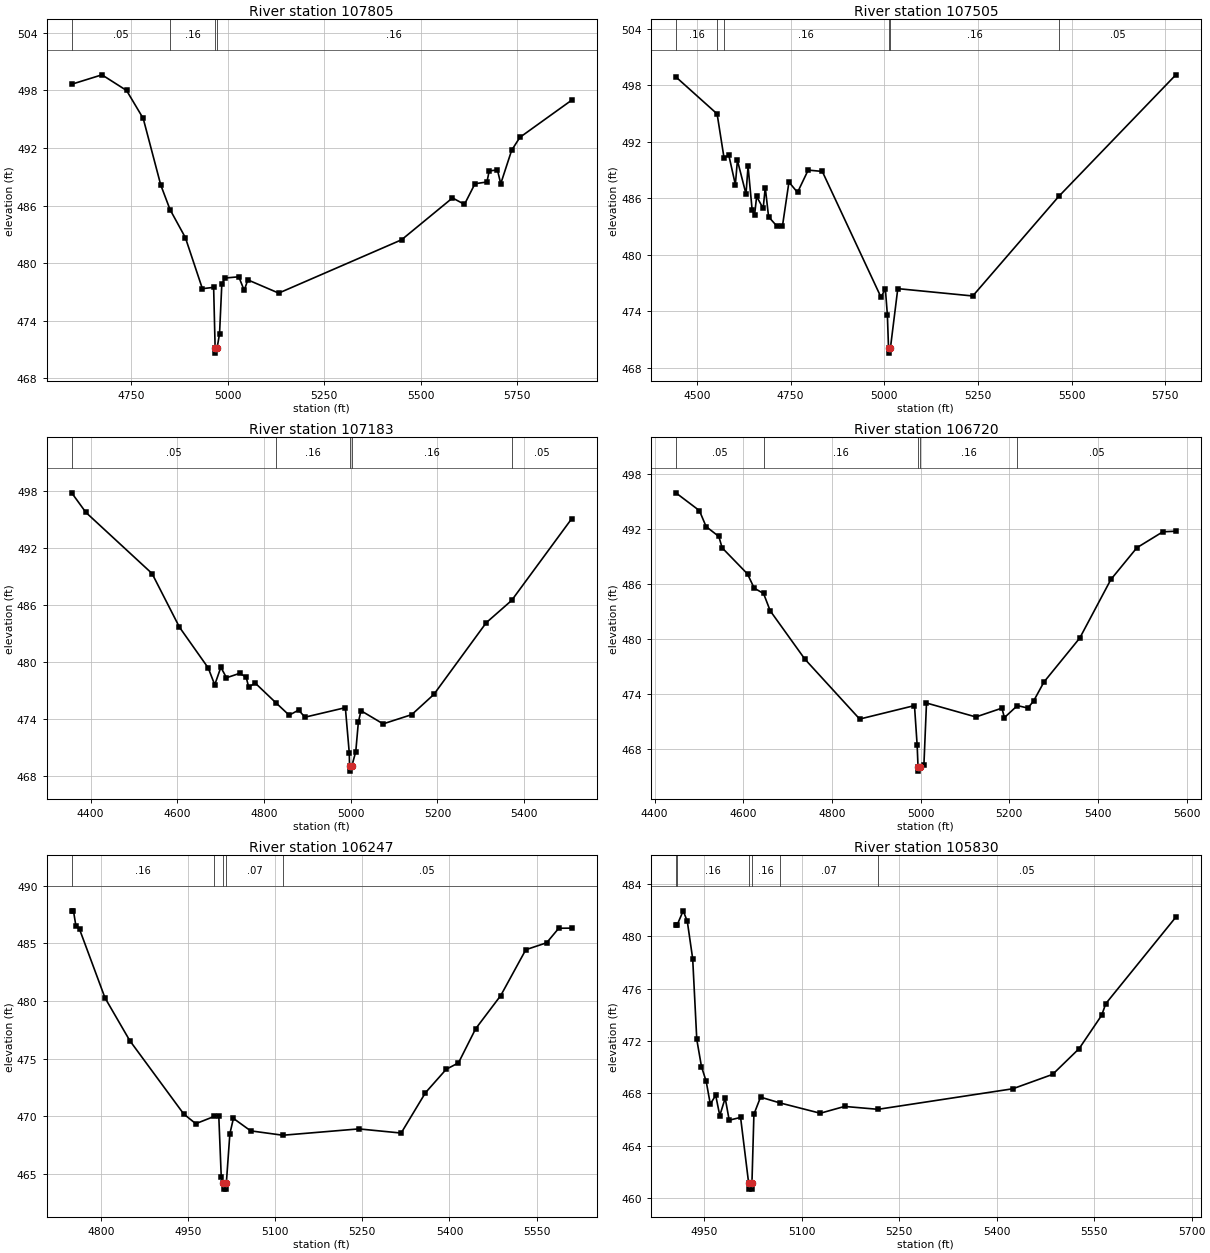
Type RM Length L Ch R = 1,107805,300,300,300
BEGIN DESCRIPTION:
Mapping XS 31f441c4
END DESCRIPTION:
XS GIS Cut Line= 3
      2758775.23      6848503.83      2758558.17      6848851.84
      2758100.02      6849608.02
#Sta/Elev= 30
  4596.2  498.64  4674.6  499.62  4738.3  497.99  4781.4  495.08  4826.8  488.15
  4850.8  485.59  4890.5  482.67  4934.6  477.35  4963.7  477.49  4967.6  471.14
  4967.9  470.64  4972.5  471.14  4979.0  472.66  4984.9  477.85  4993.6  478.46
  5028.8  478.59  5042.9  477.17  5052.1  478.27  5132.1  476.89  5450.1  482.44
  5582.0  486.80  5613.0  486.13  5640.2  488.28  5671.2  488.46  5677.0  489.61
  5698.3  489.72  5706.9  488.28  5735.2  491.77  5756.5  493.11  5890.5  496.98
#Mann=4,-1,0
  4596.2    0.05       0  4850.8    0.16       0  4967.6    0.07       0
  4972.5    0.16       0
Bank Sta=4967.6,4972.5
Exp/Cntr=0.3,0.1

Type RM Length L Ch R = 1,107505,322,322,322
BEGIN DESCRIPTION:
North Twin Creek107637.832
END DESCRIPTION:
XS GIS Cut Line= 3
      2758589.83      6848156.39      2758355.91      6848661.23
      2758002.51      6849354.33
#Sta/Elev= 30
  4443.6  498.87  4553.7  494.94  4572.1  490.29  4585.0  490.54  4602.4  487.43
  4607.9  490.01  4630.8  486.43  4636.3  489.38  4647.1  484.78  4653.7  484.21
  4659.2  486.17  4676.6  484.90  4682.2  487.12  4691.1  484.01  4713.2  483.02
  4728.0  483.00  4745.4  487.70  4768.3  486.60  4796.7  488.97  4834.4  488.83
  4991.1  475.47  5002.7  476.36  5008.1  473.61  5011.2  470.03  5011.6  469.53
  5016.1  470.03  5035.9  476.38  5236.0  475.60  5465.6  486.18  5778.0  499.09
#Mann=6,-1,0
  4443.6    0.16       0  4553.7    0.05       0  4572.1    0.16       0
  5011.2    0.07       0  5016.1    0.16       0  5465.6    0.05       0
Bank Sta=5011.2,5016.1
Exp/Cntr=0.3,0.1

Type RM Length L Ch R = 1,107183,463,463,463
BEGIN DESCRIPTION:
North Twin Creek107165.363
END DESCRIPTION:
XS GIS Cut Line= 3
      2758404.48      6848073.50      2758050.80      6848611.32
      2757767.14      6849034.68
#Sta/Elev= 30
  4356.3  497.77  4389.2  495.71  4541.7  489.30  4604.9  483.67  4671.3  479.39
  4686.3  477.62  4700.4  479.46  4713.4  478.36  4743.6  478.82  4758.6  478.44
  4764.6  477.39  4779.7  477.80  4826.8  475.76  4858.0  474.43  4879.9  474.97
  4894.2  474.22  4987.6  475.22  4996.6  470.48  4997.3  469.06  4997.7  468.56
  5002.3  469.06  5011.6  470.61  5017.6  473.71  5023.7  474.90  5074.7  473.52
  5140.7  474.49  5191.7  476.61  5312.6  484.14  5371.0  486.47  5509.6  495.05
#Mann=5,-1,0
  4356.3    0.05       0  4826.8    0.16       0  4997.3    0.07       0
  5002.3    0.16       0  5371.0    0.05       0
Bank Sta=4997.3,5002.3
Exp/Cntr=0.3,0.1

Type RM Length L Ch R = 1,106720,473,473,473
BEGIN DESCRIPTION:
North Twin Creek106720.421
END DESCRIPTION:
XS GIS Cut Line= 3
      2758129.17      6847800.04      2757826.00      6848261.00
      2757533.82      6848757.38
#Sta/Elev= 30
  4448.0  495.96  4501.1  494.02  4516.2  492.28  4544.9  491.20  4552.4  489.96
  4609.6  487.11  4624.7  485.56  4645.8  484.98  4660.8  483.09  4739.1  477.81
  4862.6  471.28  4986.2  472.75  4992.2  468.44  4994.2  466.10  4994.5  465.60
  4999.3  466.10  5007.5  466.32  5013.3  473.03  5124.7  471.51  5183.3  472.47
  5189.1  471.44  5218.3  472.75  5241.9  472.48  5255.0  473.26  5278.2  475.32
  5359.0  480.12  5429.2  486.51  5487.8  489.97  5546.4  491.71  5575.7  491.77
#Mann=5,-1,0
  4448.0    0.05       0  4645.8    0.16       0  4994.2    0.07       0
  4999.3    0.16       0  5218.3    0.05       0
Bank Sta=4994.2,4999.3
Exp/Cntr=0.3,0.1

Type RM Length L Ch R = 1,106247,417,417,417
BEGIN DESCRIPTION:
North Twin Creek106246.502
END DESCRIPTION:
XS GIS Cut Line= 3
      2757776.00      6847660.99      2757626.00      6847861.00
      2757276.02      6848360.97
#Sta/Elev= 30
  4750.0  487.82  4753.1  487.82  4757.3  486.51  4763.5  486.23  4807.3  480.28
  4850.0  476.57  4942.7  470.22  4963.5  469.37  4995.7  470.01  5003.1  470.08
  5007.4  464.73  5010.9  464.20  5011.3  463.70  5015.7  463.70  5016.1  464.20
  5022.2  468.50  5028.3  469.83  5058.0  468.75  5113.4  468.37  5244.1  468.92
  5316.9  468.56  5358.8  472.06  5394.5  474.09  5415.5  474.64  5445.1  477.60
  5488.3  480.48  5531.4  484.45  5567.2  485.05  5588.1  486.31  5610.3  486.32
#Mann=5,-1,0
  4750.0    0.16       0  4995.7    0.07       0  5010.9    0.07       0
  5016.1    0.07       0  5113.4    0.05       0
Bank Sta=5010.9,5016.1
Exp/Cntr=0.3,0.1

Type RM Length L Ch R = 1,105830,477,477,477
BEGIN DESCRIPTION:
North Twin Creek105828.194
END DESCRIPTION:
XS GIS Cut Line= 3
      2757479.76      6847439.55      2757426.00      6847511.00
      2757287.55      6848176.64
#Sta/Elev= 30
  4906.4  480.87  4908.3  480.87  4917.7  481.96  4924.0  481.16  4932.3  478.30
  4938.6  472.13  4945.8  470.06  4953.1  468.92  4959.4  467.19  4967.7  467.86
  4974.0  466.31  4982.3  467.65  4988.5  465.96  5006.0  466.17  5018.3  461.19
  5018.7  460.69  5023.1  460.69  5023.5  461.19  5026.5  466.41  5036.7  467.72
  5066.5  467.28  5128.6  466.49  5166.0  467.01  5217.5  466.79  5424.8  468.36
  5486.1  469.46  5526.9  471.43  5561.6  473.98  5567.8  474.86  5675.7  481.48
#Mann=6,-1,0
  4906.4    0.07       0  4908.3    0.16       0  5018.3    0.07       0
  5023.5    0.16       0  5066.5    0.07       0  5217.5    0.05       0
Bank Sta=5018.3,5023.5
Exp/Cntr=0.3,0.1

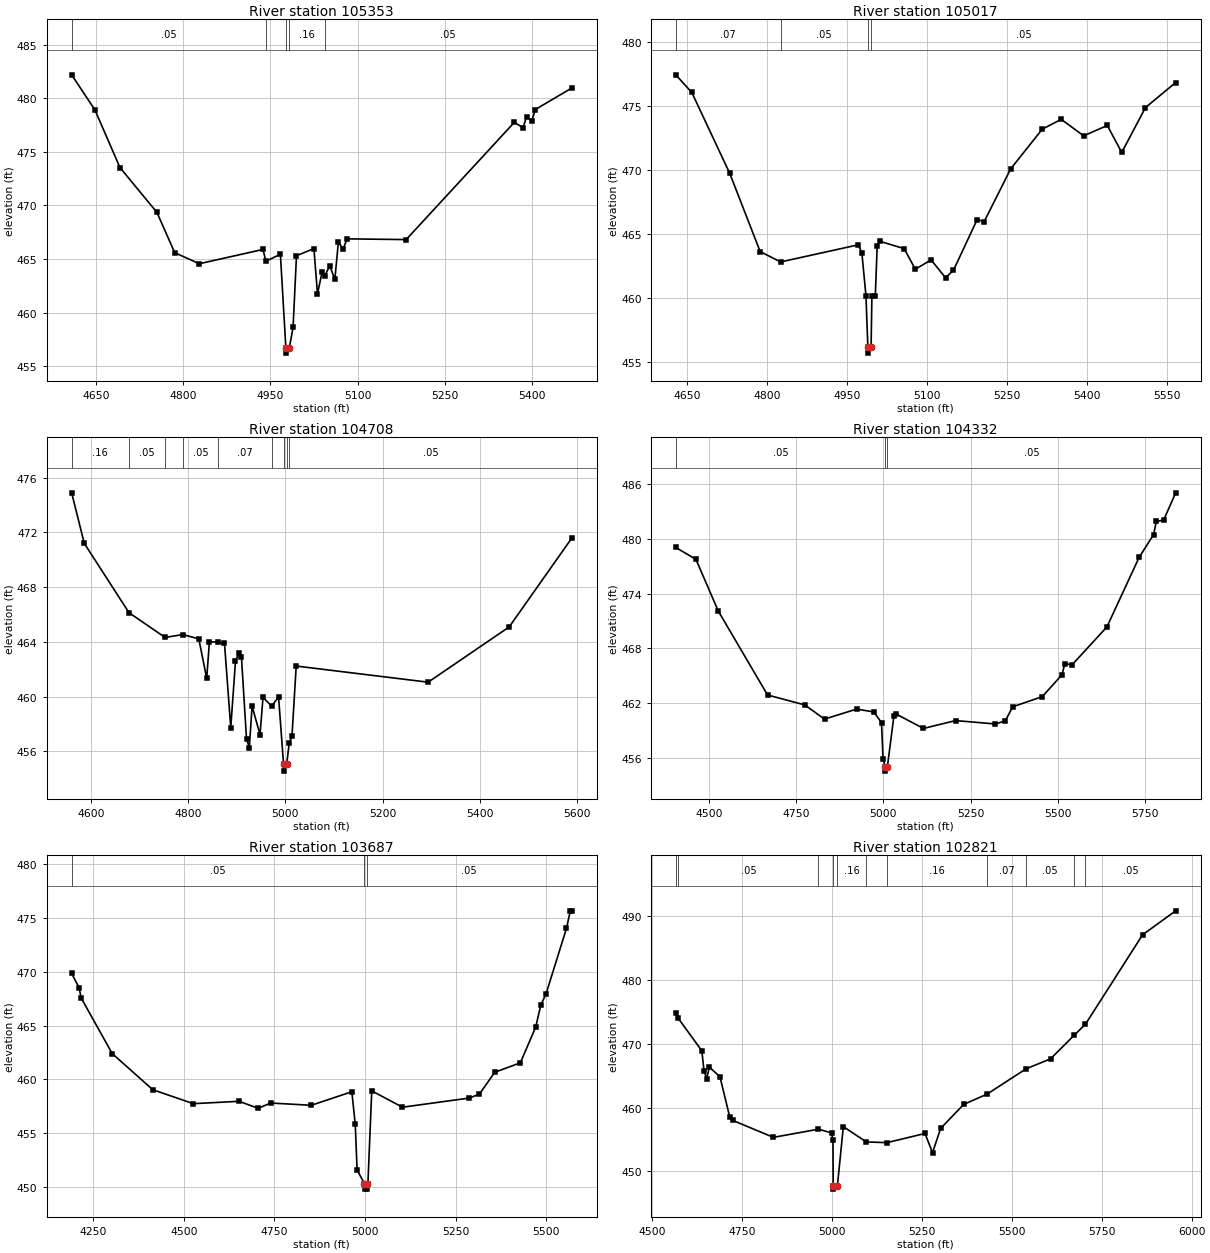
Type RM Length L Ch R = 1,105353,336,336,336
BEGIN DESCRIPTION:
North Twin Creek105387.382
END DESCRIPTION:
XS GIS Cut Line= 3
      2757246.26      6846977.13      2757037.33      6847308.70
      2756775.58      6847697.13
#Sta/Elev= 30
  4608.1  482.18  4648.1  478.91  4691.2  473.53  4754.8  469.35  4785.4  465.59
  4827.8  464.56  4937.3  465.89  4942.3  464.79  4967.3  465.44  4976.7  456.72
  4977.2  456.22  4982.7  456.72  4989.1  458.62  4995.0  465.31  5025.0  465.97
  5031.1  461.75  5039.0  463.76  5043.6  463.40  5052.1  464.38  5061.0  463.10
  5067.1  466.59  5075.1  465.90  5082.0  466.88  5183.7  466.81  5369.9  477.75
  5384.9  477.24  5390.9  478.28  5399.8  477.86  5405.9  478.94  5468.4  480.94
#Mann=5,-1,0
  4608.1    0.05       0  4942.3    0.16       0  4976.7    0.07       0
  4982.7    0.16       0  5043.6    0.05       0
Bank Sta=4976.7,4982.7
Exp/Cntr=0.3,0.1

Type RM Length L Ch R = 1,105017,309,309,309
BEGIN DESCRIPTION:
North Twin Creek104974.667
END DESCRIPTION:
XS GIS Cut Line= 3
      2757049.05      6846811.29      2756804.98      6847091.23
      2756480.55      6847555.38
#Sta/Elev= 30
  4628.6  477.46  4658.7  476.08  4729.9  469.75  4786.9  463.64  4825.3  462.83
  4971.1  464.17  4977.7  463.53  4985.3  460.20  4988.9  456.20  4989.4  455.70
  4995.0  456.20  4996.5  460.19  5002.9  460.19  5006.4  464.09  5012.5  464.43
  5057.0  463.87  5077.9  462.26  5107.6  462.99  5134.6  461.59  5149.4  462.17
  5193.9  466.14  5207.1  465.98  5256.7  470.10  5316.0  473.21  5351.7  473.98
  5393.6  472.69  5438.1  473.50  5465.1  471.39  5509.6  474.90  5566.3  476.86
#Mann=4,-1,0
  4628.6    0.07       0  4825.3    0.05       0  4988.9    0.05       0
  4995.0    0.05       0
Bank Sta=4988.9,4995
Exp/Cntr=0.3,0.1

Type RM Length L Ch R = 1,104708,376,376,376
BEGIN DESCRIPTION:
Mapping XS bf96a647
END DESCRIPTION:
XS GIS Cut Line= 3
      2756903.47      6846493.69      2756693.30      6846886.73
      2756360.74      6847365.69
#Sta/Elev= 30
  4560.3  474.89  4586.2  471.20  4678.3  466.13  4752.6  464.32  4788.8  464.53
  4821.9  464.22  4838.2  461.33  4843.8  464.02  4862.2  463.96  4874.8  463.89
  4887.7  457.73  4897.4  462.57  4904.0  463.18  4909.7  462.89  4920.1  456.93
  4925.9  456.26  4931.6  459.30  4947.9  457.22  4954.1  459.94  4971.9  459.30
  4986.1  459.97  4996.4  455.05  4996.9  454.55  5002.7  455.05  5008.0  456.59
  5013.7  457.11  5022.4  462.23  5293.9  461.05  5460.7  465.09  5589.1  471.56
#Mann=9,-1,0
  4560.3    0.16       0  4678.3    0.05       0  4752.6    0.07       0
  4788.8    0.05       0  4862.2    0.07       0  4971.9    0.12       0
  4996.4    0.07       0  5002.7    0.12       0  5008.0    0.05       0
Bank Sta=4996.4,5002.7
Exp/Cntr=0.3,0.1

Type RM Length L Ch R = 1,104332,645,645,645
BEGIN DESCRIPTION:
North Twin Creek104150.813
END DESCRIPTION:
XS GIS Cut Line= 3
      2756830.54      6846314.41      2756384.21      6846707.28
      2755836.21      6847339.67
#Sta/Elev= 30
  4405.4  479.04  4463.2  477.74  4526.8  472.11  4668.2  462.90  4774.4  461.82
  4831.3  460.26  4923.4  461.36  4972.7  461.04  4994.5  459.87  4999.0  455.86
  5005.1  455.07  5005.6  454.57  5011.4  455.07  5030.1  460.63  5036.7  460.81
  5114.6  459.24  5206.7  460.10  5320.7  459.73  5349.0  460.07  5370.1  461.61
  5454.8  462.72  5511.6  465.13  5519.2  466.34  5540.1  466.20  5639.9  470.35
  5732.0  477.95  5773.7  480.46  5781.3  481.89  5802.2  482.03  5836.8  485.02
#Mann=3,-1,0
  4405.4    0.05       0  5005.1    0.05       0  5011.4    0.05       0
Bank Sta=5005.1,5011.4
Exp/Cntr=0.3,0.1

Type RM Length L Ch R = 1,103687,866,866,866
BEGIN DESCRIPTION:
North Twin Creek103686.916
END DESCRIPTION:
XS GIS Cut Line= 3
      2756676.00      6846261.00      2755876.00      6846411.00
      2755476.02      6846810.98
#Sta/Elev= 30
  4190.5  469.86  4210.8  468.54  4216.8  467.57  4302.4  462.40  4414.3  459.04
  4526.2  457.74  4652.6  457.96  4705.1  457.31  4739.9  457.80  4851.8  457.59
  4963.7  458.85  4973.1  455.82  4978.2  451.57  4998.6  450.29  4999.1  449.79
  5004.6  449.79  5005.1  450.29  5008.0  450.29  5018.6  458.93  5103.4  457.41
  5287.3  458.26  5315.6  458.62  5358.0  460.66  5428.7  461.54  5471.1  464.87
  5485.3  466.93  5499.4  467.93  5556.0  474.05  5566.6  475.68  5570.1  475.68
#Mann=3,-1,0
  4190.5    0.05       0  4998.6    0.05       0  5005.1    0.05       0
Bank Sta=4998.6,5005.1
Exp/Cntr=0.3,0.1

Type RM Length L Ch R = 1,102821,554,554,554
BEGIN DESCRIPTION:
North Twin Creek102820.706
END DESCRIPTION:
XS GIS Cut Line= 3
      2755826.00      6845361.01      2755576.00      6845711.00
      2754975.99      6846461.02
#Sta/Elev= 30
  4565.0  474.77  4572.2  473.98  4637.5  468.91  4643.6  465.77  4651.0  464.55
  4658.4  466.35  4687.9  464.84  4714.9  458.57  4723.5  457.99  4836.6  455.33
  4961.9  456.61  4998.3  456.03  5002.3  454.88  5002.9  447.71  5003.4  447.21
  5014.6  447.71  5031.1  457.01  5095.3  454.61  5152.5  454.50  5258.4  455.94
  5279.2  452.92  5301.7  456.72  5365.7  460.49  5430.9  462.11  5539.7  466.09
  5607.4  467.64  5672.8  471.32  5704.7  473.08  5863.5  487.10  5955.6  490.86
#Mann=11,-1,0
  4565.0    0.16       0  4572.2    0.05       0  4961.9    0.16       0
  5002.9    0.07       0  5014.6    0.16       0  5095.3    0.05       0
  5152.5    0.16       0  5430.9    0.07       0  5539.7    0.05       0
  5672.8    0.07       0  5704.7    0.05       0
Bank Sta=5002.9,5014.6
Exp/Cntr=0.3,0.1