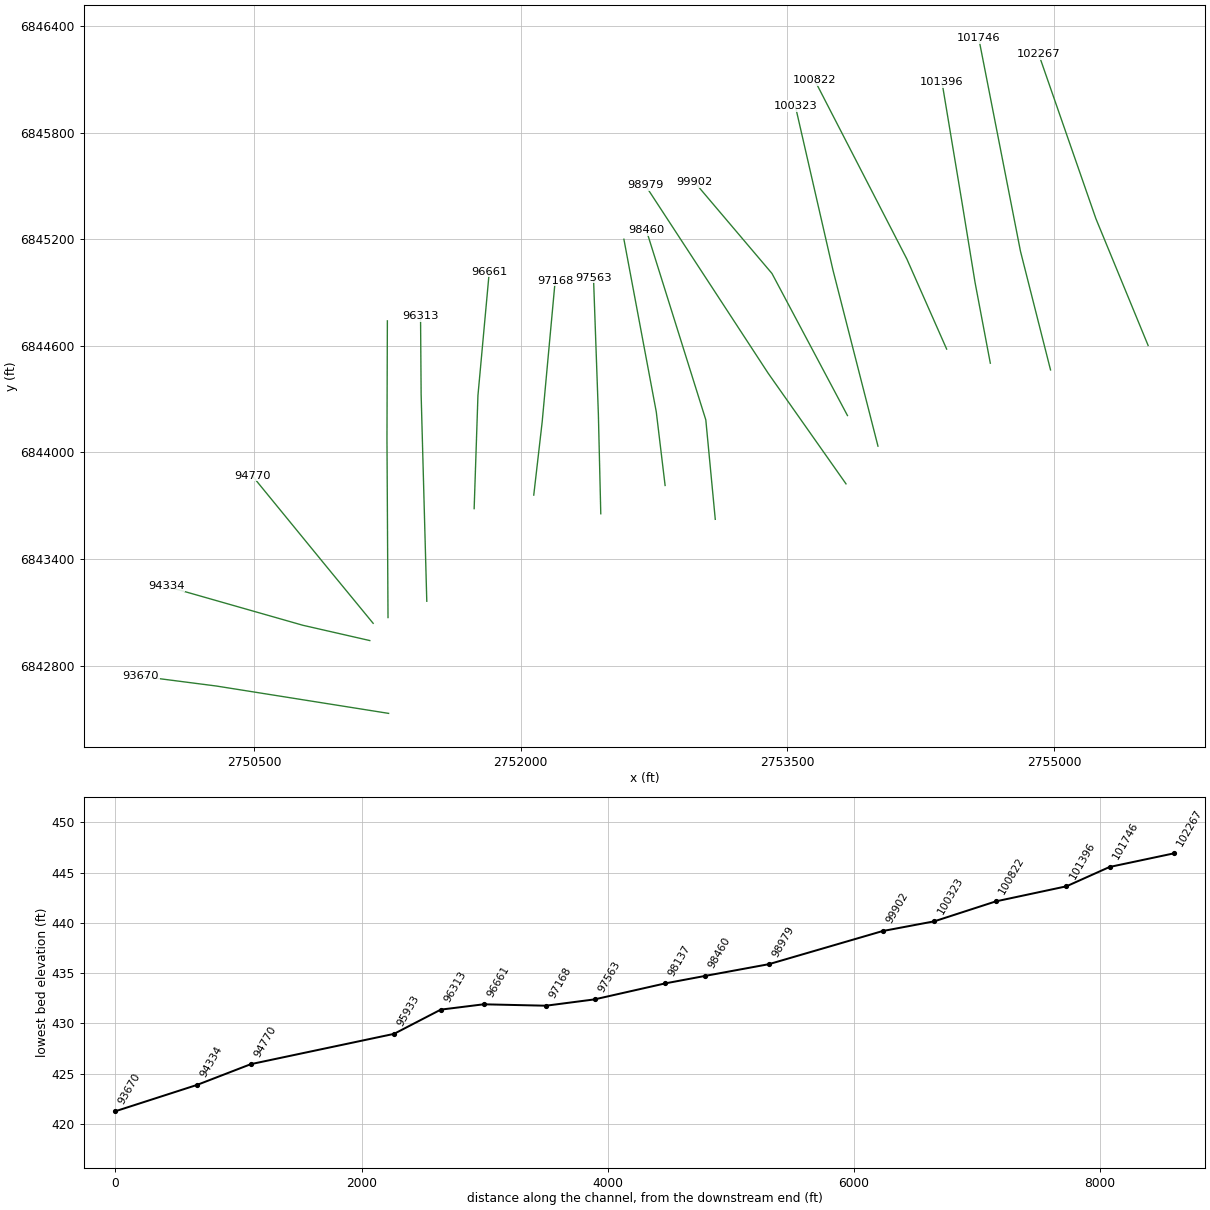
HEC-RAS study North Twin Creek.prj: North Twin Creek Base Level Engineering

--- North Twin Creek.g01 (geometry) --- (continued)

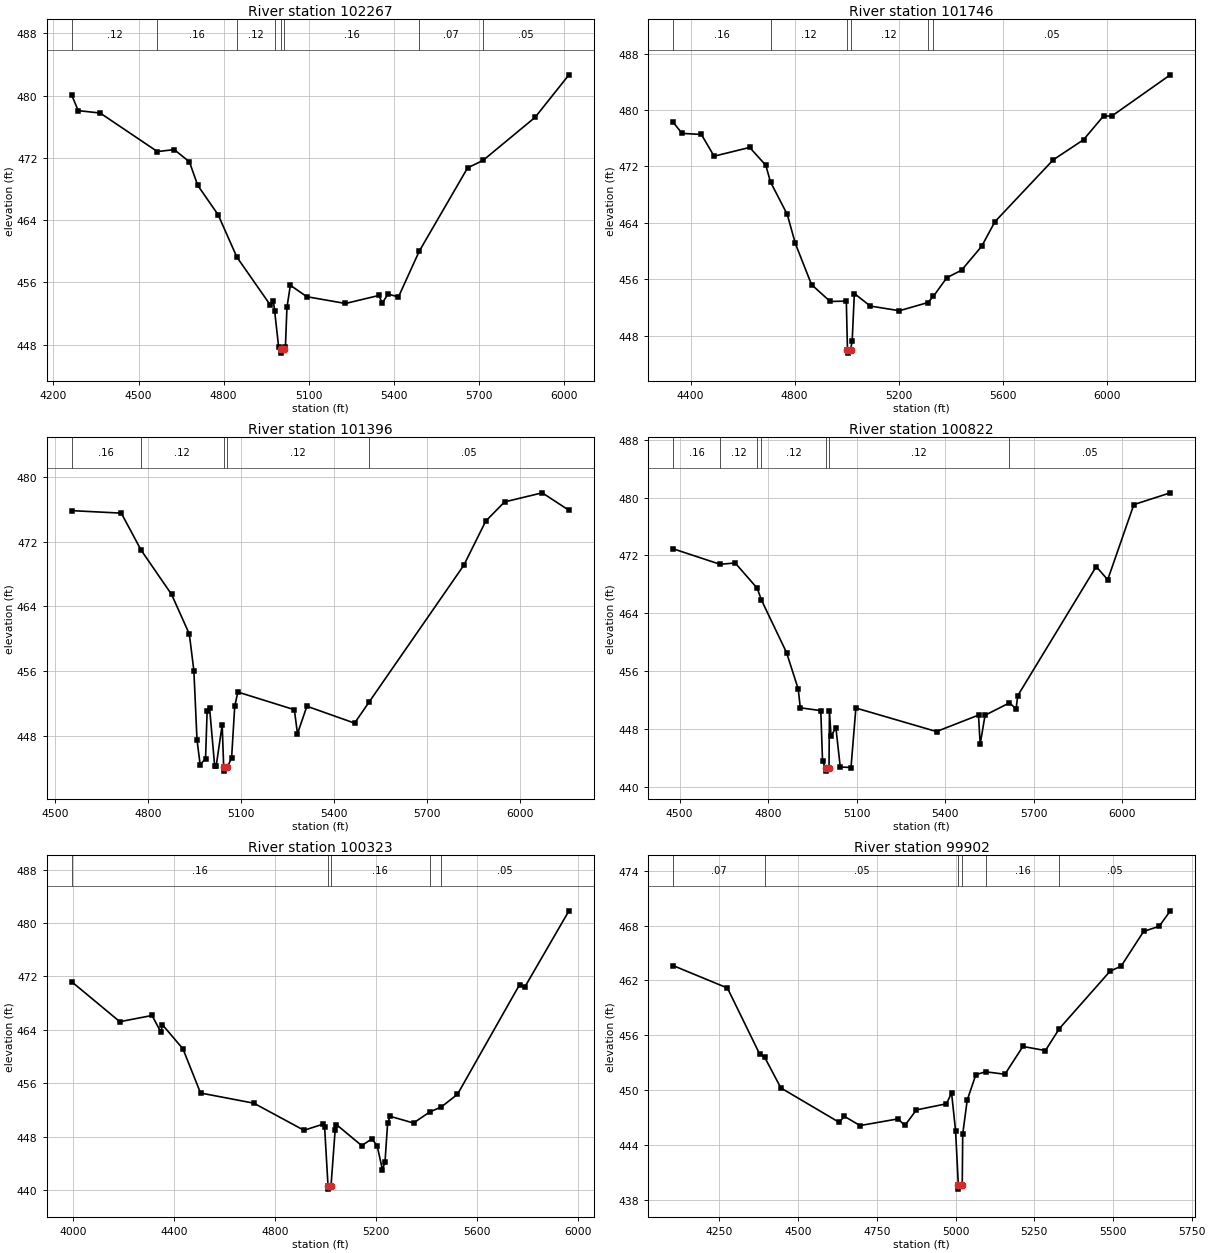
Type RM Length L Ch R = 1,102267,521,521,521
BEGIN DESCRIPTION:
North Twin Creek102266.69
END DESCRIPTION:
XS GIS Cut Line= 3
      2755529.49      6844602.99      2755235.99      6845316.34
      2754913.83      6846243.71
#Sta/Elev= 30
  4264.0  480.11  4287.6  478.06  4364.9  477.75  4566.5  472.80  4626.0  473.05
  4679.4  471.48  4708.7  468.46  4780.6  464.68  4846.7  459.24  4964.5  453.08
  4975.5  453.54  4979.8  452.32  4993.8  447.72  5002.1  447.40  5002.6  446.90
  5013.9  447.40  5017.8  447.73  5023.2  452.77  5035.2  455.62  5093.2  454.15
  5229.5  453.28  5347.3  454.31  5359.2  453.33  5379.1  454.49  5416.2  454.12
  5489.4  459.99  5659.8  470.70  5714.5  471.67  5897.8  477.20  6017.1  482.66
#Mann=8,-1,0
  4264.0    0.12       0  4566.5    0.16       0  4846.7    0.12       0
  4979.8    0.16       0  5002.1    0.07       0  5013.9    0.16       0
  5489.4    0.07       0  5714.5    0.05       0
Bank Sta=5002.1,5013.9
Exp/Cntr=0.3,0.1

Type RM Length L Ch R = 1,101746,350,350,350
BEGIN DESCRIPTION:
North Twin Creek101746.27
END DESCRIPTION:
XS GIS Cut Line= 3
      2754980.51      6844464.98      2754811.52      6845132.86
      2754576.78      6846332.49
#Sta/Elev= 30
  4332.1  478.31  4367.5  476.69  4441.5  476.54  4490.5  473.46  4627.1  474.70
  4689.0  472.18  4707.2  469.80  4771.5  465.21  4802.5  461.10  4864.8  455.26
  4936.5  452.87  4998.5  452.92  5002.9  446.05  5003.4  445.55  5014.7  446.05
  5021.0  447.25  5029.3  454.00  5090.5  452.22  5202.5  451.56  5312.1  452.72
  5333.3  453.61  5384.6  456.24  5441.2  457.30  5518.4  460.68  5569.4  464.17
  5793.5  472.94  5909.9  475.79  5987.1  479.17  6018.0  479.13  6243.4  484.99
#Mann=6,-1,0
  4332.1    0.16       0  4707.2    0.12       0  5002.9    0.07       0
  5014.7    0.12       0  5312.1    0.16       0  5333.3    0.05       0
Bank Sta=5002.9,5014.7
Exp/Cntr=0.3,0.1

Type RM Length L Ch R = 1,101396,574,574,574
BEGIN DESCRIPTION:
North Twin Creek101395.5
END DESCRIPTION:
XS GIS Cut Line= 4
      2754641.72      6844502.81      2754555.76      6844957.92
      2754483.27      6845402.97      2754369.76      6846086.03
#Sta/Elev= 30
  4552.4  475.82  4713.1  475.51  4776.9  470.95  4875.4  465.47  4932.8  460.57
  4947.5  456.04  4957.6  447.49  4967.8  444.43  4985.2  445.16  4990.3  451.08
  4998.3  451.40  5014.6  444.30  5019.7  444.30  5038.9  449.34  5043.8  444.13
  5044.3  443.63  5055.6  444.13  5069.3  445.25  5079.5  451.66  5089.6  453.40
  5272.0  451.22  5282.1  448.25  5312.5  451.65  5466.5  449.56  5513.7  452.18
  5819.3  469.07  5890.2  474.53  5951.1  476.90  6072.7  478.02  6158.9  475.86
#Mann=5,-1,0
  4552.4    0.16       0  4776.9    0.12       0  5043.8    0.07       0
  5055.6    0.12       0  5513.7    0.05       0
Bank Sta=5043.8,5055.6
Exp/Cntr=0.3,0.1

Type RM Length L Ch R = 1,100822,499,499,499
BEGIN DESCRIPTION:
North Twin Creek100821.71
END DESCRIPTION:
XS GIS Cut Line= 3
      2754395.96      6844582.42      2754172.12      6845089.64
      2753654.19      6846095.40
#Sta/Elev= 30
  4477.5  472.93  4637.5  470.77  4688.5  470.96  4763.2  467.46  4777.5  465.83
  4862.6  458.55  4902.2  453.51  4909.3  450.90  4978.7  450.51  4984.7  443.47
  4994.7  442.63  4995.2  442.13  5006.6  442.63  5008.0  450.43  5013.5  446.99
  5029.9  448.14  5044.7  442.70  5081.1  442.63  5097.6  450.87  5370.9  447.61
  5513.2  449.89  5518.8  445.84  5535.4  449.87  5618.0  451.58  5640.6  450.76
  5646.2  452.58  5912.2  470.46  5951.0  468.63  6039.6  479.04  6163.2  480.67
#Mann=7,-1,0
  4477.5    0.16       0  4637.5    0.12       0  4763.2    0.16       0
  4777.5    0.12       0  4994.7    0.07       0  5006.6    0.12       0
  5618.0    0.05       0
Bank Sta=4994.7,5006.6
Exp/Cntr=0.3,0.1

Type RM Length L Ch R = 1,100323,421,421,421
BEGIN DESCRIPTION:
North Twin Creek100322.87
END DESCRIPTION:
XS GIS Cut Line= 3
      2754009.64      6844035.52      2753756.47      6845026.86
      2753544.57      6845951.74
#Sta/Elev= 30
  3992.9  471.22  4184.3  465.22  4312.0  466.15  4347.7  463.62  4352.9  464.78
  4434.6  461.15  4504.3  454.54  4715.4  453.02  4914.4  448.96  4989.4  449.87
  4996.1  449.50  5009.7  440.65  5010.2  440.15  5021.6  440.65  5038.1  449.06
  5043.2  449.81  5143.4  446.66  5184.4  447.70  5205.0  446.55  5225.5  443.05
  5235.7  444.24  5246.0  450.05  5256.3  451.05  5348.6  450.05  5412.8  451.70
  5458.7  452.45  5523.0  454.35  5769.2  470.77  5789.7  470.40  5964.9  481.82
#Mann=5,-1,0
  3992.9    0.16       0  5009.7    0.07       0  5021.6    0.16       0
  5412.8    0.12       0  5458.7    0.05       0
Bank Sta=5009.7,5021.6
Exp/Cntr=0.3,0.1

Type RM Length L Ch R = 1,99902,923,923,923
BEGIN DESCRIPTION:
North Twin Creek99902.41
END DESCRIPTION:
XS GIS Cut Line= 3
      2753837.99      6844207.98      2753413.19      6845008.16
      2752977.68      6845522.37
#Sta/Elev= 30
  4102.4  463.63  4275.6  461.17  4378.2  453.93  4393.8  453.60  4445.5  450.24
  4630.7  446.48  4647.0  447.14  4696.7  446.13  4817.3  446.86  4839.2  446.14
  4875.7  447.84  4971.2  448.51  4987.5  449.70  5000.2  445.56  5008.9  439.68
  5009.4  439.18  5021.4  439.68  5022.9  445.20  5037.2  448.92  5064.6  451.69
  5095.6  452.01  5156.9  451.74  5214.0  454.78  5285.5  454.33  5329.8  456.73
  5490.9  463.01  5526.0  463.56  5597.5  467.36  5646.9  467.92  5682.2  469.61
#Mann=6,-1,0
  4102.4    0.07       0  4393.8    0.05       0  5008.9    0.05       0
  5021.4    0.05       0  5095.6    0.16       0  5329.8    0.05       0
Bank Sta=5008.9,5021.4
Exp/Cntr=0.3,0.1

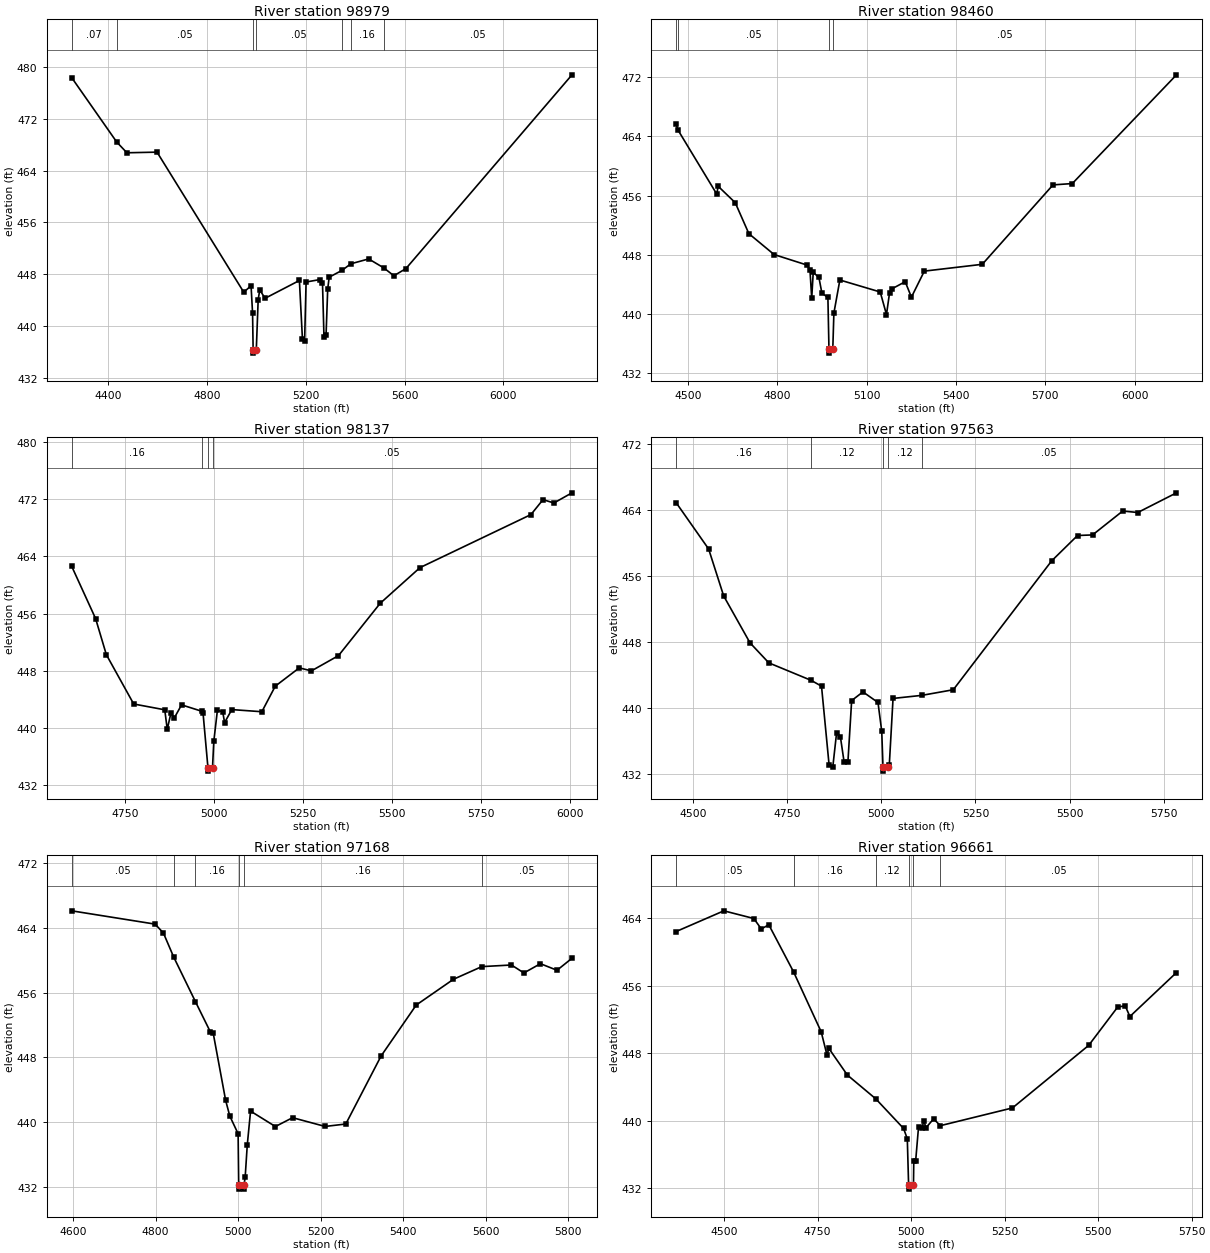
Type RM Length L Ch R = 1,98979,519,519,519
BEGIN DESCRIPTION:
North Twin Creek98978.53
END DESCRIPTION:
XS GIS Cut Line= 3
      2753829.72      6843823.27      2753391.54      6844446.53
      2752700.74      6845504.86
#Sta/Elev= 30
  4252.4  478.30  4434.9  468.38  4476.0  466.73  4598.0  466.83  4949.1  445.27
  4978.7  446.26  4984.8  442.06  4987.1  436.39  4987.6  435.89  4999.9  436.39
  5007.5  444.12  5013.9  445.62  5035.5  444.33  5174.4  447.07  5186.8  438.01
  5195.5  437.72  5201.5  446.84  5258.8  447.22  5267.9  446.74  5273.9  438.41
  5282.3  438.61  5289.0  445.73  5295.0  447.58  5347.4  448.64  5382.6  449.64
  5454.9  450.39  5515.8  449.02  5557.0  447.80  5605.7  448.90  6278.1  478.73
#Mann=7,-1,0
  4252.4    0.07       0  4434.9    0.05       0  4987.1    0.07       0
  4999.9    0.05       0  5347.4    0.05       0  5382.6    0.16       0
  5515.8    0.05       0
Bank Sta=4987.1,4999.9
Exp/Cntr=0.3,0.1

Type RM Length L Ch R = 1,98460,323,323,323
BEGIN DESCRIPTION:
North Twin Creek98460.27
END DESCRIPTION:
XS GIS Cut Line= 3
      2753094.17      6843623.60      2753040.95      6844183.46
      2752706.64      6845250.85
#Sta/Elev= 30
  4460.1  465.66  4465.5  464.90  4596.2  456.22  4601.2  457.26  4658.4  455.05
  4704.3  450.86  4789.0  448.04  4899.5  446.62  4909.5  445.98  4915.4  442.14
  4920.5  445.63  4939.6  444.94  4949.7  442.82  4969.8  442.24  4973.4  435.22
  4973.9  434.72  4986.2  435.22  4989.9  440.13  5010.0  444.60  5145.6  442.98
  5166.6  439.93  5177.1  442.91  5186.0  443.43  5229.5  444.37  5250.4  442.28
  5293.8  445.80  5488.5  446.72  5726.1  457.45  5791.0  457.63  6141.0  472.32
#Mann=4,-1,0
  4460.1    0.07       0  4465.5    0.05       0  4973.4    0.05       0
  4986.2    0.05       0
Bank Sta=4973.4,4986.2
Exp/Cntr=0.3,0.1

Type RM Length L Ch R = 1,98137,574,574,574
BEGIN DESCRIPTION:
North Twin Creek98136.68
END DESCRIPTION:
XS GIS Cut Line= 3
      2752811.92      6843814.22      2752762.23      6844228.67
      2752580.05      6845201.03
#Sta/Elev= 30
  4599.6  462.61  4666.9  455.29  4697.1  450.25  4774.0  443.36  4861.3  442.55
  4868.3  439.82  4878.4  442.04  4888.4  441.44  4908.6  443.24  4966.5  442.33
  4969.0  442.07  4982.7  434.48  4983.2  433.98  4995.6  434.48  4999.2  438.14
  5009.3  442.47  5024.1  442.29  5029.6  440.77  5049.9  442.58  5134.3  442.28
  5172.0  445.85  5239.5  448.41  5273.7  447.99  5349.8  450.12  5467.0  457.43
  5579.0  462.42  5890.9  469.83  5924.9  471.92  5955.4  471.45  6006.3  472.87
#Mann=4,-1,0
  4599.6    0.16       0  4966.5    0.05       0  4982.7    0.05       0
  4995.6    0.05       0
Bank Sta=4982.7,4995.6
Exp/Cntr=0.3,0.1

Type RM Length L Ch R = 1,97563,395,395,395
BEGIN DESCRIPTION:
North Twin Creek97562.73
END DESCRIPTION:
XS GIS Cut Line= 3
      2752450.00      6843654.86      2752436.44      6844215.59
      2752409.04      6844983.81
#Sta/Elev= 30
  4454.6  464.84  4540.8  459.25  4580.8  453.57  4650.8  447.90  4700.8  445.48
  4813.5  443.36  4840.8  442.66  4860.9  433.16  4870.9  432.94  4880.9  437.03
  4890.9  436.57  4900.9  433.47  4910.9  433.45  4920.9  440.92  4950.9  441.97
  4990.9  440.69  5000.9  437.19  5004.2  432.89  5004.7  432.39  5017.1  432.89
  5020.9  433.10  5030.9  441.18  5107.2  441.55  5191.0  442.23  5452.4  457.81
  5521.2  460.88  5561.2  460.95  5641.3  463.84  5681.3  463.66  5784.2  466.04
#Mann=5,-1,0
  4454.6    0.16       0  4813.5    0.12       0  5004.2    0.07       0
  5017.1    0.12       0  5107.2    0.05       0
Bank Sta=5004.2,5017.1
Exp/Cntr=0.3,0.1

Type RM Length L Ch R = 1,97168,507,507,507
BEGIN DESCRIPTION:
North Twin Creek97167.77
END DESCRIPTION:
XS GIS Cut Line= 3
      2752072.87      6843760.03      2752120.21      6844171.58
      2752193.38      6844967.15
#Sta/Elev= 30
  4596.5  466.08  4798.8  464.44  4818.9  463.35  4843.7  460.40  4896.5  454.89
  4932.4  451.19  4939.7  450.99  4969.9  442.69  4980.0  440.76  5000.1  438.59
  5001.5  432.26  5002.0  431.76  5014.0  431.76  5014.5  432.26  5017.3  433.31
  5022.3  437.22  5030.3  441.38  5090.5  439.48  5132.2  440.57  5211.0  439.49
  5261.2  439.79  5346.8  448.18  5432.0  454.46  5522.3  457.64  5591.0  459.20
  5662.9  459.40  5693.1  458.42  5733.2  459.56  5773.4  458.75  5809.7  460.23
#Mann=6,-1,0
  4596.5    0.05       0  4843.7    0.12       0  4896.5    0.16       0
  5001.5    0.07       0  5014.5    0.16       0  5591.0    0.05       0
Bank Sta=5001.5,5014.5
Exp/Cntr=0.3,0.1

Type RM Length L Ch R = 1,96661,348,348,348
BEGIN DESCRIPTION:
North Twin Creek96661.46
END DESCRIPTION:
XS GIS Cut Line= 3
      2751737.50      6843683.64      2751758.83      6844320.64
      2751822.58      6845017.57
#Sta/Elev= 30
  4372.3  462.42  4499.7  464.87  4579.8  463.96  4599.8  462.72  4619.8  463.22
  4686.0  457.64  4759.9  450.53  4775.3  447.79  4780.3  448.57  4829.9  445.41
  4905.9  442.59  4980.0  439.09  4990.0  437.86  4993.5  432.40  4994.0  431.90
  5006.5  432.40  5007.3  435.22  5012.3  435.22  5020.1  439.30  5029.3  439.15
  5034.3  439.95  5040.1  439.18  5060.2  440.22  5078.5  439.42  5271.1  441.52
  5474.8  448.93  5552.3  453.47  5572.4  453.62  5584.9  452.35  5709.5  457.56
#Mann=6,-1,0
  4372.3    0.05       0  4686.0    0.16       0  4905.9    0.12       0
  4993.5    0.07       0  5006.5    0.12       0  5078.5    0.05       0
Bank Sta=4993.5,5006.5
Exp/Cntr=0.3,0.1

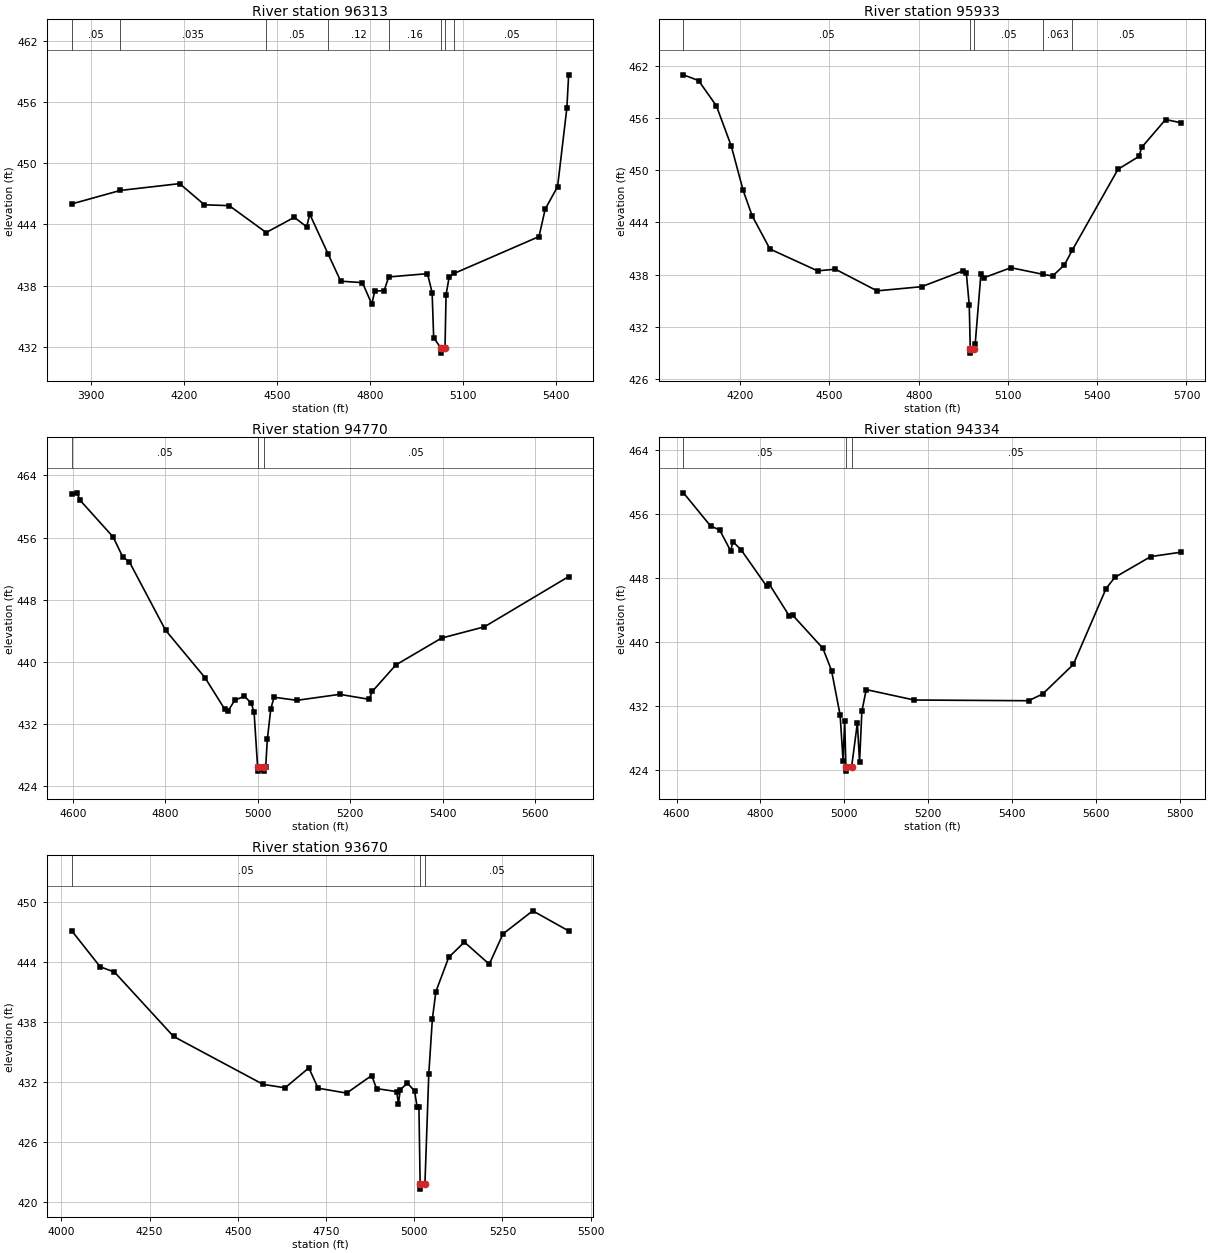
Type RM Length L Ch R = 1,96313,380,380,380
BEGIN DESCRIPTION:
North Twin Creek96312.89
END DESCRIPTION:
XS GIS Cut Line= 3
      2751471.00      6843161.99      2751439.21      6844325.91
      2751435.89      6844766.74
#Sta/Elev= 30
  3836.7  446.01  3994.0  447.34  4185.8  448.01  4265.9  445.93  4345.9  445.85
  4465.2  443.21  4556.0  444.70  4596.0  443.77  4606.0  445.01  4665.1  441.11
  4706.0  438.43  4776.1  438.29  4806.1  436.19  4816.1  437.47  4846.1  437.50
  4860.9  438.85  4986.1  439.17  5001.1  437.31  5006.1  432.88  5029.5  431.87
  5030.0  431.37  5042.7  431.87  5046.1  437.10  5056.1  438.84  5072.6  439.20
  5346.2  442.81  5366.2  445.51  5406.2  447.71  5436.2  455.44  5441.9  458.69
#Mann=8,-1,0
  3836.7    0.05       0  3994.0   0.035       0  4465.2    0.05       0
  4665.1    0.12       0  4860.9    0.16       0  5029.5    0.07       0
  5042.7    0.16       0  5072.6    0.05       0
Bank Sta=5029.5,5042.7
Exp/Cntr=0.3,0.1

Type RM Length L Ch R = 1,95933,1163,1163,1163
BEGIN DESCRIPTION:
North Twin Creek95933.24
END DESCRIPTION:
XS GIS Cut Line= 3
      2751252.87      6843070.17      2751246.97      6844074.48
      2751249.23      6844741.25
#Sta/Elev= 30
  4009.1  460.96  4059.9  460.30  4119.9  457.39  4169.9  452.77  4209.9  447.66
  4239.9  444.76  4299.9  440.93  4459.9  438.42  4519.9  438.61  4659.9  436.12
  4809.9  436.60  4949.9  438.43  4959.9  438.23  4969.9  434.46  4973.3  429.46
  4973.8  428.96  4986.5  429.46  4989.9  430.04  5009.2  438.11  5019.9  437.64
  5109.9  438.78  5218.0  438.02  5249.9  437.82  5289.9  439.11  5315.9  440.78
  5469.9  450.10  5539.9  451.57  5549.9  452.63  5629.9  455.82  5680.2  455.46
#Mann=5,-1,0
  4009.1    0.05       0  4973.3    0.05       0  4986.5    0.05       0
  5218.0   0.063       0  5315.9    0.05       0
Bank Sta=4973.3,4986.5
Exp/Cntr=0.3,0.1

Type RM Length L Ch R = 1,94770,436,436,436
BEGIN DESCRIPTION:
North Twin Creek94769.88
END DESCRIPTION:
XS GIS Cut Line= 3
      2751169.20      6843037.82      2750904.31      6843360.49
      2750488.04      6843869.99
#Sta/Elev= 30
  4597.4  461.63  4609.2  461.76  4615.6  460.82  4687.4  456.08  4708.2  453.51
  4722.5  452.88  4800.7  444.09  4886.1  437.98  4928.5  433.95  4936.4  433.72
  4950.7  435.09  4971.5  435.58  4985.9  434.72  4992.3  433.53  5000.0  426.45
  5000.5  425.95  5012.9  425.95  5013.4  426.45  5017.5  426.52  5021.0  430.04
  5028.4  433.92  5035.4  435.46  5084.9  435.06  5177.5  435.83  5241.4  435.19
  5248.0  436.20  5298.9  439.61  5397.9  443.07  5490.6  444.52  5672.8  450.98
#Mann=3,-1,0
  4597.4    0.05       0  5000.0    0.05       0  5013.4    0.05       0
Bank Sta=5000,5013.4
Exp/Cntr=0.3,0.1

Type RM Length L Ch R = 1,94334,664,664,664
BEGIN DESCRIPTION:
North Twin Creek94334.39
END DESCRIPTION:
XS GIS Cut Line= 3
      2751150.27      6842940.69      2750773.55      6843026.85
      2750005.09      6843246.21
#Sta/Elev= 30
  4616.4  458.64  4681.1  454.50  4702.8  454.00  4729.2  451.37  4734.3  452.55
  4754.1  451.51  4815.1  446.96  4820.2  447.31  4868.3  443.31  4877.2  443.35
  4949.0  439.22  4969.6  436.45  4990.1  430.89  4997.1  425.17  5000.9  430.20
  5003.9  424.39  5004.4  423.89  5017.4  424.39  5031.2  429.91  5036.4  424.98
  5041.9  431.34  5052.3  434.07  5166.7  432.77  5439.6  432.68  5473.4  433.53
  5546.2  437.21  5624.3  446.68  5645.1  448.08  5730.9  450.68  5802.0  451.22
#Mann=3,-1,0
  4616.4    0.05       0  5003.9    0.05       0  5017.4    0.05       0
Bank Sta=5003.9,5017.4
Exp/Cntr=0.3,0.1

Type RM Length L Ch R = 1,93670,433,433,433
BEGIN DESCRIPTION:
Mapping XS c92c90db
END DESCRIPTION:
XS GIS Cut Line= 3
      2751256.15      6842530.56      2750286.59      6842684.67
      2749862.94      6842739.39
#Sta/Elev= 30
  4028.7  447.15  4109.9  443.52  4150.4  442.99  4317.8  436.55  4571.8  431.75
  4634.0  431.41  4701.3  433.40  4727.5  431.37  4808.5  430.88  4879.4  432.64
  4893.1  431.33  4950.2  431.03  4955.3  429.82  4960.4  431.22  4980.7  431.88
  5000.9  431.09  5008.2  429.50  5013.3  429.50  5016.7  421.77  5017.2  421.27
  5030.3  421.77  5041.3  432.84  5051.4  438.30  5061.4  441.04  5097.8  444.47
  5142.1  445.99  5212.7  443.78  5251.5  446.81  5335.9  449.12  5437.6  447.11
#Mann=3,-1,0
  4028.7    0.05       0  5016.7    0.05       0  5030.3    0.05       0
Bank Sta=5016.7,5030.3
Exp/Cntr=0.3,0.1