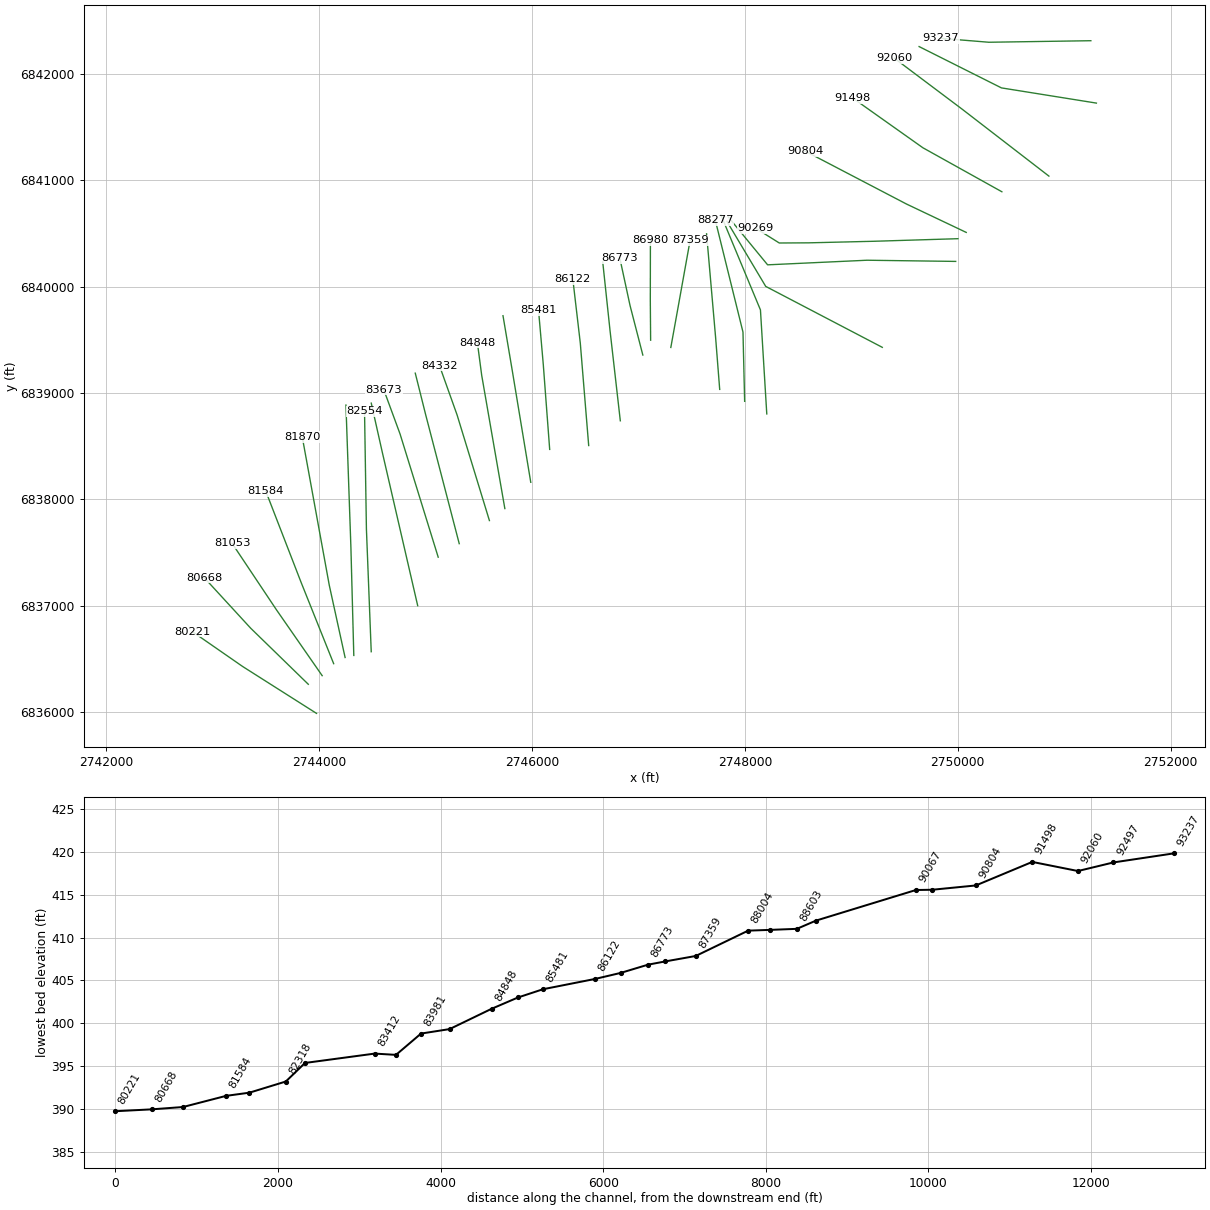
HEC-RAS study North Twin Creek.prj: North Twin Creek Base Level Engineering

--- North Twin Creek.g01 (geometry) --- (continued)

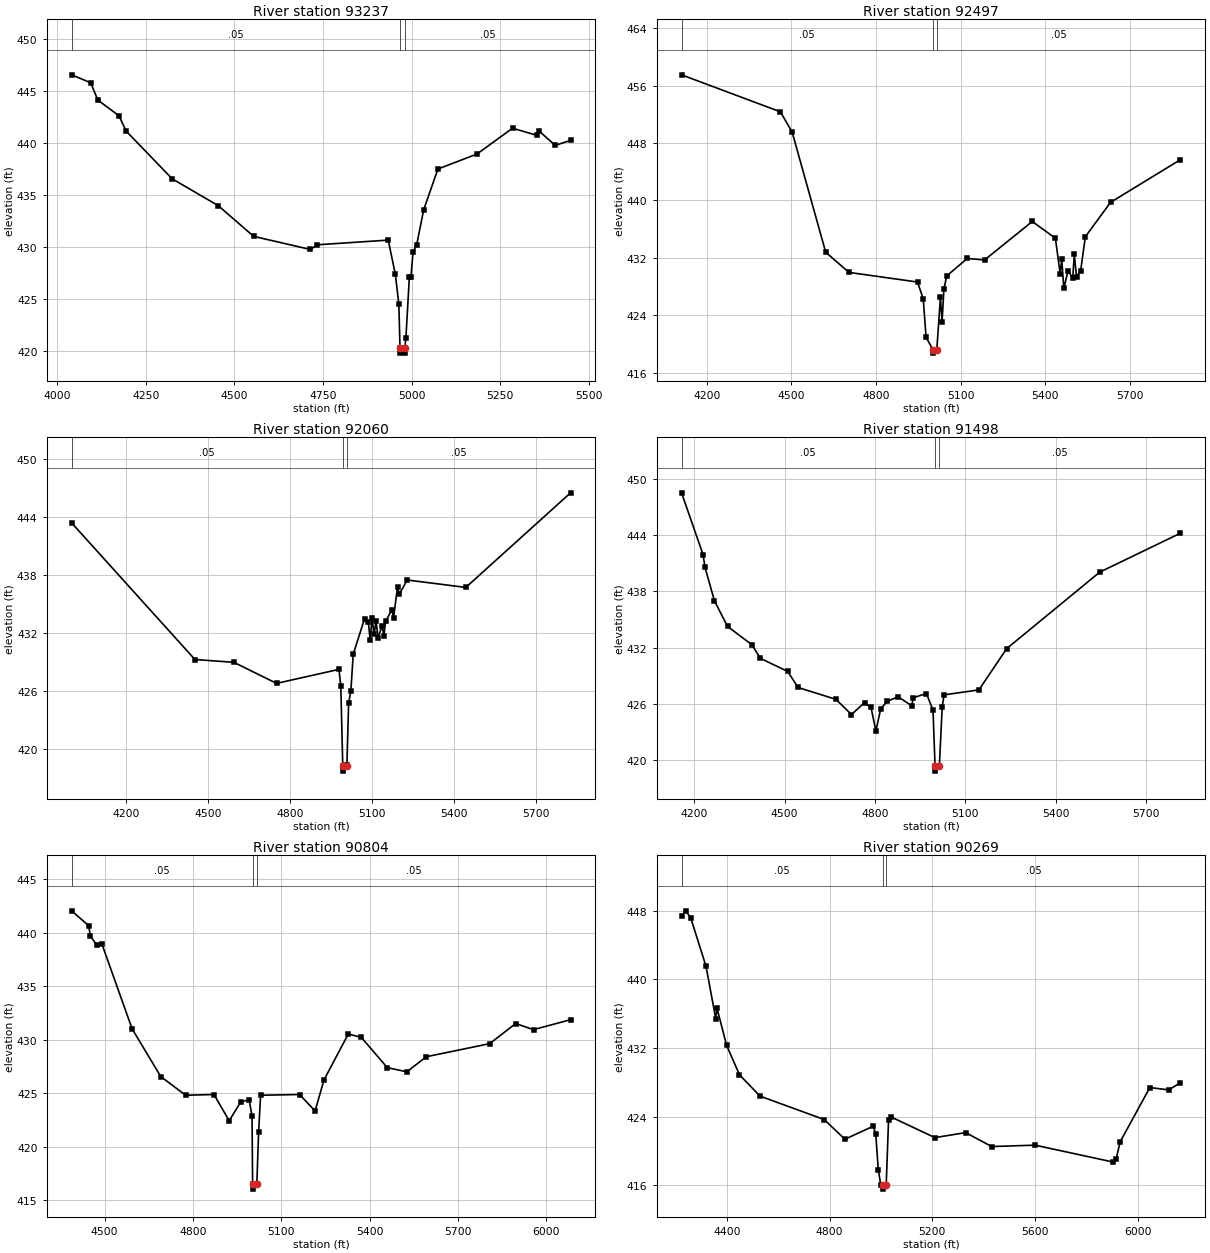
Type RM Length L Ch R = 1,93237,740,740,740
BEGIN DESCRIPTION:
North Twin Creek93236.68
END DESCRIPTION:
XS GIS Cut Line= 3
      2751249.91      6842311.00      2750291.70      6842296.53
      2749842.72      6842333.33
#Sta/Elev= 30
  4040.1  446.53  4094.0  445.77  4114.0  444.11  4174.0  442.59  4194.0  441.13
  4324.0  436.54  4454.1  433.96  4554.1  431.01  4714.1  429.75  4734.1  430.20
  4934.1  430.65  4954.1  427.38  4964.1  424.50  4967.3  420.29  4967.8  419.79
  4980.4  419.79  4980.9  420.29  4984.1  421.28  4993.8  427.14  4998.4  427.14
  5004.1  429.49  5014.2  430.16  5034.2  433.56  5074.4  437.48  5184.7  438.92
  5285.1  441.40  5354.7  440.71  5359.8  441.14  5405.5  439.75  5448.9  440.23
#Mann=3,-1,0
  4040.1    0.05       0  4967.3    0.05       0  4980.9    0.05       0
Bank Sta=4967.3,4980.9
Exp/Cntr=0.3,0.1

Type RM Length L Ch R = 1,92497,437,437,437
BEGIN DESCRIPTION:
North Twin Creek92497.41
END DESCRIPTION:
XS GIS Cut Line= 3
      2751302.09      6841724.57      2750409.85      6841867.55
      2749636.60      6842255.87
#Sta/Elev= 30
  4110.6  457.49  4461.1  452.34  4502.8  449.51  4621.7  432.79  4704.2  429.98
  4947.2  428.64  4967.5  426.30  4977.6  420.93  5001.9  419.24  5002.4  418.74
  5015.6  419.24  5028.6  426.55  5034.2  423.04  5040.9  427.69  5050.9  429.49
  5123.5  431.92  5184.9  431.71  5354.2  437.07  5436.1  434.73  5452.9  429.80
  5458.5  431.78  5466.1  427.74  5480.8  430.22  5497.5  429.21  5503.1  432.49
  5510.9  429.37  5525.5  430.17  5542.2  434.94  5631.5  439.73  5879.5  445.68
#Mann=3,-1,0
  4110.6    0.05       0  5001.9    0.05       0  5015.6    0.05       0
Bank Sta=5001.9,5015.6
Exp/Cntr=0.3,0.1

Type RM Length L Ch R = 1,92060,562,562,562
BEGIN DESCRIPTION:
North Twin Creek92060.35
END DESCRIPTION:
XS GIS Cut Line= 3
      2750855.91      6841038.38      2750040.05      6841668.13
      2749404.40      6842146.20
#Sta/Elev= 30
  4000.4  443.43  4451.7  429.29  4594.0  429.00  4750.6  426.82  4978.9  428.27
  4985.6  426.53  4992.8  418.24  4993.3  417.74  5006.6  418.24  5007.9  418.40
  5014.2  424.78  5022.4  426.03  5031.0  429.82  5072.4  433.52  5086.2  433.20
  5093.2  431.29  5099.5  433.57  5107.8  431.89  5114.1  433.31  5122.4  431.54
  5136.2  432.79  5143.2  431.77  5149.5  433.23  5172.4  434.44  5178.6  433.62
  5193.2  436.80  5199.4  436.04  5228.6  437.52  5443.1  436.75  5826.4  446.54
#Mann=3,-1,0
  4000.4    0.05       0  4992.8    0.05       0  5006.6    0.05       0
Bank Sta=4992.8,5006.6
Exp/Cntr=0.3,0.1

Type RM Length L Ch R = 1,91498,694,694,694
BEGIN DESCRIPTION:
North Twin Creek91498.38
END DESCRIPTION:
XS GIS Cut Line= 3
      2750413.97      6840891.33      2749672.37      6841304.68
      2749013.24      6841771.98
#Sta/Elev= 30
  4157.9  448.54  4229.6  441.92  4235.7  440.59  4267.3  436.99  4310.7  434.26
  4391.9  432.30  4419.3  430.86  4510.5  429.45  4544.8  427.74  4670.8  426.47
  4722.2  424.85  4765.6  426.12  4787.3  425.60  4803.3  423.09  4819.3  425.45
  4841.0  426.26  4876.8  426.75  4922.2  425.79  4927.9  426.65  4971.3  427.09
  4993.1  425.30  4999.9  419.30  5000.4  418.80  5014.0  419.30  5023.7  425.67
  5029.8  426.95  5145.5  427.48  5237.7  431.89  5546.6  440.06  5814.9  444.23
#Mann=3,-1,0
  4157.9    0.05       0  4999.9    0.05       0  5014.0    0.05       0
Bank Sta=4999.9,5014
Exp/Cntr=0.3,0.1

Type RM Length L Ch R = 1,90804,535,535,535
BEGIN DESCRIPTION:
North Twin Creek90804.45
END DESCRIPTION:
XS GIS Cut Line= 3
      2750079.36      6840509.22      2749517.62      6840776.22
      2748566.89      6841272.87
#Sta/Elev= 30
  4388.1  442.06  4446.1  440.67  4451.6  439.72  4474.3  438.83  4491.5  438.92
  4593.5  431.04  4690.8  426.58  4775.2  424.83  4871.6  424.90  4923.3  422.45
  4962.5  424.20  4990.8  424.41  5000.8  422.92  5002.9  416.56  5003.4  416.06
  5017.2  416.56  5023.2  421.36  5030.0  424.83  5162.5  424.90  5215.0  423.36
  5245.2  426.26  5327.8  430.55  5372.0  430.24  5460.3  427.41  5526.6  427.02
  5592.8  428.43  5808.0  429.65  5896.3  431.53  5956.9  430.96  6082.7  431.89
#Mann=3,-1,0
  4388.1    0.05       0  5002.9    0.05       0  5017.2    0.05       0
Bank Sta=5002.9,5017.2
Exp/Cntr=0.3,0.1

Type RM Length L Ch R = 1,90269,202,202,202
BEGIN DESCRIPTION:
North Twin Creek90269.09
END DESCRIPTION:
XS GIS Cut Line= 5
      2750001.46      6840450.18      2749221.95      6840426.20
      2748600.87      6840411.24      2748323.25      6840409.76
      2748100.22      6840549.40
#Sta/Elev= 30
  4223.8  447.37  4239.3  447.97  4259.3  447.18  4319.3  441.49  4357.0  435.40
  4362.0  436.61  4399.3  432.30  4449.4  428.87  4529.4  426.39  4779.5  423.66
  4859.6  421.37  4969.6  422.88  4979.6  422.02  4989.6  417.82  4999.1  416.09
  5006.0  416.06  5006.5  415.56  5020.4  416.06  5029.6  423.63  5039.6  423.96
  5209.7  421.56  5329.7  422.14  5431.0  420.52  5599.8  420.68  5902.6  418.72
  5915.7  419.12  5931.0  421.07  6046.5  427.39  6119.6  427.12  6165.7  427.94
#Mann=3,-1,0
  4223.8    0.05       0  5006.0    0.05       0  5020.4    0.05       0
Bank Sta=5006,5020.4
Exp/Cntr=0.3,0.1

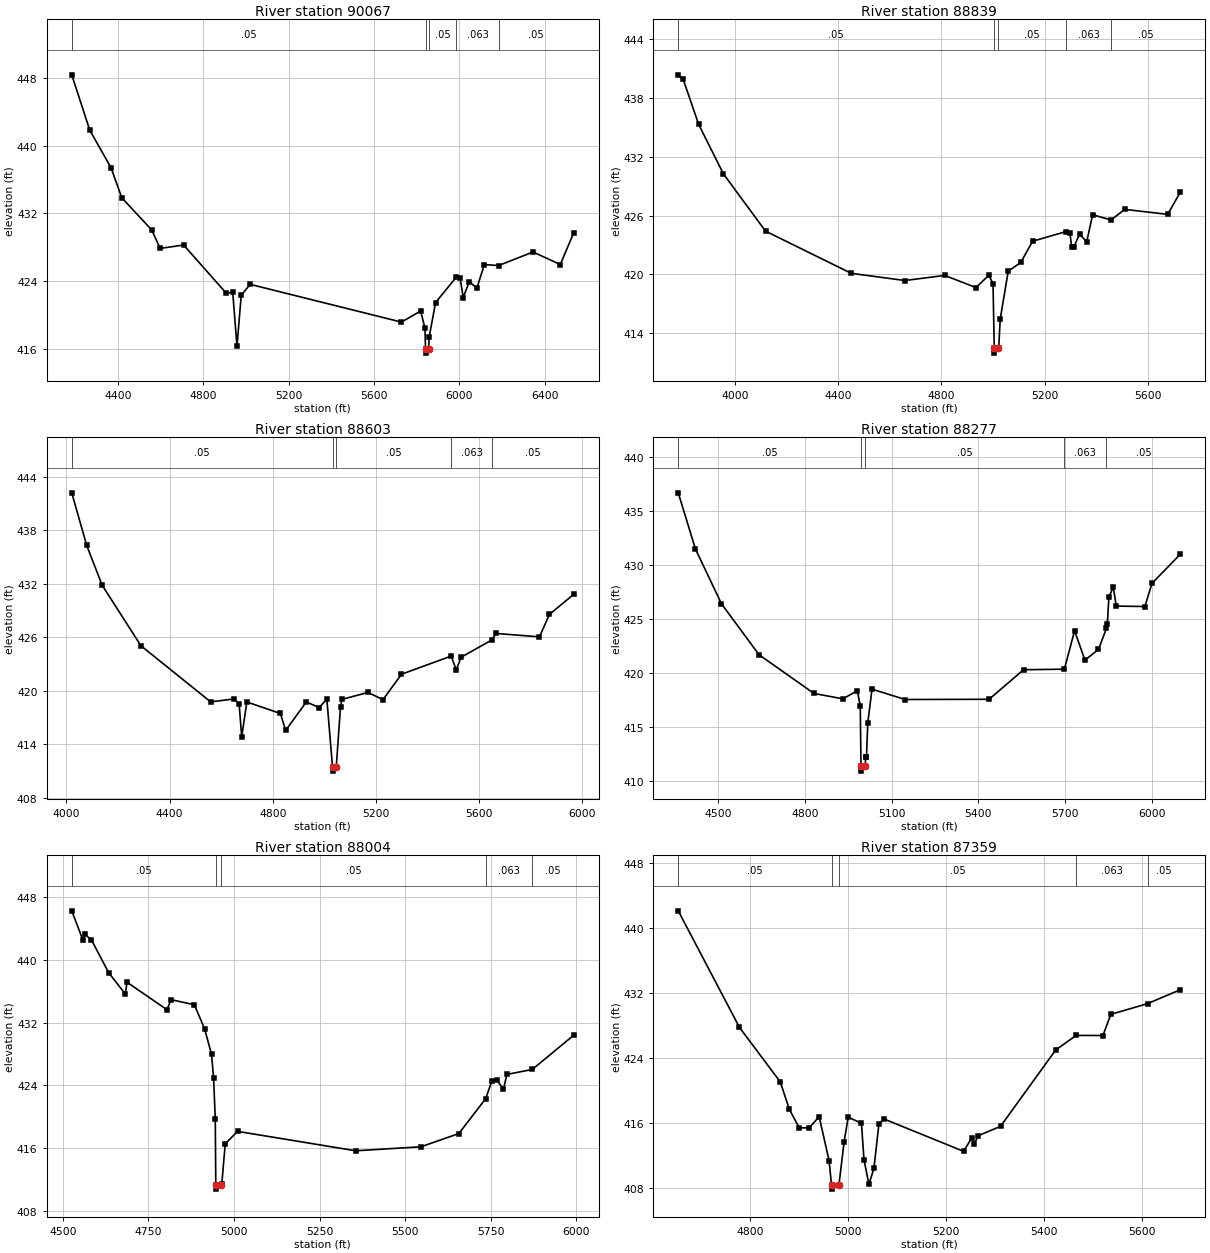
Type RM Length L Ch R = 1,90067,1228,1228,1228
BEGIN DESCRIPTION:
North Twin Creek90066.62
END DESCRIPTION:
XS GIS Cut Line= 4
      2749980.21      6840236.65      2749146.92      6840247.75
      2748213.59      6840204.50      2747842.11      6840656.93
#Sta/Elev= 30
  4183.0  448.35  4267.2  441.83  4367.2  437.38  4417.2  433.86  4557.2  430.07
  4597.3  427.88  4707.3  428.28  4907.3  422.59  4937.3  422.72  4957.3  416.34
  4977.3  422.37  5019.3  423.64  5728.1  419.19  5818.1  420.50  5838.2  418.48
  5841.0  416.03  5841.5  415.53  5855.4  416.03  5858.2  417.46  5888.2  421.50
  5985.3  424.49  6003.2  424.37  6017.6  422.09  6046.3  423.97  6081.4  423.18
  6116.6  425.97  6183.9  425.86  6344.8  427.46  6472.5  425.98  6536.1  429.75
#Mann=5,-1,0
  4183.0    0.05       0  5841.0    0.05       0  5855.4    0.05       0
  5985.3   0.063       0  6183.9    0.05       0
Bank Sta=5841,5855.4
Exp/Cntr=0.3,0.1

Type RM Length L Ch R = 1,88839,236,236,236
BEGIN DESCRIPTION:
North Twin Creek88838.72
END DESCRIPTION:
XS GIS Cut Line= 3
      2749290.88      6839429.03      2748195.83      6840001.86
      2747831.48      6840613.07
#Sta/Elev= 30
  3779.3  440.37  3798.0  439.95  3858.6  435.31  3954.1  430.28  4117.8  424.42
  4450.7  420.11  4658.4  419.38  4812.9  419.90  4934.0  418.66  4983.8  419.91
  5000.3  419.06  5004.9  412.47  5005.4  411.97  5019.5  412.47  5022.3  412.48
  5028.1  415.43  5059.2  420.33  5107.9  421.22  5153.8  423.39  5284.4  424.38
  5298.7  424.23  5305.2  422.78  5314.3  422.82  5335.7  424.13  5363.4  423.32
  5386.7  426.09  5458.2  425.56  5510.9  426.64  5677.7  426.13  5726.7  428.39
#Mann=5,-1,0
  3779.3    0.05       0  5004.9    0.05       0  5019.5    0.05       0
  5284.4   0.063       0  5458.2    0.05       0
Bank Sta=5004.9,5019.5
Exp/Cntr=0.3,0.1

Type RM Length L Ch R = 1,88603,326,326,326
BEGIN DESCRIPTION:
North Twin Creek88603.228
END DESCRIPTION:
XS GIS Cut Line= 3
      2748205.81      6838803.32      2748146.35      6839780.72
      2747774.82      6840674.14
#Sta/Elev= 30
  4020.8  442.20  4078.6  436.31  4138.7  431.84  4289.0  425.06  4559.5  418.77
  4649.6  419.10  4669.7  418.57  4679.7  414.86  4699.7  418.76  4830.0  417.47
  4850.0  415.57  4930.2  418.76  4980.2  418.13  5009.8  419.09  5031.8  411.51
  5032.3  411.01  5046.4  411.51  5062.9  418.23  5068.4  419.05  5169.2  419.83
  5227.7  419.02  5299.3  421.87  5491.7  423.90  5511.7  422.36  5530.2  423.77
  5649.8  425.71  5665.7  426.44  5834.2  426.06  5872.8  428.57  5967.6  430.84
#Mann=5,-1,0
  4020.8    0.05       0  5031.8    0.05       0  5046.4    0.05       0
  5491.7   0.063       0  5649.8    0.05       0
Bank Sta=5031.8,5046.4
Exp/Cntr=0.3,0.1

Type RM Length L Ch R = 1,88277,273,273,273
BEGIN DESCRIPTION:
North Twin Creek88276.52
END DESCRIPTION:
XS GIS Cut Line= 3
      2747997.91      6838921.64      2747982.26      6839572.43
      2747721.86      6840626.05
#Sta/Elev= 30
  4362.4  436.69  4421.8  431.49  4511.8  426.41  4641.8  421.68  4831.9  418.09
  4931.9  417.59  4981.9  418.35  4991.9  416.90  4994.4  411.39  4994.9  410.89
  5009.4  411.39  5010.2  412.21  5013.4  412.21  5017.8  415.35  5032.5  418.49
  5147.3  417.53  5437.4  417.55  5556.6  420.29  5697.8  420.34  5733.0  423.90
  5768.9  421.18  5815.5  422.17  5843.2  424.12  5846.3  424.53  5851.8  427.03
  5866.9  427.96  5877.2  426.19  5976.1  426.15  6000.8  428.30  6098.7  431.00
#Mann=5,-1,0
  4362.4    0.05       0  4994.4    0.05       0  5009.4    0.05       0
  5697.8   0.063       0  5843.2    0.05       0
Bank Sta=4994.4,5009.4
Exp/Cntr=0.3,0.1

Type RM Length L Ch R = 1,88004,645,645,645
BEGIN DESCRIPTION:
North Twin Creek88003.59
END DESCRIPTION:
XS GIS Cut Line= 3
      2747763.58      6839033.86      2747725.50      6839517.81
      2747640.28      6840495.96
#Sta/Elev= 30
  4525.8  446.22  4558.4  442.49  4563.4  443.24  4583.1  442.54  4633.3  438.37
  4682.3  435.63  4687.3  437.13  4803.8  433.64  4816.2  434.91  4884.0  434.27
  4914.1  431.19  4934.2  427.95  4940.2  425.00  4945.2  419.74  4946.7  411.30
  4947.2  410.80  4961.8  411.30  4964.3  411.47  4974.3  416.57  5010.3  418.15
  5355.7  415.68  5546.5  416.19  5656.9  417.87  5735.4  422.31  5753.3  424.53
  5767.3  424.75  5787.4  423.49  5797.4  425.40  5871.6  426.03  5993.1  430.40
#Mann=5,-1,0
  4525.8    0.05       0  4946.7    0.05       0  4961.8    0.05       0
  5735.4   0.063       0  5871.6    0.05       0
Bank Sta=4946.7,4961.8
Exp/Cntr=0.3,0.1

Type RM Length L Ch R = 1,87359,379,379,379
BEGIN DESCRIPTION:
North Twin Creek87358.53
END DESCRIPTION:
XS GIS Cut Line= 3
      2747304.53      6839427.99      2747366.79      6839772.42
      2747485.90      6840436.41
#Sta/Elev= 30
  4654.1  442.07  4779.1  427.73  4862.3  421.04  4880.7  417.68  4901.1  415.38
  4921.4  415.39  4941.7  416.76  4962.0  411.33  4966.9  408.35  4967.4  407.85
  4982.0  408.35  4992.5  413.61  5000.9  416.70  5028.0  415.95  5033.2  411.43
  5043.3  408.44  5053.5  410.42  5063.6  415.87  5073.8  416.48  5236.3  412.50
  5253.0  414.13  5258.1  413.43  5266.8  414.43  5311.8  415.57  5424.4  424.96
  5466.1  426.75  5520.8  426.74  5536.9  429.34  5611.9  430.66  5678.7  432.37
#Mann=5,-1,0
  4654.1    0.05       0  4966.9    0.05       0  4982.0    0.05       0
  5466.1   0.063       0  5611.9    0.05       0
Bank Sta=4966.9,4982
Exp/Cntr=0.3,0.1

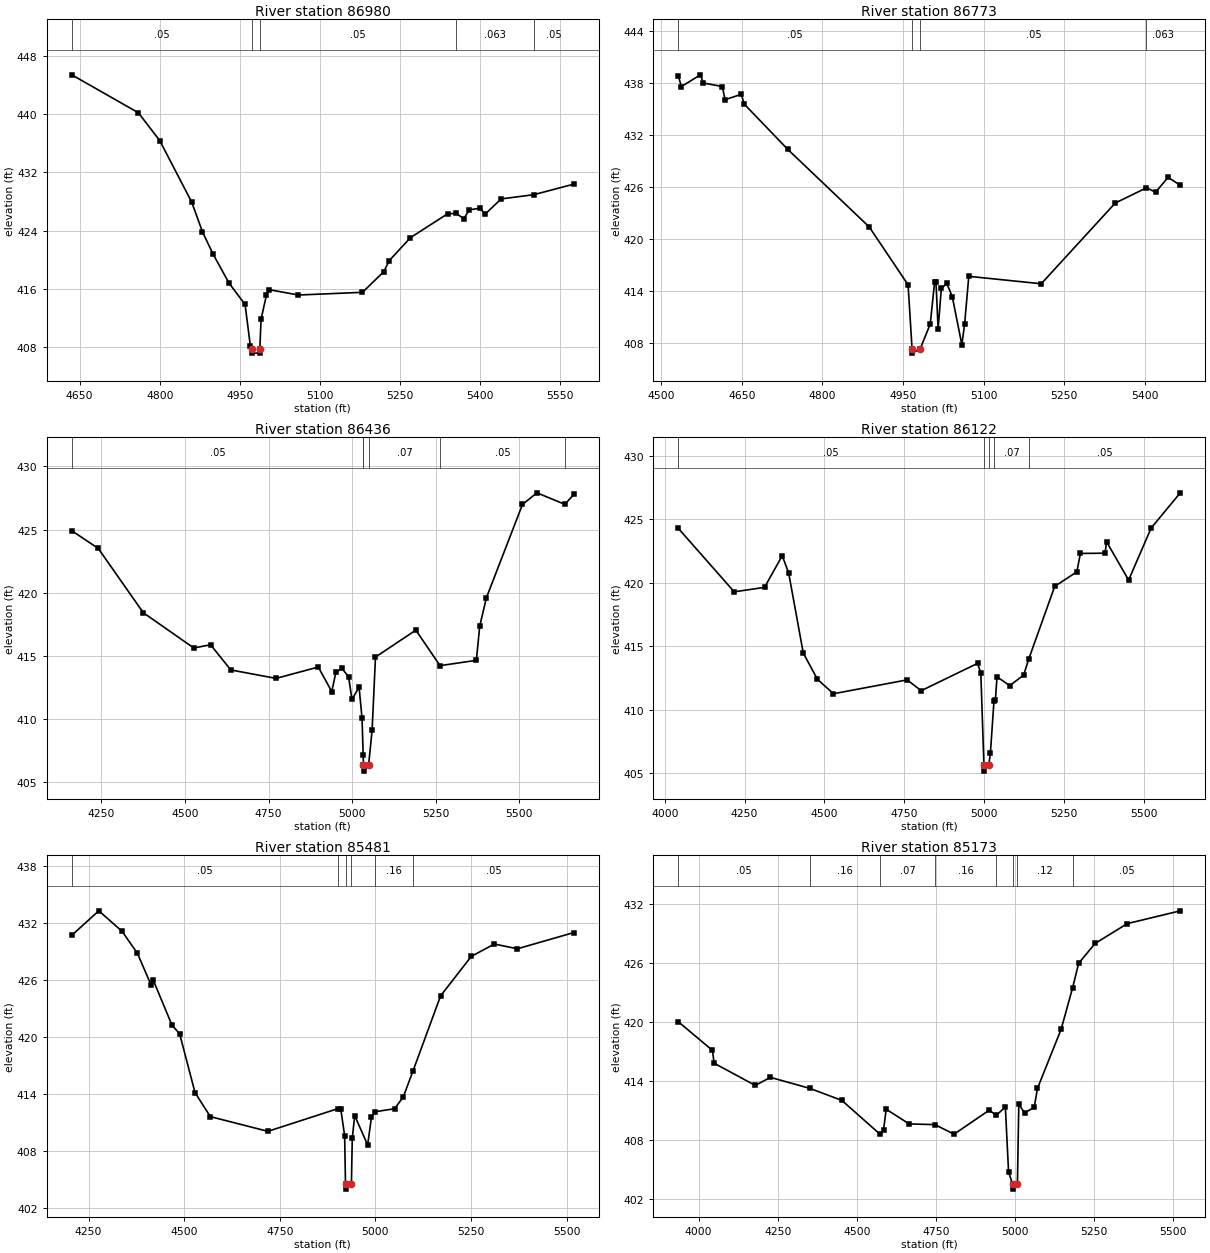
Type RM Length L Ch R = 1,86980,207,207,207
BEGIN DESCRIPTION:
North Twin Creek86979.5
END DESCRIPTION:
XS GIS Cut Line= 3
      2747114.85      6839496.18      2747111.83      6839866.74
      2747112.79      6840437.17
#Sta/Elev= 30
  4635.2  445.38  4760.0  440.18  4800.0  436.37  4860.0  427.92  4880.0  423.88
  4900.0  420.79  4930.0  416.81  4960.0  413.88  4970.0  408.14  4972.4  407.71
  4972.9  407.21  4987.1  407.21  4987.6  407.71  4990.0  411.87  5000.0  415.15
  5005.4  415.91  5060.0  415.18  5180.0  415.55  5220.0  418.38  5230.0  419.88
  5270.0  423.05  5340.0  426.34  5355.7  426.37  5370.0  425.64  5380.0  426.85
  5400.0  427.09  5410.0  426.28  5440.0  428.36  5501.1  428.94  5576.2  430.39
#Mann=5,-1,0
  4635.2    0.05       0  4972.4    0.05       0  4987.6    0.05       0
  5355.7   0.063       0  5501.1    0.05       0
Bank Sta=4972.4,4987.6
Exp/Cntr=0.3,0.1

Type RM Length L Ch R = 1,86773,337,337,337
BEGIN DESCRIPTION:
North Twin Creek86773.37
END DESCRIPTION:
XS GIS Cut Line= 3
      2747041.52      6839356.66      2746921.63      6839821.39
      2746825.74      6840265.92
#Sta/Elev= 30
  4531.6  438.87  4537.5  437.63  4573.0  438.98  4578.1  438.04  4613.6  437.63
  4618.8  436.11  4649.1  436.73  4654.3  435.61  4735.7  430.36  4887.2  421.41
  4959.5  414.73  4966.9  407.34  4967.4  406.84  4982.1  407.34  5000.8  410.22
  5008.8  415.00  5011.5  415.00  5015.4  409.62  5021.4  414.31  5031.6  414.89
  5041.8  413.36  5059.6  407.81  5064.7  410.17  5072.5  415.71  5207.4  414.85
  5345.1  424.17  5403.2  425.93  5420.3  425.43  5443.6  427.14  5466.3  426.22
#Mann=4,-1,0
  4531.6    0.05       0  4966.9    0.05       0  4982.1    0.05       0
  5403.2   0.063       0
Bank Sta=4966.9,4982.1
Exp/Cntr=0.3,0.1

Type RM Length L Ch R = 1,86436,314,314,314
BEGIN DESCRIPTION:
North Twin Creek86435.89
END DESCRIPTION:
XS GIS Cut Line= 3
      2746830.11      6838738.50      2746733.30      6839588.27
      2746664.99      6840230.88
#Sta/Elev= 30
  4161.3  424.91  4240.5  423.51  4375.2  418.42  4526.1  415.63  4576.5  415.88
  4636.9  413.89  4772.3  413.22  4898.5  414.12  4938.8  412.18  4951.2  413.70
  4969.0  414.01  4989.1  413.36  4999.2  411.55  5020.5  412.53  5029.4  410.06
  5032.8  407.15  5033.7  406.38  5034.2  405.88  5049.1  406.38  5059.5  409.13
  5069.6  414.91  5190.3  417.04  5262.6  414.23  5371.3  414.65  5381.3  417.36
  5401.5  419.62  5509.2  426.99  5552.3  427.91  5635.9  427.00  5662.8  427.78
#Mann=6,-1,0
  4161.3    0.05       0  5032.8    0.07       0  5033.7    0.05       0
  5049.1    0.07       0  5262.6    0.05       0  5635.9   0.063       0
Bank Sta=5033.7,5049.1
Exp/Cntr=0.3,0.1

Type RM Length L Ch R = 1,86122,641,641,641
BEGIN DESCRIPTION:
North Twin Creek86121.75
END DESCRIPTION:
XS GIS Cut Line= 3
      2746533.03      6838506.28      2746454.05      6839470.73
      2746383.79      6840071.76
#Sta/Elev= 30
  4042.3  424.29  4217.6  419.29  4312.6  419.64  4368.1  422.13  4388.2  420.78
  4434.0  414.47  4478.5  412.40  4528.6  411.27  4759.4  412.36  4803.4  411.51
  4980.1  413.66  4990.2  412.88  4999.9  405.68  5000.4  405.18  5015.3  405.68
  5020.3  406.64  5031.3  410.66  5035.8  410.77  5040.9  412.60  5080.7  411.91
  5124.2  412.73  5140.3  414.00  5221.7  419.72  5290.9  420.86  5302.2  422.31
  5379.2  422.33  5384.3  423.22  5453.2  420.21  5523.7  424.31  5615.1  427.08
#Mann=5,-1,0
  4042.3    0.05       0  4999.9    0.05       0  5015.3    0.05       0
  5031.3    0.07       0  5140.3    0.05       0
Bank Sta=4999.9,5015.3
Exp/Cntr=0.3,0.1

Type RM Length L Ch R = 1,85481,308,308,308
BEGIN DESCRIPTION:
North Twin Creek85481.08
END DESCRIPTION:
XS GIS Cut Line= 3
      2746166.61      6838469.73      2746106.22      6839271.88
      2746061.88      6839778.02
#Sta/Elev= 30
  4206.2  430.73  4276.8  433.31  4337.8  431.15  4378.0  428.82  4413.6  425.48
  4418.6  426.06  4468.2  421.26  4488.3  420.34  4528.4  414.15  4568.5  411.62
  4718.9  410.07  4901.8  412.46  4909.5  412.39  4919.5  409.62  4921.8  404.48
  4922.3  403.98  4937.2  404.48  4939.5  409.36  4945.8  411.73  4979.7  408.63
  4989.7  411.59  4999.8  412.14  5049.9  412.45  5072.7  413.68  5097.9  416.40
  5170.4  424.35  5250.7  428.51  5310.9  429.81  5371.1  429.31  5518.7  431.02
#Mann=6,-1,0
  4206.2    0.05       0  4901.8    0.12       0  4921.8    0.07       0
  4937.2    0.12       0  4999.8    0.16       0  5097.9    0.05       0
Bank Sta=4921.8,4937.2
Exp/Cntr=0.3,0.1

Type RM Length L Ch R = 1,85173,325,325,325
BEGIN DESCRIPTION:
North Twin Creek85173.06
END DESCRIPTION:
XS GIS Cut Line= 3
      2745988.90      6838160.70      2745813.64      6839219.84
      2745728.10      6839726.42
#Sta/Elev= 30
  3935.6  420.02  4043.8  417.11  4048.9  415.81  4179.2  413.55  4226.9  414.37
  4351.8  413.25  4452.8  412.03  4574.5  408.57  4584.6  409.02  4593.1  411.13
  4665.7  409.64  4747.2  409.57  4807.6  408.60  4919.1  411.04  4940.8  410.51
  4969.8  411.36  4979.9  404.79  4992.5  403.52  4993.0  403.02  5007.9  403.52
  5012.3  411.64  5030.6  410.76  5061.0  411.32  5071.2  413.24  5146.2  419.26
  5182.6  423.49  5201.6  425.96  5253.7  427.97  5355.1  429.98  5522.9  431.28
#Mann=8,-1,0
  3935.6    0.05       0  4351.8    0.16       0  4574.5    0.07       0
  4747.2    0.16       0  4940.8    0.12       0  4992.5    0.07       0
  5007.9    0.12       0  5182.6    0.05       0
Bank Sta=4992.5,5007.9
Exp/Cntr=0.3,0.1

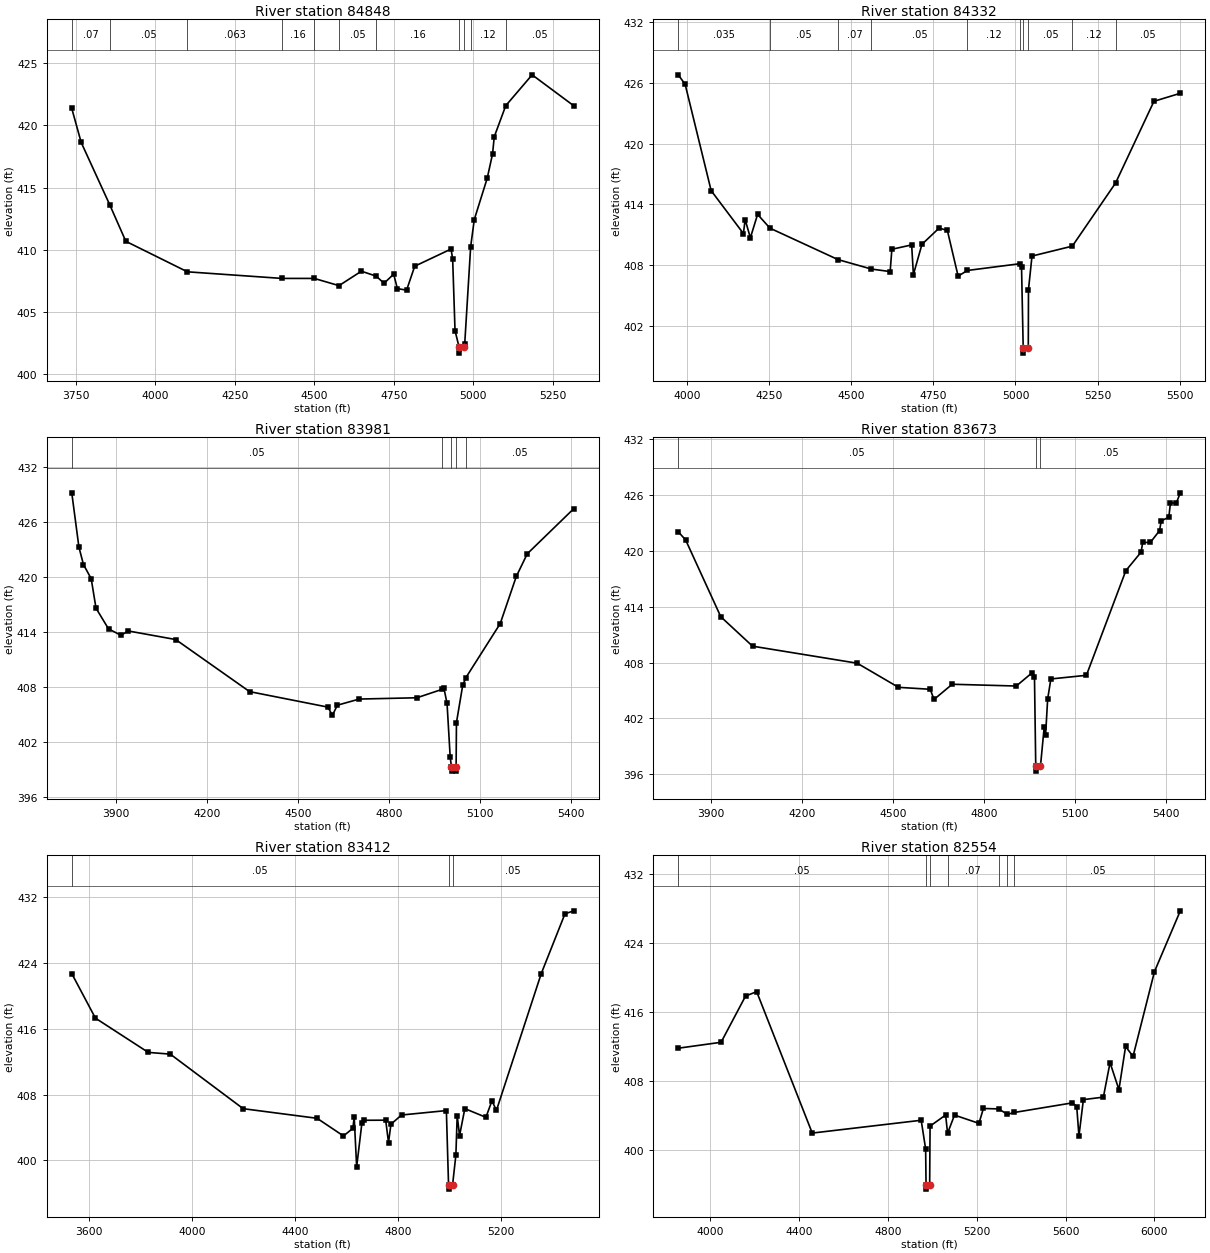
Type RM Length L Ch R = 1,84848,516,516,516
BEGIN DESCRIPTION:
North Twin Creek84847.74
END DESCRIPTION:
XS GIS Cut Line= 3
      2745745.49      6837913.49      2745528.16      6839165.54
      2745487.77      6839471.11
#Sta/Elev= 30
  3737.4  421.35  3767.0  418.62  3857.4  413.58  3907.4  410.68  4101.1  408.23
  4398.1  407.70  4500.0  407.70  4577.8  407.12  4648.3  408.28  4695.0  407.88
  4719.4  407.31  4749.8  408.04  4761.4  406.88  4790.4  406.76  4816.0  408.68
  4930.3  410.06  4935.3  409.24  4942.7  403.51  4955.3  402.20  4955.8  401.70
  4970.7  402.20  4973.1  402.40  4991.9  410.25  5003.3  412.43  5043.9  415.74
  5060.9  417.72  5066.0  419.07  5102.2  421.57  5185.2  424.05  5316.4  421.56
#Mann=11,-1,0
  3737.4    0.07       0  3857.4    0.05       0  4101.1   0.063       0
  4398.1    0.16       0  4500.0    0.07       0  4577.8    0.05       0
  4695.0    0.16       0  4955.3    0.07       0  4970.7    0.16       0
  4991.9    0.12       0  5102.2    0.05       0
Bank Sta=4955.3,4970.7
Exp/Cntr=0.3,0.1

Type RM Length L Ch R = 1,84332,351,351,351
BEGIN DESCRIPTION:
North Twin Creek84332.34
END DESCRIPTION:
XS GIS Cut Line= 3
      2745600.55      6837800.86      2745296.86      6838793.72
      2745131.72      6839256.68
#Sta/Elev= 30
  3972.5  426.78  3993.6  425.84  4072.8  415.36  4171.1  411.13  4176.3  412.51
  4192.3  410.71  4214.3  413.02  4252.0  411.66  4459.5  408.56  4561.1  407.63
  4618.2  407.38  4623.4  409.58  4683.7  410.01  4689.0  407.08  4715.1  410.07
  4767.4  411.67  4792.5  411.44  4825.3  406.93  4853.5  407.49  5014.5  408.16
  5018.5  407.87  5023.6  399.84  5024.1  399.34  5039.1  399.84  5039.7  405.61
  5050.4  408.91  5173.3  409.89  5305.0  416.11  5422.0  424.17  5502.3  424.96
#Mann=10,-1,0
  3972.5   0.035       0  4252.0    0.05       0  4459.5    0.07       0
  4561.1    0.05       0  4853.5    0.12       0  5014.5    0.05       0
  5023.6    0.07       0  5039.1    0.05       0  5173.3    0.12       0
  5305.0    0.05       0
Bank Sta=5023.6,5039.1
Exp/Cntr=0.3,0.1

Type RM Length L Ch R = 1,83981,308,308,308
BEGIN DESCRIPTION:
North Twin Creek83981.05
END DESCRIPTION:
XS GIS Cut Line= 3
      2745317.04      6837583.70      2745001.47      6838797.04
      2744904.11      6839186.45
#Sta/Elev= 30
  3754.7  429.17  3778.2  423.26  3793.2  421.35  3818.7  419.81  3834.6  416.59
  3875.9  414.33  3917.2  413.63  3940.3  414.11  4097.3  413.17  4340.9  407.49
  4599.2  405.80  4613.8  404.90  4630.2  406.01  4702.5  406.68  4892.4  406.82
  4975.6  407.74  4981.5  407.87  4991.8  406.20  5002.2  400.35  5006.2  399.32
  5006.7  398.82  5021.2  398.82  5021.7  399.32  5022.8  404.11  5043.4  408.17
  5054.0  409.02  5167.1  414.91  5220.1  420.05  5256.2  422.52  5409.8  427.45
#Mann=5,-1,0
  3754.7    0.05       0  4975.6    0.12       0  5006.2    0.07       0
  5021.7    0.12       0  5054.0    0.05       0
Bank Sta=5006.2,5021.7
Exp/Cntr=0.3,0.1

Type RM Length L Ch R = 1,83673,261,261,261
BEGIN DESCRIPTION:
North Twin Creek83673.24
END DESCRIPTION:
XS GIS Cut Line= 3
      2745119.52      6837456.90      2744761.22      6838614.64
      2744608.00      6839031.77
#Sta/Elev= 30
  3790.8  422.05  3815.2  421.17  3931.2  412.92  4035.9  409.76  4381.3  407.93
  4517.4  405.34  4622.1  405.13  4634.6  404.04  4694.6  405.67  4906.0  405.48
  4957.0  406.87  4966.0  406.47  4970.2  396.84  4970.7  396.34  4985.7  396.84
  4998.2  401.12  5002.7  400.24  5009.5  404.09  5020.1  406.24  5137.3  406.63
  5267.4  417.87  5317.7  419.86  5323.1  420.90  5348.2  420.90  5378.7  422.17
  5384.0  423.22  5409.2  423.61  5414.5  425.12  5434.3  425.17  5447.1  426.23
#Mann=3,-1,0
  3790.8    0.05       0  4970.2    0.05       0  4985.7    0.05       0
Bank Sta=4970.2,4985.7
Exp/Cntr=0.3,0.1

Type RM Length L Ch R = 1,83412,858,858,858
BEGIN DESCRIPTION:
North Twin Creek83411.57
END DESCRIPTION:
XS GIS Cut Line= 3
      2744926.77      6837001.31      2744595.58      6838437.71
      2744490.69      6838904.69
#Sta/Elev= 30
  3532.3  422.72  3624.3  417.30  3829.9  413.13  3915.4  412.92  4199.0  406.28
  4486.4  405.11  4589.0  402.96  4625.6  403.89  4630.7  405.26  4640.3  399.20
  4660.8  404.56  4668.3  404.87  4753.2  404.88  4764.2  402.16  4773.7  404.39
  4814.8  405.51  4989.2  406.05  4997.7  396.99  4998.2  396.49  5013.3  396.99
  5026.2  400.64  5031.3  405.44  5040.5  403.00  5061.0  406.29  5143.0  405.23
  5166.4  407.23  5184.0  406.08  5358.2  422.72  5450.5  430.00  5485.0  430.36
#Mann=3,-1,0
  3532.3    0.05       0  4997.7    0.05       0  5013.3    0.05       0
Bank Sta=4997.7,5013.3
Exp/Cntr=0.3,0.1

Type RM Length L Ch R = 1,82554,236,236,236
BEGIN DESCRIPTION:
North Twin Creek82554.21
END DESCRIPTION:
XS GIS Cut Line= 3
      2744490.48      6836568.28      2744445.26      6837720.61
      2744427.57      6838827.26
#Sta/Elev= 30
  3856.8  411.79  4049.7  412.48  4159.7  417.85  4209.8  418.37  4460.0  401.92
  4950.4  403.41  4970.4  400.08  4972.3  395.90  4972.8  395.40  4988.5  395.90
  4990.4  402.73  5060.4  404.02  5069.2  401.90  5100.4  404.01  5210.4  403.05
  5230.4  404.78  5298.7  404.73  5338.6  404.10  5370.4  404.32  5630.5  405.43
  5650.5  405.01  5660.5  401.58  5680.5  405.81  5770.5  406.10  5800.5  410.11
  5840.5  406.97  5870.5  411.99  5904.0  410.84  6000.5  420.70  6116.8  427.77
#Mann=7,-1,0
  3856.8    0.05       0  4972.3    0.05       0  4988.5    0.05       0
  5069.2    0.07       0  5298.7    0.05       0  5338.6    0.07       0
  5370.4    0.05       0
Bank Sta=4972.3,4988.5
Exp/Cntr=0.3,0.1

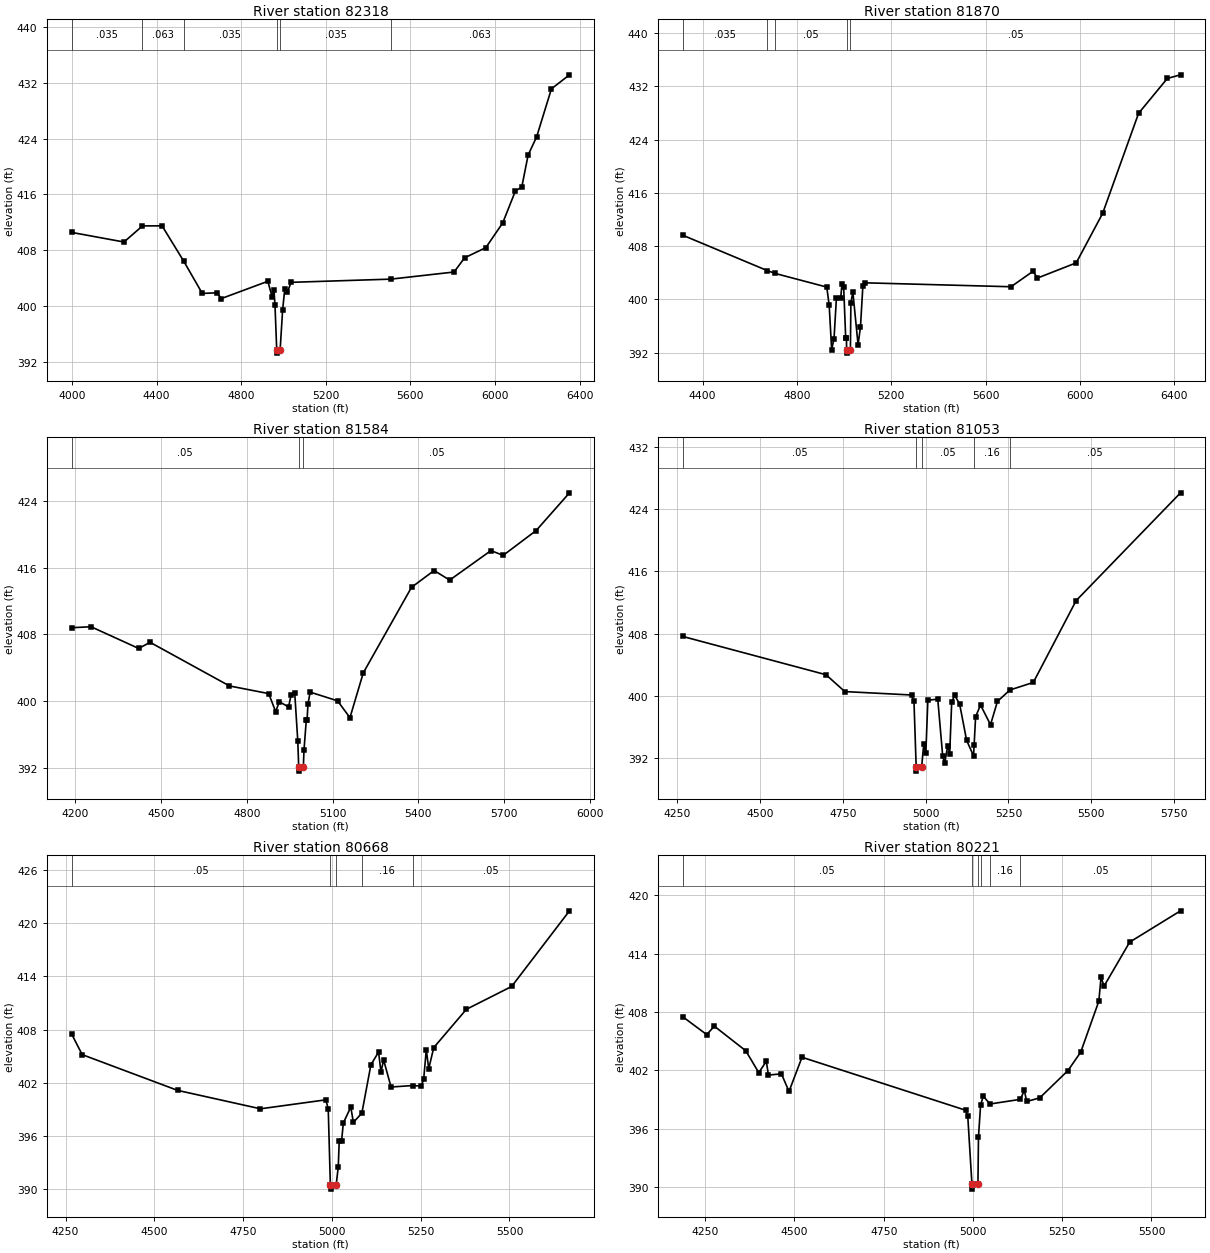
Type RM Length L Ch R = 1,82318,448,448,448
BEGIN DESCRIPTION:
North Twin Creek82317.52
END DESCRIPTION:
XS GIS Cut Line= 3
      2744326.75      6836533.26      2744299.46      6837550.87
      2744252.81      6838886.38
#Sta/Elev= 30
  3997.9  410.55  4245.7  409.17  4333.3  411.48  4425.8  411.49  4529.1  406.38
  4615.9  401.80  4685.9  401.89  4705.9  401.06  4926.0  403.54  4946.0  401.31
  4954.7  402.34  4959.7  400.16  4967.9  393.74  4968.4  393.24  4984.1  393.74
  4996.0  399.47  5006.0  402.44  5018.4  402.00  5036.0  403.39  5508.0  403.85
  5806.5  404.87  5856.5  406.91  5956.6  408.36  6036.6  411.91  6096.7  416.50
  6126.7  417.05  6156.7  421.65  6196.7  424.23  6266.8  431.13  6352.2  433.14
#Mann=6,-1,0
  3997.9   0.035       0  4333.3   0.063       0  4529.1   0.035       0
  4967.9   0.035       0  4984.1   0.035       0  5508.0   0.063       0
Bank Sta=4967.9,4984.1
Exp/Cntr=0.3,0.1

Type RM Length L Ch R = 1,81870,286,286,286
BEGIN DESCRIPTION:
North Twin Creek81870.33
END DESCRIPTION:
XS GIS Cut Line= 3
      2744244.93      6836513.97      2744096.46      6837192.72
      2743842.75      6838585.90
#Sta/Elev= 30
  4315.6  409.66  4674.9  404.33  4708.8  403.90  4926.8  401.86  4937.0  399.14
  4947.4  392.48  4957.5  394.10  4967.7  400.19  4986.1  400.29  4991.2  402.29
  4998.4  401.88  5007.0  394.26  5010.4  394.26  5010.7  392.44  5011.2  391.94
  5027.0  392.44  5029.0  399.53  5037.5  401.10  5059.5  393.18  5069.6  395.86
  5079.8  402.01  5090.0  402.50  5707.8  401.91  5801.5  404.24  5819.5  403.21
  5984.4  405.50  6096.3  412.93  6248.7  427.96  6370.7  433.20  6426.5  433.74
#Mann=5,-1,0
  4315.6   0.035       0  4674.9   0.063       0  4708.8    0.05       0
  5010.7    0.05       0  5027.0    0.05       0
Bank Sta=5010.7,5027
Exp/Cntr=0.3,0.1

Type RM Length L Ch R = 1,81584,531,531,531
BEGIN DESCRIPTION:
North Twin Creek81584.01
END DESCRIPTION:
XS GIS Cut Line= 3
      2744137.59      6836455.99      2743831.32      6837221.02
      2743499.90      6838077.47
#Sta/Elev= 30
  4186.6  408.79  4254.7  408.91  4421.6  406.30  4461.3  407.04  4739.2  401.80
  4876.5  400.88  4900.7  398.72  4913.7  399.90  4946.0  399.28  4954.5  400.66
  4967.6  400.92  4978.3  395.15  4981.4  392.07  4981.9  391.57  4997.7  392.07
  4999.9  394.07  5008.0  397.70  5010.7  397.70  5013.8  399.59  5021.4  401.06
  5117.4  400.01  5160.8  397.99  5207.3  403.36  5376.2  413.64  5455.3  415.66
  5509.8  414.51  5654.1  418.05  5696.9  417.48  5812.3  420.46  5929.0  424.99
#Mann=3,-1,0
  4186.6    0.05       0  4981.4    0.05       0  4997.7    0.05       0
Bank Sta=4981.4,4997.7
Exp/Cntr=0.3,0.1

Type RM Length L Ch R = 1,81053,385,385,385
BEGIN DESCRIPTION:
North Twin Creek81052.91
END DESCRIPTION:
XS GIS Cut Line= 3
      2744029.67      6836343.21      2743600.52      6836961.62
      2743184.50      6837585.51
#Sta/Elev= 30
  4266.8  407.63  4699.6  402.69  4756.3  400.52  4957.9  400.08  4965.0  399.28
  4971.7  390.77  4972.2  390.27  4988.1  390.77  4994.4  393.71  5000.8  392.56
  5006.9  399.40  5036.8  399.55  5051.8  392.17  5057.8  391.28  5066.8  393.56
  5072.8  392.52  5078.9  399.16  5087.8  400.05  5102.8  398.91  5123.9  394.23
  5144.9  392.24  5146.6  393.64  5151.0  397.27  5165.9  398.79  5196.0  396.25
  5217.0  399.26  5254.9  400.73  5325.2  401.70  5454.4  412.24  5769.4  426.13
#Mann=5,-1,0
  4266.8    0.05       0  4971.7    0.05       0  4988.1    0.05       0
  5146.6    0.16       0  5254.9    0.05       0
Bank Sta=4971.7,4988.1
Exp/Cntr=0.3,0.1

Type RM Length L Ch R = 1,80668,447,447,447
BEGIN DESCRIPTION:
North Twin Creek80667.87
END DESCRIPTION:
XS GIS Cut Line= 3
      2743899.35      6836262.19      2743357.79      6836789.57
      2742920.59      6837265.52
#Sta/Elev= 30
  4266.8  407.51  4296.7  405.17  4565.3  401.14  4798.8  399.06  4982.7  400.07
  4989.6  399.08  4995.6  390.50  4996.1  390.00  5012.0  390.50  5017.9  392.51
  5020.5  395.38  5027.1  395.38  5032.1  397.46  5053.1  399.25  5060.5  397.53
  5084.3  398.57  5109.8  404.03  5131.4  405.46  5138.2  403.17  5145.5  404.58
  5166.5  401.52  5227.5  401.68  5251.6  401.62  5258.4  402.41  5265.8  405.72
  5272.6  403.57  5286.7  405.96  5378.6  410.28  5506.2  412.86  5669.0  421.39
#Mann=5,-1,0
  4266.8    0.05       0  4995.6    0.05       0  5012.0    0.05       0
  5084.3    0.16       0  5227.5    0.05       0
Bank Sta=4995.6,5012
Exp/Cntr=0.3,0.1

Type RM Length L Ch R = 1,80221,588,588,588
BEGIN DESCRIPTION:
North Twin Creek80220.79
END DESCRIPTION:
XS GIS Cut Line= 3
      2743976.40      6835988.70      2743282.66      6836429.29
      2742812.03      6836755.75
#Sta/Elev= 30
  4186.7  407.53  4254.3  405.68  4275.5  406.55  4363.6  404.02  4400.0  401.77
  4421.2  402.93  4427.1  401.52  4463.5  401.64  4484.7  399.83  4521.1  403.35
  4979.3  397.90  4985.3  397.35  4997.1  390.28  4997.6  389.78  5013.9  390.28
  5015.4  395.16  5021.3  398.41  5028.8  399.35  5047.5  398.54  5132.8  399.02
  5143.8  399.94  5150.5  398.80  5187.0  399.17  5266.0  401.98  5301.8  403.88
  5352.5  409.12  5358.6  411.56  5367.3  410.68  5438.9  415.20  5581.3  418.42
#Mann=6,-1,0
  4186.7    0.05       0  4997.1    0.05       0  5013.9    0.05       0
  5021.3    0.12       0  5047.5    0.16       0  5132.8    0.05       0
Bank Sta=4997.1,5013.9
Exp/Cntr=0.3,0.1