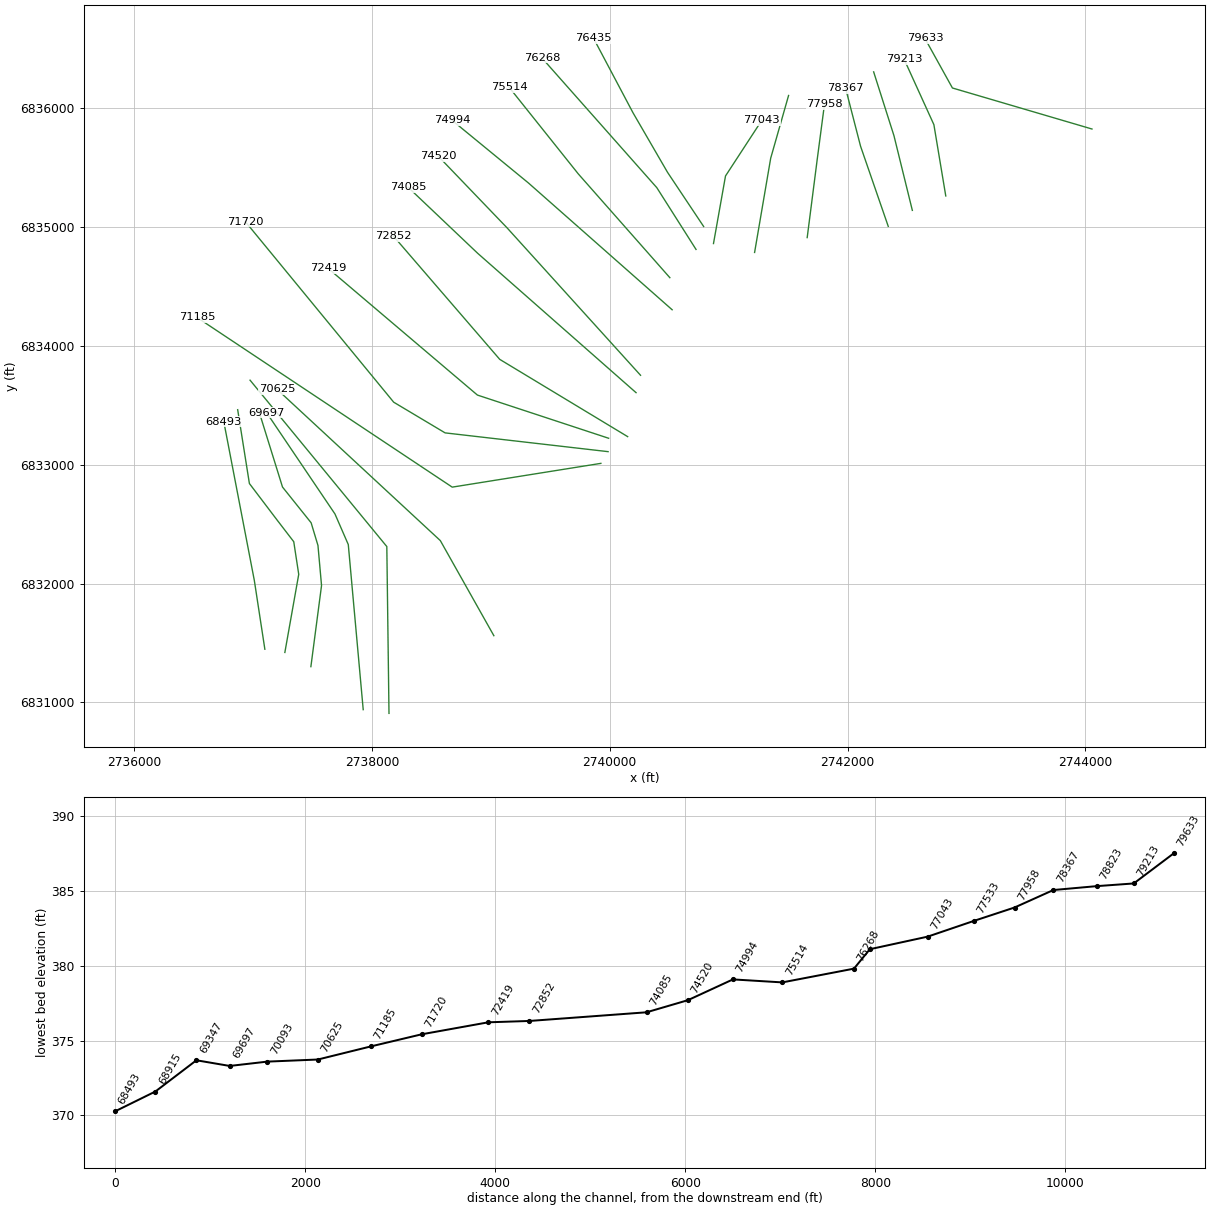
HEC-RAS study North Twin Creek.prj: North Twin Creek Base Level Engineering

--- North Twin Creek.g01 (geometry) --- (continued)

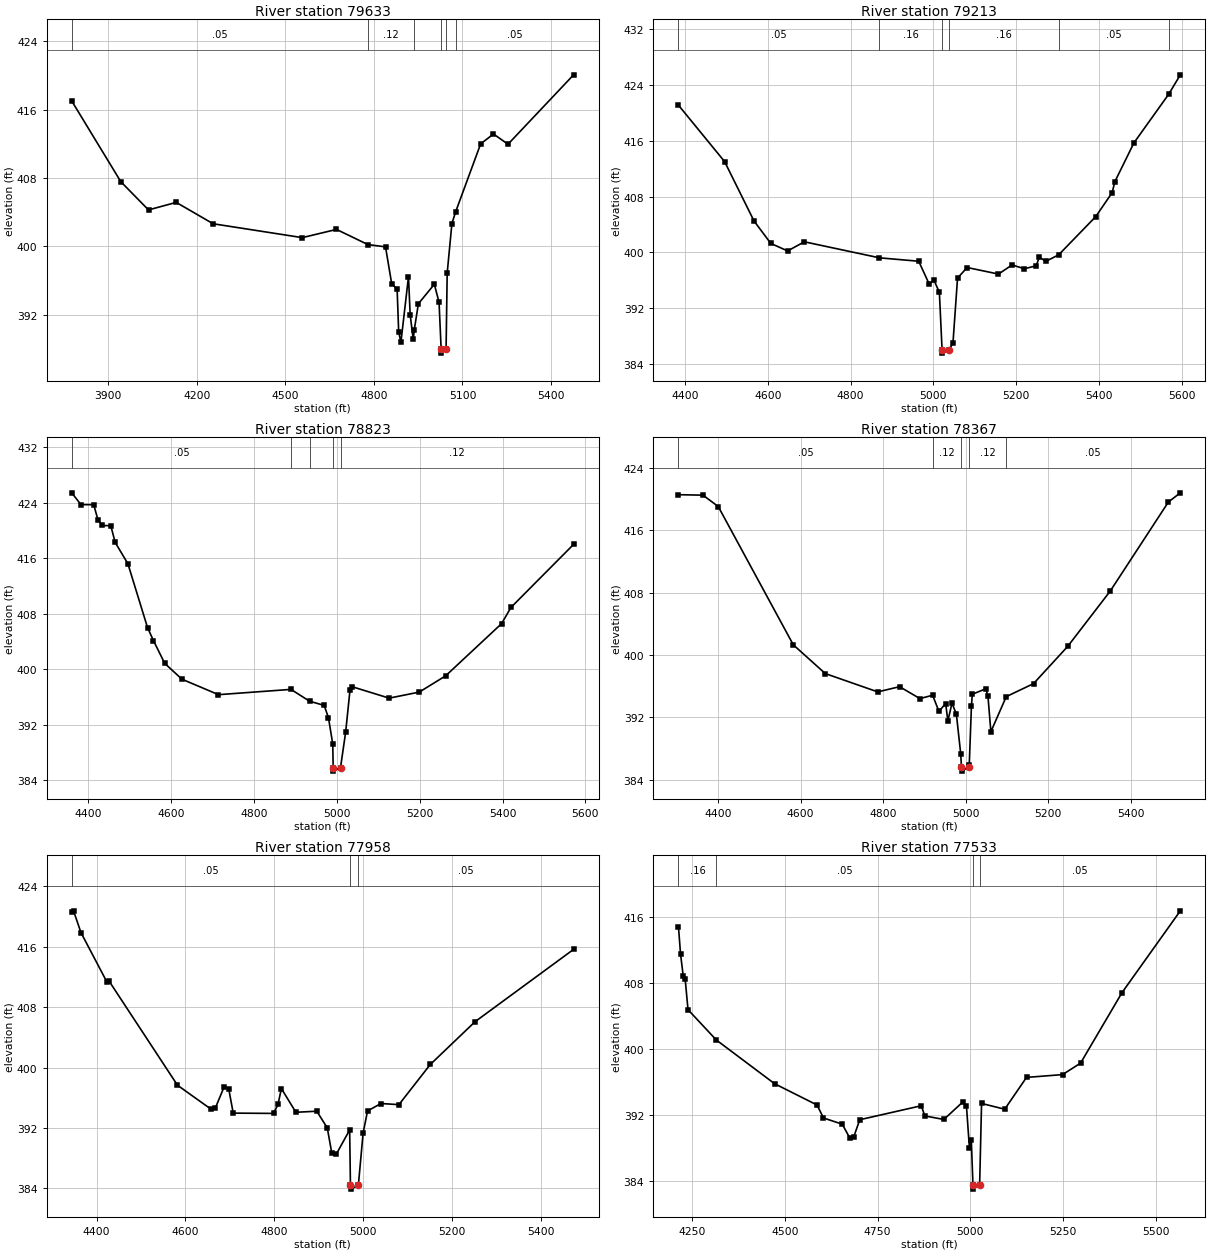
Type RM Length L Ch R = 1,79633,420,420,420
BEGIN DESCRIPTION:
North Twin Creek79633.3
END DESCRIPTION:
XS GIS Cut Line= 3
      2744055.30      6835824.31      2742881.91      6836169.45
      2742650.98      6836586.03
#Sta/Elev= 30
  3776.9  417.00  3943.0  407.57  4036.8  404.27  4130.6  405.15  4255.7  402.65
  4557.6  401.03  4673.3  401.99  4779.7  400.22  4839.4  399.95  4860.2  395.66
  4878.7  395.00  4883.9  390.04  4891.5  388.80  4917.2  396.47  4922.8  392.04
  4933.2  389.13  4937.0  390.29  4950.6  393.30  5004.7  395.58  5020.7  393.46
  5027.7  388.03  5028.2  387.53  5044.5  388.03  5048.2  396.88  5064.2  402.68
  5077.2  404.08  5161.5  411.99  5205.0  413.14  5254.2  411.95  5476.3  420.06
#Mann=6,-1,0
  3776.9    0.05       0  4779.7    0.12       0  4937.0    0.16       0
  5027.7    0.07       0  5044.5    0.16       0  5077.2    0.05       0
Bank Sta=5027.7,5044.5
Exp/Cntr=0.3,0.1

Type RM Length L Ch R = 1,79213,390,390,390
BEGIN DESCRIPTION:
North Twin Creek79213.331
END DESCRIPTION:
XS GIS Cut Line= 3
      2742826.00      6835260.99      2742726.00      6835861.00
      2742476.01      6836410.97
#Sta/Elev= 30
  4384.3  421.11  4495.8  413.01  4566.8  404.49  4607.3  401.27  4647.9  400.19
  4688.4  401.50  4869.9  399.20  4964.7  398.71  4990.0  395.43  5001.4  396.00
  5014.6  394.25  5021.1  386.02  5021.6  385.52  5038.8  386.02  5047.5  387.03
  5058.5  396.29  5081.6  397.81  5157.4  396.87  5190.3  398.18  5220.0  397.63
  5248.5  398.06  5256.2  399.31  5271.6  398.69  5302.8  399.63  5392.4  405.12
  5432.0  408.56  5438.6  410.14  5484.7  415.71  5568.2  422.65  5596.7  425.47
#Mann=6,-1,0
  4384.3    0.05       0  4869.9    0.16       0  5021.1    0.07       0
  5038.8    0.16       0  5302.8    0.05       0  5568.2    0.12       0
Bank Sta=5021.1,5038.8
Exp/Cntr=0.3,0.1

Type RM Length L Ch R = 1,78823,456,456,456
BEGIN DESCRIPTION:
North Twin Creek78822.81
END DESCRIPTION:
XS GIS Cut Line= 3
      2742544.90      6835139.55      2742390.31      6835767.97
      2742219.53      6836305.12
#Sta/Elev= 30
  4360.7  425.45  4382.8  423.75  4413.7  423.74  4424.0  421.53  4434.3  420.75
  4454.9  420.70  4465.5  418.30  4496.1  415.24  4543.5  406.03  4557.9  404.14
  4585.0  400.87  4626.5  398.59  4714.7  396.36  4889.6  397.12  4934.4  395.42
  4969.8  394.81  4980.1  393.02  4990.4  389.25  4991.4  385.84  4991.9  385.34
  5009.1  385.84  5021.5  390.94  5032.0  397.03  5037.9  397.49  5126.5  395.86
  5199.1  396.73  5262.9  399.08  5397.8  406.60  5420.3  408.93  5571.5  418.02
#Mann=5,-1,0
  4360.7    0.05       0  4889.6    0.16       0  4934.4    0.12       0
  4991.4    0.07       0  5009.1    0.12       0
Bank Sta=4991.4,5009.1
Exp/Cntr=0.3,0.1

Type RM Length L Ch R = 1,78367,409,409,409
BEGIN DESCRIPTION:
North Twin Creek78367.08
END DESCRIPTION:
XS GIS Cut Line= 3
      2742342.40      6835004.86      2742109.59      6835679.01
      2741984.12      6836165.26
#Sta/Elev= 30
  4304.4  420.56  4363.8  420.50  4400.7  419.04  4582.5  401.29  4660.0  397.60
  4787.0  395.25  4839.9  395.92  4889.1  394.39  4919.9  394.82  4935.1  392.76
  4951.5  393.75  4956.8  391.52  4966.8  393.80  4977.4  392.40  4988.0  387.29
  4989.7  385.58  4990.2  385.08  5007.5  385.58  5008.6  385.84  5013.9  393.45
  5016.0  394.95  5048.8  395.65  5053.9  394.69  5061.0  390.14  5098.2  394.64
  5164.3  396.31  5246.9  401.08  5350.2  408.20  5490.9  419.62  5519.8  420.80
#Mann=5,-1,0
  4304.4    0.05       0  4919.9    0.12       0  4989.7    0.07       0
  5007.5    0.12       0  5098.2    0.05       0
Bank Sta=4989.7,5007.5
Exp/Cntr=0.3,0.1

Type RM Length L Ch R = 1,77958,425,425,425
BEGIN DESCRIPTION:
North Twin Creek77958.42
END DESCRIPTION:
XS GIS Cut Line= 3
      2741660.69      6834910.45      2741746.16      6835577.47
      2741805.87      6836030.89
#Sta/Elev= 30
  4344.3  420.61  4348.3  420.74  4365.0  417.86  4423.0  411.37  4428.0  411.47
  4582.3  397.66  4656.9  394.53  4667.5  394.63  4687.6  397.49  4697.7  397.18
  4707.8  393.97  4798.5  393.93  4808.6  395.11  4816.2  397.22  4848.9  394.08
  4895.9  394.22  4919.5  392.02  4929.6  388.72  4939.7  388.52  4969.9  391.74
  4971.7  384.41  4972.2  383.91  4989.5  384.41  5000.2  391.32  5010.2  394.26
  5040.5  395.24  5080.8  395.09  5151.5  400.41  5252.3  406.07  5474.1  415.64
#Mann=3,-1,0
  4344.3    0.05       0  4971.7    0.05       0  4989.5    0.05       0
Bank Sta=4971.7,4989.5
Exp/Cntr=0.3,0.1

Type RM Length L Ch R = 1,77533,490,490,490
BEGIN DESCRIPTION:
North Twin Creek77532.85
END DESCRIPTION:
XS GIS Cut Line= 3
      2741218.45      6834785.62      2741353.82      6835578.50
      2741504.21      6836106.45
#Sta/Elev= 30
  4212.9  414.75  4218.4  411.51  4225.7  408.80  4230.8  408.51  4238.6  404.74
  4314.9  401.07  4472.0  395.78  4586.6  393.20  4603.9  391.63  4654.6  390.88
  4674.9  389.20  4685.0  389.28  4701.8  391.42  4867.6  393.11  4877.2  391.88
  4928.5  391.45  4979.2  393.55  4989.4  393.13  4997.5  387.99  5002.5  388.97
  5007.0  383.52  5007.5  383.02  5025.0  383.52  5030.2  393.39  5092.6  392.69
  5151.4  396.54  5248.6  396.88  5297.2  398.27  5409.1  406.81  5566.2  416.70
#Mann=4,-1,0
  4212.9    0.16       0  4314.9    0.05       0  5007.0    0.05       0
  5025.0    0.05       0
Bank Sta=5007,5025
Exp/Cntr=0.3,0.1

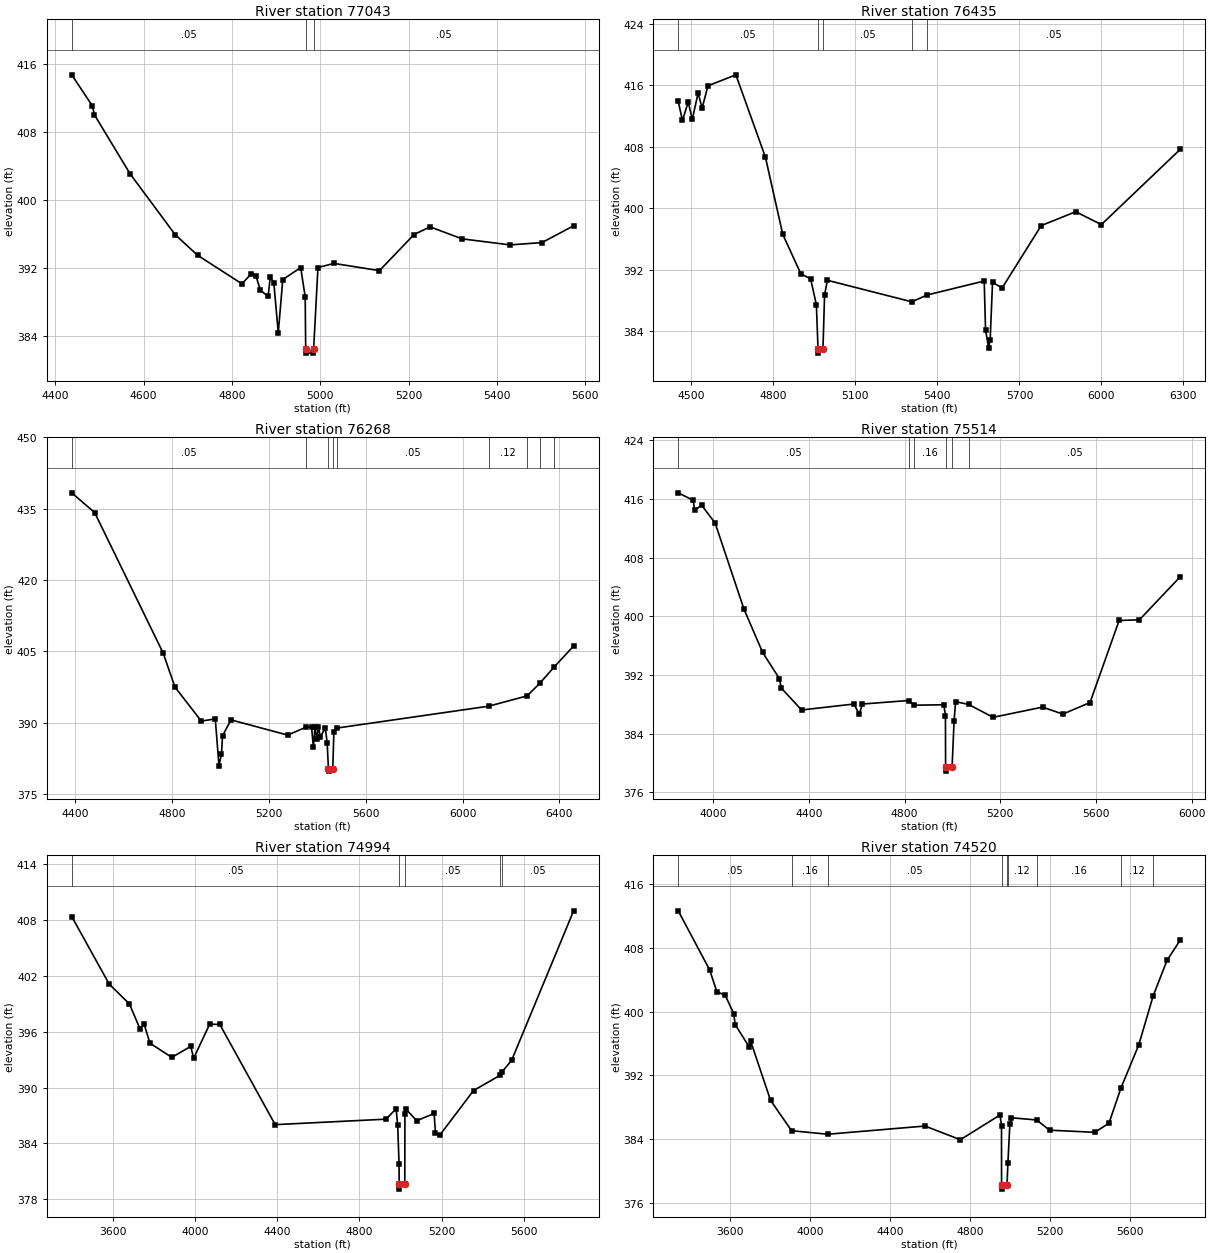
Type RM Length L Ch R = 1,77043,608,608,608
BEGIN DESCRIPTION:
North Twin Creek77042.66
END DESCRIPTION:
XS GIS Cut Line= 3
      2740872.83      6834860.47      2740973.89      6835429.17
      2741279.15      6835897.45
#Sta/Elev= 30
  4437.3  414.69  4483.8  411.05  4488.8  409.97  4569.9  403.01  4671.4  395.90
  4722.2  393.47  4822.8  390.11  4844.1  391.31  4854.3  391.06  4864.4  389.37
  4881.9  388.62  4886.9  390.87  4894.9  390.25  4905.0  384.34  4915.2  390.61
  4955.8  392.02  4966.0  388.59  4967.1  382.46  4967.6  381.96  4984.6  381.96
  4985.1  382.46  4994.9  392.03  5031.5  392.51  5134.1  391.66  5212.6  395.91
  5248.8  396.81  5321.2  395.40  5429.9  394.69  5502.3  394.96  5573.9  396.94
#Mann=3,-1,0
  4437.3    0.05       0  4967.1    0.05       0  4985.1    0.05       0
Bank Sta=4967.1,4985.1
Exp/Cntr=0.3,0.1

Type RM Length L Ch R = 1,76435,167,167,167
BEGIN DESCRIPTION:
North Twin Creek76524.664
END DESCRIPTION:
XS GIS Cut Line= 4
      2740790.09      6835003.94      2740486.28      6835460.01
      2740196.13      6835960.79      2739864.51      6836587.27
#Sta/Elev= 30
  4452.0  413.89  4467.4  411.41  4488.5  413.81  4503.5  411.55  4524.5  414.97
  4539.6  413.03  4560.6  415.92  4662.8  417.35  4771.0  406.62  4834.1  396.61
  4900.2  391.46  4936.2  390.79  4957.3  387.42  4963.3  381.62  4963.8  381.12
  4981.3  381.62  4987.3  388.71  4997.6  390.60  5306.6  387.80  5362.4  388.69
  5571.1  390.51  5576.0  384.14  5587.2  381.82  5592.9  382.82  5601.6  390.32
  5636.9  389.62  5779.6  397.72  5905.9  399.53  5999.6  397.85  6287.6  407.63
#Mann=5,-1,0
  4452.0    0.05       0  4963.3    0.05       0  4981.3    0.05       0
  5306.6    0.12       0  5362.4    0.05       0
Bank Sta=4963.3,4981.3
Exp/Cntr=0.3,0.1

Type RM Length L Ch R = 1,76268,754,754,754
BEGIN DESCRIPTION:
North Twin Creek76268.006
END DESCRIPTION:
XS GIS Cut Line= 3
      2740726.00      6834811.00      2740396.54      6835330.43
      2739429.77      6836422.88
#Sta/Elev= 30
  4384.9  438.35  4479.6  434.19  4762.8  404.63  4811.2  397.51  4920.3  390.34
  4978.0  390.80  4993.2  381.00  5003.7  383.40  5007.9  387.26  5043.0  390.60
  5277.2  387.40  5352.9  389.06  5375.9  389.09  5383.5  384.81  5390.1  389.20
  5397.7  386.56  5404.4  389.17  5411.9  387.05  5432.8  388.82  5440.4  385.79
  5445.6  380.32  5446.1  379.82  5463.6  380.32  5468.1  388.15  5480.9  388.88
  6108.1  393.48  6266.3  395.64  6318.6  398.26  6377.3  401.66  6458.8  406.13
#Mann=9,-1,0
  4384.9    0.05       0  5352.9    0.12       0  5445.6    0.05       0
  5463.6    0.12       0  5480.9    0.05       0  6108.1    0.12       0
  6266.3    0.16       0  6318.6    0.05       0  6377.3    0.16       0
Bank Sta=5445.6,5463.6
Exp/Cntr=0.3,0.1

Type RM Length L Ch R = 1,75514,520,520,520
BEGIN DESCRIPTION:
North Twin Creek75514.47
END DESCRIPTION:
XS GIS Cut Line= 3
      2740505.86      6834573.40      2739735.68      6835446.97
      2739153.30      6836176.91
#Sta/Elev= 30
  3853.5  416.81  3915.8  415.79  3922.5  414.42  3950.9  415.14  4007.8  412.69
  4128.3  400.97  4206.1  395.09  4276.9  391.48  4283.9  390.23  4369.3  387.23
  4588.4  388.04  4610.2  386.64  4623.6  388.04  4816.7  388.52  4840.0  387.88
  4964.1  387.94  4970.8  386.46  4971.4  379.40  4971.9  378.90  4998.5  379.40
  5006.8  385.71  5013.4  388.37  5067.9  387.98  5170.1  386.23  5376.7  387.62
  5461.6  386.67  5575.3  388.24  5697.0  399.42  5781.8  399.51  5951.9  405.36
#Mann=6,-1,0
  3853.5    0.05       0  4816.7    0.12       0  4840.0    0.16       0
  4971.4    0.07       0  4998.5    0.16       0  5067.9    0.05       0
Bank Sta=4971.4,4998.5
Exp/Cntr=0.3,0.1

Type RM Length L Ch R = 1,74994,474,474,474
BEGIN DESCRIPTION:
Mapping XS b06896bc
END DESCRIPTION:
XS GIS Cut Line= 3
      2740525.16      6834303.47      2739316.95      6835370.09
      2738676.34      6835896.02
#Sta/Elev= 30
  3400.9  408.35  3582.9  401.11  3681.6  398.97  3731.9  396.34  3752.8  396.81
  3781.2  394.76  3887.4  393.24  3979.5  394.42  3993.7  393.15  4071.5  396.80
  4120.8  396.78  4390.2  386.02  4929.0  386.61  4978.3  387.72  4985.9  385.95
  4992.5  381.84  4993.2  379.60  4993.7  379.10  5020.3  379.60  5021.1  387.18
  5027.5  387.65  5078.5  386.44  5163.1  387.22  5169.6  385.11  5191.8  384.93
  5354.7  389.68  5483.2  391.31  5492.0  391.65  5539.9  392.92  5841.4  408.97
#Mann=5,-1,0
  3400.9    0.05       0  4993.2    0.05       0  5020.3    0.05       0
  5483.2    0.12       0  5492.0    0.05       0
Bank Sta=4993.2,5020.3
Exp/Cntr=0.3,0.1

Type RM Length L Ch R = 1,74520,435,435,435
BEGIN DESCRIPTION:
North Twin Creek74519.88
END DESCRIPTION:
XS GIS Cut Line= 3
      2740259.40      6833752.21      2739136.70      6834993.14
      2738558.17      6835595.89
#Sta/Elev= 30
  3342.3  412.69  3499.8  405.24  3534.9  402.54  3577.5  402.06  3620.1  399.75
  3626.9  398.39  3697.8  395.56  3704.8  396.27  3804.0  388.86  3909.2  385.05
  4090.1  384.61  4575.8  385.64  4752.9  383.92  4950.9  387.03  4958.4  385.67
  4958.7  378.21  4959.2  377.71  4986.0  378.21  4990.4  380.99  5000.3  385.91
  5007.7  386.68  5134.4  386.40  5198.6  385.12  5425.0  384.85  5495.7  386.00
  5556.2  390.46  5644.2  395.81  5716.7  402.00  5785.7  406.46  5851.2  408.98
#Mann=9,-1,0
  3342.3    0.05       0  3909.2    0.16       0  4090.1    0.05       0
  4958.7    0.07       0  4986.0    0.05       0  4990.4    0.12       0
  5134.4    0.16       0  5556.2    0.12       0  5716.7    0.05       0
Bank Sta=4958.7,4986
Exp/Cntr=0.3,0.1

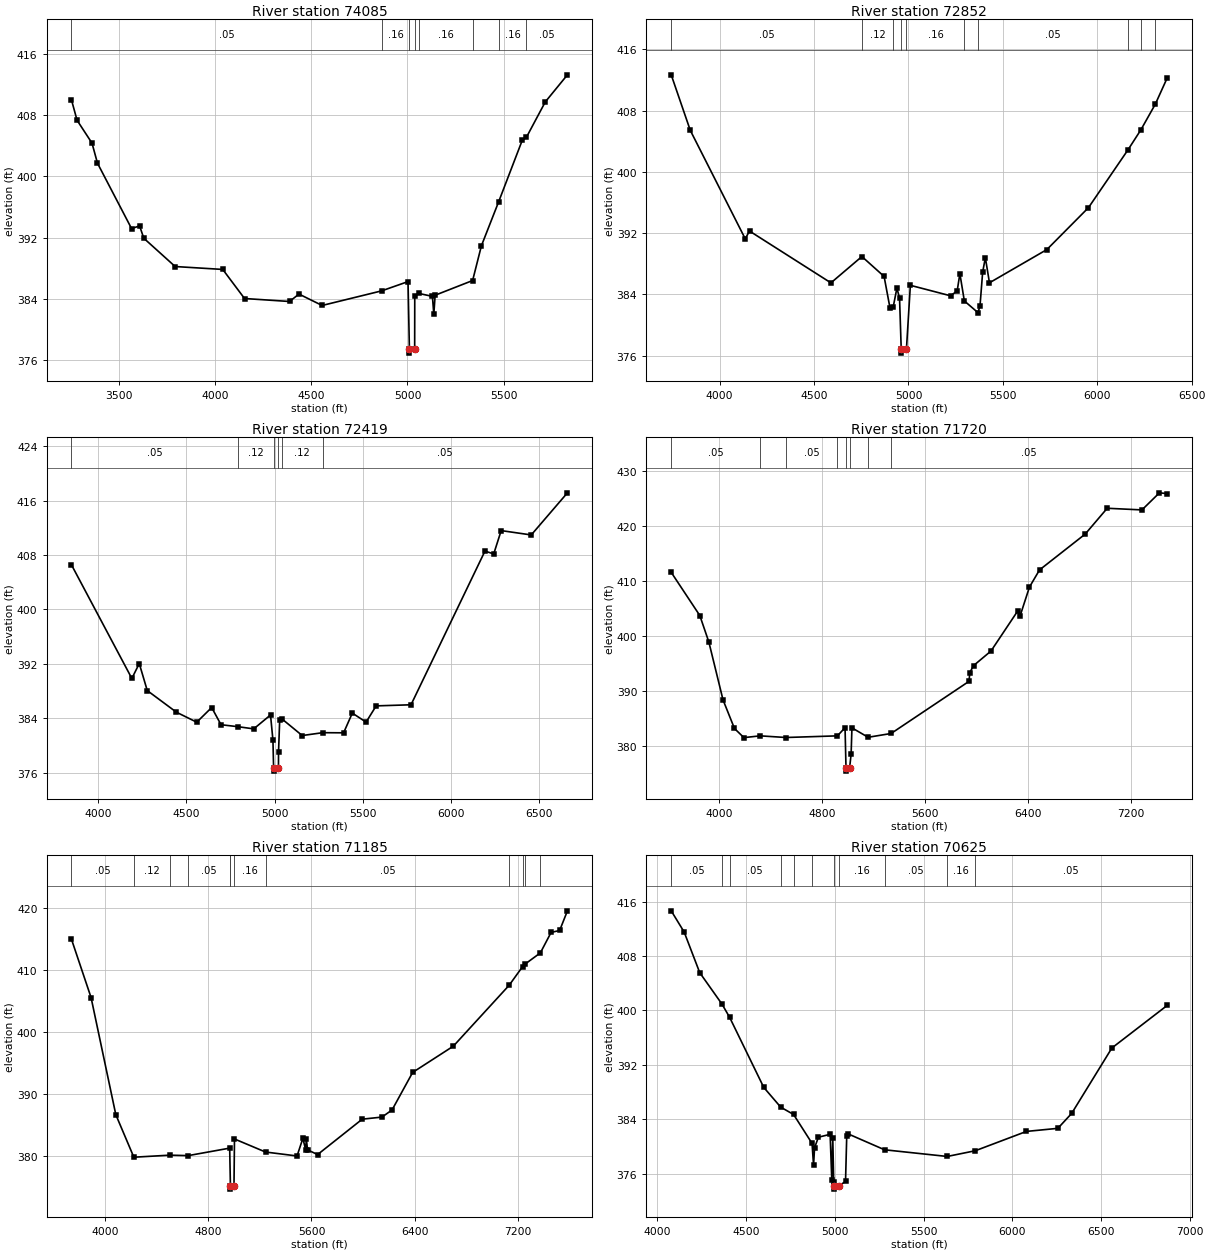
Type RM Length L Ch R = 1,74085,1233,1233,1233
BEGIN DESCRIPTION:
North Twin Creek74084.55
END DESCRIPTION:
XS GIS Cut Line= 3
      2740221.76      6833605.82      2738889.05      6834779.44
      2738305.75      6835333.64
#Sta/Elev= 30
  3251.8  410.01  3280.9  407.34  3358.7  404.35  3387.1  401.73  3564.5  393.18
  3606.3  393.53  3628.1  391.92  3791.3  388.22  4038.9  387.84  4152.2  384.04
  4386.2  383.65  4435.5  384.62  4556.0  383.13  4865.7  385.04  5002.8  386.25
  5010.0  377.40  5010.5  376.90  5037.4  377.40  5037.9  384.40  5059.5  384.70
  5129.8  384.32  5137.0  381.97  5143.9  384.47  5338.9  386.39  5384.6  390.93
  5474.9  396.72  5596.9  404.71  5618.3  405.09  5717.0  409.74  5832.2  413.28
#Mann=8,-1,0
  3251.8    0.05       0  4865.7    0.16       0  5010.0    0.07       0
  5037.4    0.16       0  5059.5    0.16       0  5338.9    0.12       0
  5474.9    0.16       0  5618.3    0.05       0
Bank Sta=5010,5037.4
Exp/Cntr=0.3,0.1

Type RM Length L Ch R = 1,72852,433,433,433
BEGIN DESCRIPTION:
North Twin Creek72851.692
END DESCRIPTION:
XS GIS Cut Line= 3
      2740151.03      6833235.98      2739075.52      6833886.04
      2738180.95      6834924.04
#Sta/Elev= 30
  3743.3  412.68  3844.2  405.43  4135.3  391.26  4158.1  392.27  4589.3  385.50
  4753.3  388.94  4870.9  386.34  4901.7  382.28  4919.6  382.41  4938.6  384.80
  4952.7  383.53  4961.6  376.82  4962.1  376.32  4989.2  376.82  5010.0  385.18
  5222.9  383.81  5258.0  384.45  5272.3  386.71  5295.9  383.14  5367.6  381.62
  5378.7  382.44  5392.9  386.89  5407.2  388.79  5429.0  385.51  5733.0  389.85
  5953.5  395.33  6163.5  402.91  6231.4  405.51  6307.5  408.85  6370.3  412.27
#Mann=10,-1,0
  3743.3    0.05       0  4753.3    0.12       0  4919.6    0.16       0
  4961.6    0.07       0  4989.2    0.16       0  5295.9    0.12       0
  5367.6    0.05       0  6163.5    0.16       0  6231.4    0.05       0
  6307.5    0.16       0
Bank Sta=4961.6,4989.2
Exp/Cntr=0.3,0.1

Type RM Length L Ch R = 1,72419,699,699,699
BEGIN DESCRIPTION:
North Twin Creek72418.68
END DESCRIPTION:
XS GIS Cut Line= 3
      2739991.19      6833222.20      2738887.81      6833585.62
      2737629.60      6834654.15
#Sta/Elev= 30
  3848.4  406.55  4190.8  389.85  4232.9  392.04  4278.2  388.07  4443.5  384.89
  4558.9  383.42  4643.5  385.58  4696.5  383.05  4792.6  382.76  4881.9  382.44
  4977.2  384.48  4990.9  380.76  4994.6  376.73  4995.1  376.23  5022.2  376.73
  5022.6  379.05  5029.1  383.71  5040.7  383.93  5156.8  381.46  5273.3  381.88
  5391.6  381.86  5441.0  384.76  5519.0  383.43  5576.2  385.82  5773.8  385.98
  6193.2  408.57  6242.8  408.15  6285.1  411.58  6455.6  410.94  6660.8  417.13
#Mann=6,-1,0
  3848.4    0.05       0  4792.6    0.12       0  4994.6    0.07       0
  5022.2    0.12       0  5040.7    0.12       0  5273.3    0.05       0
Bank Sta=4994.6,5022.2
Exp/Cntr=0.3,0.1

Type RM Length L Ch R = 1,71720,535,535,535
BEGIN DESCRIPTION:
North Twin Creek71720.26
END DESCRIPTION:
XS GIS Cut Line= 4
      2739986.49      6833109.53      2738616.18      6833267.44
      2738183.92      6833525.60      2736935.63      6835045.93
#Sta/Elev= 30
  3631.3  411.61  3853.3  403.75  3923.7  398.91  4033.3  388.41  4122.3  383.19
  4195.5  381.53  4322.1  381.85  4521.9  381.55  4921.6  381.85  4980.7  383.34
  4988.2  375.93  4988.7  375.43  5015.8  375.93  5027.9  378.56  5034.2  383.31
  5159.9  381.59  5338.1  382.28  5943.0  391.77  5949.4  393.37  5978.1  394.63
  6113.7  397.29  6319.7  404.53  6340.5  403.75  6412.2  408.93  6490.4  412.05
  6844.9  418.57  7015.7  423.27  7285.5  422.97  7421.1  426.08  7481.3  425.94
#Mann=8,-1,0
  3631.3    0.05       0  4322.1    0.16       0  4521.9    0.05       0
  4921.6    0.16       0  4988.2    0.07       0  5015.8    0.16       0
  5159.9    0.07       0  5338.1    0.05       0
Bank Sta=4988.2,5015.8
Exp/Cntr=0.3,0.1

Type RM Length L Ch R = 1,71185,560,560,560
BEGIN DESCRIPTION:
North Twin Creek71184.973
END DESCRIPTION:
XS GIS Cut Line= 3
      2739926.02      6833011.00      2738676.00      6832811.00
      2736529.81      6834238.88
#Sta/Elev= 30
  3739.9  415.03  3891.8  405.60  4083.6  386.66  4223.4  379.78  4500.6  380.11
  4645.2  380.04  4966.1  381.25  4971.8  375.12  4972.3  374.62  4999.4  375.12
  5003.3  382.73  5243.7  380.62  5488.2  379.98  5533.3  382.84  5554.4  381.01
  5560.4  382.68  5569.4  380.97  5647.6  380.21  5993.2  385.93  6146.5  386.27
  6224.7  387.43  6384.0  393.49  6699.6  397.74  7132.2  407.59  7236.0  410.60
  7253.0  410.97  7373.8  412.82  7457.0  416.13  7523.2  416.44  7583.6  419.62
#Mann=12,-1,0
  3739.9    0.05       0  4223.4    0.12       0  4500.6    0.16       0
  4645.2    0.05       0  4966.1    0.16       0  4971.8    0.07       0
  4999.4    0.16       0  5243.7    0.05       0  7132.2   0.063       0
  7236.0    0.05       0  7253.0   0.063       0  7373.8    0.05       0
Bank Sta=4971.8,4999.4
Exp/Cntr=0.3,0.1

Type RM Length L Ch R = 1,70625,532,532,532
BEGIN DESCRIPTION:
North Twin Creek70624.762
END DESCRIPTION:
XS GIS Cut Line= 3
      2739026.01      6831560.98      2738576.00      6832361.00
      2737200.98      6833636.02
#Sta/Elev= 30
  4078.0  414.63  4151.0  411.51  4238.7  405.54  4364.6  400.90  4407.4  398.96
  4599.1  388.69  4694.8  385.78  4767.1  384.71  4871.2  380.46  4879.6  377.24
  4885.3  379.82  4907.0  381.37  4973.0  381.79  4982.2  375.15  4987.9  381.24
  4993.0  374.84  4995.9  374.24  4996.4  373.74  5023.7  374.24  5059.7  374.87
  5066.5  381.58  5073.9  381.86  5279.5  379.52  5632.2  378.54  5790.5  379.38
  6078.5  382.22  6255.4  382.67  6333.1  384.86  6559.8  394.48  6871.1  400.73
#Mann=11,-1,0
  4078.0    0.05       0  4364.6    0.16       0  4407.4    0.05       0
  4694.8    0.16       0  4767.1    0.12       0  4871.2    0.16       0
  4995.9    0.07       0  5023.7    0.16       0  5279.5    0.05       0
  5632.2    0.16       0  5790.5    0.05       0
Bank Sta=4995.9,5023.7
Exp/Cntr=0.3,0.1

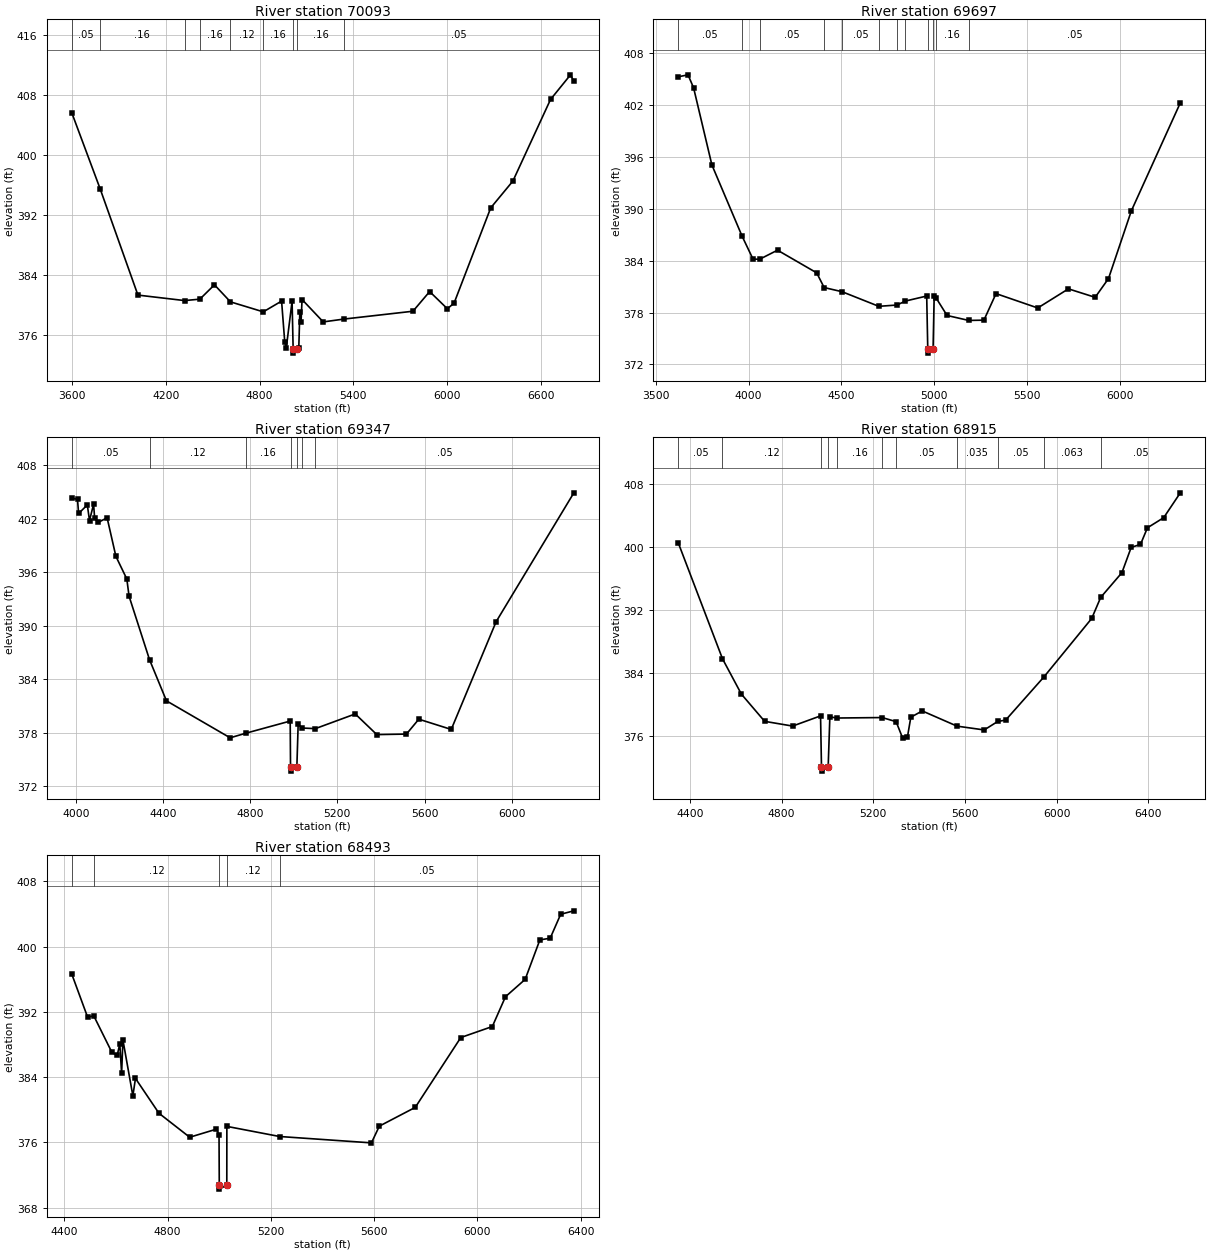
Type RM Length L Ch R = 1,70093,396,396,396
BEGIN DESCRIPTION:
North Twin Creek70092.873
END DESCRIPTION:
XS GIS Cut Line= 3
      2738144.32      6830907.30      2738126.00      6832311.00
      2736975.99      6833711.01
#Sta/Elev= 30
  3596.5  405.62  3777.6  395.52  4020.2  381.33  4319.0  380.60  4416.9  380.79
  4510.3  382.70  4612.7  380.43  4823.0  379.10  4940.3  380.53  4960.3  375.14
  4970.3  374.29  5007.5  380.51  5014.4  374.10  5014.9  373.60  5042.2  374.10
  5050.5  374.27  5057.0  379.06  5064.9  377.76  5071.4  380.74  5207.0  377.76
  5341.2  378.14  5781.7  379.18  5888.6  381.80  6002.0  379.51  6045.0  380.26
  6279.7  392.95  6421.7  396.52  6662.8  407.39  6790.6  410.67  6812.1  409.81
#Mann=9,-1,0
  3596.5    0.05       0  3777.6    0.16       0  4319.0    0.12       0
  4416.9    0.16       0  4612.7    0.12       0  4823.0    0.16       0
  5014.4    0.07       0  5042.2    0.16       0  5341.2    0.05       0
Bank Sta=5014.4,5042.2
Exp/Cntr=0.3,0.1

Type RM Length L Ch R = 1,69697,350,350,350
BEGIN DESCRIPTION:
North Twin Creek69696.582
END DESCRIPTION:
XS GIS Cut Line= 4
      2737927.56      6830938.53      2737802.01      6832327.88
      2737690.11      6832585.00      2737115.43      6833437.46
#Sta/Elev= 30
  3621.3  405.25  3674.0  405.48  3704.1  403.97  3802.4  395.07  3964.9  386.84
  4023.9  384.18  4059.4  384.16  4155.9  385.21  4366.8  382.59  4407.0  380.89
  4503.3  380.41  4701.3  378.72  4799.4  378.87  4844.5  379.33  4959.2  379.91
  4964.9  373.81  4965.4  373.31  4993.6  373.81  4999.4  379.92  5009.4  379.70
  5068.9  377.66  5185.4  377.09  5267.3  377.12  5332.5  380.19  5557.2  378.53
  5722.3  380.74  5866.2  379.76  5938.1  381.93  6061.0  389.75  6324.8  402.24
#Mann=12,-1,0
  3621.3    0.05       0  3964.9    0.16       0  4059.4    0.05       0
  4407.0    0.16       0  4503.3    0.05       0  4701.3    0.12       0
  4799.4    0.16       0  4844.5    0.12       0  4964.9    0.07       0
  4993.6    0.12       0  5009.4    0.16       0  5185.4    0.05       0
Bank Sta=4964.9,4993.6
Exp/Cntr=0.3,0.1

Type RM Length L Ch R = 1,69347,432,432,432
BEGIN DESCRIPTION:
North Twin Creek69347.4
END DESCRIPTION:
XS GIS Cut Line= 6
      2737487.52      6831300.33      2737577.13      6831983.05
      2737547.10      6832320.04      2737489.67      6832510.90
      2737248.89      6832811.72      2737043.68      6833471.87
#Sta/Elev= 30
  3981.6  404.33  4007.9  404.21  4012.9  402.61  4052.9  403.57  4063.0  401.82
  4081.6  403.65  4086.7  402.05  4103.3  401.61  4143.7  402.13  4184.0  397.80
  4234.1  395.26  4244.5  393.32  4338.3  386.20  4416.0  381.58  4708.2  377.43
  4780.5  377.95  4983.6  379.31  4985.1  374.19  4985.6  373.69  5014.2  374.19
  5020.2  378.97  5038.3  378.53  5099.0  378.46  5282.0  380.11  5380.9  377.79
  5516.9  377.85  5573.6  379.52  5722.4  378.37  5928.2  390.46  6284.8  404.93
#Mann=7,-1,0
  3981.6    0.05       0  4338.3    0.12       0  4780.5    0.16       0
  4985.1    0.07       0  5014.2    0.16       0  5038.3   0.035       0
  5099.0    0.05       0
Bank Sta=4985.1,5014.2
Exp/Cntr=0.3,0.1

Type RM Length L Ch R = 1,68915,422,422,422
BEGIN DESCRIPTION:
North Twin Creek68914.79
END DESCRIPTION:
XS GIS Cut Line= 6
      2737268.68      6831419.88      2737385.34      6832077.21
      2737343.56      6832351.58      2737202.55      6832535.27
      2736970.47      6832841.49      2736871.99      6833462.59
#Sta/Elev= 30
  4349.4  400.54  4542.4  385.84  4624.8  381.36  4726.3  377.91  4848.2  377.31
  4970.1  378.60  4974.2  372.10  4974.7  371.60  5003.3  372.10  5010.7  378.48
  5041.5  378.33  5238.8  378.39  5299.6  377.87  5328.5  375.76  5349.3  375.96
  5363.8  378.43  5413.6  379.23  5565.5  377.30  5683.9  376.82  5742.7  377.89
  5777.5  378.07  5944.1  383.53  6152.8  390.95  6192.0  393.62  6284.5  396.75
  6325.0  399.96  6365.5  400.33  6395.8  402.44  6466.7  403.72  6539.2  406.87
#Mann=11,-1,0
  4349.4    0.05       0  4542.4    0.12       0  4974.2    0.07       0
  5003.3    0.12       0  5041.5    0.16       0  5238.8   0.035       0
  5299.6    0.05       0  5565.5   0.035       0  5742.7    0.05       0
  5944.1   0.063       0  6192.0    0.05       0
Bank Sta=4974.2,5003.3
Exp/Cntr=0.3,0.1

Type RM Length L Ch R = 1,68493,339,339,339
BEGIN DESCRIPTION:
North Twin Creek68492.93
END DESCRIPTION:
XS GIS Cut Line= 3
      2737100.50      6831447.06      2737011.82      6832026.79
      2736755.37      6833361.09
#Sta/Elev= 30
  4429.0  396.64  4490.2  391.37  4514.4  391.51  4584.7  387.03  4605.0  386.69
  4615.1  388.07  4622.1  384.47  4627.2  388.56  4665.7  381.71  4675.8  383.85
  4766.8  379.58  4885.9  376.64  4989.4  377.63  4999.5  376.97  5000.5  370.78
  5001.0  370.28  5029.6  370.78  5029.9  377.97  5234.2  376.73  5590.0  375.95
  5620.6  378.00  5759.8  380.30  5936.2  388.86  6058.4  390.21  6109.3  393.86
  6185.6  395.99  6242.6  400.83  6282.5  401.03  6323.2  403.97  6374.2  404.39
#Mann=5,-1,0
  4429.0    0.16       0  4514.4    0.12       0  5000.5    0.07       0
  5029.6    0.12       0  5234.2    0.05       0
Bank Sta=5000.5,5029.6
Exp/Cntr=0.3,0.1