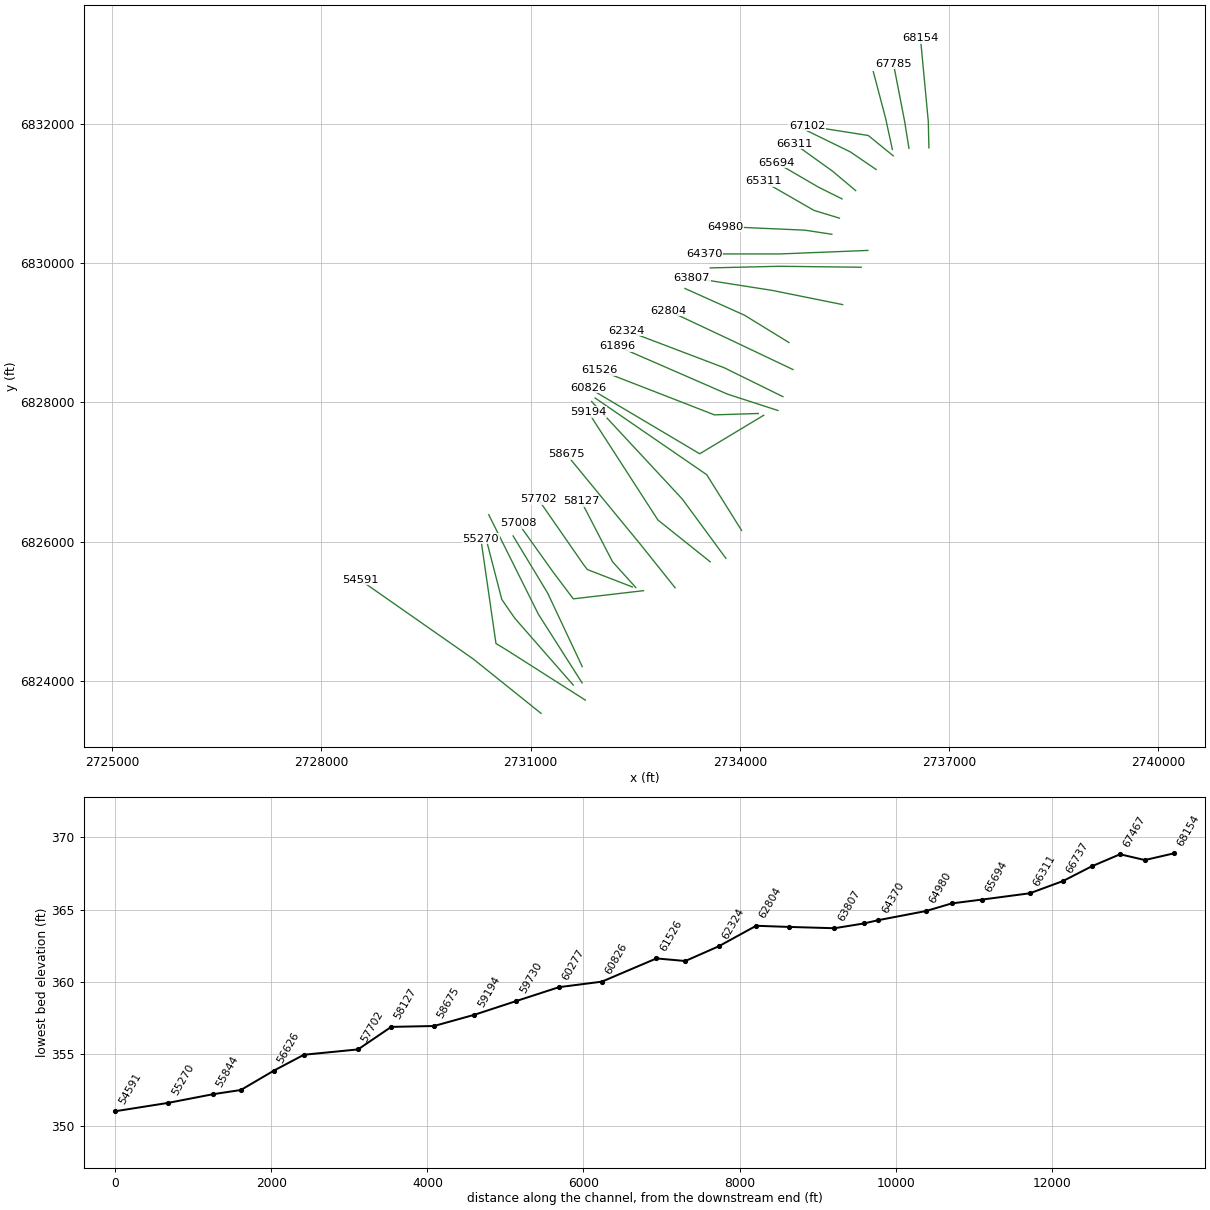
HEC-RAS study North Twin Creek.prj: North Twin Creek Base Level Engineering

--- North Twin Creek.g01 (geometry) --- (continued)

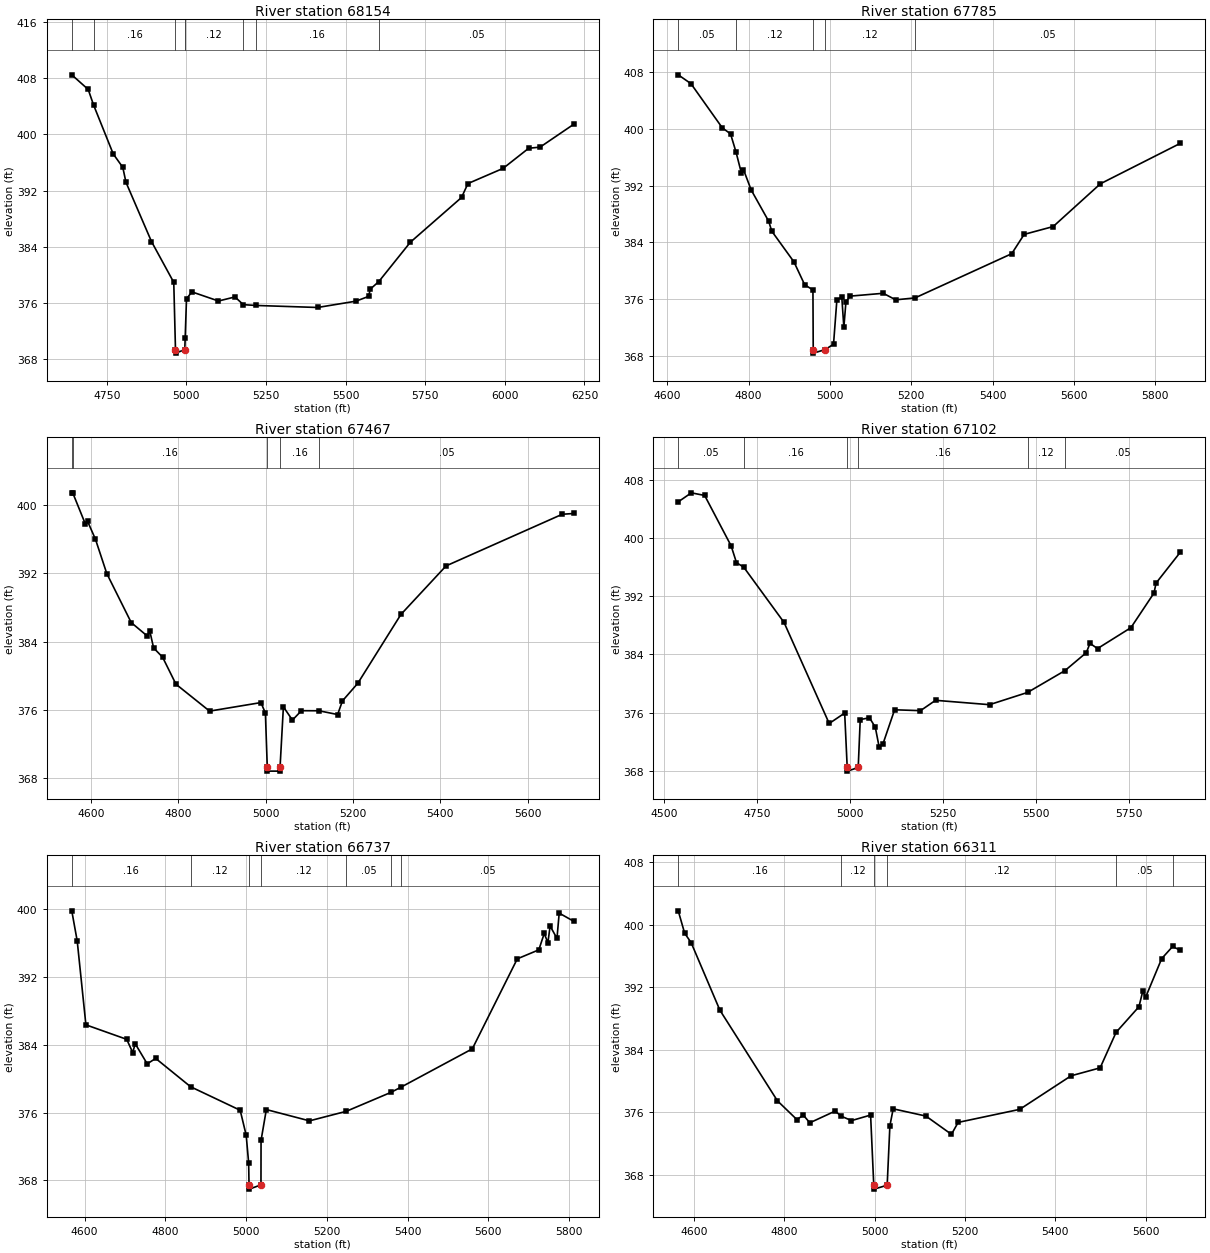
Type RM Length L Ch R = 1,68154,369,369,369
BEGIN DESCRIPTION:
North Twin Creek68154.08
END DESCRIPTION:
XS GIS Cut Line= 3
      2736712.14      6831650.81      2736703.16      6832029.87
      2736591.15      6833222.15
#Sta/Elev= 30
  4640.0  408.46  4691.6  406.38  4708.3  404.19  4770.2  397.21  4800.2  395.31
  4810.2  393.18  4890.3  384.76  4960.3  378.95  4965.7  369.39  4966.2  368.89
  4994.9  369.39  4996.1  370.99  5000.3  376.61  5017.2  377.60  5100.7  376.30
  5152.5  376.88  5178.7  375.78  5217.8  375.67  5412.0  375.38  5532.6  376.28
  5572.3  376.96  5577.3  377.98  5604.3  379.07  5703.3  384.66  5864.0  391.02
  5884.1  393.00  5994.6  395.16  6074.9  398.02  6110.7  398.18  6216.7  401.44
#Mann=8,-1,0
  4640.0    0.05       0  4708.3    0.16       0  4965.7    0.07       0
  4994.9    0.16       0  4996.1    0.12       0  5178.7    0.05       0
  5217.8    0.16       0  5604.3    0.05       0
Bank Sta=4965.7,4994.9
Exp/Cntr=0.3,0.1

Type RM Length L Ch R = 1,67785,318,318,318
BEGIN DESCRIPTION:
North Twin Creek67784.98
END DESCRIPTION:
XS GIS Cut Line= 3
      2736425.75      6831644.05      2736363.65      6832032.22
      2736203.35      6832857.80
#Sta/Elev= 30
  4627.2  407.59  4658.4  406.35  4735.5  400.13  4755.8  399.28  4769.3  396.71
  4782.5  393.75  4787.5  394.26  4806.4  391.40  4849.6  386.98  4857.0  385.60
  4911.6  381.27  4938.0  378.05  4958.3  377.32  4959.0  368.93  4959.5  368.43
  4988.3  368.93  5008.9  369.68  5017.1  375.89  5029.2  376.32  5034.3  372.06
  5039.4  375.65  5049.6  376.45  5131.1  376.85  5161.7  375.93  5209.2  376.20
  5446.9  382.42  5477.5  385.14  5548.8  386.24  5664.9  392.26  5861.3  397.95
#Mann=5,-1,0
  4627.2    0.05       0  4769.3    0.12       0  4959.0    0.07       0
  4988.3    0.12       0  5209.2    0.05       0
Bank Sta=4959,4988.3
Exp/Cntr=0.3,0.1

Type RM Length L Ch R = 1,67467,365,365,365
BEGIN DESCRIPTION:
North Twin Creek67466.92
END DESCRIPTION:
XS GIS Cut Line= 3
      2736188.08      6831627.98      2736089.13      6832082.87
      2735914.79      6832743.73
#Sta/Elev= 30
  4556.6  401.43  4558.8  401.43  4587.6  397.79  4592.7  398.10  4610.9  395.98
  4636.7  391.98  4692.7  386.23  4729.8  384.64  4734.9  385.29  4743.9  383.26
  4764.4  382.18  4795.1  379.01  4872.0  375.86  4989.5  376.86  4999.7  375.63
  5004.0  369.33  5004.5  368.83  5032.8  368.83  5033.3  369.33  5040.9  376.36
  5061.6  374.81  5082.2  375.91  5122.3  375.90  5165.0  375.46  5176.1  377.06
  5211.2  379.12  5309.8  387.18  5413.2  392.87  5679.1  398.92  5705.6  399.01
#Mann=5,-1,0
  4556.6    0.05       0  4558.8    0.16       0  5004.0    0.07       0
  5033.3    0.16       0  5122.3    0.05       0
Bank Sta=5004,5033.3
Exp/Cntr=0.3,0.1

Type RM Length L Ch R = 1,67102,365,365,365
BEGIN DESCRIPTION:
North Twin Creek67102.253
END DESCRIPTION:
XS GIS Cut Line= 3
      2736201.02      6831535.99      2735842.52      6831828.04
      2734966.12      6831966.06
#Sta/Elev= 30
  4537.6  404.95  4572.8  406.19  4608.6  405.83  4679.8  398.91  4694.2  396.60
  4713.6  395.99  4822.0  388.40  4943.4  374.53  4985.0  375.96  4991.8  368.49
  4992.3  367.99  5021.4  368.49  5026.8  375.07  5051.7  375.31  5067.3  374.02
  5077.5  371.34  5087.6  371.68  5119.2  376.41  5188.8  376.29  5229.3  377.71
  5374.3  377.11  5476.6  378.79  5577.2  381.79  5634.5  384.25  5644.4  385.53
  5664.6  384.81  5754.4  387.68  5816.5  392.44  5822.0  393.80  5887.2  398.04
#Mann=6,-1,0
  4537.6    0.05       0  4713.6    0.16       0  4991.8    0.07       0
  5021.4    0.16       0  5476.6    0.12       0  5577.2    0.05       0
Bank Sta=4991.8,5021.4
Exp/Cntr=0.3,0.1

Type RM Length L Ch R = 1,66737,426,426,426
BEGIN DESCRIPTION:
North Twin Creek66737.15
END DESCRIPTION:
XS GIS Cut Line= 3
      2735954.91      6831340.26      2735587.46      6831591.35
      2734870.19      6831942.83
#Sta/Elev= 30
  4568.1  399.79  4581.6  396.23  4603.1  386.35  4704.2  384.64  4719.1  383.08
  4725.2  384.13  4755.0  381.75  4776.0  382.39  4862.5  379.05  4985.3  376.28
  5000.2  373.33  5006.3  370.07  5007.2  367.48  5007.7  366.98  5036.8  367.48
  5037.0  372.72  5050.1  376.36  5157.0  375.03  5247.9  376.15  5359.4  378.40
  5384.8  379.03  5560.4  383.52  5671.8  394.13  5725.1  395.19  5738.6  397.13
  5747.6  396.01  5753.1  398.00  5770.1  396.54  5775.6  399.52  5811.9  398.55
#Mann=7,-1,0
  4568.1    0.16       0  4862.5    0.12       0  5007.2    0.07       0
  5036.8    0.12       0  5247.9    0.05       0  5359.4    0.12       0
  5384.8    0.05       0
Bank Sta=5007.2,5036.8
Exp/Cntr=0.3,0.1

Type RM Length L Ch R = 1,66311,617,617,617
BEGIN DESCRIPTION:
North Twin Creek66311.48
END DESCRIPTION:
XS GIS Cut Line= 3
      2735662.27      6831037.22      2735324.95      6831320.17
      2734779.39      6831711.37
#Sta/Elev= 30
  4565.0  401.79  4579.2  398.92  4593.5  397.72  4657.2  389.06  4784.7  377.44
  4827.7  375.04  4842.0  375.61  4856.3  374.63  4912.5  376.13  4925.8  375.48
  4948.6  374.91  4990.9  375.62  4997.9  366.63  4998.4  366.13  5027.6  366.63
  5033.6  374.25  5040.9  376.42  5113.4  375.49  5169.9  373.15  5184.7  374.68
  5321.0  376.35  5434.7  380.65  5499.1  381.67  5534.4  386.22  5585.0  389.50
  5593.6  391.51  5599.8  390.72  5635.4  395.67  5659.6  397.22  5676.6  396.73
#Mann=6,-1,0
  4565.0    0.16       0  4925.8    0.12       0  4997.9    0.07       0
  5027.6    0.12       0  5534.4    0.05       0  5659.6    0.16       0
Bank Sta=4997.9,5027.6
Exp/Cntr=0.3,0.1

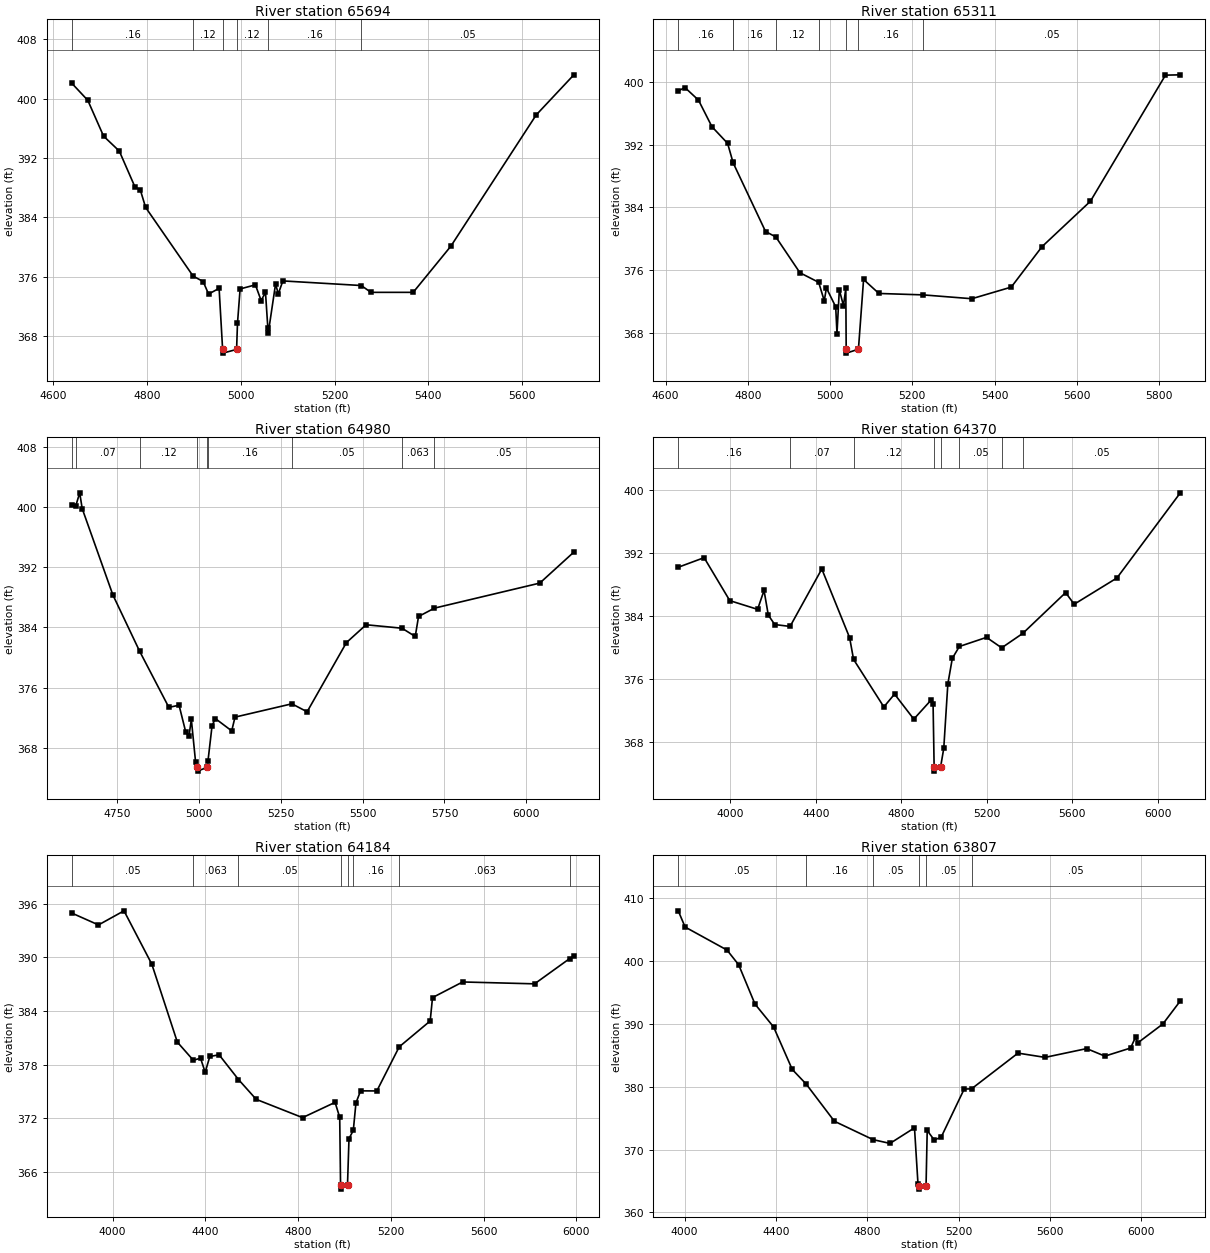
Type RM Length L Ch R = 1,65694,383,383,383
BEGIN DESCRIPTION:
North Twin Creek65694.43
END DESCRIPTION:
XS GIS Cut Line= 3
      2735466.68      6830918.30      2735127.68      6831086.91
      2734530.18      6831435.55
#Sta/Elev= 30
  4639.8  402.06  4674.0  399.75  4707.6  394.93  4741.1  392.92  4774.8  388.04
  4785.8  387.71  4797.2  385.33  4898.5  376.07  4919.8  375.34  4931.5  373.65
  4953.9  374.42  4961.4  366.19  4961.9  365.69  4991.2  366.19  4993.1  369.72
  4998.7  374.34  5031.3  374.89  5043.5  372.78  5052.8  373.87  5057.8  369.10
  5058.6  368.34  5074.3  375.02  5080.1  373.67  5089.8  375.42  5256.9  374.80
  5277.7  373.88  5367.7  373.88  5448.0  380.10  5630.0  397.79  5710.2  403.19
#Mann=6,-1,0
  4639.8    0.16       0  4898.5    0.12       0  4961.4    0.07       0
  4991.2    0.12       0  5057.8    0.16       0  5256.9    0.05       0
Bank Sta=4961.4,4991.2
Exp/Cntr=0.3,0.1

Type RM Length L Ch R = 1,65311,331,331,331
BEGIN DESCRIPTION:
North Twin Creek65310.62
END DESCRIPTION:
XS GIS Cut Line= 3
      2735429.20      6830642.04      2735065.04      6830752.93
      2734336.51      6831172.14
#Sta/Elev= 30
  4630.6  398.83  4646.9  399.26  4679.8  397.66  4712.6  394.27  4750.7  392.15
  4763.8  389.73  4764.3  389.65  4843.0  380.92  4868.0  380.23  4926.6  375.67
  4972.2  374.45  4985.8  372.09  4991.0  373.73  5013.6  371.33  5016.7  367.92
  5022.4  373.50  5032.5  371.47  5038.2  373.70  5039.1  365.93  5039.6  365.43
  5068.9  365.93  5081.4  374.81  5118.7  373.03  5225.9  372.85  5344.7  372.36
  5440.6  373.84  5515.4  378.99  5633.2  384.78  5815.7  400.84  5851.8  400.88
#Mann=8,-1,0
  4630.6    0.16       0  4763.8    0.07       0  4764.3    0.16       0
  4868.0    0.12       0  4972.2    0.16       0  5039.1    0.07       0
  5068.9    0.16       0  5225.9    0.05       0
Bank Sta=5039.1,5068.9
Exp/Cntr=0.3,0.1

Type RM Length L Ch R = 1,64980,610,610,610
BEGIN DESCRIPTION:
North Twin Creek64979.83
END DESCRIPTION:
XS GIS Cut Line= 3
      2735320.04      6830410.86      2734935.08      6830469.31
      2733792.08      6830520.23
#Sta/Elev= 30
  4611.6  400.22  4623.6  400.14  4635.9  401.90  4643.4  399.81  4737.1  388.33
  4818.5  380.87  4908.1  373.38  4939.3  373.66  4959.6  370.11  4969.7  369.60
  4976.8  371.77  4989.9  366.05  4995.2  365.40  4995.7  364.90  5025.0  365.40
  5027.6  366.24  5040.1  370.93  5050.1  371.89  5100.1  370.25  5110.2  372.08
  5283.9  373.85  5330.4  372.79  5450.5  381.99  5510.6  384.36  5620.2  383.90
  5660.7  382.80  5670.7  385.46  5719.4  386.57  6041.1  389.90  6145.1  394.02
#Mann=9,-1,0
  4611.6    0.16       0  4623.6    0.07       0  4818.5    0.12       0
  4995.2    0.07       0  5025.0    0.12       0  5027.6    0.16       0
  5283.9    0.05       0  5620.2   0.063       0  5719.4    0.05       0
Bank Sta=4995.2,5025
Exp/Cntr=0.3,0.1

Type RM Length L Ch R = 1,64370,186,186,186
BEGIN DESCRIPTION:
North Twin Creek64369.85
END DESCRIPTION:
XS GIS Cut Line= 3
      2735836.93      6830178.92      2734572.81      6830128.24
      2733489.65      6830128.61
#Sta/Elev= 30
  3756.3  390.18  3877.3  391.40  3997.4  385.94  4127.5  384.83  4157.6  387.23
  4177.6  384.10  4207.6  382.90  4279.4  382.66  4427.8  389.96  4557.9  381.23
  4576.3  378.47  4718.0  372.43  4768.0  374.06  4858.1  370.88  4938.2  373.28
  4948.2  372.84  4953.2  364.77  4953.7  364.27  4983.2  364.77  4998.2  367.16
  5017.3  375.35  5038.2  378.60  5071.1  380.11  5198.2  381.27  5269.1  379.94
  5368.0  381.78  5568.2  386.96  5608.2  385.48  5808.2  388.82  6104.6  399.64
#Mann=8,-1,0
  3756.3    0.16       0  4279.4    0.07       0  4576.3    0.12       0
  4953.2    0.07       0  4983.2    0.12       0  5071.1    0.05       0
  5269.1   0.063       0  5368.0    0.05       0
Bank Sta=4953.2,4983.2
Exp/Cntr=0.3,0.1

Type RM Length L Ch R = 1,64184,377,377,377
BEGIN DESCRIPTION:
North Twin Creek64184.26
END DESCRIPTION:
XS GIS Cut Line= 3
      2735741.17      6829937.66      2734563.76      6829951.38
      2733576.73      6829928.08
#Sta/Elev= 30
  3823.9  394.97  3939.1  393.64  4049.1  395.22  4169.1  389.24  4279.1  380.51
  4348.0  378.48  4379.1  378.71  4399.1  377.13  4419.1  378.90  4459.1  379.09
  4542.7  376.32  4619.1  374.10  4819.1  372.05  4959.2  373.76  4979.2  372.08
  4982.8  364.54  4983.3  364.04  5012.8  364.54  5019.2  369.70  5037.8  370.62
  5049.2  373.70  5069.2  375.05  5139.2  375.04  5235.7  379.98  5369.3  382.88
  5379.3  385.50  5509.3  387.25  5819.4  387.04  5970.7  389.87  5988.7  390.13
#Mann=8,-1,0
  3823.9    0.05       0  4348.0   0.063       0  4542.7    0.05       0
  4982.8    0.05       0  5012.8    0.05       0  5037.8    0.16       0
  5235.7   0.063       0  5970.7    0.05       0
Bank Sta=4982.8,5012.8
Exp/Cntr=0.3,0.1

Type RM Length L Ch R = 1,63807,580,580,580
BEGIN DESCRIPTION:
North Twin Creek63806.6
END DESCRIPTION:
XS GIS Cut Line= 3
      2735475.50      6829401.38      2734467.86      6829604.94
      2733310.73      6829786.62
#Sta/Elev= 30
  3972.0  408.03  4002.1  405.45  4185.7  401.78  4236.7  399.44  4308.2  393.18
  4389.8  389.53  4471.4  382.77  4532.7  380.43  4656.0  374.52  4825.6  371.59
  4899.6  370.99  5006.9  373.47  5022.1  364.59  5027.2  364.21  5027.7  363.71
  5057.5  364.21  5062.6  373.05  5093.0  371.55  5123.3  371.95  5224.6  379.65
  5256.8  379.68  5460.3  385.37  5578.9  384.69  5761.1  386.09  5841.0  384.89
  5953.4  386.18  5976.3  387.99  5983.8  386.97  6095.1  390.02  6171.3  393.68
#Mann=6,-1,0
  3972.0    0.05       0  4532.7    0.16       0  4825.6    0.05       0
  5027.2    0.05       0  5057.5    0.05       0  5256.8    0.05       0
Bank Sta=5027.2,5057.5
Exp/Cntr=0.3,0.1

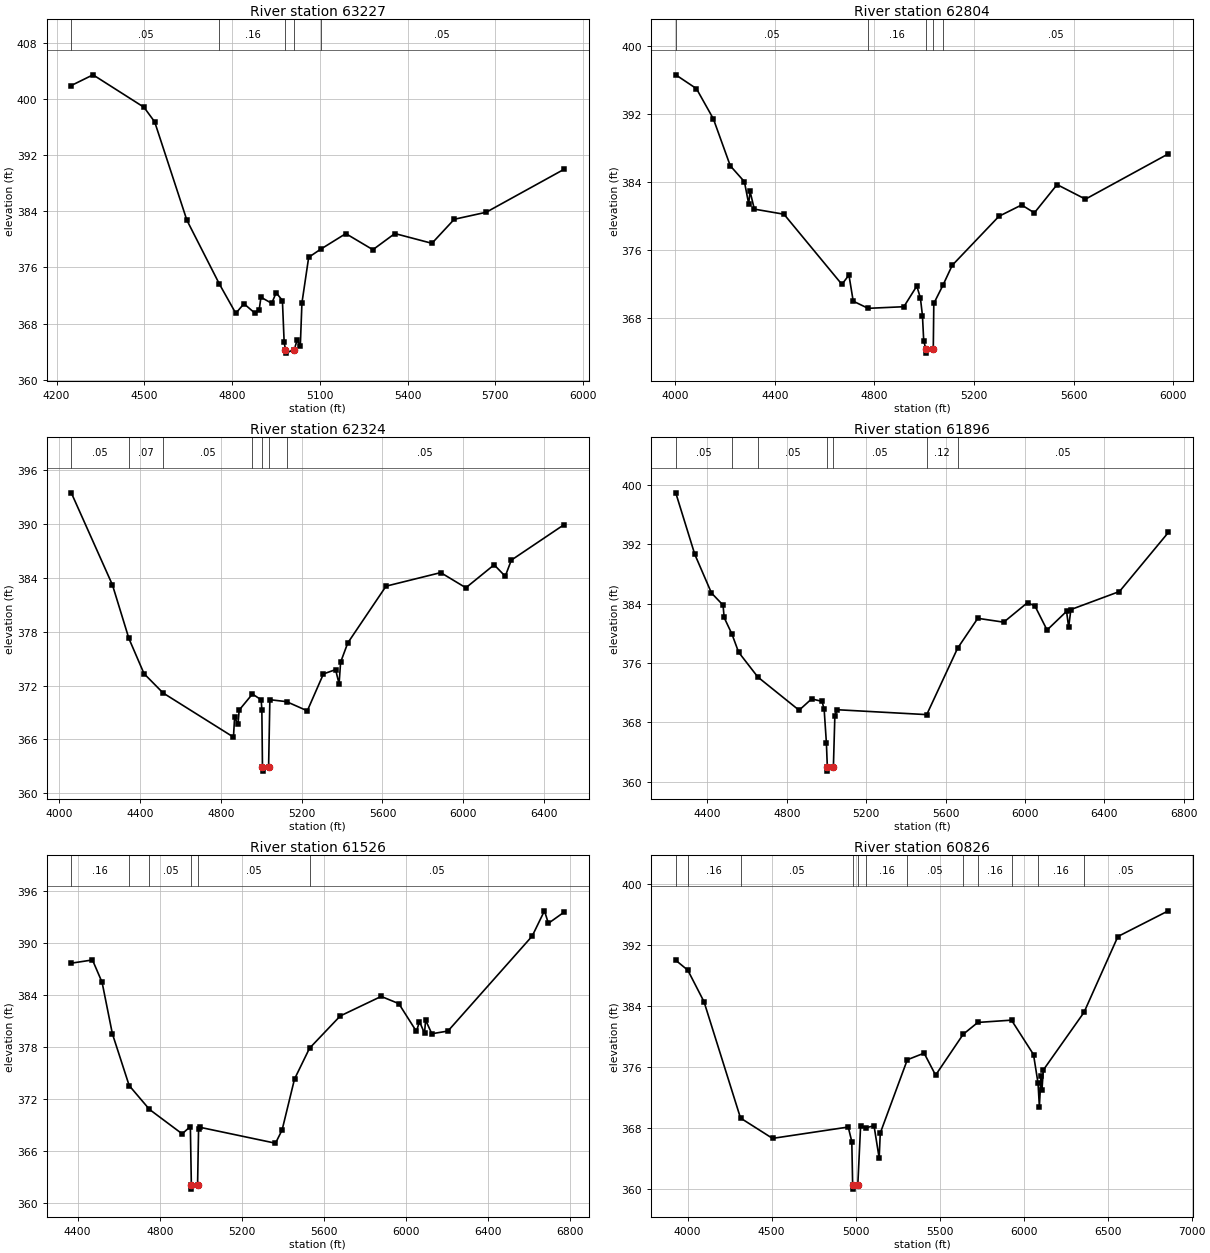
Type RM Length L Ch R = 1,63227,423,423,423
BEGIN DESCRIPTION:
North Twin Creek63226.722
END DESCRIPTION:
XS GIS Cut Line= 3
      2734704.95      6828857.46      2734066.26      6829250.25
      2733214.07      6829632.76
#Sta/Elev= 30
  4250.2  401.89  4324.5  403.41  4498.5  398.80  4535.2  396.72  4645.3  382.72
  4756.6  373.62  4812.5  369.47  4840.5  370.83  4877.2  369.51  4892.6  369.99
  4898.5  371.76  4935.2  370.89  4950.6  372.40  4971.9  371.28  4977.8  365.39
  4982.1  364.30  4982.6  363.80  5012.4  364.30  5022.2  365.66  5033.1  364.86
  5038.6  370.94  5061.7  377.44  5102.3  378.58  5188.6  380.81  5281.2  378.52
  5356.2  380.82  5483.0  379.43  5559.3  382.85  5668.4  383.85  5934.1  389.95
#Mann=5,-1,0
  4250.2    0.05       0  4756.6    0.16       0  4982.1    0.07       0
  5012.4    0.16       0  5102.3    0.05       0
Bank Sta=4982.1,5012.4
Exp/Cntr=0.3,0.1

Type RM Length L Ch R = 1,62804,480,480,480
BEGIN DESCRIPTION:
North Twin Creek62803.983
END DESCRIPTION:
XS GIS Cut Line= 3
      2734763.88      6828469.32      2733861.95      6828897.96
      2732974.64      6829315.40
#Sta/Elev= 30
  4001.4  396.56  4084.5  394.94  4152.6  391.39  4220.5  385.88  4277.3  384.01
  4294.5  381.41  4300.0  382.87  4317.2  380.79  4436.3  380.19  4669.1  371.95
  4697.3  373.05  4714.5  369.98  4774.4  369.14  4918.0  369.33  4970.0  371.76
  4984.4  370.36  4992.7  368.28  4997.7  365.36  5005.8  364.38  5006.3  363.88
  5036.2  364.38  5038.3  369.71  5075.6  371.89  5112.2  374.19  5300.1  379.95
  5391.3  381.28  5442.4  380.35  5533.6  383.67  5647.6  381.96  5980.6  387.28
#Mann=5,-1,0
  4001.4    0.05       0  4774.4    0.16       0  5005.8    0.07       0
  5036.2    0.16       0  5075.6    0.05       0
Bank Sta=5005.8,5036.2
Exp/Cntr=0.3,0.1

Type RM Length L Ch R = 1,62324,428,428,428
BEGIN DESCRIPTION:
North Twin Creek62324.245
END DESCRIPTION:
XS GIS Cut Line= 3
      2734618.74      6828080.57      2733776.10      6828495.61
      2732376.61      6829027.89
#Sta/Elev= 30
  4060.7  393.47  4264.4  383.20  4345.6  377.24  4420.5  373.32  4514.7  371.17
  4862.9  366.25  4868.5  368.46  4885.4  367.68  4891.0  369.26  4956.6  371.05
  5000.0  370.41  5003.3  369.28  5006.3  362.96  5006.8  362.46  5036.7  362.96
  5042.9  370.42  5125.7  370.20  5228.1  369.18  5307.8  373.29  5368.0  373.77
  5385.3  372.18  5392.8  374.59  5428.2  376.74  5617.6  383.07  5888.1  384.58
  6012.5  382.89  6152.3  385.45  6207.2  384.17  6237.3  385.97  6497.3  389.91
#Mann=7,-1,0
  4060.7    0.05       0  4345.6    0.07       0  4514.7    0.05       0
  4956.6    0.16       0  5006.3    0.07       0  5036.7    0.16       0
  5125.7    0.05       0
Bank Sta=5006.3,5036.7
Exp/Cntr=0.3,0.1

Type RM Length L Ch R = 1,61896,370,370,370
BEGIN DESCRIPTION:
North Twin Creek61895.719
END DESCRIPTION:
XS GIS Cut Line= 3
      2734547.21      6827882.21      2733824.27      6828116.62
      2732246.02      6828804.66
#Sta/Elev= 30
  4240.0  398.92  4335.9  390.64  4420.0  385.43  4478.5  383.79  4483.8  382.13
  4523.4  379.88  4556.7  377.46  4653.7  374.11  4861.5  369.64  4924.6  371.17
  4977.2  370.83  4987.7  369.76  4999.0  365.26  5003.8  361.94  5004.3  361.44
  5034.2  361.94  5041.7  368.91  5053.3  369.71  5504.5  369.05  5660.0  377.99
  5761.7  382.02  5892.6  381.50  6012.6  384.14  6050.1  383.66  6110.8  380.44
  6209.0  382.96  6219.5  380.82  6230.8  383.20  6475.5  385.63  6721.7  393.58
#Mann=7,-1,0
  4240.0    0.05       0  4523.4    0.07       0  4653.7    0.05       0
  5003.8    0.05       0  5034.2    0.05       0  5504.5    0.12       0
  5660.0    0.05       0
Bank Sta=5003.8,5034.2
Exp/Cntr=0.3,0.1

Type RM Length L Ch R = 1,61526,700,700,700
BEGIN DESCRIPTION:
North Twin Creek61526.406
END DESCRIPTION:
XS GIS Cut Line= 3
      2734266.04      6827839.20      2733636.54      6827819.27
      2731986.18      6828461.71
#Sta/Elev= 30
  4369.0  387.65  4472.2  388.02  4519.1  385.44  4569.1  379.53  4651.1  373.55
  4750.1  370.80  4909.3  367.99  4949.3  368.83  4954.1  362.12  4954.6  361.62
  4984.5  362.12  4989.3  368.49  4996.6  368.74  5364.2  366.91  5396.4  368.43
  5456.9  374.30  5530.1  377.85  5679.9  381.57  5879.3  383.82  5965.2  382.99
  6051.0  379.79  6066.0  380.92  6090.5  379.58  6095.9  381.09  6126.1  379.52
  6204.7  379.83  6615.3  390.77  6675.1  393.68  6694.2  392.24  6769.8  393.51
#Mann=6,-1,0
  4369.0    0.16       0  4651.1    0.07       0  4750.1    0.05       0
  4954.1    0.07       0  4984.5    0.05       0  5530.1    0.05       0
Bank Sta=4954.1,4984.5
Exp/Cntr=0.3,0.1

Type RM Length L Ch R = 1,60826,549,549,549
BEGIN DESCRIPTION:
North Twin Creek60826.126
END DESCRIPTION:
XS GIS Cut Line= 3
      2734343.70      6827813.76      2733426.00      6827261.00
      2731826.00      6828211.00
#Sta/Elev= 30
  3929.0  390.05  4000.8  388.75  4097.3  384.61  4314.6  369.34  4505.1  366.67
  4955.7  368.16  4977.0  366.25  4982.1  360.51  4982.6  360.01  5012.6  360.51
  5029.5  368.34  5060.2  368.06  5109.4  368.32  5139.9  364.08  5146.5  367.37
  5307.4  376.99  5407.5  377.86  5475.8  374.97  5640.2  380.34  5727.1  381.89
  5927.6  382.19  6058.6  377.68  6085.7  373.89  6093.5  370.84  6103.2  374.86
  6109.0  373.03  6116.8  375.64  6359.1  383.21  6561.0  393.17  6861.1  396.54
#Mann=12,-1,0
  3929.0    0.05       0  4000.8    0.16       0  4314.6    0.05       0
  4982.1    0.05       0  5012.6    0.05       0  5060.2    0.16       0
  5307.4    0.05       0  5640.2    0.12       0  5727.1    0.16       0
  5927.6    0.05       0  6085.7    0.16       0  6359.1    0.05       0
Bank Sta=4982.1,5012.6
Exp/Cntr=0.3,0.1

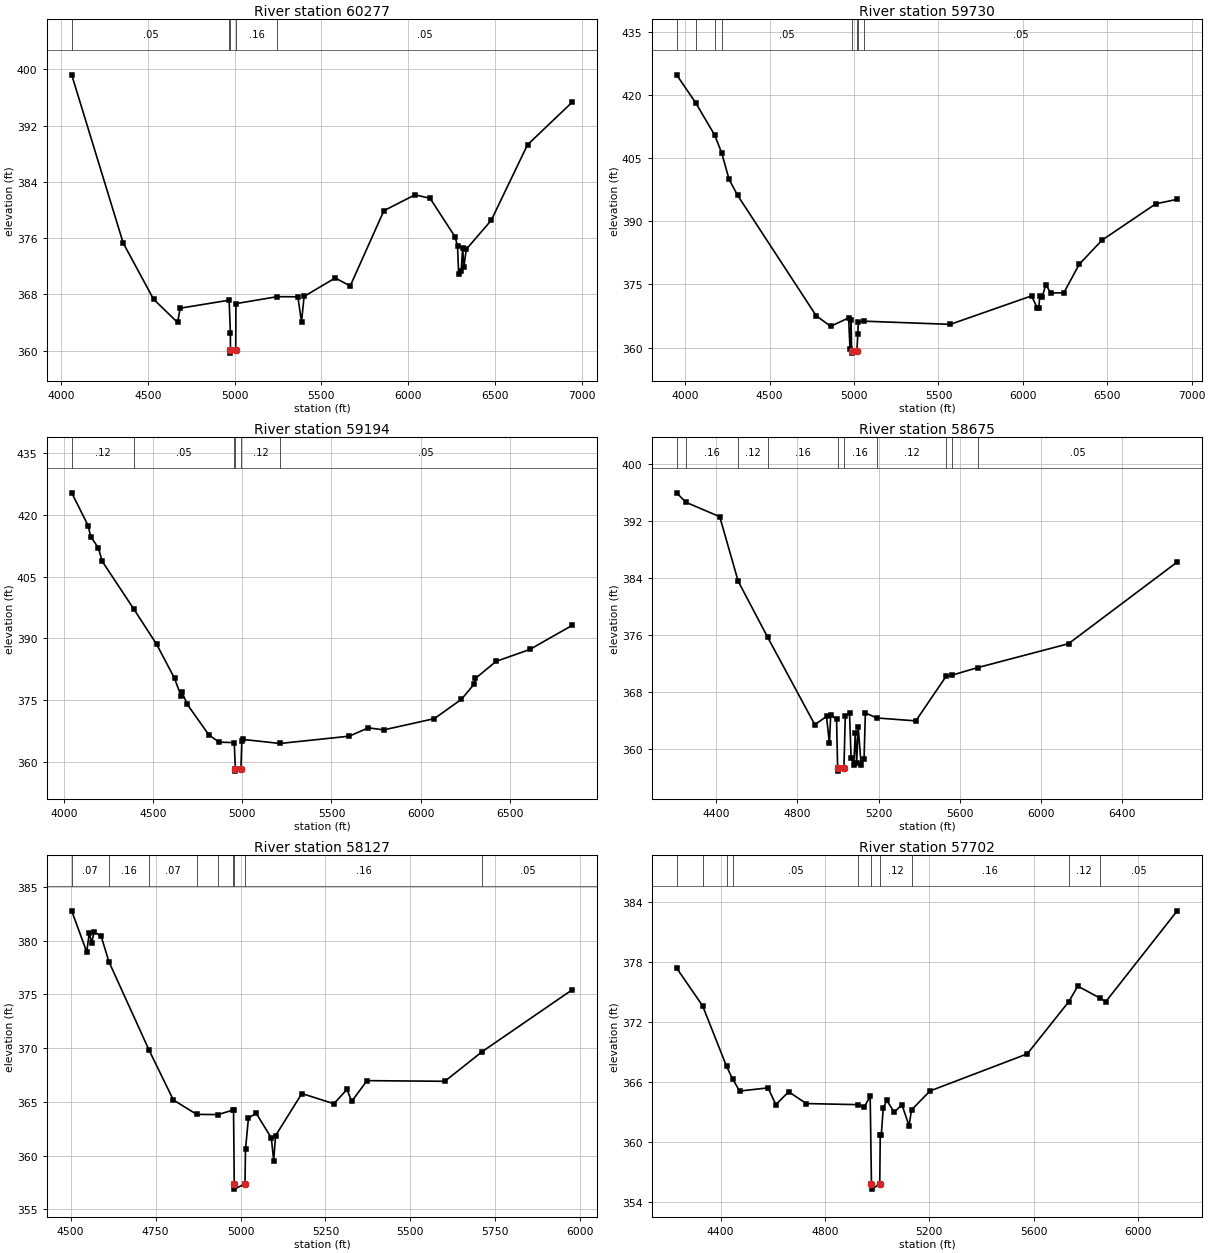
Type RM Length L Ch R = 1,60277,547,547,547
BEGIN DESCRIPTION:
North Twin Creek60276.586
END DESCRIPTION:
XS GIS Cut Line= 3
      2734026.00      6826161.01      2733526.00      6826961.00
      2731926.03      6828060.98
#Sta/Elev= 30
  4060.9  399.21  4357.5  375.30  4532.6  367.30  4671.2  363.99  4685.9  366.02
  4968.1  367.16  4975.4  362.48  4975.5  360.13  4976.0  359.63  5006.0  360.13
  5007.3  366.67  5245.3  367.66  5364.2  367.64  5385.2  364.07  5400.1  367.69
  5579.3  370.32  5665.9  369.18  5860.1  379.89  6039.4  382.15  6126.0  381.65
  6269.4  376.20  6284.3  374.89  6290.6  370.90  6305.2  371.33  6314.1  374.65
  6320.1  371.81  6335.0  374.41  6478.5  378.52  6687.5  389.26  6945.9  395.34
#Mann=5,-1,0
  4060.9    0.05       0  4968.1    0.16       0  4975.5    0.07       0
  5006.0    0.16       0  5245.3    0.05       0
Bank Sta=4975.5,5006
Exp/Cntr=0.3,0.1

Type RM Length L Ch R = 1,59730,536,536,536
BEGIN DESCRIPTION:
North Twin Creek59729.5
END DESCRIPTION:
XS GIS Cut Line= 3
      2733801.32      6825760.32      2733176.00      6826611.00
      2731875.99      6828011.02
#Sta/Elev= 30
  3948.4  424.74  4061.7  418.09  4173.8  410.45  4215.3  406.24  4259.5  399.92
  4309.4  396.16  4775.4  367.55  4861.1  365.04  4967.6  367.03  4976.0  359.56
  4982.2  366.63  4985.5  359.17  4986.0  358.67  5016.6  359.17  5022.2  363.15
  5025.4  366.10  5056.4  366.26  5570.2  365.50  6051.5  372.26  6086.7  369.30
  6094.1  369.44  6100.9  372.31  6115.1  372.07  6136.6  374.96  6164.4  372.95
  6242.6  372.99  6334.4  379.78  6468.8  385.48  6787.4  394.11  6914.7  395.19
#Mann=8,-1,0
  3948.4    0.16       0  4061.7    0.05       0  4173.8    0.07       0
  4215.3    0.05       0  4985.5    0.05       0  5016.6    0.05       0
  5022.2    0.12       0  5056.4    0.05       0
Bank Sta=4985.5,5016.6
Exp/Cntr=0.3,0.1

Type RM Length L Ch R = 1,59194,519,519,519
BEGIN DESCRIPTION:
North Twin Creek59193.577
END DESCRIPTION:
XS GIS Cut Line= 3
      2733575.98      6825711.01      2732826.00      6826311.00
      2731826.02      6827860.97
#Sta/Elev= 30
  4044.4  425.34  4136.4  417.37  4150.8  414.72  4194.1  411.93  4214.9  408.73
  4391.3  397.17  4520.6  388.51  4620.7  380.25  4656.7  376.01  4663.1  376.83
  4691.9  373.94  4812.8  366.53  4869.6  364.76  4955.2  364.65  4961.3  358.22
  4961.8  357.72  4992.4  358.22  4997.6  365.09  5001.6  365.43  5211.5  364.44
  5599.1  366.21  5707.0  368.24  5792.5  367.74  6075.9  370.47  6228.1  375.18
  6300.7  378.94  6306.6  380.25  6421.5  384.37  6611.4  387.29  6849.4  393.16
#Mann=6,-1,0
  4044.4    0.12       0  4391.3    0.05       0  4955.2    0.12       0
  4961.3    0.07       0  4992.4    0.12       0  5211.5    0.05       0
Bank Sta=4961.3,4992.4
Exp/Cntr=0.3,0.1

Type RM Length L Ch R = 1,58675,548,548,548
BEGIN DESCRIPTION:
North Twin Creek58675.175
END DESCRIPTION:
XS GIS Cut Line= 3
      2733072.85      6825338.46      2732576.00      6825961.00
      2731513.64      6827254.31
#Sta/Elev= 30
  4203.7  395.99  4250.0  394.66  4416.6  392.64  4507.4  383.60  4652.3  375.76
  4885.7  363.46  4943.4  364.61  4957.8  360.82  4964.2  364.87  4993.0  364.19
  4998.2  357.44  4998.7  356.94  5029.4  357.44  5036.1  364.73  5056.9  365.06
  5064.8  358.77  5077.9  357.82  5085.6  362.33  5092.1  358.14  5099.9  363.09
  5114.3  357.80  5128.6  358.58  5135.1  365.10  5191.5  364.40  5384.1  363.99
  5534.0  370.27  5564.4  370.42  5688.7  371.46  6137.5  374.82  6673.9  386.28
#Mann=10,-1,0
  4203.7    0.05       0  4250.0    0.16       0  4507.4    0.12       0
  4652.3    0.16       0  4998.2    0.07       0  5029.4    0.16       0
  5191.5    0.12       0  5534.0    0.16       0  5564.4    0.12       0
  5688.7    0.05       0
Bank Sta=4998.2,5029.4
Exp/Cntr=0.3,0.1

Type RM Length L Ch R = 1,58127,425,425,425
BEGIN DESCRIPTION:
North Twin Creek58127.023
END DESCRIPTION:
XS GIS Cut Line= 3
      2732509.51      6825341.74      2732176.00      6825711.00
      2731727.73      6826577.77
#Sta/Elev= 30
  4503.2  382.79  4547.5  378.96  4555.0  380.75  4561.7  379.78  4569.2  380.85
  4590.1  380.40  4612.6  378.06  4731.2  369.80  4802.4  365.18  4871.0  363.84
  4933.8  363.82  4978.0  364.24  4979.5  364.29  4981.6  357.38  4982.1  356.88
  5013.2  357.38  5014.7  360.59  5023.3  363.48  5045.8  363.96  5090.8  361.64
  5097.6  359.52  5103.2  361.86  5180.5  365.78  5274.7  364.83  5313.4  366.16
  5327.3  365.05  5372.3  366.98  5601.3  366.92  5711.7  369.69  5976.6  375.45
#Mann=9,-1,0
  4503.2    0.07       0  4612.6    0.16       0  4731.2    0.07       0
  4871.0    0.16       0  4933.8    0.05       0  4978.0    0.16       0
  4981.6    0.07       0  5013.2    0.16       0  5711.7    0.05       0
Bank Sta=4981.6,5013.2
Exp/Cntr=0.3,0.1

Type RM Length L Ch R = 1,57702,694,694,694
BEGIN DESCRIPTION:
North Twin Creek57702.17
END DESCRIPTION:
XS GIS Cut Line= 4
      2732459.63      6825350.03      2731814.44      6825599.78
      2731759.84      6825671.23      2731111.98      6826606.37
#Sta/Elev= 30
  4231.4  377.44  4331.3  373.65  4423.2  367.59  4445.8  366.36  4473.1  365.13
  4582.1  365.45  4612.0  363.77  4661.2  365.06  4728.6  363.88  4928.4  363.77
  4950.8  363.54  4973.6  364.60  4978.5  355.82  4979.0  355.32  5010.3  355.82
  5012.2  360.73  5016.1  360.73  5023.8  363.43  5037.2  364.20  5065.7  363.02
  5095.4  363.76  5122.5  361.67  5132.3  363.25  5202.9  365.14  5575.8  368.85
  5734.6  374.06  5769.7  375.63  5853.1  374.45  5877.1  374.08  6150.8  383.16
#Mann=10,-1,0
  4231.4    0.07       0  4331.3    0.05       0  4423.2    0.07       0
  4445.8    0.05       0  4928.4    0.12       0  4978.5    0.07       0
  5010.3    0.12       0  5132.3    0.16       0  5734.6    0.12       0
  5853.1    0.05       0
Bank Sta=4978.5,5010.3
Exp/Cntr=0.3,0.1

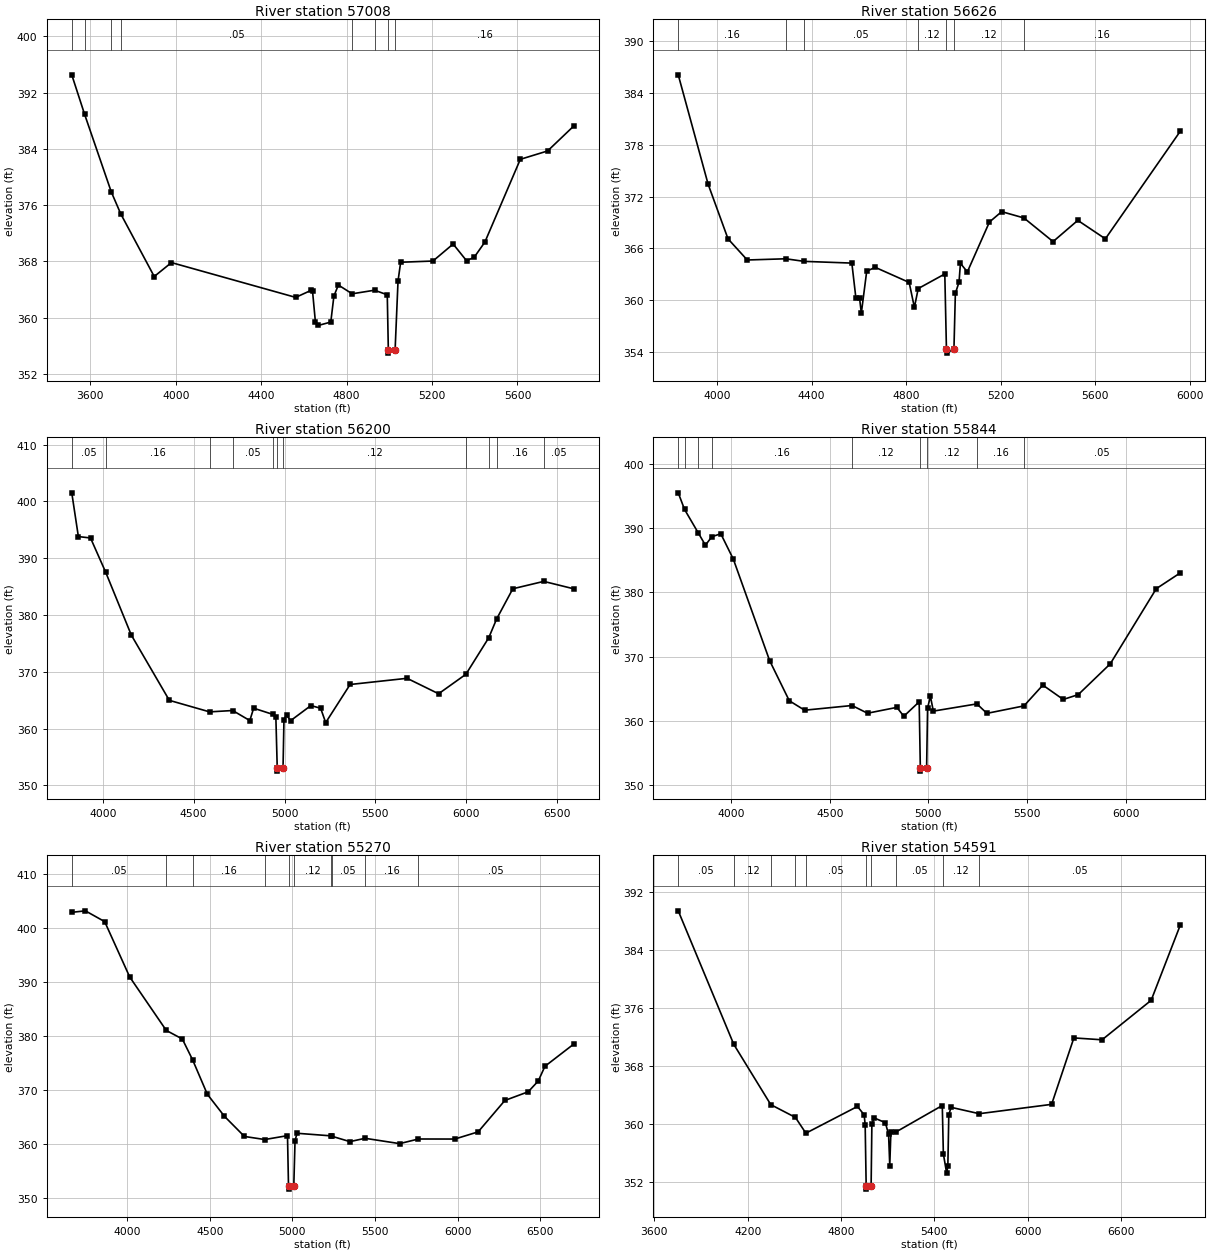
Type RM Length L Ch R = 1,57008,382,382,382
BEGIN DESCRIPTION:
North Twin Creek57007.725
END DESCRIPTION:
XS GIS Cut Line= 4
      2732619.65      6825296.63      2731612.69      6825179.40
      2731326.00      6825561.00      2730825.99      6826261.01
#Sta/Elev= 30
  3512.8  394.54  3572.9  388.92  3698.0  377.87  3742.3  374.75  3899.0  365.85
  3979.6  367.83  4561.3  362.88  4632.1  363.86  4640.4  363.74  4653.6  359.44
  4667.5  358.89  4725.8  359.37  4740.4  363.06  4761.2  364.64  4825.9  363.39
  4930.6  363.90  4990.3  363.25  4995.3  355.45  4995.8  354.95  5027.1  355.45
  5040.7  365.20  5053.0  367.88  5204.2  368.05  5298.8  370.47  5361.5  368.10
  5397.1  368.57  5447.5  370.75  5613.4  382.52  5741.2  383.71  5864.1  387.27
#Mann=8,-1,0
  3512.8    0.07       0  3572.9    0.05       0  3698.0    0.07       0
  3742.3    0.05       0  4825.9    0.12       0  4930.6    0.16       0
  4995.3    0.07       0  5027.1    0.16       0
Bank Sta=4995.3,5027.1
Exp/Cntr=0.3,0.1

Type RM Length L Ch R = 1,56626,426,426,426
BEGIN DESCRIPTION:
Mapping XS caa71a04
END DESCRIPTION:
XS GIS Cut Line= 3
      2731741.11      6824206.68      2731246.27      6825260.48
      2730749.99      6826082.25
#Sta/Elev= 30
  3835.8  386.10  3962.1  373.44  4046.4  367.10  4127.8  364.65  4290.7  364.79
  4368.4  364.49  4570.3  364.29  4587.6  360.20  4602.9  360.25  4610.4  358.49
  4633.2  363.35  4669.1  363.80  4812.8  362.05  4834.9  359.16  4851.2  361.34
  4963.6  363.03  4970.5  354.36  4971.0  353.86  5002.3  354.36  5008.3  360.79
  5023.8  362.08  5029.7  364.26  5059.0  363.27  5152.5  369.05  5204.3  370.25
  5298.3  369.52  5421.7  366.78  5526.3  369.24  5642.9  367.10  5960.0  379.57
#Mann=7,-1,0
  3835.8    0.16       0  4290.7    0.12       0  4368.4    0.05       0
  4851.2    0.12       0  4970.5    0.07       0  5002.3    0.12       0
  5298.3    0.16       0
Bank Sta=4970.5,5002.3
Exp/Cntr=0.3,0.1

Type RM Length L Ch R = 1,56200,356,356,356
BEGIN DESCRIPTION:
North Twin Creek56199.958
END DESCRIPTION:
XS GIS Cut Line= 3
      2731739.20      6823973.34      2731110.98      6824961.32
      2730400.99      6826386.01
#Sta/Elev= 30
  3829.2  401.50  3865.5  393.80  3932.4  393.55  4016.0  387.51  4156.8  376.46
  4366.0  364.97  4587.6  362.94  4714.6  363.18  4808.8  361.41  4830.0  363.59
  4936.3  362.49  4952.2  362.00  4959.8  353.01  4960.3  352.51  4991.6  353.01
  4996.8  361.57  5010.8  362.40  5033.2  361.39  5144.9  364.05  5198.5  363.58
  5226.4  361.05  5360.7  367.76  5674.1  368.85  5847.6  366.13  5997.9  369.56
  6123.6  375.99  6166.7  379.28  6256.0  384.61  6426.1  385.91  6591.8  384.60
#Mann=11,-1,0
  3829.2    0.05       0  4016.0    0.16       0  4587.6    0.12       0
  4714.6    0.05       0  4936.3    0.12       0  4959.8    0.07       0
  4991.6    0.12       0  5997.9    0.16       0  6123.6    0.12       0
  6166.7    0.16       0  6426.1    0.05       0
Bank Sta=4959.8,4991.6
Exp/Cntr=0.3,0.1

Type RM Length L Ch R = 1,55844,574,574,574
BEGIN DESCRIPTION:
North Twin Creek55844.308
END DESCRIPTION:
XS GIS Cut Line= 4
      2731612.20      6823942.63      2730773.91      6824901.36
      2730587.77      6825170.94      2730351.01      6826085.97
#Sta/Elev= 30
  3731.5  395.48  3763.3  392.91  3832.3  389.29  3869.4  387.34  3901.6  388.65
  3947.3  389.12  4010.9  385.17  4195.0  369.40  4294.7  363.16  4372.5  361.69
  4612.9  362.42  4691.4  361.22  4840.4  362.13  4875.5  360.75  4953.4  362.99
  4959.3  352.72  4959.8  352.22  4991.2  352.72  4996.1  362.05  5010.4  363.84
  5025.3  361.55  5246.2  362.67  5297.0  361.20  5484.9  362.36  5580.6  365.59
  5684.0  363.36  5760.1  364.11  5922.6  368.90  6156.0  380.58  6277.8  383.04
#Mann=9,-1,0
  3731.5    0.05       0  3763.3    0.16       0  3832.3    0.05       0
  3901.6    0.16       0  4612.9    0.12       0  4959.3    0.07       0
  4991.2    0.12       0  5246.2    0.16       0  5484.9    0.05       0
Bank Sta=4959.3,4991.2
Exp/Cntr=0.3,0.1

Type RM Length L Ch R = 1,55270,679,679,679
BEGIN DESCRIPTION:
North Twin Creek55270.088
END DESCRIPTION:
XS GIS Cut Line= 4
      2731785.32      6823726.65      2730660.00      6824443.96
      2730504.40      6824538.34      2730286.91      6826044.13
#Sta/Elev= 30
  3665.5  402.91  3747.7  403.19  3864.6  401.19  4016.1  390.93  4237.3  381.03
  4334.4  379.44  4396.9  375.56  4485.9  369.19  4589.1  365.12  4710.2  361.38
  4833.2  360.81  4970.8  361.53  4976.9  352.12  4977.4  351.62  5008.8  352.12
  5016.4  360.59  5028.6  361.97  5235.1  361.49  5237.2  361.44  5348.5  360.42
  5439.9  361.04  5649.4  360.05  5763.0  360.91  5982.9  360.90  6124.3  362.23
  6286.0  368.05  6427.4  369.66  6488.1  371.66  6528.5  374.38  6703.4  378.51
#Mann=10,-1,0
  3665.5    0.05       0  4237.3    0.12       0  4396.9    0.16       0
  4833.2    0.12       0  4976.9    0.07       0  5008.8    0.12       0
  5235.1    0.16       0  5237.2    0.05       0  5439.9    0.16       0
  5763.0    0.05       0
Bank Sta=4976.9,5008.8
Exp/Cntr=0.3,0.1

Type RM Length L Ch R = 1,54591,878,878,878
BEGIN DESCRIPTION:
North Twin Creek54591.232
END DESCRIPTION:
XS GIS Cut Line= 3
      2731151.03      6823535.97      2730178.70      6824316.41
      2728555.29      6825451.87
#Sta/Elev= 30
  3753.2  389.45  4110.3  371.02  4348.2  362.70  4506.4  360.94  4573.9  358.76
  4905.4  362.45  4948.6  361.29  4955.0  359.91  4961.4  351.54  4961.9  351.04
  4993.3  351.54  4998.2  360.07  5013.1  360.87  5084.6  360.21  5105.5  358.62
  5113.1  354.30  5120.3  358.86  5155.7  358.96  5450.8  362.58  5457.7  355.92
  5479.2  353.20  5486.6  354.29  5492.7  361.32  5507.5  362.33  5688.5  361.45
  6153.7  362.74  6296.8  371.91  6478.1  371.65  6793.7  377.10  6981.1  387.49
#Mann=10,-1,0
  3753.2    0.05       0  4110.3    0.12       0  4348.2    0.05       0
  4506.4    0.16       0  4573.9    0.05       0  4961.4    0.07       0
  4993.3    0.05       0  5155.7    0.05       0  5457.7    0.12       0
  5688.5    0.05       0
Bank Sta=4961.4,4993.3
Exp/Cntr=0.3,0.1