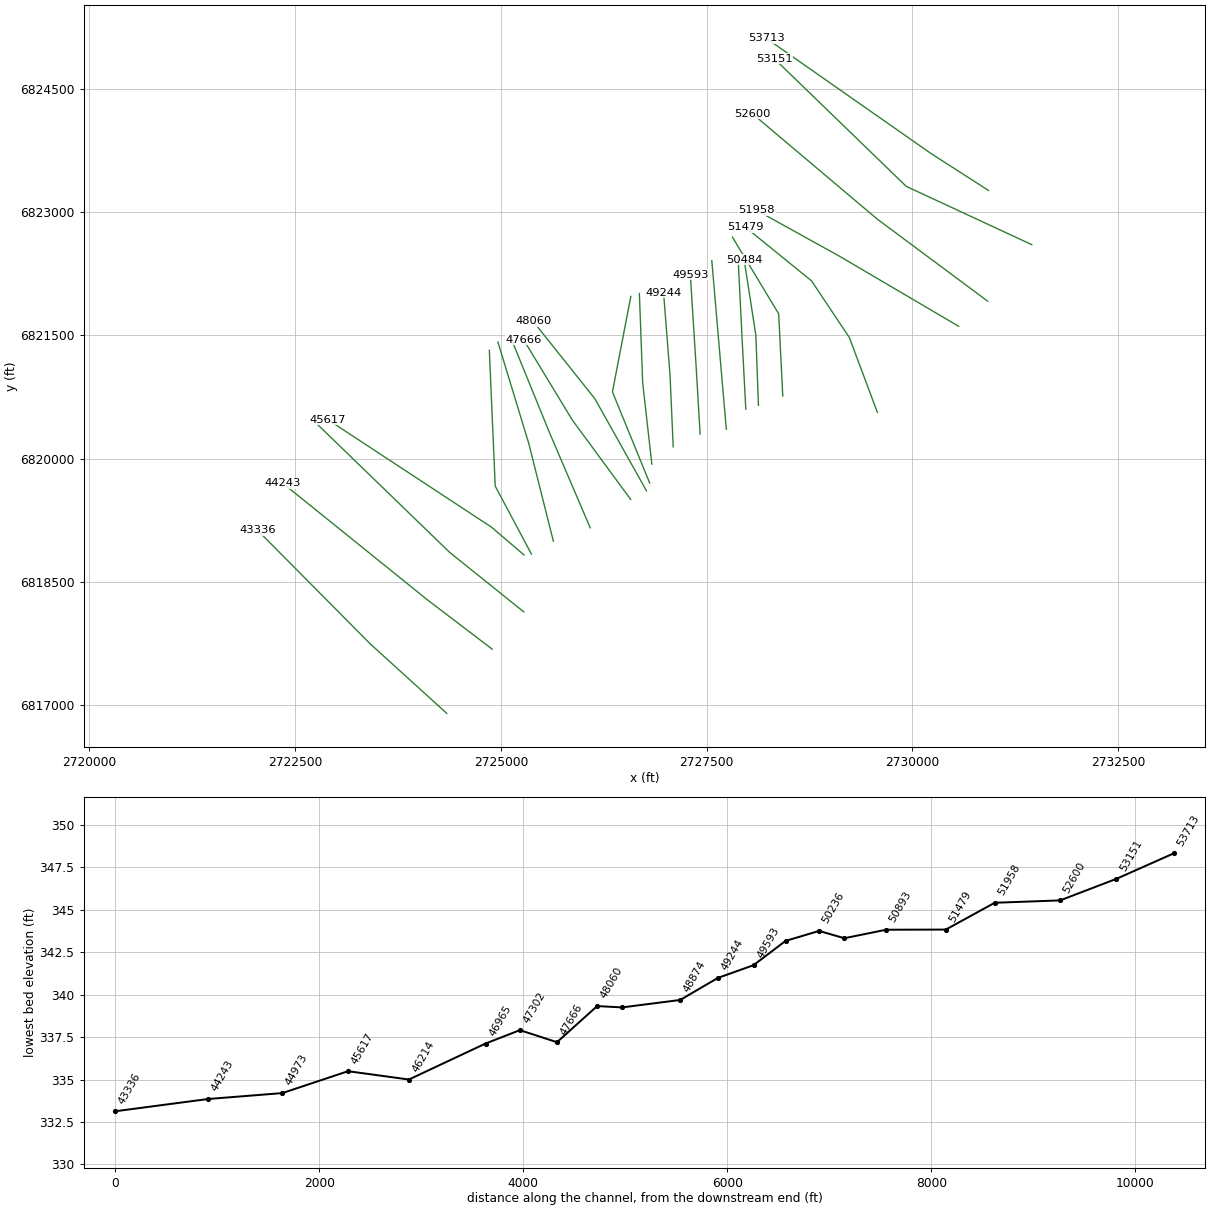
HEC-RAS study North Twin Creek.prj: North Twin Creek Base Level Engineering

--- North Twin Creek.g01 (geometry) --- (continued)

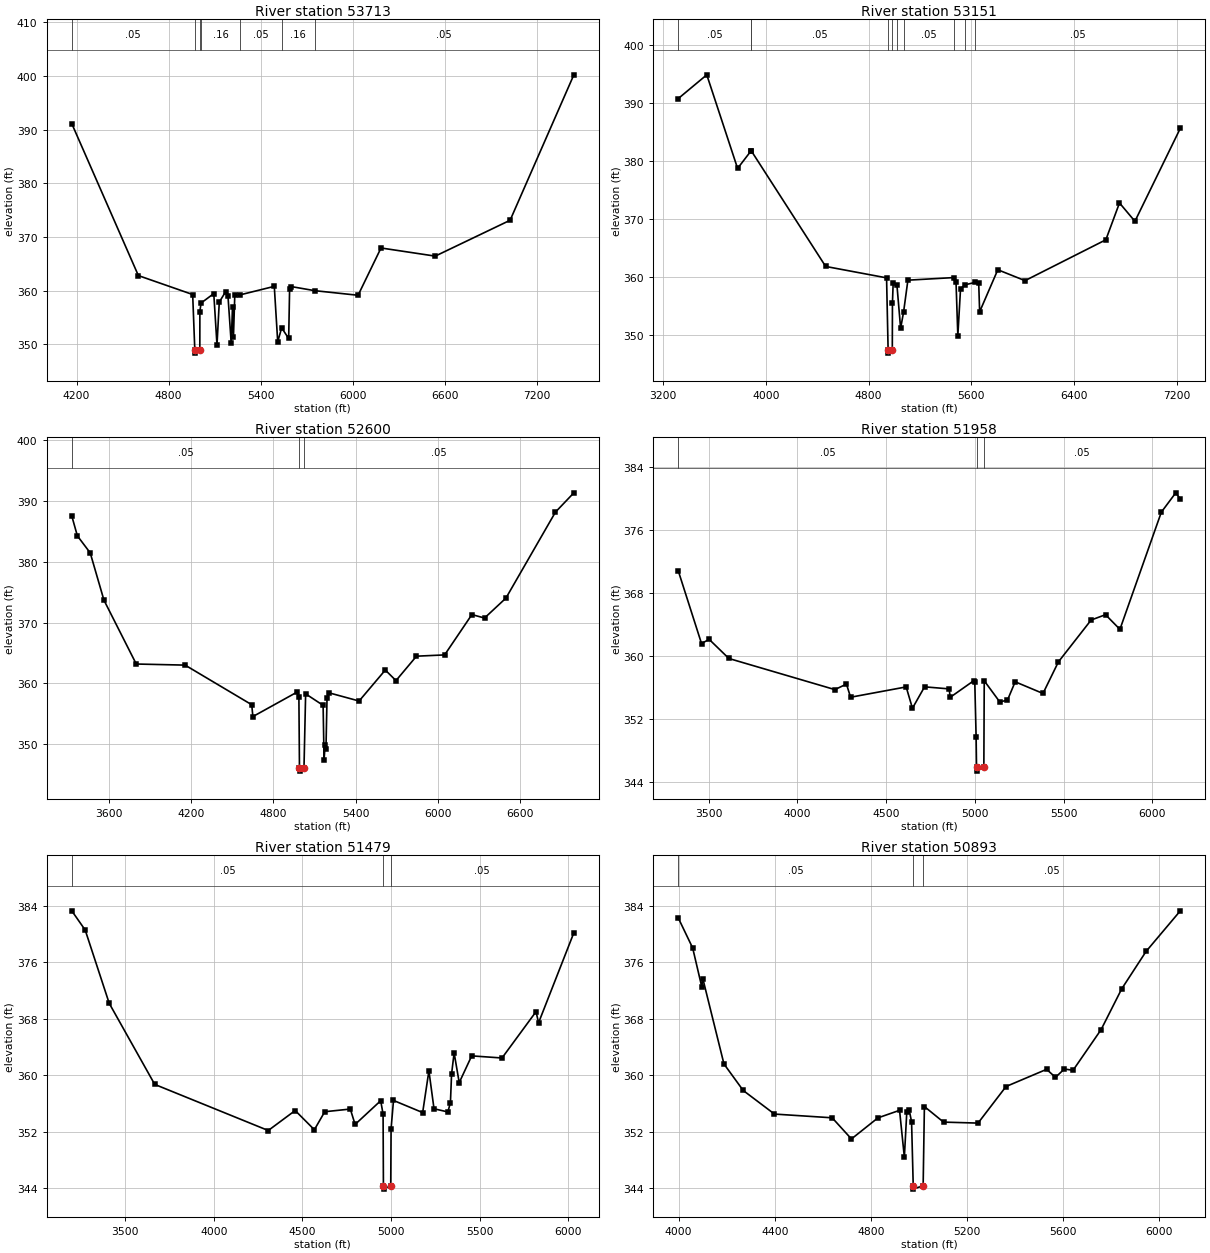
Type RM Length L Ch R = 1,53713,562,562,562
BEGIN DESCRIPTION:
North Twin Creek53712.675
END DESCRIPTION:
XS GIS Cut Line= 3
      2730926.01      6823260.99      2730226.00      6823711.00
      2728225.99      6825111.01
#Sta/Elev= 30
  4168.4  391.13  4602.7  362.79  4956.7  359.26  4970.7  348.83  4971.3  348.33
  5003.3  348.83  5003.6  356.09  5011.3  357.67  5094.3  359.43  5115.2  349.84
  5130.1  357.86  5171.9  359.79  5186.7  359.05  5208.1  350.14  5216.4  356.99
  5222.5  351.31  5231.2  359.09  5267.8  359.21  5488.8  360.78  5511.1  350.45
  5536.9  353.04  5582.6  351.06  5588.7  360.34  5597.4  360.75  5751.8  359.98
  6035.1  359.12  6184.6  367.94  6538.2  366.42  7026.4  373.11  7441.9  400.23
#Mann=7,-1,0
  4168.4    0.05       0  4970.7    0.05       0  5003.3    0.05       0
  5011.3    0.16       0  5267.8    0.05       0  5536.9    0.16       0
  5751.8    0.05       0
Bank Sta=4970.7,5003.3
Exp/Cntr=0.3,0.1

Type RM Length L Ch R = 1,53151,551,551,551
BEGIN DESCRIPTION:
North Twin Creek53150.5
END DESCRIPTION:
XS GIS Cut Line= 3
      2731451.61      6822601.84      2729926.00      6823311.00
      2728326.03      6824860.97
#Sta/Elev= 30
  3317.4  390.76  3539.7  394.86  3779.6  378.71  3885.4  381.76  3886.3  381.74
  4465.5  361.79  4939.8  359.82  4951.9  347.33  4952.4  346.83  4984.5  347.33
  4985.6  355.48  4991.1  358.87  5020.8  358.51  5049.3  351.10  5072.6  353.97
  5105.9  359.42  5464.5  359.87  5480.7  359.10  5494.8  349.85  5515.9  357.95
  5551.6  358.62  5625.3  359.02  5657.4  358.95  5664.6  353.96  5806.1  361.22
  6018.1  359.34  6647.5  366.39  6753.7  372.75  6873.9  369.58  7227.4  385.63
#Mann=10,-1,0
  3317.4    0.05       0  3885.4    0.07       0  3886.3    0.05       0
  4951.9    0.05       0  4984.5    0.05       0  5020.8    0.16       0
  5072.6    0.05       0  5464.5    0.16       0  5551.6    0.12       0
  5625.3    0.05       0
Bank Sta=4951.9,4984.5
Exp/Cntr=0.3,0.1

Type RM Length L Ch R = 1,52600,642,642,642
BEGIN DESCRIPTION:
North Twin Creek52600.032
END DESCRIPTION:
XS GIS Cut Line= 3
      2730916.62      6821913.83      2729576.00      6822911.00
      2728053.52      6824196.79
#Sta/Elev= 30
  3329.2  387.57  3370.0  384.29  3463.9  381.48  3564.0  373.70  3799.7  363.19
  4156.3  363.01  4642.3  356.49  4650.7  354.54  4971.9  358.55  4986.5  357.77
  4990.7  346.06  4991.3  345.56  5023.6  346.06  5035.7  358.28  5163.2  356.39
  5170.2  347.40  5177.5  349.78  5184.0  349.19  5191.8  357.62  5206.1  358.45
  5425.8  357.10  5617.0  362.20  5695.0  360.46  5844.5  364.48  6049.9  364.69
  6248.8  371.33  6341.1  370.76  6497.2  374.04  6858.7  388.20  6992.8  391.37
#Mann=3,-1,0
  3329.2    0.05       0  4990.7    0.05       0  5023.6    0.05       0
Bank Sta=4990.7,5023.6
Exp/Cntr=0.3,0.1

Type RM Length L Ch R = 1,51958,479,479,479
BEGIN DESCRIPTION:
North Twin Creek51958.33
END DESCRIPTION:
XS GIS Cut Line= 3
      2730563.19      6821608.89      2729126.34      6822454.90
      2728109.38      6823018.90
#Sta/Elev= 30
  3328.1  370.86  3459.3  361.62  3502.3  362.15  3613.6  359.72  4211.0  355.77
  4276.4  356.47  4299.6  354.80  4613.0  356.11  4648.3  353.40  4716.7  356.12
  4855.3  355.86  4861.1  354.79  4995.5  356.92  4999.7  356.77  5007.3  349.79
  5009.6  345.92  5010.6  345.42  5050.9  345.92  5053.1  356.89  5140.5  354.21
  5184.0  354.43  5227.5  356.76  5384.3  355.28  5471.2  359.29  5655.5  364.60
  5736.8  365.28  5818.0  363.42  6051.5  378.30  6132.7  380.75  6158.4  379.97
#Mann=3,-1,0
  3328.1    0.05       0  5009.6    0.05       0  5050.9    0.05       0
Bank Sta=5009.6,5050.9
Exp/Cntr=0.3,0.1

Type RM Length L Ch R = 1,51479,586,586,586
BEGIN DESCRIPTION:
North Twin Creek51478.752
END DESCRIPTION:
XS GIS Cut Line= 4
      2729576.00      6820561.00      2729235.68      6821471.17
      2728776.00      6822161.00      2727976.03      6822810.97
#Sta/Elev= 30
  3199.1  383.25  3274.8  380.53  3410.3  370.15  3666.9  358.67  4307.1  352.14
  4459.0  354.97  4567.2  352.25  4625.7  354.80  4769.9  355.18  4796.9  353.00
  4941.2  356.36  4954.7  354.46  4956.6  344.34  4957.6  343.84  4997.9  344.34
  4999.8  352.37  5013.4  356.40  5177.9  354.68  5213.1  360.60  5241.9  355.22
  5320.1  354.77  5334.5  356.10  5341.0  360.15  5355.3  363.14  5384.1  358.92
  5454.4  362.71  5625.4  362.41  5817.2  368.97  5831.6  367.40  6030.5  380.14
#Mann=3,-1,0
  3199.1    0.05       0  4956.6    0.05       0  4997.9    0.05       0
Bank Sta=4956.6,4997.9
Exp/Cntr=0.3,0.1

Type RM Length L Ch R = 1,50893,409,409,409
BEGIN DESCRIPTION:
North Twin Creek50893.379
END DESCRIPTION:
XS GIS Cut Line= 3
      2728426.00      6820760.97      2728376.00      6821761.00
      2727814.05      6822693.25
#Sta/Elev= 30
  3998.5  382.32  4058.6  378.05  4096.2  372.57  4101.2  373.65  4188.8  361.59
  4268.9  357.83  4399.0  354.48  4639.3  353.95  4719.4  350.95  4829.6  353.94
  4919.7  355.01  4939.7  348.36  4949.7  354.72  4959.7  355.06  4969.7  353.40
  4976.6  344.33  4977.6  343.83  5017.9  344.33  5023.1  355.55  5102.7  353.34
  5246.4  353.20  5362.9  358.39  5531.8  360.83  5568.6  359.69  5605.5  360.87
  5642.0  360.70  5758.7  366.47  5844.4  372.25  5945.6  377.55  6088.3  383.32
#Mann=3,-1,0
  3998.5    0.05       0  4976.6    0.05       0  5017.9    0.05       0
Bank Sta=4976.6,5017.9
Exp/Cntr=0.3,0.1

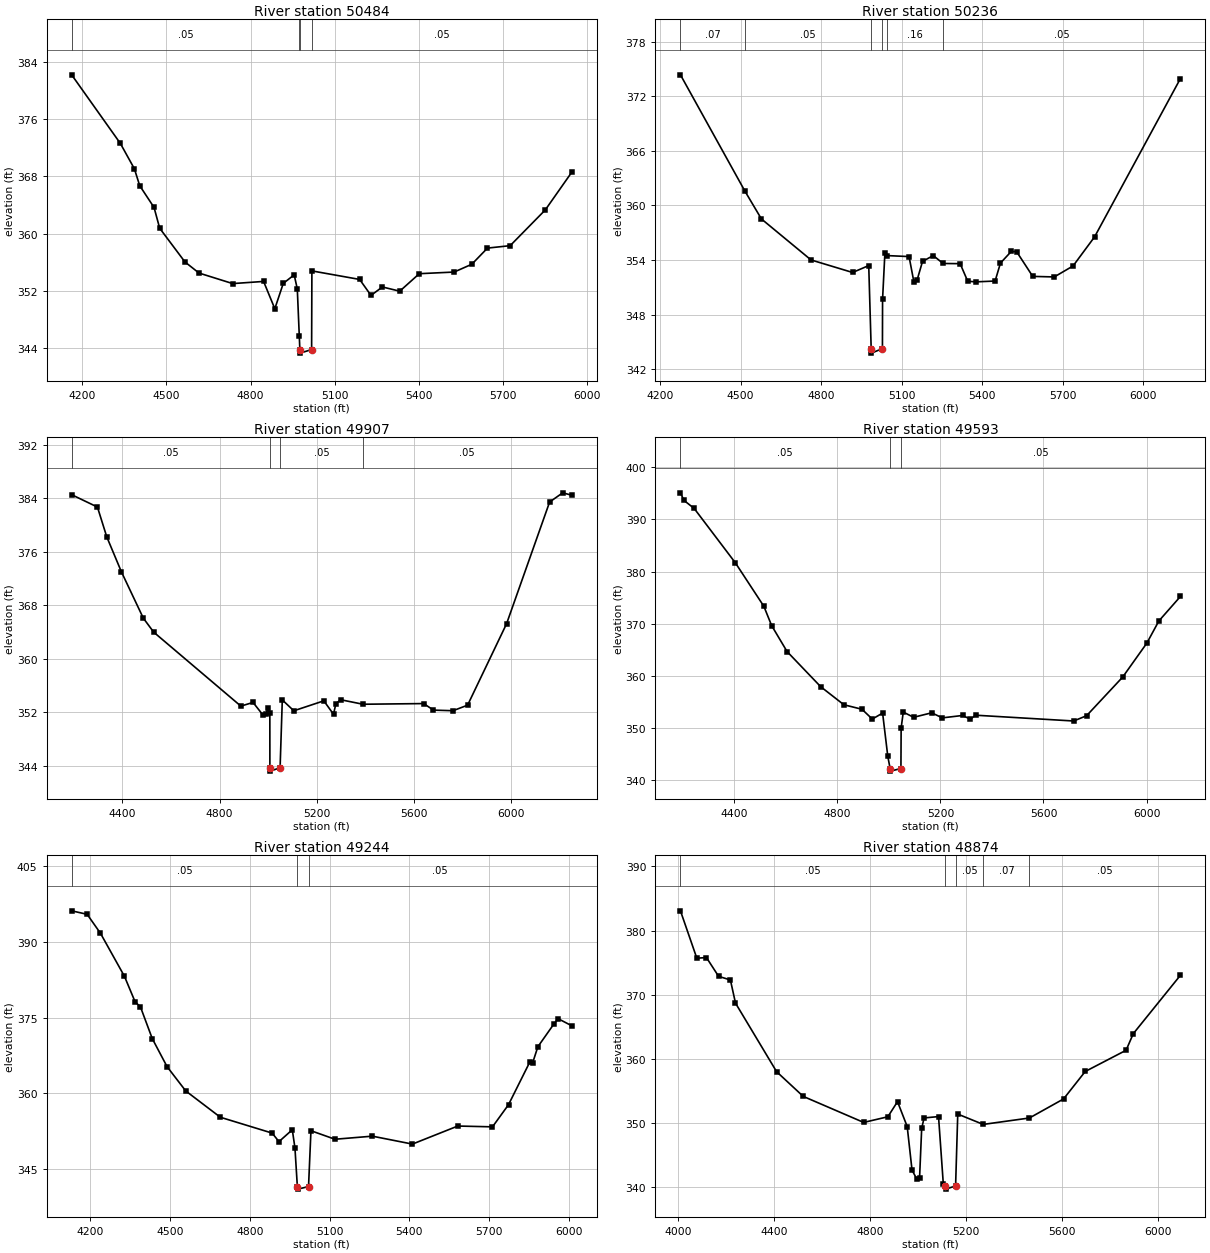
Type RM Length L Ch R = 1,50484,248,248,248
BEGIN DESCRIPTION:
North Twin Creek50483.91
END DESCRIPTION:
XS GIS Cut Line= 3
      2728129.95      6820647.65      2728098.97      6821499.84
      2727956.38      6822417.37
#Sta/Elev= 30
  4162.2  382.15  4335.7  372.58  4385.7  369.04  4404.6  366.69  4455.7  363.65
  4475.8  360.75  4565.8  356.05  4615.9  354.50  4735.9  353.03  4846.0  353.33
  4886.0  349.52  4916.1  353.06  4955.0  354.25  4966.1  352.28  4973.2  345.69
  4975.2  343.83  4976.2  343.33  5017.1  343.83  5018.1  354.80  5188.2  353.61
  5228.7  351.38  5269.1  352.56  5331.1  351.97  5400.7  354.41  5524.9  354.64
  5587.9  355.73  5643.6  357.98  5724.5  358.32  5849.7  363.31  5943.5  368.54
#Mann=4,-1,0
  4162.2    0.05       0  4973.2    0.16       0  4975.2    0.07       0
  5017.1    0.05       0
Bank Sta=4975.2,5017.1
Exp/Cntr=0.3,0.1

Type RM Length L Ch R = 1,50236,329,329,329
BEGIN DESCRIPTION:
North Twin Creek50236.18
END DESCRIPTION:
XS GIS Cut Line= 3
      2727976.70      6820600.77      2727937.13      6821348.85
      2727881.71      6822460.25
#Sta/Elev= 30
  4276.0  374.37  4515.3  361.62  4577.5  358.52  4762.3  354.01  4917.1  352.63
  4977.2  353.39  4986.3  344.26  4987.3  343.76  5028.2  344.26  5028.7  349.68
  5037.3  354.73  5043.7  354.49  5127.4  354.38  5145.3  351.60  5157.4  351.81
  5177.5  353.85  5217.5  354.49  5254.0  353.62  5317.6  353.60  5345.9  351.66
  5377.7  351.60  5447.8  351.69  5467.8  353.67  5507.9  354.94  5527.9  354.92
  5588.0  352.20  5668.1  352.14  5738.2  353.35  5818.3  356.55  6137.9  373.96
#Mann=6,-1,0
  4276.0    0.07       0  4515.3    0.05       0  4986.3    0.05       0
  5028.2    0.05       0  5043.7    0.16       0  5254.0    0.05       0
Bank Sta=4986.3,5028.2
Exp/Cntr=0.3,0.1

Type RM Length L Ch R = 1,49907,314,314,314
BEGIN DESCRIPTION:
North Twin Creek49907.02
END DESCRIPTION:
XS GIS Cut Line= 3
      2727739.86      6820357.10      2727669.29      6821173.73
      2727563.35      6822407.72
#Sta/Elev= 30
  4191.0  384.54  4297.1  382.69  4335.4  378.24  4395.7  373.00  4486.0  366.06
  4528.7  363.97  4887.5  352.90  4937.7  353.45  4977.8  351.60  4991.9  351.72
  4997.9  352.59  5006.8  351.92  5007.0  343.67  5008.0  343.17  5049.0  343.67
  5058.1  353.83  5105.5  352.20  5229.1  353.69  5268.9  351.68  5278.9  353.29
  5299.0  353.85  5390.2  353.18  5640.2  353.28  5680.4  352.30  5760.7  352.21
  5820.9  353.04  5981.5  365.24  6158.5  383.44  6212.3  384.82  6249.2  384.47
#Mann=4,-1,0
  4191.0    0.05       0  5007.0    0.05       0  5049.0    0.05       0
  5390.2    0.05       0
Bank Sta=5007,5049
Exp/Cntr=0.3,0.1

Type RM Length L Ch R = 1,49593,349,349,349
BEGIN DESCRIPTION:
North Twin Creek49593.4
END DESCRIPTION:
XS GIS Cut Line= 3
      2727421.53      6820297.73      2727372.91      6821119.17
      2727302.72      6822234.48
#Sta/Elev= 30
  4191.1  395.09  4204.7  393.64  4244.5  392.09  4404.7  381.64  4514.9  373.33
  4545.0  369.64  4605.1  364.65  4735.3  357.93  4825.5  354.46  4895.6  353.60
  4935.7  351.72  4975.7  352.87  4995.8  344.58  5004.8  342.24  5005.8  341.74
  5046.8  342.24  5047.6  349.99  5055.9  353.06  5096.0  352.06  5166.1  352.92
  5207.4  351.95  5286.3  352.41  5316.4  351.69  5336.4  352.46  5717.2  351.35
  5767.3  352.36  5907.6  359.78  6001.2  366.28  6047.9  370.53  6131.5  375.22
#Mann=3,-1,0
  4191.1    0.05       0  5004.8    0.05       0  5046.8    0.05       0
Bank Sta=5004.8,5046.8
Exp/Cntr=0.3,0.1

Type RM Length L Ch R = 1,49244,370,370,370
BEGIN DESCRIPTION:
North Twin Creek49244.21
END DESCRIPTION:
XS GIS Cut Line= 3
      2727094.41      6820142.84      2727055.60      6821016.50
      2726977.15      6822017.51
#Sta/Elev= 30
  4130.9  396.17  4189.1  395.48  4239.2  391.71  4329.3  383.18  4369.3  378.12
  4389.3  377.13  4433.7  370.84  4489.4  365.27  4559.5  360.46  4689.6  355.24
  4884.2  352.10  4909.8  350.41  4959.9  352.76  4969.9  349.14  4978.9  341.49
  4979.9  340.99  5020.9  341.49  5030.0  352.57  5120.3  350.88  5260.7  351.49
  5411.2  349.92  5581.7  353.50  5712.1  353.34  5772.3  357.73  5852.5  366.21
  5862.5  365.95  5882.6  369.22  5942.8  373.73  5959.0  374.78  6009.5  373.39
#Mann=3,-1,0
  4130.9    0.05       0  4978.9    0.05       0  5020.9    0.05       0
Bank Sta=4978.9,5020.9
Exp/Cntr=0.3,0.1

Type RM Length L Ch R = 1,48874,571,571,571
BEGIN DESCRIPTION:
North Twin Creek48874.35
END DESCRIPTION:
XS GIS Cut Line= 3
      2726834.70      6819933.33      2726723.39      6820922.14
      2726683.34      6822006.95
#Sta/Elev= 30
  4011.2  383.08  4079.3  375.70  4119.5  375.79  4169.9  372.87  4219.1  372.30
  4240.3  368.69  4411.4  358.00  4522.1  354.15  4773.7  350.09  4874.3  350.97
  4914.5  353.33  4954.8  349.45  4974.9  342.66  4995.0  341.24  5006.3  341.46
  5015.1  349.16  5025.1  350.79  5085.2  351.00  5105.2  340.44  5114.2  340.19
  5115.2  339.69  5156.2  340.19  5165.2  351.39  5271.2  349.78  5463.4  350.78
  5605.5  353.75  5695.6  358.03  5865.7  361.34  5895.7  363.93  6091.8  373.03
#Mann=5,-1,0
  4011.2    0.05       0  5114.2    0.05       0  5156.2    0.05       0
  5271.2    0.07       0  5463.4    0.05       0
Bank Sta=5114.2,5156.2
Exp/Cntr=0.3,0.1

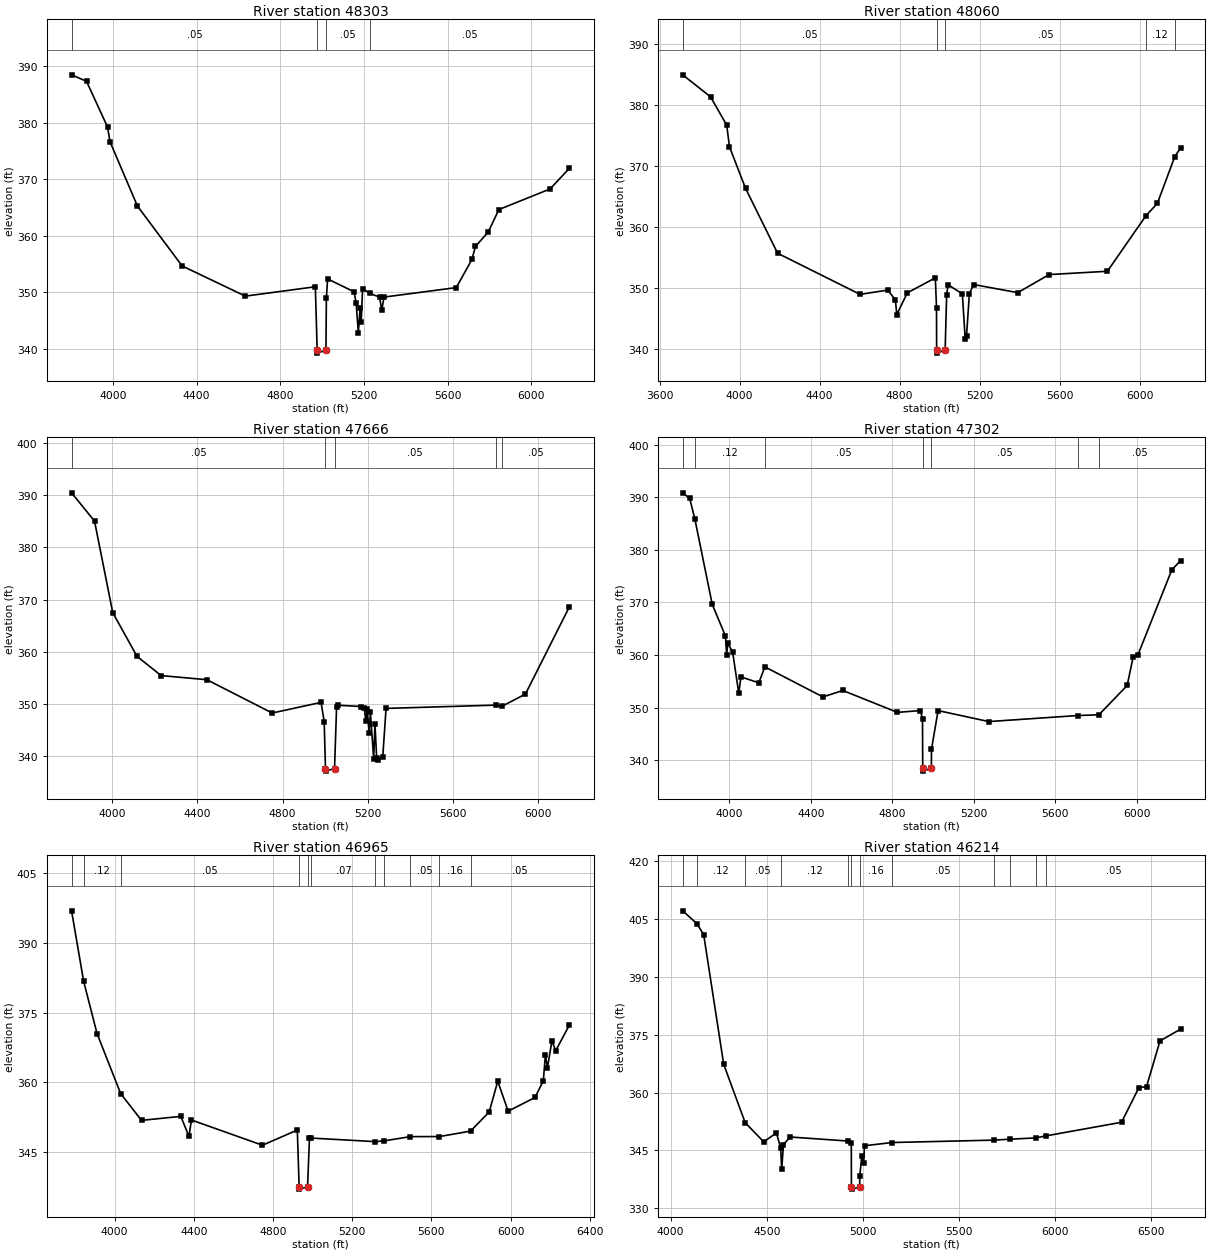
Type RM Length L Ch R = 1,48303,243,243,243
BEGIN DESCRIPTION:
North Twin Creek48303.499
END DESCRIPTION:
XS GIS Cut Line= 3
      2726808.87      6819701.81      2726355.96      6820811.12
      2726579.40      6821972.01
#Sta/Elev= 30
  3801.8  388.52  3873.3  387.38  3973.7  379.29  3985.6  376.68  4116.6  365.30
  4330.4  354.69  4632.6  349.34  4967.5  351.00  4976.2  339.75  4977.2  339.25
  5018.2  339.75  5020.2  348.94  5026.0  352.39  5152.6  350.11  5162.8  348.06
  5173.0  342.84  5181.8  347.32  5186.8  344.83  5193.4  350.68  5229.0  349.81
  5274.8  349.16  5285.0  346.80  5295.8  349.17  5641.4  350.85  5716.2  355.84
  5733.1  358.13  5794.2  360.70  5845.1  364.67  6089.7  368.31  6182.2  371.97
#Mann=4,-1,0
  3801.8    0.05       0  4976.2    0.05       0  5018.2    0.05       0
  5229.0    0.05       0
Bank Sta=4976.2,5018.2
Exp/Cntr=0.3,0.1

Type RM Length L Ch R = 1,48060,394,394,394
BEGIN DESCRIPTION:
North Twin Creek48060.25
END DESCRIPTION:
XS GIS Cut Line= 3
      2726770.21      6819606.94      2726142.65      6820727.82
      2725391.69      6821670.20
#Sta/Elev= 30
  3715.4  384.89  3854.5  381.29  3935.5  376.66  3949.3  373.12  4029.5  366.32
  4190.1  355.68  4602.5  348.95  4741.5  349.65  4779.2  348.03  4785.9  345.63
  4838.5  349.20  4978.9  351.65  4984.7  346.77  4985.3  339.83  4986.3  339.33
  5027.9  339.83  5035.4  348.86  5042.4  350.53  5113.9  349.03  5128.3  341.59
  5134.7  342.14  5149.1  349.05  5170.3  350.56  5390.9  349.23  5547.9  352.19
  5839.3  352.73  6031.9  361.82  6089.2  363.84  6176.3  371.50  6205.0  372.91
#Mann=5,-1,0
  3715.4    0.05       0  4985.3    0.05       0  5027.9    0.05       0
  6031.9    0.12       0  6176.3    0.05       0
Bank Sta=4985.3,5027.9
Exp/Cntr=0.3,0.1

Type RM Length L Ch R = 1,47666,364,364,364
BEGIN DESCRIPTION:
North Twin Creek47666.19
END DESCRIPTION:
XS GIS Cut Line= 3
      2726577.86      6819502.88      2725868.06      6820469.09
      2725275.84      6821446.35
#Sta/Elev= 30
  3807.8  390.45  3915.8  385.05  4001.5  367.53  4115.7  359.16  4229.2  355.48
  4444.4  354.69  4751.5  348.32  4981.4  350.35  4996.1  346.69  5002.1  337.70
  5003.1  337.20  5044.7  337.70  5054.4  349.42  5060.2  349.81  5170.7  349.56
  5184.3  349.25  5192.1  346.83  5197.9  349.08  5207.6  344.42  5213.4  348.45
  5228.9  339.55  5234.8  346.30  5242.8  339.80  5250.3  339.35  5271.6  339.97
  5287.1  349.20  5802.8  349.83  5830.1  349.57  5942.5  351.93  6149.4  368.64
#Mann=5,-1,0
  3807.8    0.05       0  5002.1    0.05       0  5044.7    0.05       0
  5802.8    0.16       0  5830.1    0.05       0
Bank Sta=5002.1,5044.7
Exp/Cntr=0.3,0.1

Type RM Length L Ch R = 1,47302,337,337,337
BEGIN DESCRIPTION:
North Twin Creek47302.02
END DESCRIPTION:
XS GIS Cut Line= 3
      2726086.11      6819158.02      2725596.33      6820302.55
      2725144.13      6821413.30
#Sta/Elev= 30
  3771.4  390.82  3805.8  389.76  3831.3  385.81  3916.5  369.60  3981.3  363.61
  3987.2  360.00  3992.7  362.19  4016.3  360.61  4046.6  352.76  4057.4  355.82
  4145.1  354.70  4174.9  357.73  4459.9  352.02  4557.8  353.24  4825.4  349.08
  4938.5  349.42  4948.8  347.86  4949.8  338.41  4950.8  337.91  4992.4  338.41
  4992.9  342.07  5025.3  349.42  5274.2  347.33  5710.1  348.48  5814.8  348.62
  5953.6  354.19  5983.1  359.64  6007.1  360.08  6173.1  376.20  6215.6  377.92
#Mann=7,-1,0
  3771.4    0.16       0  3831.3    0.12       0  4174.9    0.05       0
  4949.8    0.05       0  4992.4    0.05       0  5710.1    0.16       0
  5814.8    0.05       0
Bank Sta=4949.8,4992.4
Exp/Cntr=0.3,0.1

Type RM Length L Ch R = 1,46965,751,751,751
BEGIN DESCRIPTION:
North Twin Creek46965.25
END DESCRIPTION:
XS GIS Cut Line= 3
      2725637.84      6818996.06      2725338.07      6820188.29
      2724964.21      6821416.93
#Sta/Elev= 30
  3783.0  396.83  3843.8  381.75  3911.8  370.48  4031.2  357.59  4136.3  351.87
  4334.6  352.73  4375.8  348.44  4388.2  351.95  4747.0  346.54  4922.9  349.80
  4932.0  337.62  4933.0  337.12  4974.6  337.62  4984.2  348.01  4994.0  348.07
  5317.6  347.31  5361.0  347.47  5492.9  348.38  5640.5  348.40  5797.8  349.57
  5891.7  353.68  5935.0  360.27  5987.3  353.84  6123.2  356.79  6165.0  360.38
  6175.4  365.91  6185.9  363.16  6208.3  368.92  6227.7  366.83  6296.6  372.33
#Mann=11,-1,0
  3783.0    0.16       0  3843.8    0.12       0  4031.2    0.05       0
  4932.0    0.07       0  4974.6    0.05       0  4994.0    0.07       0
  5317.6    0.05       0  5361.0    0.07       0  5492.9    0.05       0
  5640.5    0.16       0  5797.8    0.05       0
Bank Sta=4932,4974.6
Exp/Cntr=0.3,0.1

Type RM Length L Ch R = 1,46214,597,597,597
BEGIN DESCRIPTION:
North Twin Creek46214.213
END DESCRIPTION:
XS GIS Cut Line= 3
      2725371.55      6818838.25      2724931.33      6819665.74
      2724859.93      6821317.70
#Sta/Elev= 30
  4062.7  407.02  4136.4  403.71  4171.9  400.87  4276.1  367.30  4387.9  352.19
  4484.5  347.24  4550.4  349.56  4572.5  345.66  4578.0  340.08  4586.9  346.52
  4622.0  348.49  4925.1  347.44  4940.2  346.83  4940.7  335.50  4941.7  335.00
  4983.7  335.50  4984.2  338.31  4994.5  343.48  5004.0  341.74  5009.0  346.22
  5151.4  347.06  5682.4  347.68  5764.1  347.92  5899.5  348.25  5954.3  348.79
  6346.5  352.30  6436.6  361.23  6476.6  361.54  6546.7  373.36  6653.5  376.40
#Mann=12,-1,0
  4062.7    0.05       0  4136.4    0.12       0  4387.9    0.05       0
  4572.5    0.12       0  4925.1    0.16       0  4940.7    0.07       0
  4983.7    0.16       0  5151.4    0.05       0  5682.4    0.07       0
  5764.1    0.05       0  5899.5    0.07       0  5954.3    0.05       0
Bank Sta=4940.7,4983.7
Exp/Cntr=0.3,0.1

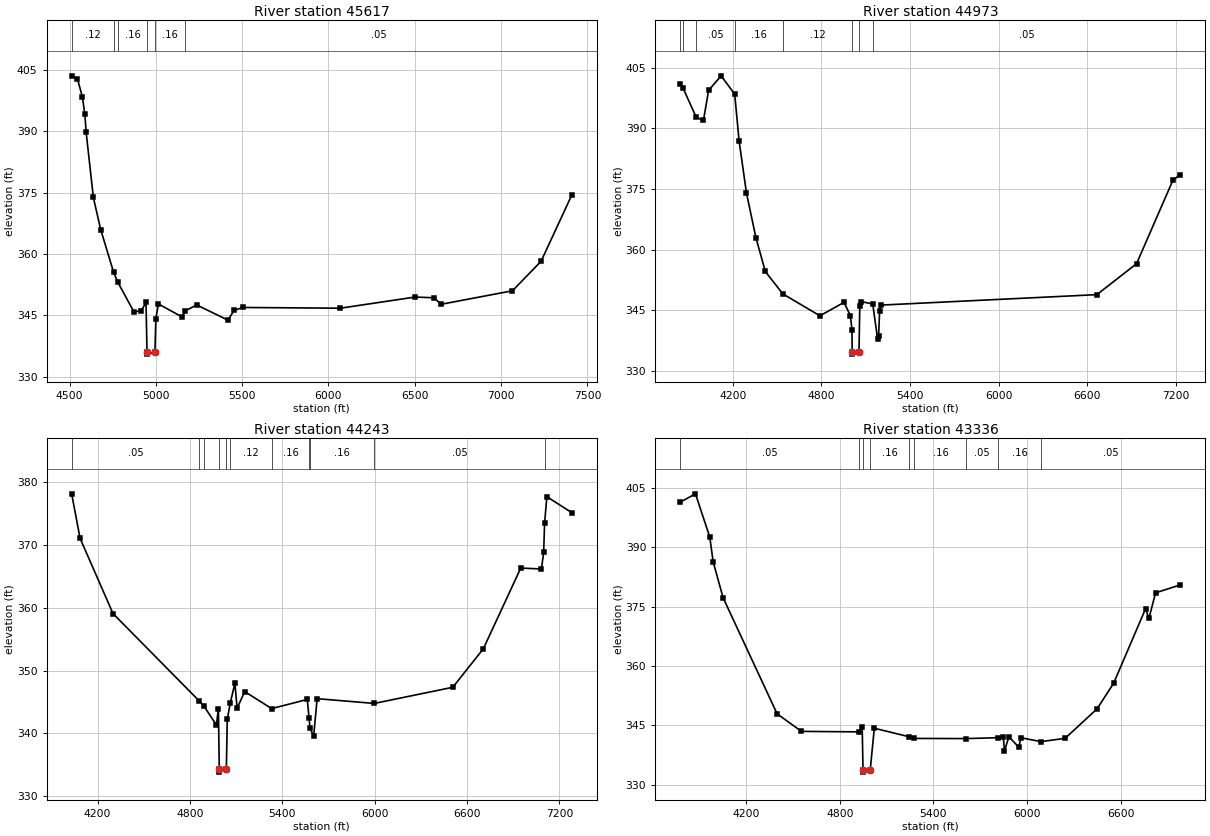
Type RM Length L Ch R = 1,45617,644,644,644
BEGIN DESCRIPTION:
North Twin Creek45616.93
END DESCRIPTION:
XS GIS Cut Line= 3
      2725280.97      6818828.25      2724887.20      6819165.44
      2722900.38      6820471.74
#Sta/Elev= 30
  4512.4  403.54  4545.8  402.81  4574.3  398.41  4588.6  394.21  4596.3  389.73
  4638.0  373.80  4680.8  365.91  4755.5  355.48  4779.9  353.06  4872.9  345.84
  4914.6  346.05  4943.1  348.13  4948.7  335.99  4949.7  335.49  4994.7  335.99
  5000.2  344.18  5014.5  347.77  5151.9  344.59  5171.6  346.11  5236.9  347.51
  5417.6  343.80  5453.8  346.22  5505.0  346.90  6068.4  346.72  6502.3  349.45
  6610.7  349.27  6652.9  347.68  7065.7  350.98  7231.3  358.19  7408.6  374.33
#Mann=6,-1,0
  4512.4    0.12       0  4755.5    0.05       0  4779.9    0.16       0
  4948.7    0.07       0  4994.7    0.16       0  5171.6    0.05       0
Bank Sta=4948.7,4994.7
Exp/Cntr=0.3,0.1

Type RM Length L Ch R = 1,44973,730,730,730
BEGIN DESCRIPTION:
North Twin Creek44973.329
END DESCRIPTION:
XS GIS Cut Line= 3
      2725278.75      6818135.49      2724376.00      6818861.00
      2722776.01      6820410.99
#Sta/Elev= 30
  3846.0  400.98  3864.9  399.91  3953.0  392.79  4001.8  391.98  4037.0  399.43
  4121.8  403.02  4213.6  398.48  4243.4  386.95  4293.0  374.11  4357.0  363.04
  4421.0  354.64  4539.0  349.11  4790.6  343.68  4953.8  347.00  4997.0  343.73
  5007.6  340.23  5009.3  334.70  5010.3  334.20  5055.3  334.70  5060.6  346.19
  5067.8  347.20  5148.3  346.60  5181.0  338.02  5188.0  338.56  5195.1  344.94
  5202.1  346.32  6666.0  348.91  6934.8  356.56  7182.3  377.31  7231.8  378.52
#Mann=8,-1,0
  3846.0    0.05       0  3864.9   0.094       0  3953.0    0.05       0
  4213.6    0.16       0  4539.0    0.12       0  5009.3    0.07       0
  5055.3    0.12       0  5148.3    0.05       0
Bank Sta=5009.3,5055.3
Exp/Cntr=0.3,0.1

Type RM Length L Ch R = 1,44243,907,907,907
BEGIN DESCRIPTION:
North Twin Creek44243.37
END DESCRIPTION:
XS GIS Cut Line= 3
      2724894.22      6817682.76      2724108.46      6818281.40
      2722349.55      6819700.47
#Sta/Elev= 30
  4032.2  378.13  4086.8  371.05  4300.9  359.07  4861.7  345.15  4891.6  344.35
  4972.3  341.34  4985.4  343.97  4990.9  334.35  4991.9  333.85  5037.0  334.35
  5042.9  342.25  5062.1  344.81  5092.4  347.99  5106.8  344.03  5156.4  346.66
  5331.3  343.96  5562.6  345.41  5574.5  342.43  5580.1  340.82  5604.2  339.61
  5626.6  345.54  5997.8  344.78  6507.8  347.35  6706.4  353.48  6949.2  366.32
  7083.6  366.17  7098.0  368.81  7104.2  373.50  7118.8  377.67  7280.0  375.15
#Mann=11,-1,0
  4032.2    0.05       0  4861.7    0.12       0  4891.6    0.16       0
  4990.9    0.07       0  5037.0    0.16       0  5062.1    0.12       0
  5331.3    0.16       0  5574.5    0.12       0  5580.1    0.16       0
  5997.8    0.05       0  7104.2   0.033       0
Bank Sta=4990.9,5037
Exp/Cntr=0.3,0.1

Type RM Length L Ch R = 1,43336,860,860,860
BEGIN DESCRIPTION:
North Twin Creek43335.88
END DESCRIPTION:
XS GIS Cut Line= 3
      2724342.76      6816901.44      2723413.46      6817745.68
      2722040.42      6819131.01
#Sta/Elev= 30
  3777.8  401.41  3874.3  403.49  3966.2  392.55  3987.8  386.31  4051.3  377.24
  4398.0  347.86  4554.1  343.43  4920.4  343.31  4943.3  344.58  4948.7  333.63
  4949.7  333.13  4994.8  333.63  5021.0  344.23  5242.7  342.09  5278.1  341.65
  5611.7  341.61  5814.8  341.84  5848.5  341.89  5855.6  338.51  5883.9  342.08
  5947.5  339.43  5961.6  341.82  6089.8  340.84  6244.5  341.67  6449.5  349.14
  6555.6  355.60  6760.6  374.47  6781.9  371.98  6824.3  378.45  6983.8  380.48
#Mann=9,-1,0
  3777.8    0.05       0  4920.4    0.16       0  4948.7    0.07       0
  4994.8    0.16       0  5242.7    0.12       0  5278.1    0.16       0
  5611.7    0.05       0  5814.8    0.16       0  6089.8    0.05       0
Bank Sta=4948.7,4994.8
Exp/Cntr=0.3,0.1