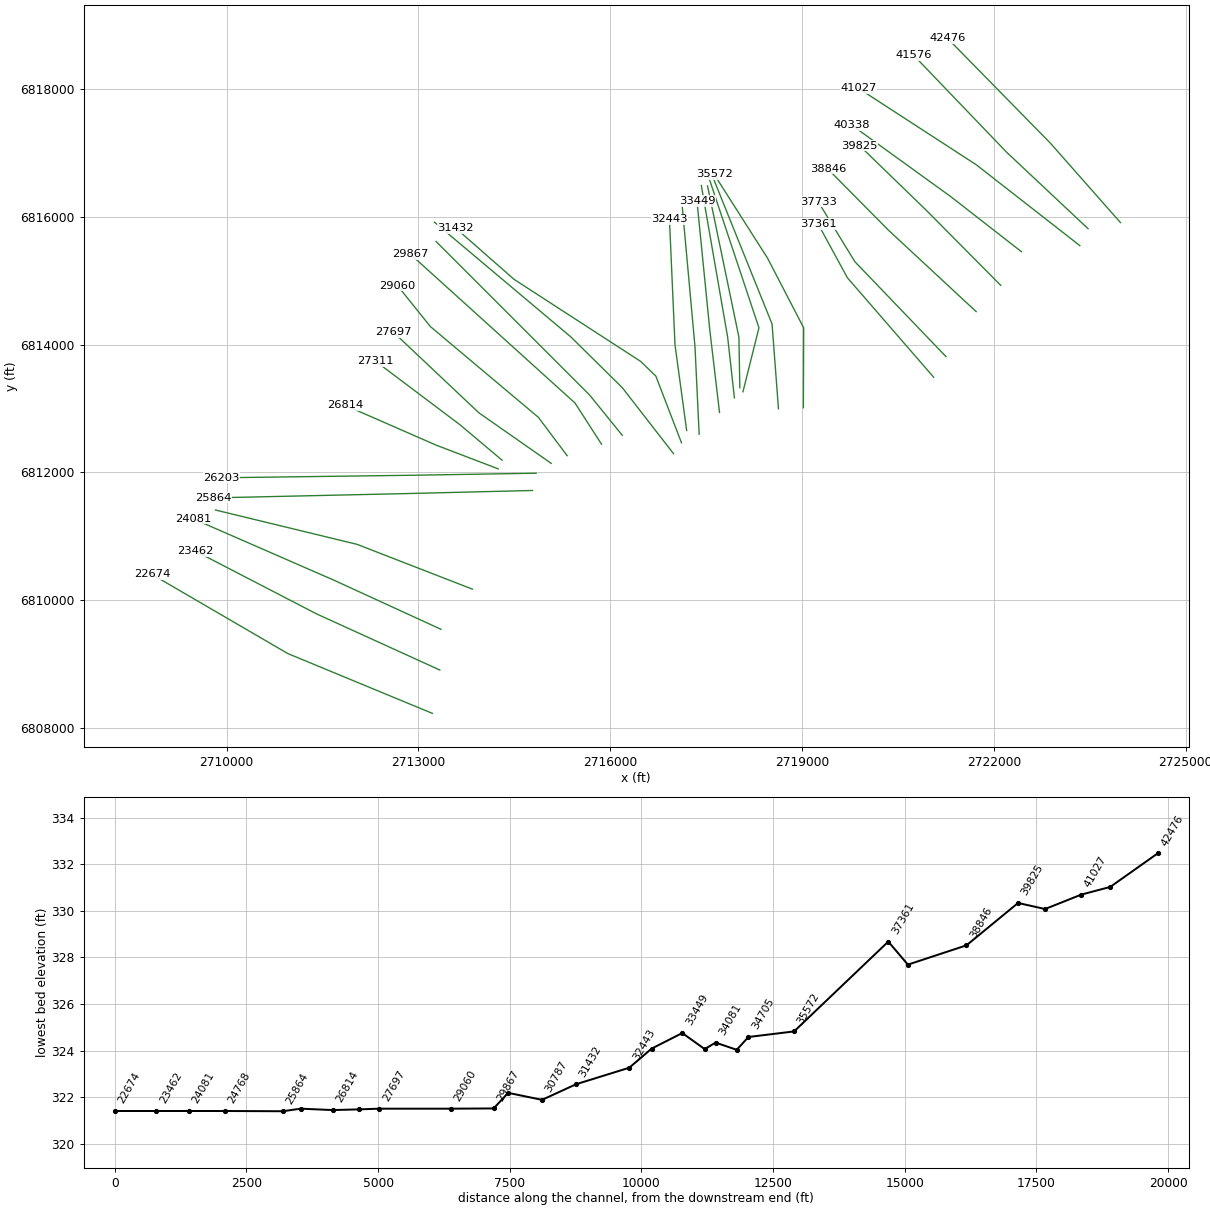
HEC-RAS study North Twin Creek.prj: North Twin Creek Base Level Engineering

--- North Twin Creek.g01 (geometry) --- (continued)

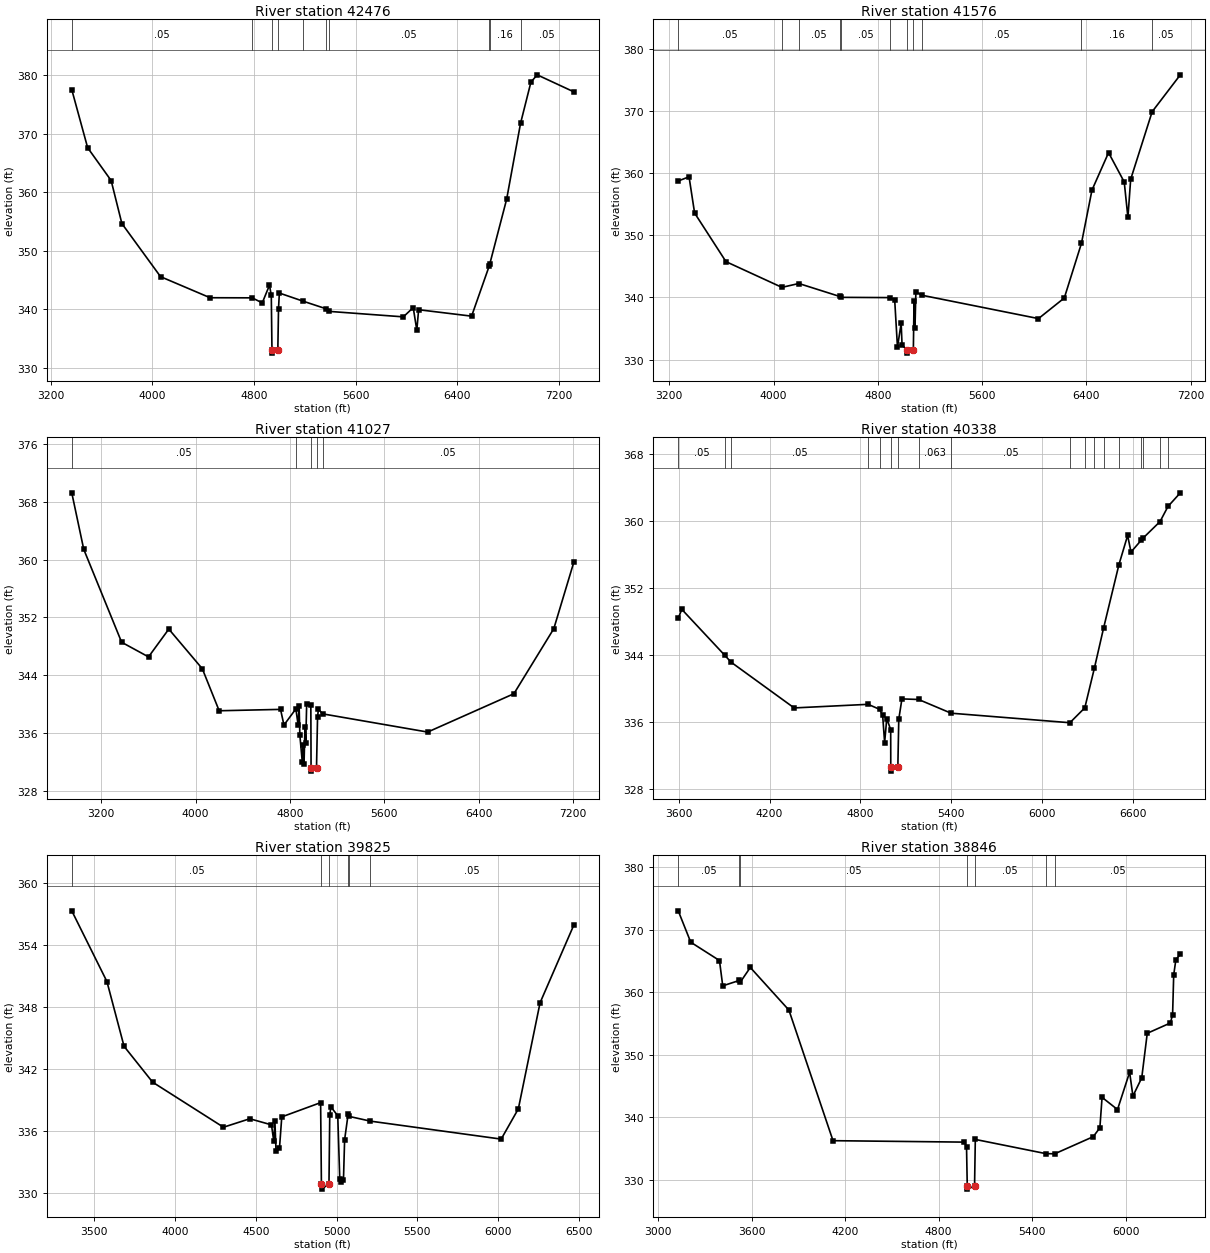
Type RM Length L Ch R = 1,42476,900,900,900
BEGIN DESCRIPTION:
North Twin Creek42476.27
END DESCRIPTION:
XS GIS Cut Line= 3
      2723979.98      6815908.04      2722885.25      6817148.92
      2721276.00      6818789.17
#Sta/Elev= 30
  3366.0  377.51  3491.0  367.58  3675.9  361.97  3760.4  354.62  4064.9  345.54
  4454.8  341.94  4786.7  341.92  4865.5  341.05  4922.4  344.08  4936.7  342.36
  4942.1  332.97  4943.1  332.47  4988.2  332.97  4993.6  340.08  5000.2  342.74
  5185.6  341.36  5370.9  340.03  5388.4  339.61  5976.3  338.67  6054.1  340.25
  6082.4  336.39  6096.6  339.89  6513.7  338.79  6652.6  347.38  6656.0  347.64
  6789.5  358.77  6899.0  371.75  6980.5  378.78  7029.9  380.04  7318.6  377.13
#Mann=10,-1,0
  3366.0    0.05       0  4786.7    0.12       0  4942.1    0.07       0
  4988.2    0.12       0  5185.6    0.05       0  5370.9    0.12       0
  5388.4    0.05       0  6652.6    0.12       0  6656.0    0.16       0
  6899.0    0.05       0
Bank Sta=4942.1,4988.2
Exp/Cntr=0.3,0.1

Type RM Length L Ch R = 1,41576,549,549,549
BEGIN DESCRIPTION:
Mapping XS 95fc58f0
END DESCRIPTION:
XS GIS Cut Line= 3
      2723473.98      6815811.46      2722196.42      6817011.33
      2720743.32      6818526.76
#Sta/Elev= 30
  3268.6  358.75  3351.6  359.42  3394.1  353.59  3634.9  345.76  4064.1  341.62
  4194.0  342.24  4506.9  340.16  4520.1  340.01  4894.4  339.97  4929.3  339.62
  4950.7  331.98  4979.0  335.85  4985.9  332.31  5026.4  331.53  5027.4  331.03
  5072.5  331.53  5077.8  339.42  5085.0  335.03  5091.9  340.92  5135.9  340.36
  6032.6  336.59  6230.7  339.91  6362.4  348.72  6443.0  357.28  6570.3  363.31
  6690.5  358.59  6718.8  352.87  6739.9  359.01  6904.7  369.90  7120.8  375.84
#Mann=11,-1,0
  3268.6    0.05       0  4064.1    0.16       0  4194.0    0.05       0
  4506.9    0.16       0  4520.1    0.05       0  4894.4    0.16       0
  5026.4    0.07       0  5072.5    0.16       0  5135.9    0.05       0
  6362.4    0.16       0  6904.7    0.05       0
Bank Sta=5026.4,5072.5
Exp/Cntr=0.3,0.1

Type RM Length L Ch R = 1,41027,689,689,689
BEGIN DESCRIPTION:
North Twin Creek41027.489
END DESCRIPTION:
XS GIS Cut Line= 3
      2723345.18      6815546.91      2721726.00      6816811.00
      2719880.05      6818009.37
#Sta/Elev= 30
  2950.3  369.24  3051.7  361.42  3372.8  348.55  3600.7  346.52  3772.6  350.37
  4056.6  344.88  4199.5  339.06  4719.6  339.25  4748.5  337.08  4849.6  339.32
  4868.8  337.06  4876.9  339.78  4883.3  335.67  4904.1  331.92  4912.2  334.36
  4918.6  331.66  4926.7  336.85  4933.0  334.56  4941.0  339.97  4976.4  339.83
  4978.3  331.20  4979.3  330.70  5024.4  331.20  5033.2  338.14  5040.2  339.28
  5076.5  338.63  5966.4  336.11  6697.4  341.42  7035.5  350.43  7205.3  359.65
#Mann=5,-1,0
  2950.3    0.05       0  4849.6    0.16       0  4978.3    0.07       0
  5024.4    0.16       0  5076.5    0.05       0
Bank Sta=4978.3,5024.4
Exp/Cntr=0.3,0.1

Type RM Length L Ch R = 1,40338,513,513,513
BEGIN DESCRIPTION:
North Twin Creek40338.328
END DESCRIPTION:
XS GIS Cut Line= 3
      2722430.84      6815452.49      2721324.36      6816314.95
      2719773.91      6817434.31
#Sta/Elev= 30
  3597.1  348.37  3620.7  349.43  3904.1  343.94  3946.2  343.11  4362.5  337.64
  4850.9  338.07  4927.2  337.47  4946.9  336.74  4959.9  333.50  4974.0  336.37
  5000.0  335.03  5000.4  330.58  5001.4  330.08  5047.2  330.58  5053.3  336.28
  5074.1  338.72  5184.2  338.65  5398.7  337.01  6183.2  335.87  6281.6  337.65
  6345.1  342.41  6405.8  347.21  6507.0  354.78  6564.4  358.27  6586.7  356.29
  6654.2  357.70  6669.0  358.00  6778.4  359.93  6830.9  361.74  6912.3  363.37
#Mann=18,-1,0
  3597.1    0.05       0  3904.1   0.063       0  3946.2    0.05       0
  4850.9   0.063       0  4927.2    0.12       0  5000.4    0.07       0
  5047.2    0.12       0  5184.2   0.063       0  5398.7    0.05       0
  6183.2   0.035       0  6281.6    0.05       0  6345.1   0.035       0
  6405.8    0.05       0  6507.0   0.035       0  6654.2    0.05       0
  6669.0   0.035       0  6778.4    0.05       0  6830.9   0.035       0
Bank Sta=5000.4,5047.2
Exp/Cntr=0.3,0.1

Type RM Length L Ch R = 1,39825,979,979,979
BEGIN DESCRIPTION:
North Twin Creek39825.11
END DESCRIPTION:
XS GIS Cut Line= 3
      2722107.93      6814925.41      2720939.69      6816103.63
      2719899.96      6817110.69
#Sta/Elev= 30
  3361.3  357.27  3578.8  350.43  3684.8  344.16  3861.6  340.69  4300.0  336.33
  4462.7  337.15  4597.0  336.56  4611.1  335.00  4618.2  336.90  4625.3  333.99
  4646.5  334.29  4660.7  337.33  4901.1  338.71  4906.0  330.84  4907.0  330.34
  4952.8  330.84  4957.6  337.49  4964.7  338.30  5007.1  337.44  5019.6  331.31
  5028.3  331.03  5042.4  331.18  5049.6  335.12  5071.4  337.60  5074.1  337.39
  5208.8  336.92  6018.4  335.18  6124.6  338.11  6258.9  348.37  6468.0  355.90
#Mann=6,-1,0
  3361.3    0.05       0  4906.0    0.07       0  4952.8    0.05       0
  5071.4    0.05       0  5074.1   0.035       0  5208.8    0.05       0
Bank Sta=4906,4952.8
Exp/Cntr=0.3,0.1

Type RM Length L Ch R = 1,38846,1113,1113,1113
BEGIN DESCRIPTION:
North Twin Creek38845.58
END DESCRIPTION:
XS GIS Cut Line= 3
      2721723.41      6814514.75      2720352.41      6815787.65
      2719402.26      6816747.22
#Sta/Elev= 30
  3129.2  373.04  3209.4  368.02  3393.7  365.09  3414.7  361.04  3522.0  361.91
  3528.4  361.67  3591.5  363.98  3839.3  357.16  4122.2  336.27  4964.6  336.04
  4978.8  335.30  4983.5  329.02  4984.5  328.52  5030.3  329.02  5035.2  336.47
  5487.5  334.20  5544.6  334.17  5791.8  336.91  5834.3  338.33  5848.4  343.20
  5947.4  341.25  6025.2  347.22  6046.3  343.41  6102.9  346.32  6138.3  353.45
  6286.8  355.10  6300.9  356.45  6308.0  362.79  6322.1  365.25  6350.4  366.08
#Mann=7,-1,0
  3129.2    0.05       0  3522.0    0.07       0  3528.4    0.05       0
  4983.5    0.05       0  5030.3    0.05       0  5487.5    0.16       0
  5544.6    0.05       0
Bank Sta=4983.5,5030.3
Exp/Cntr=0.3,0.1

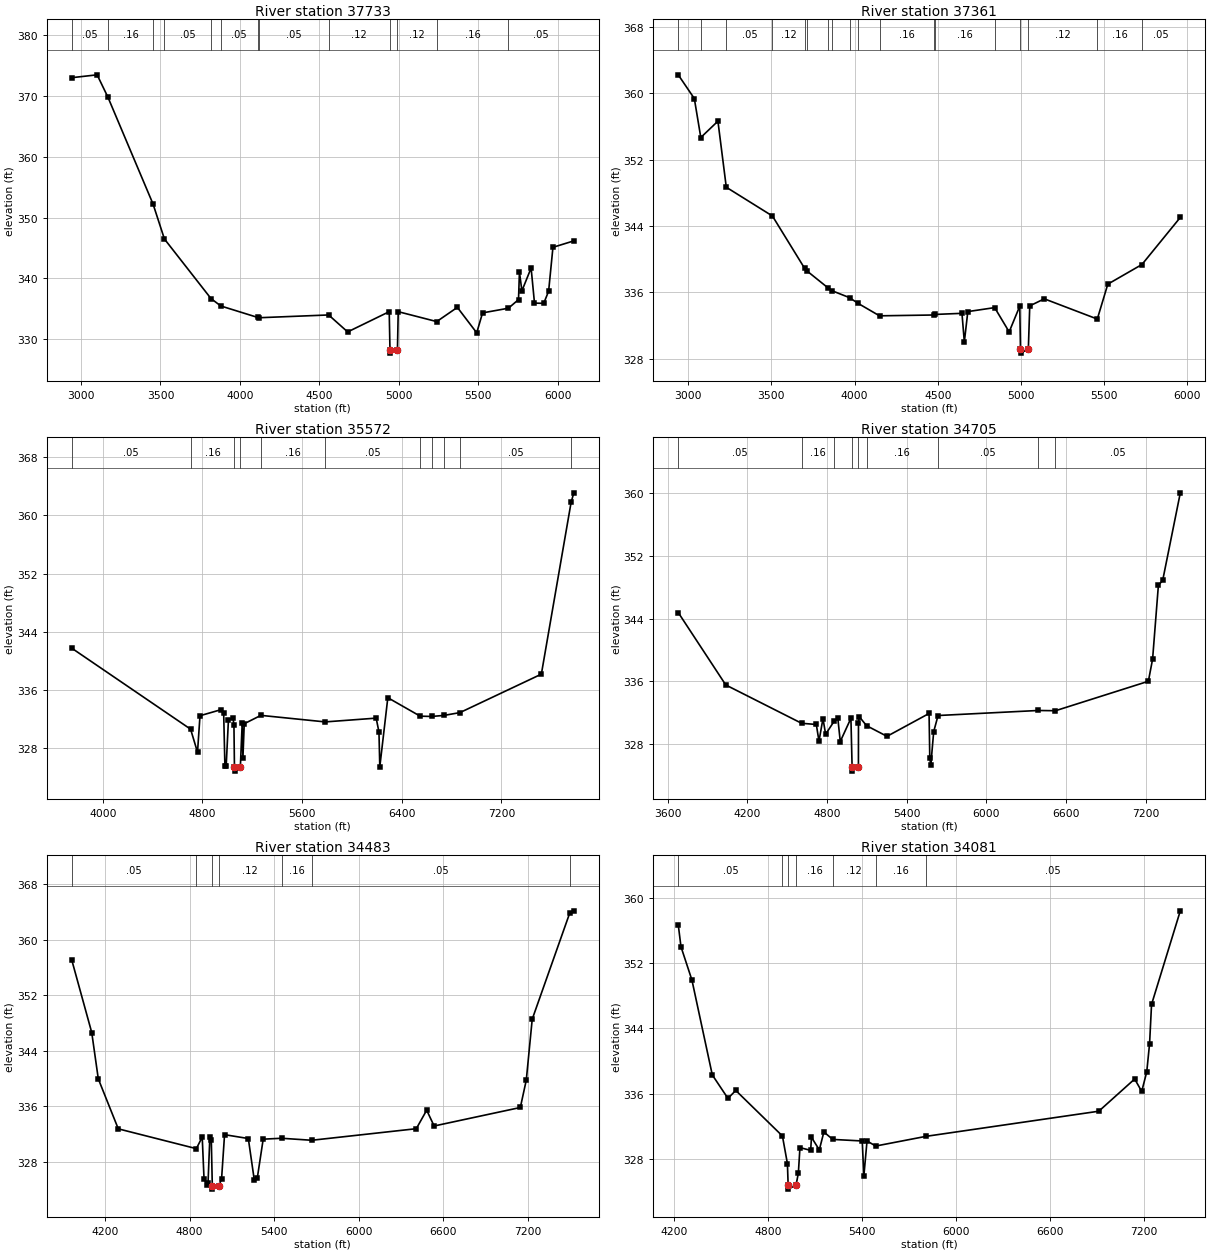
Type RM Length L Ch R = 1,37733,372,372,372
BEGIN DESCRIPTION:
North Twin Creek37732.507
END DESCRIPTION:
XS GIS Cut Line= 3
      2721251.66      6813811.04      2719826.14      6815295.93
      2719250.97      6816236.04
#Sta/Elev= 30
  2941.6  373.01  3101.2  373.48  3169.2  369.80  3453.5  352.20  3524.8  346.47
  3817.9  336.67  3879.6  335.45  4111.0  333.57  4117.1  333.51  4558.5  333.97
  4678.3  331.18  4939.9  334.51  4944.7  328.19  4945.7  327.69  4991.7  328.19
  4996.5  334.51  5238.9  332.88  5368.7  335.22  5490.7  331.03  5527.4  334.31
  5690.3  335.08  5753.8  336.50  5759.6  341.05  5775.1  337.93  5833.1  341.70
  5854.4  335.92  5912.5  335.88  5943.3  337.88  5970.5  345.10  6102.1  346.16
#Mann=13,-1,0
  2941.6    0.05       0  3169.2    0.16       0  3453.5    0.07       0
  3524.8    0.05       0  3817.9    0.12       0  3879.6    0.05       0
  4111.0    0.16       0  4117.1    0.05       0  4558.5    0.12       0
  4944.7    0.07       0  4991.7    0.12       0  5238.9    0.16       0
  5690.3    0.05       0
Bank Sta=4944.7,4991.7
Exp/Cntr=0.3,0.1

Type RM Length L Ch R = 1,37361,1789,1789,1789
BEGIN DESCRIPTION:
North Twin Creek37360.864
END DESCRIPTION:
XS GIS Cut Line= 3
      2721059.21      6813487.93      2719709.35      6815044.31
      2719251.00      6815886.00
#Sta/Elev= 30
  2939.8  362.25  3036.5  359.39  3075.5  354.69  3178.4  356.66  3228.7  348.69
  3506.1  345.22  3699.9  338.90  3715.8  338.56  3842.8  336.51  3865.1  336.20
  3969.8  335.37  4020.4  334.69  4149.9  333.18  4477.8  333.28  4486.4  333.35
  4645.6  333.48  4659.9  330.03  4680.8  333.69  4842.2  334.17  4929.4  331.24
  4993.2  334.35  4997.5  329.18  4998.5  328.68  5044.7  329.18  5053.2  334.38
  5140.7  335.23  5459.3  332.79  5522.5  337.00  5727.7  339.37  5958.4  345.05
#Mann=18,-1,0
  2939.8    0.05       0  3075.5    0.12       0  3228.7    0.05       0
  3506.1    0.12       0  3699.9    0.05       0  3715.8    0.12       0
  3842.8    0.16       0  3865.1    0.12       0  3969.8    0.16       0
  4020.4    0.05       0  4149.9    0.16       0  4477.8    0.12       0
  4486.4    0.16       0  4842.2    0.12       0  4997.5    0.07       0
  5044.7    0.12       0  5459.3    0.16       0  5727.7    0.05       0
Bank Sta=4997.5,5044.7
Exp/Cntr=0.3,0.1

Type RM Length L Ch R = 1,35572,867,867,867
BEGIN DESCRIPTION:
North Twin Creek35572.489
END DESCRIPTION:
XS GIS Cut Line= 4
      2719020.76      6813011.61      2719026.00      6814261.00
      2718462.10      6815347.84      2717625.98      6816661.03
#Sta/Elev= 30
  3751.3  341.73  4705.2  330.59  4760.7  327.42  4780.7  332.44  4950.7  333.28
  4970.7  332.84  4980.7  325.50  4990.7  325.46  5008.9  331.84  5045.8  332.16
  5053.2  331.12  5057.3  325.32  5058.3  324.82  5104.5  325.32  5119.6  331.47
  5125.2  326.59  5135.9  331.34  5269.8  332.49  5786.2  331.59  6194.9  332.11
  6217.4  330.20  6224.1  325.40  6288.5  334.92  6548.3  332.38  6639.6  332.34
  6737.9  332.48  6867.3  332.87  7521.1  338.16  7760.1  361.81  7781.9  363.10
#Mann=11,-1,0
  3751.3    0.05       0  4705.2    0.16       0  5057.3    0.07       0
  5104.5    0.16       0  5269.8    0.16       0  5786.2    0.05       0
  6548.3   0.035       0  6639.6   0.033       0  6737.9   0.035       0
  6867.3    0.05       0  7760.1   0.063       0
Bank Sta=5057.3,5104.5
Exp/Cntr=0.3,0.1

Type RM Length L Ch R = 1,34705,222,222,222
BEGIN DESCRIPTION:
Mapping XS a7b95dc8
END DESCRIPTION:
XS GIS Cut Line= 3
      2718631.54      6812993.97      2718531.02      6814320.76
      2717614.76      6816594.17
#Sta/Elev= 30
  3679.6  344.77  4037.7  335.55  4609.0  330.67  4719.6  330.52  4739.7  328.39
  4769.7  331.27  4789.8  329.28  4854.9  330.96  4881.6  331.31  4900.1  328.35
  4980.3  331.31  4989.2  325.08  4990.2  324.58  5036.8  325.08  5037.2  330.65
  5042.8  331.52  5097.7  330.37  5252.0  329.01  5568.9  331.92  5574.3  326.27
  5581.9  325.34  5603.8  329.61  5636.6  331.66  6390.4  332.30  6521.1  332.27
  7220.7  336.02  7252.5  338.84  7296.2  348.24  7328.5  348.86  7461.3  360.01
#Mann=9,-1,0
  3679.6    0.05       0  4609.0    0.16       0  4854.9    0.12       0
  4989.2    0.07       0  5036.8    0.12       0  5097.7    0.16       0
  5636.6    0.05       0  6390.4   0.035       0  6521.1    0.05       0
Bank Sta=4989.2,5036.8
Exp/Cntr=0.3,0.1

Type RM Length L Ch R = 1,34483,402,402,402
BEGIN DESCRIPTION:
North Twin Creek34482.84
END DESCRIPTION:
XS GIS Cut Line= 3
      2718076.01      6813261.02      2718326.00      6814261.00
      2717525.99      6816661.02
#Sta/Elev= 30
  3964.7  357.09  4106.4  346.62  4152.8  339.94  4294.5  332.73  4848.2  329.87
  4889.8  331.55  4902.7  325.48  4923.3  324.58  4931.0  324.92  4943.9  331.50
  4954.2  331.16  4961.3  324.53  4962.3  324.03  5008.9  324.53  5027.1  325.52
  5048.2  331.89  5216.8  331.33  5259.0  325.35  5280.1  325.59  5322.2  331.24
  5452.5  331.37  5666.2  331.08  6407.9  332.75  6481.7  335.42  6534.4  333.14
  7145.8  335.81  7188.0  339.76  7230.1  348.55  7495.6  363.84  7525.3  364.19
#Mann=7,-1,0
  3964.7    0.05       0  4848.2    0.12       0  4961.3    0.07       0
  5008.9    0.12       0  5452.5    0.16       0  5666.2    0.05       0
  7495.6   0.063       0
Bank Sta=4961.3,5008.9
Exp/Cntr=0.3,0.1

Type RM Length L Ch R = 1,34081,206,206,206
BEGIN DESCRIPTION:
Mapping XS b78595c0
END DESCRIPTION:
XS GIS Cut Line= 3
      2718026.83      6813323.47      2718013.00      6814112.88
      2717521.65      6816481.01
#Sta/Elev= 30
  4225.7  356.69  4243.2  353.99  4313.2  349.91  4443.3  338.31  4543.3  335.44
  4593.3  336.41  4891.4  330.84  4923.3  327.47  4928.0  324.84  4929.0  324.34
  4978.6  324.84  4993.3  326.31  5003.4  329.42  5071.9  329.08  5077.0  330.68
  5127.1  329.14  5156.3  331.33  5212.9  330.42  5401.4  330.23  5411.6  325.92
  5432.0  330.23  5487.4  329.61  5810.0  330.80  6912.9  333.87  7142.2  337.81
  7187.2  336.29  7219.3  338.68  7237.4  342.13  7250.0  346.93  7433.8  358.38
#Mann=7,-1,0
  4225.7    0.05       0  4891.4    0.16       0  4928.0    0.07       0
  4978.6    0.16       0  5212.9    0.12       0  5487.4    0.16       0
  5810.0    0.05       0
Bank Sta=4928,4978.6
Exp/Cntr=0.3,0.1

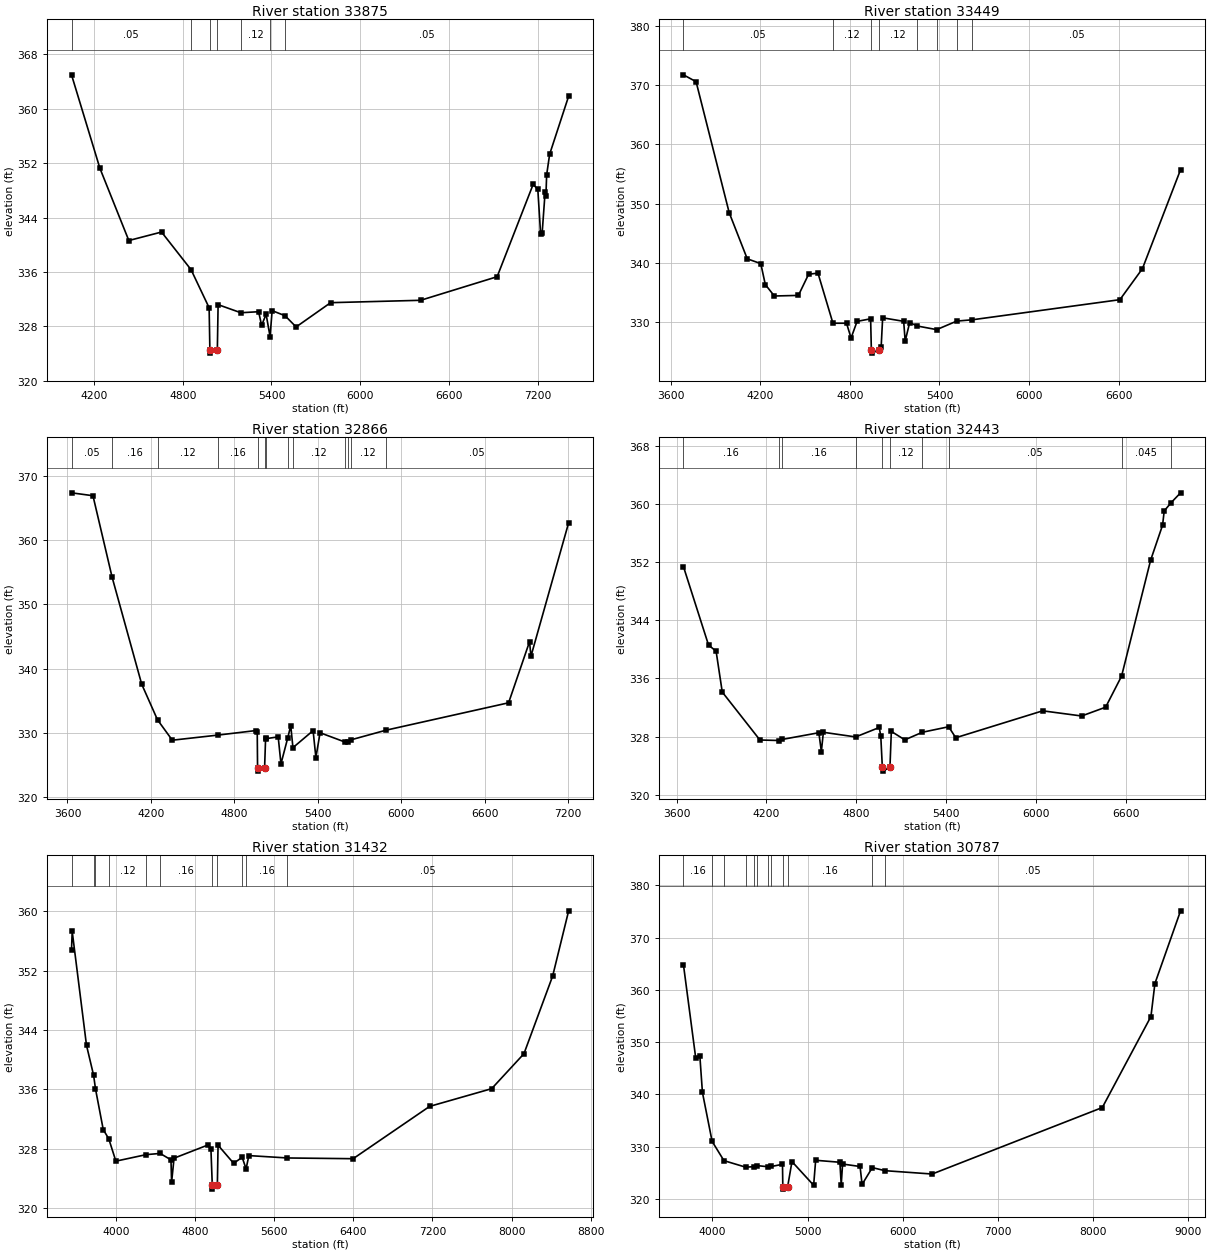
Type RM Length L Ch R = 1,33875,426,426,426
BEGIN DESCRIPTION:
North Twin Creek33916.347
END DESCRIPTION:
XS GIS Cut Line= 3
      2717942.25      6813165.71      2717836.68      6814112.64
      2717424.70      6816487.58
#Sta/Elev= 30
  4047.2  364.99  4238.8  351.27  4434.9  340.62  4656.2  341.87  4856.0  336.33
  4978.2  330.73  4983.2  324.56  4984.2  324.06  5033.8  324.56  5038.9  331.19
  5192.6  330.00  5313.0  330.15  5333.3  328.15  5363.7  329.78  5390.5  326.48
  5404.3  330.31  5491.8  329.56  5566.7  327.91  5800.1  331.48  6409.1  331.83
  6926.7  335.30  7170.3  348.88  7201.9  348.13  7221.0  341.53  7231.2  341.72
  7251.5  347.82  7256.6  347.11  7261.6  350.27  7281.9  353.31  7410.4  361.85
#Mann=7,-1,0
  4047.2    0.05       0  4856.0    0.16       0  4983.2    0.07       0
  5033.8    0.16       0  5192.6    0.12       0  5390.5    0.16       0
  5491.8    0.05       0
Bank Sta=4983.2,5033.8
Exp/Cntr=0.3,0.1

Type RM Length L Ch R = 1,33449,583,583,583
BEGIN DESCRIPTION:
North Twin Creek33403.586
END DESCRIPTION:
XS GIS Cut Line= 3
      2717709.35      6812936.95      2717555.65      6814241.33
      2717356.50      6816244.96
#Sta/Elev= 30
  3686.6  371.76  3771.2  370.60  3992.8  348.47  4113.6  340.68  4204.2  339.87
  4234.4  336.34  4294.8  334.40  4455.9  334.50  4524.2  338.07  4586.8  338.27
  4687.1  329.80  4778.1  329.80  4808.4  327.30  4848.6  330.11  4939.3  330.55
  4944.2  325.25  4945.2  324.75  4994.8  325.25  5009.7  325.77  5019.8  330.72
  5160.5  330.12  5170.5  326.79  5200.7  329.92  5251.6  329.33  5381.4  328.72
  5515.5  330.16  5619.2  330.38  6607.6  333.78  6758.3  339.02  7013.5  355.74
#Mann=8,-1,0
  3686.6    0.05       0  4687.1    0.12       0  4944.2    0.07       0
  4994.8    0.12       0  5251.6    0.16       0  5381.4    0.05       0
  5515.5    0.16       0  5619.2    0.05       0
Bank Sta=4944.2,4994.8
Exp/Cntr=0.3,0.1

Type RM Length L Ch R = 1,32866,423,423,423
BEGIN DESCRIPTION:
North Twin Creek32866.122
END DESCRIPTION:
XS GIS Cut Line= 3
      2717390.79      6812597.07      2717326.00      6813961.00
      2717126.00      6816160.96
#Sta/Elev= 30
  3629.2  367.37  3783.3  366.92  3921.0  354.25  4133.7  337.61  4247.5  332.06
  4353.9  328.89  4683.7  329.69  4954.6  330.39  4964.6  330.16  4966.9  324.58
  4967.9  324.08  5017.5  324.58  5024.8  329.26  5030.9  329.14  5115.2  329.41
  5135.2  325.22  5183.2  329.19  5205.5  331.16  5221.3  327.73  5366.2  330.38
  5386.3  326.19  5416.4  330.05  5597.5  328.59  5615.3  328.57  5635.7  328.93
  5889.2  330.44  6772.0  334.71  6922.6  344.22  6932.6  341.94  7203.7  362.71
#Mann=13,-1,0
  3629.2    0.05       0  3921.0    0.16       0  4247.5    0.12       0
  4683.7    0.16       0  4966.9    0.07       0  5017.5    0.16       0
  5030.9    0.12       0  5183.2    0.16       0  5221.3    0.12       0
  5597.5    0.16       0  5615.3    0.05       0  5635.7    0.12       0
  5889.2    0.05       0
Bank Sta=4966.9,5017.5
Exp/Cntr=0.3,0.1

Type RM Length L Ch R = 1,32443,1011,1011,1011
BEGIN DESCRIPTION:
North Twin Creek32344.047
END DESCRIPTION:
XS GIS Cut Line= 3
      2717195.38      6812654.89      2717012.81      6813997.03
      2716926.00      6815961.01
#Sta/Elev= 30
  3645.5  351.38  3813.1  340.59  3863.6  339.75  3904.8  334.13  4156.3  327.54
  4283.3  327.47  4303.1  327.61  4549.9  328.54  4566.6  325.95  4580.1  328.60
  4795.6  327.96  4953.5  329.26  4963.6  328.05  4974.1  323.76  4975.1  323.26
  5024.8  323.76  5034.0  328.72  5124.1  327.56  5240.7  328.60  5416.9  329.36
  5464.4  327.85  6045.0  331.55  6305.2  330.84  6465.4  332.05  6571.9  336.32
  6765.7  352.24  6845.8  357.08  6856.7  359.03  6902.5  360.16  6965.9  361.52
#Mann=10,-1,0
  3645.5    0.16       0  4283.3    0.12       0  4303.1    0.16       0
  4795.6    0.12       0  4974.1    0.07       0  5024.8    0.12       0
  5240.7    0.16       0  5416.9    0.05       0  6571.9   0.045       0
  6902.5    0.05       0
Bank Sta=4974.1,5024.8
Exp/Cntr=0.3,0.1

Type RM Length L Ch R = 1,31432,645,645,645
BEGIN DESCRIPTION:
Mapping XS 0982cae6
END DESCRIPTION:
XS GIS Cut Line= 5
      2717114.56      6812462.49      2716713.33      6813506.20
      2716475.42      6813736.37      2714496.42      6815018.65
      2713580.11      6815823.05
#Sta/Elev= 30
  3550.8  354.82  3557.6  357.29  3702.3  341.93  3774.5  337.87  3793.2  336.06
  3871.6  330.57  3927.2  329.34  3999.2  326.32  4306.0  327.20  4447.0  327.36
  4556.3  326.50  4562.8  323.48  4587.5  326.72  4932.1  328.51  4960.4  327.94
  4974.2  323.05  4975.2  322.55  5025.3  323.05  5032.6  328.47  5190.0  326.03
  5276.2  326.84  5315.9  325.28  5343.8  327.07  5734.0  326.75  6398.2  326.65
  7171.6  333.70  7799.1  336.09  8125.5  340.80  8415.8  351.27  8577.4  360.06
#Mann=11,-1,0
  3550.8    0.16       0  3774.5    0.12       0  3793.2    0.16       0
  3927.2    0.12       0  4306.0   0.035       0  4447.0    0.16       0
  4974.2    0.07       0  5025.3    0.16       0  5276.2    0.12       0
  5315.9    0.16       0  5734.0    0.05       0
Bank Sta=4974.2,5025.3
Exp/Cntr=0.3,0.1

Type RM Length L Ch R = 1,30787,645,645,645
BEGIN DESCRIPTION:
North Twin Creek30927.73
END DESCRIPTION:
XS GIS Cut Line= 4
      2716989.05      6812293.39      2716189.32      6813324.12
      2715382.58      6814119.75      2713249.56      6815913.72
#Sta/Elev= 30
  3695.4  364.83  3824.0  347.03  3867.5  347.44  3894.9  340.39  3996.8  331.01
  4121.2  327.33  4347.9  326.09  4438.9  326.17  4464.1  326.39  4585.8  326.16
  4619.0  326.21  4736.4  326.63  4739.8  322.38  4740.8  321.88  4790.9  322.38
  4836.0  327.15  5063.8  322.62  5085.0  327.40  5339.6  327.02  5353.7  322.72
  5367.9  326.68  5551.7  326.21  5572.9  322.78  5680.4  326.00  5813.2  325.41
  6309.3  324.77  8097.7  337.49  8608.9  354.91  8650.5  361.21  8920.2  375.13
#Mann=12,-1,0
  3695.4    0.16       0  3996.8    0.12       0  4121.2    0.16       0
  4347.9   0.035       0  4438.9    0.16       0  4464.1   0.035       0
  4585.8    0.12       0  4619.0    0.16       0  4739.8    0.07       0
  4790.9    0.16       0  5680.4    0.12       0  5813.2    0.05       0
Bank Sta=4739.8,4790.9
Exp/Cntr=0.3,0.1

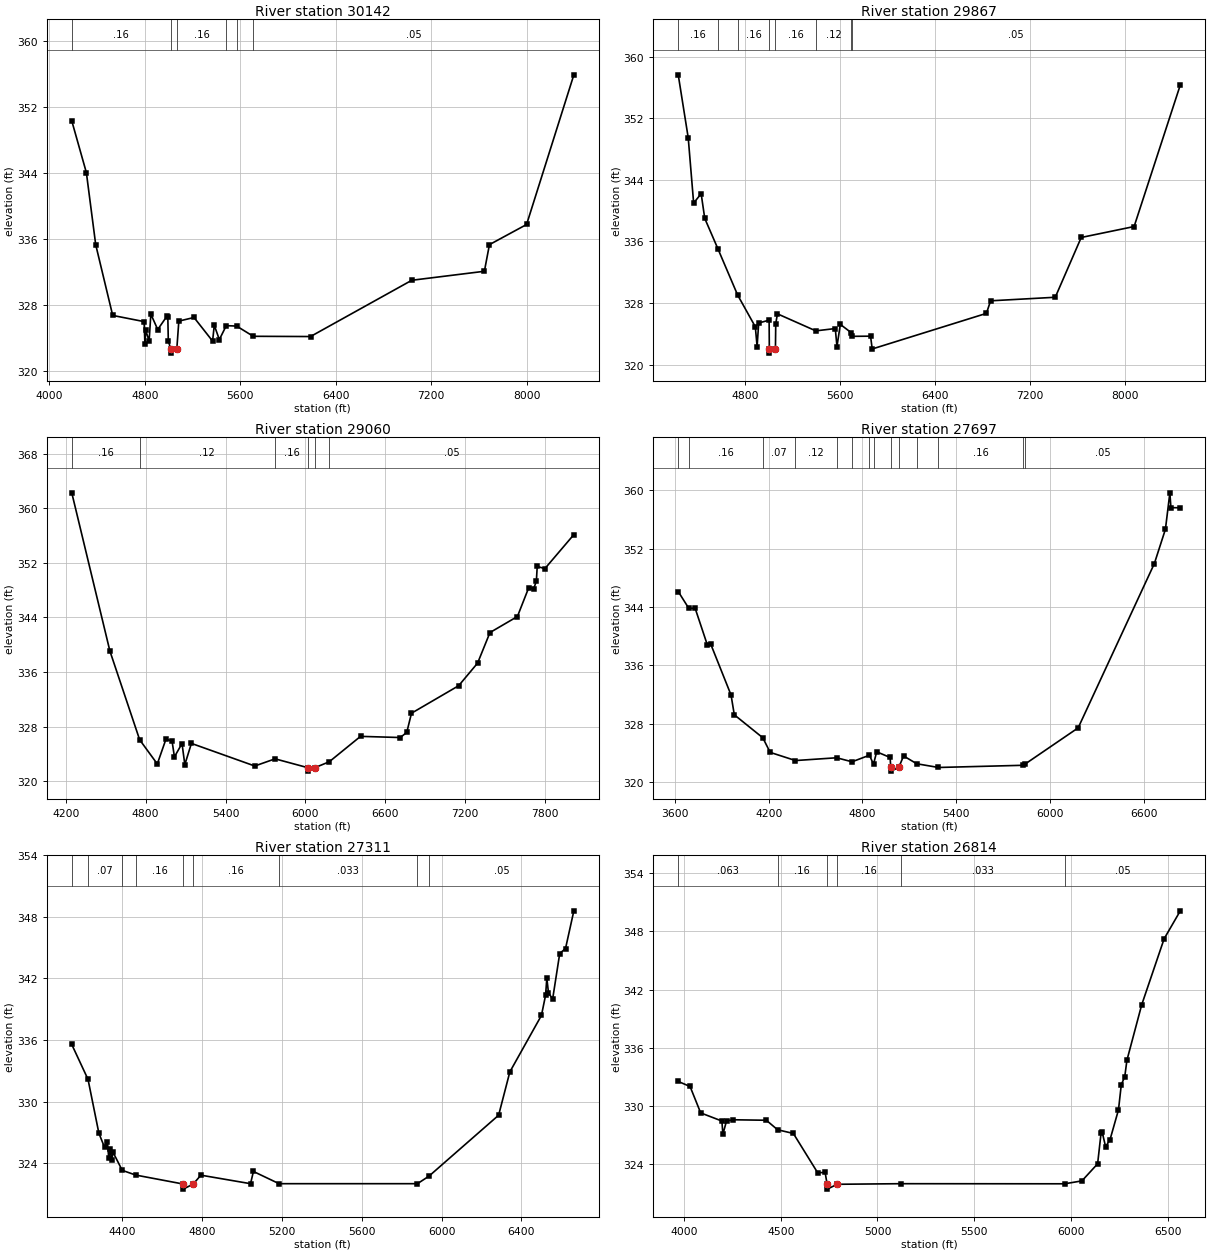
Type RM Length L Ch R = 1,30142,275,275,275
BEGIN DESCRIPTION:
North Twin Creek30142.079
END DESCRIPTION:
XS GIS Cut Line= 3
      2716187.68      6812580.60      2715676.00      6813211.00
      2713276.03      6815610.97
#Sta/Elev= 30
  4188.1  350.33  4310.4  344.06  4388.7  335.32  4530.9  326.75  4794.0  326.00
  4801.0  323.26  4807.5  324.93  4836.2  323.66  4850.6  326.91  4908.1  325.04
  4986.4  326.68  4992.8  326.53  4996.8  323.67  5016.8  322.68  5017.8  322.18
  5068.1  322.68  5084.9  326.06  5212.2  326.50  5367.7  323.64  5381.9  325.56
  5424.3  323.82  5482.3  325.51  5569.0  325.46  5708.4  324.22  6188.0  324.19
  7036.5  331.01  7644.6  332.10  7687.0  335.33  7998.2  337.77  8394.1  355.91
#Mann=6,-1,0
  4188.1    0.16       0  5016.8    0.07       0  5068.1    0.16       0
  5482.3    0.12       0  5569.0    0.16       0  5708.4    0.05       0
Bank Sta=5016.8,5068.1
Exp/Cntr=0.3,0.1

Type RM Length L Ch R = 1,29867,807,807,807
BEGIN DESCRIPTION:
North Twin Creek29526.195
END DESCRIPTION:
XS GIS Cut Line= 3
      2715863.80      6812440.63      2715448.68      6813084.99
      2712875.99      6815411.01
#Sta/Elev= 30
  4233.5  357.63  4317.8  349.45  4363.4  340.99  4426.8  342.20  4457.1  339.00
  4568.7  335.03  4734.5  329.05  4883.6  324.93  4898.8  322.37  4912.0  325.42
  5000.0  325.79  5001.9  322.01  5002.9  321.51  5053.3  322.01  5056.0  325.34
  5070.2  326.61  5393.9  324.40  5558.1  324.70  5572.3  322.37  5600.7  325.24
  5693.1  324.16  5699.5  323.69  5855.5  323.71  5869.7  322.05  6832.9  326.67
  6868.1  328.30  7413.5  328.76  7632.5  336.52  8078.6  337.94  8468.3  356.32
#Mann=8,-1,0
  4233.5    0.16       0  4568.7    0.12       0  4734.5    0.16       0
  5001.9    0.07       0  5053.3    0.16       0  5393.9    0.12       0
  5693.1    0.16       0  5699.5    0.05       0
Bank Sta=5001.9,5053.3
Exp/Cntr=0.3,0.1

Type RM Length L Ch R = 1,29060,1363,1363,1363
BEGIN DESCRIPTION:
North Twin Creek29059.824
END DESCRIPTION:
XS GIS Cut Line= 4
      2715325.99      6812261.01      2714876.00      6812861.00
      2713187.89      6814279.70      2712675.41      6814916.65
#Sta/Elev= 30
  4244.7  362.25  4531.1  339.09  4754.8  326.09  4887.4  322.55  4952.0  326.16
  4998.0  325.92  5016.1  323.59  5073.1  325.54  5094.2  322.45  5143.6  325.56
  5619.7  322.25  5772.3  323.30  6019.3  322.00  6020.3  321.50  6070.7  322.00
  6179.5  322.87  6414.4  326.59  6712.3  326.42  6761.7  327.16  6797.3  329.98
  7152.0  334.01  7294.1  337.32  7386.9  341.79  7593.3  344.14  7678.1  348.35
  7714.8  348.19  7735.6  349.29  7742.1  351.47  7799.6  351.15  8017.3  356.13
#Mann=6,-1,0
  4244.7    0.16       0  4754.8    0.12       0  5772.3    0.16       0
  6019.3    0.07       0  6070.7    0.16       0  6179.5    0.05       0
Bank Sta=6019.3,6070.7
Exp/Cntr=0.3,0.1

Type RM Length L Ch R = 1,27697,386,386,386
BEGIN DESCRIPTION:
North Twin Creek27460.173
END DESCRIPTION:
XS GIS Cut Line= 3
      2715076.35      6812141.09      2713945.96      6812931.11
      2712610.88      6814190.58
#Sta/Elev= 30
  3620.9  346.11  3687.9  343.83  3729.6  343.79  3807.2  338.80  3828.7  338.92
  3959.0  331.93  3979.9  329.22  4162.4  326.07  4209.3  324.07  4371.6  322.95
  4634.8  323.33  4733.8  322.78  4845.0  323.68  4871.2  322.44  4891.3  324.15
  4977.6  323.37  4981.3  322.00  4982.3  321.50  5032.7  322.00  5063.6  323.58
  5147.9  322.51  5287.1  322.00  5828.4  322.30  5843.8  322.50  6181.4  327.43
  6669.3  349.95  6740.1  354.65  6768.5  359.64  6775.3  357.61  6835.4  357.59
#Mann=14,-1,0
  3620.9    0.07       0  3687.9    0.16       0  4162.4    0.07       0
  4371.6    0.12       0  4634.8    0.16       0  4733.8    0.12       0
  4845.0    0.16       0  4871.2    0.12       0  4981.3    0.07       0
  5032.7    0.12       0  5147.9   0.033       0  5287.1    0.16       0
  5828.4    0.07       0  5843.8    0.05       0
Bank Sta=4981.3,5032.7
Exp/Cntr=0.3,0.1

Type RM Length L Ch R = 1,27311,497,497,497
BEGIN DESCRIPTION:
Mapping XS 15ec068e
END DESCRIPTION:
XS GIS Cut Line= 3
      2714307.71      6812190.94      2713646.51      6812747.23
      2712326.91      6813740.44
#Sta/Elev= 30
  4147.3  335.56  4228.8  332.16  4283.1  326.92  4311.7  325.53  4326.0  326.08
  4332.5  324.49  4340.3  325.38  4346.8  324.32  4354.6  325.04  4400.1  323.30
  4467.7  322.84  4704.8  321.97  4705.8  321.47  4756.2  321.97  4794.2  322.83
  5043.0  322.00  5057.5  323.19  5186.0  322.00  5879.4  322.00  5937.4  322.74
  6286.1  328.67  6342.3  332.89  6500.6  338.39  6521.4  340.36  6527.6  342.02
  6536.0  340.58  6556.8  339.99  6592.2  344.42  6621.3  344.91  6663.0  348.58
#Mann=9,-1,0
  4147.3   0.063       0  4228.8    0.07       0  4400.1    0.12       0
  4467.7    0.16       0  4704.8    0.07       0  4756.2    0.16       0
  5186.0   0.033       0  5879.4    0.07       0  5937.4    0.05       0
Bank Sta=4704.8,4756.2
Exp/Cntr=0.3,0.1

Type RM Length L Ch R = 1,26814,611,611,611
BEGIN DESCRIPTION:
Mapping XS ef9559ac
END DESCRIPTION:
XS GIS Cut Line= 3
      2714249.07      6812054.52      2713274.53      6812426.97
      2711853.16      6813048.99
#Sta/Elev= 30
  3970.2  332.54  4031.4  332.02  4086.1  329.30  4195.7  328.46  4201.0  327.09
  4219.7  328.47  4255.8  328.59  4425.5  328.54  4483.7  327.56  4565.1  327.18
  4690.8  323.13  4729.4  323.16  4739.6  321.94  4740.6  321.44  4791.7  321.94
  5120.8  322.00  5967.3  321.99  6056.5  322.29  6137.6  324.05  6155.5  327.23
  6161.0  327.34  6178.9  325.81  6201.7  326.54  6245.4  329.61  6260.0  332.21
  6277.9  333.03  6289.0  334.72  6365.4  340.44  6481.4  347.25  6565.0  350.13
#Mann=6,-1,0
  3970.2   0.063       0  4483.7    0.16       0  4739.6    0.07       0
  4791.7    0.16       0  5120.8   0.033       0  5967.3    0.05       0
Bank Sta=4739.6,4791.7
Exp/Cntr=0.3,0.1

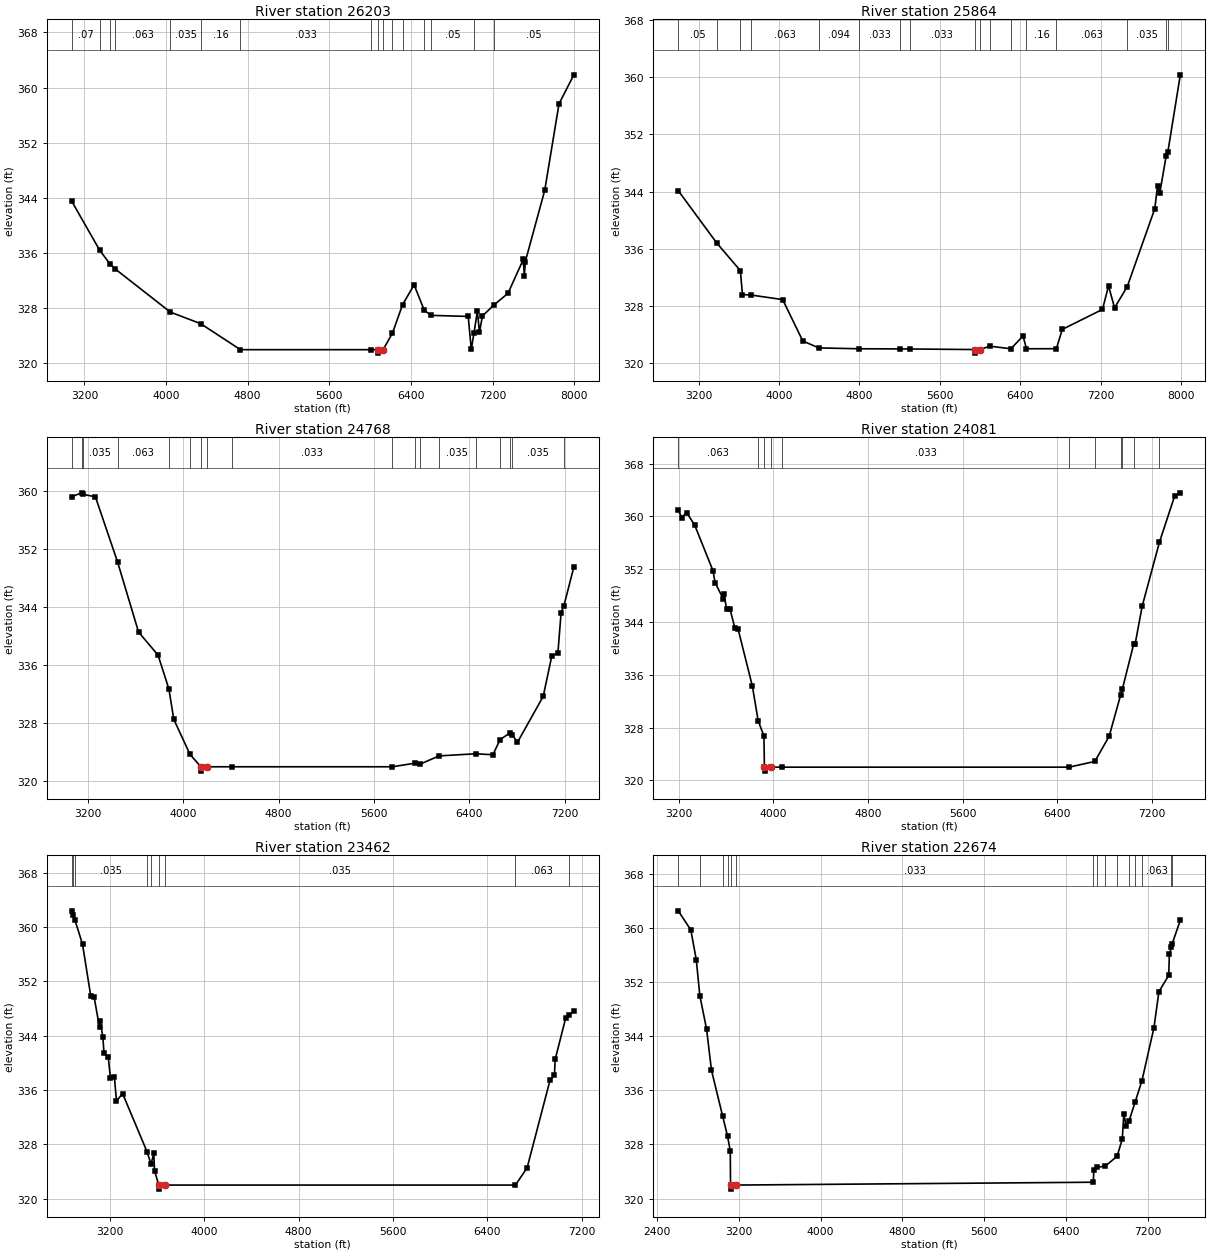
Type RM Length L Ch R = 1,26203,339,339,339
BEGIN DESCRIPTION:
North Twin Creek26328.551
END DESCRIPTION:
XS GIS Cut Line= 3
      2714841.35      6811986.92      2712917.51      6811955.09
      2709920.67      6811915.64
#Sta/Elev= 30
  3075.9  343.51  3350.0  336.40  3448.9  334.46  3504.3  333.67  4042.6  327.44
  4339.4  325.77  4729.2  322.00  6012.4  322.00  6075.6  322.00  6076.6  321.50
  6127.7  322.00  6219.4  324.41  6318.4  328.53  6431.6  331.40  6531.3  327.69
  6599.9  326.97  6961.7  326.82  6991.7  322.06  7018.7  324.47  7051.7  327.56
  7071.7  324.57  7101.7  326.89  7214.7  328.49  7351.7  330.17  7501.7  335.08
  7511.7  332.71  7521.7  334.78  7711.7  345.10  7851.8  357.64  7997.1  361.84
#Mann=16,-1,0
  3075.9    0.07       0  3350.0    0.16       0  3448.9    0.07       0
  3504.3   0.063       0  4042.6   0.035       0  4339.4    0.16       0
  4729.2   0.033       0  6012.4    0.05       0  6075.6   0.033       0
  6127.7    0.05       0  6219.4   0.063       0  6318.4    0.05       0
  6531.3   0.035       0  6599.9    0.05       0  7018.7    0.16       0
  7214.7    0.05       0
Bank Sta=6075.6,6127.7
Exp/Cntr=0.3,0.1

Type RM Length L Ch R = 1,25864,1096,1096,1096
BEGIN DESCRIPTION:
North Twin Creek25585.046
END DESCRIPTION:
XS GIS Cut Line= 3
      2714784.38      6811716.72      2712782.69      6811667.66
      2709792.23      6811601.00
#Sta/Elev= 30
  2997.7  344.13  3380.5  336.81  3615.8  332.93  3636.3  329.58  3718.9  329.53
  4036.4  328.88  4236.5  323.09  4395.7  322.12  4797.8  322.00  5207.8  321.98
  5298.6  321.97  5945.8  321.89  5946.8  321.39  5998.0  321.89  6097.0  322.36
  6306.8  322.00  6427.0  323.80  6460.9  322.00  6758.7  322.01  6817.1  324.71
  7217.2  327.51  7277.3  330.80  7337.3  327.73  7462.9  330.68  7737.4  341.61
  7764.5  344.77  7787.4  343.81  7849.8  348.93  7867.8  349.59  7991.2  360.34
#Mann=17,-1,0
  2997.7    0.05       0  3380.5   0.063       0  3615.8   0.094       0
  3718.9   0.063       0  4395.7   0.094       0  4797.8   0.033       0
  5207.8   0.094       0  5298.6   0.033       0  5945.8   0.033       0
  5998.0   0.033       0  6097.0   0.033       0  6306.8   0.063       0
  6460.9    0.16       0  6758.7   0.063       0  7462.9   0.035       0
  7849.8   0.063       0  7867.8   0.035       0
Bank Sta=5945.8,5998
Exp/Cntr=0.3,0.1

Type RM Length L Ch R = 1,24768,687,687,687
BEGIN DESCRIPTION:
North Twin Creek24767.862
END DESCRIPTION:
XS GIS Cut Line= 3
      2713844.32      6810173.32      2712039.55      6810874.25
      2709825.99      6811411.00
#Sta/Elev= 30
  3063.9  359.24  3146.0  359.77  3157.8  359.57  3262.6  359.21  3449.3  350.18
  3624.5  340.57  3787.8  337.40  3879.2  332.72  3920.3  328.53  4056.1  323.71
  4147.5  322.00  4148.6  321.40  4201.0  322.00  4406.1  322.00  5754.5  322.00
  5941.6  322.49  5984.1  322.34  6146.4  323.50  6453.7  323.79  6598.6  323.66
  6658.6  325.75  6740.7  326.65  6761.0  326.42  6804.4  325.37  7020.4  331.70
  7092.5  337.26  7143.9  337.69  7170.6  343.24  7194.5  344.22  7277.7  349.55
#Mann=18,-1,0
  3063.9   0.035       0  3146.0   0.063       0  3157.8   0.035       0
  3449.3   0.063       0  3879.2   0.035       0  4056.1   0.033       0
  4147.5   0.033       0  4201.0   0.033       0  4406.1   0.033       0
  5754.5   0.063       0  5941.6   0.035       0  5984.1   0.063       0
  6146.4   0.035       0  6453.7    0.16       0  6658.6   0.035       0
  6740.7    0.16       0  6761.0   0.035       0  7194.5   0.063       0
Bank Sta=4147.5,4201
Exp/Cntr=0.3,0.1

Type RM Length L Ch R = 1,24081,619,619,619
BEGIN DESCRIPTION:
North Twin Creek24080.53
END DESCRIPTION:
XS GIS Cut Line= 3
      2713352.69      6809545.21      2711680.86      6810312.15
      2709475.33      6811274.77
#Sta/Elev= 30
  3195.3  360.93  3225.7  359.83  3266.2  360.59  3334.7  358.68  3489.6  351.75
  3507.1  349.96  3576.1  347.50  3581.6  348.26  3604.6  345.98  3633.1  345.95
  3673.6  343.15  3702.0  342.89  3822.5  334.26  3871.2  329.03  3920.0  326.73
  3924.0  322.00  3925.1  321.40  3977.5  322.00  4074.4  322.00  6500.4  322.00
  6718.3  322.87  6839.5  326.69  6937.0  332.98  6950.4  333.79  7046.1  340.61
  7058.5  340.61  7118.8  346.41  7264.3  356.08  7392.7  363.07  7441.1  363.58
#Mann=11,-1,0
  3195.3   0.063       0  3871.2    0.16       0  3924.0   0.033       0
  3977.5    0.16       0  4074.4   0.033       0  6500.4   0.035       0
  6718.3   0.063       0  6937.0   0.035       0  6950.4   0.063       0
  7046.1   0.035       0  7264.3   0.063       0
Bank Sta=3924,3977.5
Exp/Cntr=0.3,0.1

Type RM Length L Ch R = 1,23462,788,788,788
BEGIN DESCRIPTION:
North Twin Creek23462.41
END DESCRIPTION:
XS GIS Cut Line= 3
      2713334.23      6808908.36      2711406.17      6809786.33
      2709509.98      6810768.46
#Sta/Elev= 30
  2878.1  362.41  2889.8  361.77  2905.0  361.04  2969.2  357.49  3038.4  349.92
  3067.0  349.76  3113.1  345.23  3118.6  346.15  3141.6  343.81  3150.9  341.50
  3187.7  340.83  3205.3  337.80  3239.3  337.92  3256.9  334.38  3308.5  335.49
  3515.6  326.92  3549.9  325.08  3573.0  326.67  3579.4  324.11  3615.4  322.00
  3616.5  321.40  3669.0  322.00  6637.1  322.00  6736.1  324.53  6929.6  337.41
  6967.7  338.20  6973.9  340.52  7062.4  346.57  7087.8  347.05  7132.1  347.58
#Mann=9,-1,0
  2878.1   0.035       0  2889.8   0.063       0  2905.0   0.035       0
  3515.6    0.16       0  3549.9   0.035       0  3615.4   0.033       0
  3669.0   0.035       0  6637.1   0.063       0  7087.8   0.035       0
Bank Sta=3615.4,3669
Exp/Cntr=0.3,0.1

Type RM Length L Ch R = 1,22674,706,706,706
BEGIN DESCRIPTION:
North Twin Creek22674.43
END DESCRIPTION:
XS GIS Cut Line= 3
      2713217.46      6808230.29      2710957.19      6809165.60
      2708833.59      6810402.89
#Sta/Elev= 30
  2609.6  362.51  2732.4  359.69  2785.6  355.32  2820.4  350.00  2886.6  345.01
  2934.4  338.95  3042.1  332.26  3091.5  329.20  3117.9  327.03  3120.4  322.00
  3121.5  321.40  3174.1  322.00  6663.8  322.42  6668.6  324.26  6697.4  324.62
  6780.0  324.80  6896.1  326.25  6946.5  328.79  6962.2  332.56  6983.7  330.73
  7012.3  331.45  7071.2  334.22  7138.8  337.41  7255.9  345.24  7304.7  350.58
  7400.6  352.98  7406.5  356.12  7425.6  357.10  7433.7  357.64  7513.5  361.11
#Mann=15,-1,0
  2609.6   0.063       0  2820.4   0.035       0  3042.1   0.063       0
  3091.5   0.033       0  3120.4   0.033       0  3174.1   0.033       0
  6663.8   0.063       0  6697.4   0.035       0  6780.0   0.063       0
  6896.1   0.094       0  7012.3   0.063       0  7071.2   0.035       0
  7138.8   0.063       0  7425.6    0.16       0  7433.7   0.063       0
Bank Sta=3120.4,3174.1
Exp/Cntr=0.3,0.1