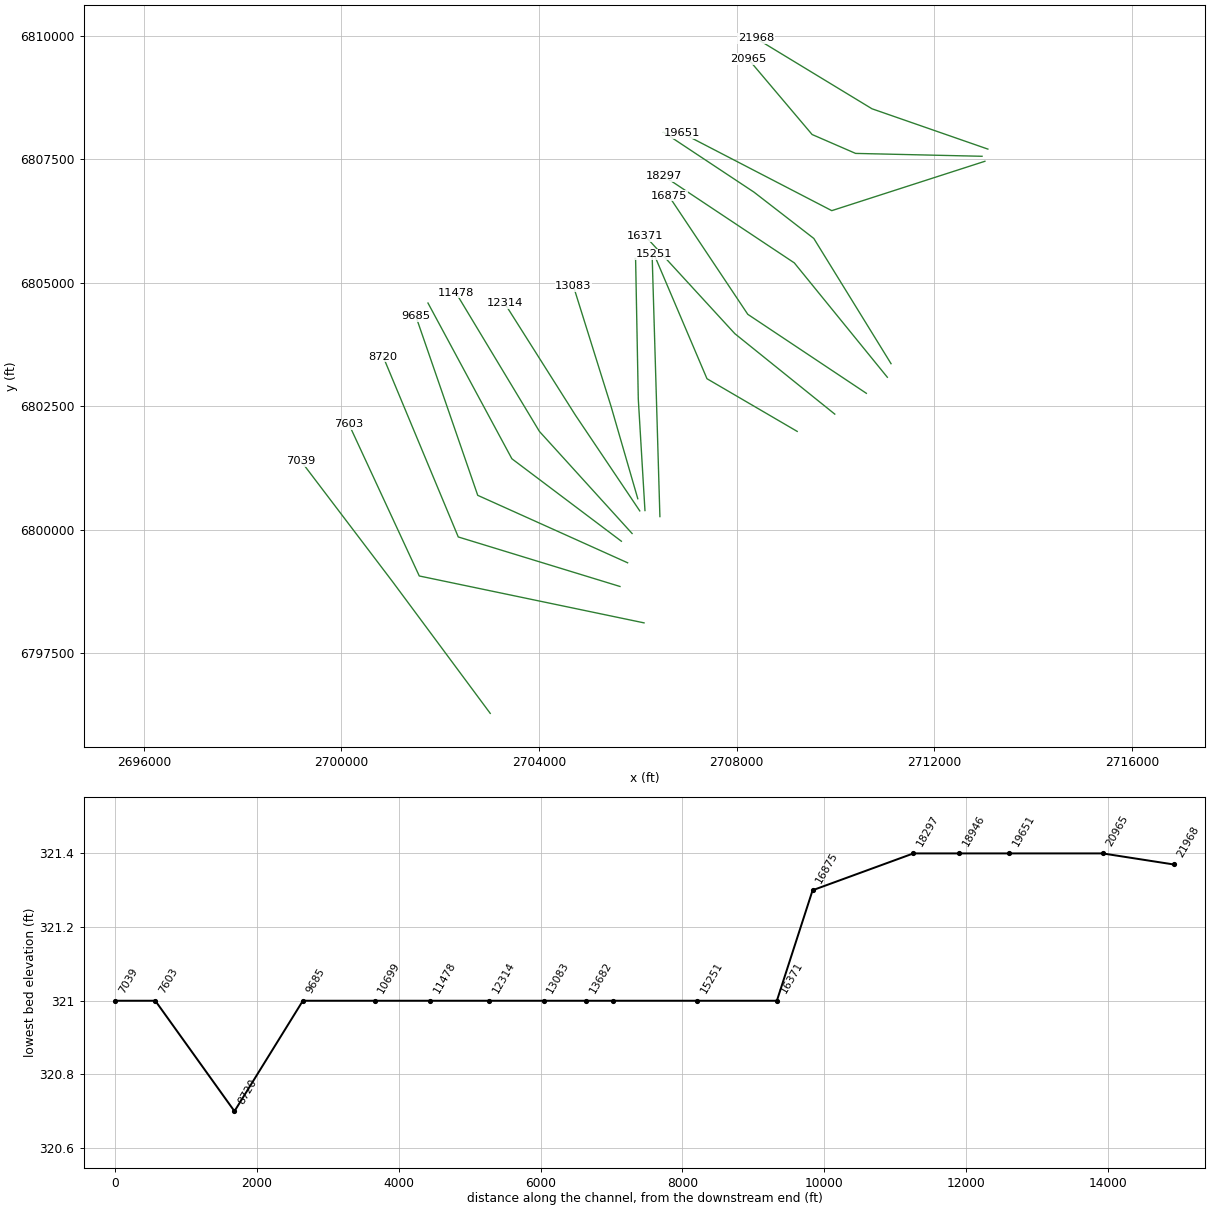
HEC-RAS study North Twin Creek.prj: North Twin Creek Base Level Engineering

--- North Twin Creek.g01 (geometry) --- (continued)

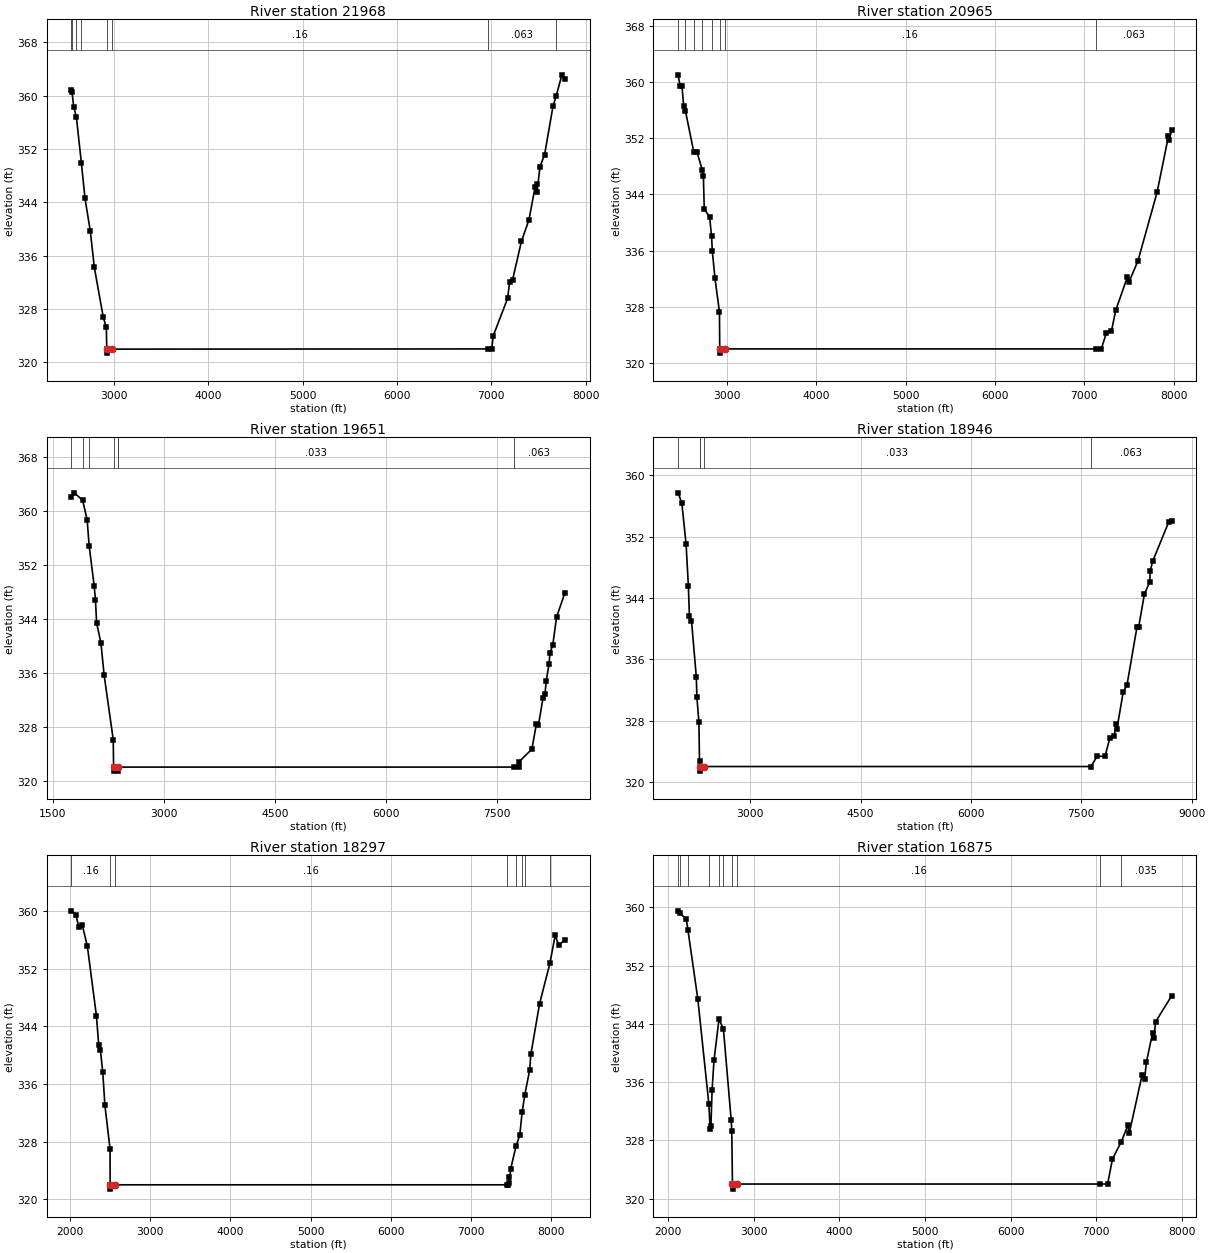
Type RM Length L Ch R = 1,21968,1003,1003,1003
BEGIN DESCRIPTION:
North Twin Creek21968.44
END DESCRIPTION:
XS GIS Cut Line= 3
      2713086.01      6807707.77      2710740.27      6808524.22
      2708391.69      6809951.24
#Sta/Elev= 30
  2549.8  360.77  2556.7  360.49  2575.6  358.31  2603.1  356.78  2655.6  349.96
  2694.6  344.58  2751.0  339.64  2793.3  334.24  2888.6  326.72  2920.4  325.24
  2925.2  321.97  2926.3  321.37  2979.1  321.97  6962.4  322.00  7005.8  322.00
  7021.2  323.95  7174.3  329.59  7195.7  332.04  7226.6  332.35  7320.3  338.13
  7401.0  341.40  7465.0  346.26  7480.5  346.70  7486.4  345.60  7517.3  349.33
  7566.0  351.14  7654.9  358.37  7687.3  359.88  7749.9  363.12  7781.7  362.54
#Mann=8,-1,0
  2549.8   0.035       0  2556.7    0.16       0  2603.1   0.063       0
  2655.6    0.16       0  2925.2   0.033       0  2979.1    0.16       0
  6962.4   0.063       0  7687.3   0.035       0
Bank Sta=2925.2,2979.1
Exp/Cntr=0.3,0.1

Type RM Length L Ch R = 1,20965,1314,1314,1314
BEGIN DESCRIPTION:
North Twin Creek20965.05
END DESCRIPTION:
XS GIS Cut Line= 4
      2712968.10      6807562.18      2710408.02      6807620.43
      2709528.00      6808002.95      2708235.88      6809532.01
#Sta/Elev= 30
  2455.6  361.01  2477.7  359.37  2497.7  359.48  2517.7  356.56  2536.5  355.91
  2631.3  349.98  2667.8  349.98  2726.4  347.41  2737.8  346.65  2747.8  341.91
  2807.8  340.77  2829.4  338.03  2837.8  335.94  2867.8  332.05  2917.8  327.24
  2920.9  322.00  2922.0  321.40  2974.8  322.00  7127.5  322.00  7189.8  322.00
  7245.8  324.24  7302.9  324.54  7352.4  327.53  7479.8  332.17  7501.8  331.59
  7600.7  334.56  7813.9  344.29  7941.3  352.29  7949.1  351.68  7977.8  353.15
#Mann=8,-1,0
  2455.6   0.035       0  2536.5   0.063       0  2631.3    0.16       0
  2726.4    0.07       0  2829.4    0.16       0  2920.9   0.033       0
  2974.8    0.16       0  7127.5   0.063       0
Bank Sta=2920.9,2974.8
Exp/Cntr=0.3,0.1

Type RM Length L Ch R = 1,19651,705,705,705
BEGIN DESCRIPTION:
North Twin Creek19651.104
END DESCRIPTION:
XS GIS Cut Line= 3
      2713026.00      6807461.00      2709926.00      6806461.00
      2706896.01      6808031.91
#Sta/Elev= 30
  1749.0  362.07  1791.0  362.70  1902.2  361.58  1962.6  358.69  1989.9  354.81
  2058.7  348.81  2074.7  346.77  2090.7  343.38  2148.3  340.44  2192.1  335.65
  2315.1  326.08  2320.1  322.00  2321.2  321.40  2373.1  321.40  2374.2  322.00
  2383.7  322.00  7726.8  322.00  7796.1  322.04  7801.8  322.82  7973.2  324.66
  8033.9  328.44  8061.7  328.25  8122.4  332.21  8150.2  332.90  8166.7  334.81
  8205.3  337.34  8216.6  338.92  8255.2  340.13  8306.7  344.27  8419.3  347.86
#Mann=7,-1,0
  1749.0   0.035       0  1902.2   0.063       0  1989.9    0.07       0
  2320.1   0.033       0  2374.2    0.07       0  2383.7   0.033       0
  7726.8   0.063       0
Bank Sta=2320.1,2374.2
Exp/Cntr=0.3,0.1

Type RM Length L Ch R = 1,18946,649,649,649
BEGIN DESCRIPTION:
North Twin Creek18946.171
END DESCRIPTION:
XS GIS Cut Line= 4
      2711125.99      6803361.01      2709562.32      6805897.81
      2708351.00      6806836.00      2706520.71      6808049.71
#Sta/Elev= 30
  2020.0  357.70  2070.2  356.36  2128.2  350.98  2159.0  345.57  2172.7  341.67
  2201.5  341.02  2266.7  333.70  2274.9  331.03  2302.1  327.77  2310.5  322.67
  2311.6  322.00  2312.7  321.40  2365.8  322.00  7630.5  322.00  7714.2  323.33
  7822.4  323.34  7888.6  325.78  7945.8  325.97  7975.9  327.51  7981.9  326.84
  8069.1  331.72  8120.2  332.63  8255.6  340.17  8278.0  340.14  8357.8  344.54
  8430.0  346.07  8436.0  347.52  8472.1  348.84  8688.7  353.91  8728.3  353.97
#Mann=5,-1,0
  2020.0    0.16       0  2310.5   0.033       0  2311.6   0.033       0
  2365.8   0.033       0  7630.5   0.063       0
Bank Sta=2311.6,2365.8
Exp/Cntr=0.3,0.1

Type RM Length L Ch R = 1,18297,1422,1422,1422
BEGIN DESCRIPTION:
North Twin Creek18297.452
END DESCRIPTION:
XS GIS Cut Line= 3
      2711050.98      6803086.02      2709167.76      6805402.76
      2706525.98      6807161.01
#Sta/Elev= 30
  2014.4  360.03  2071.9  359.51  2107.0  357.74  2149.7  358.11  2214.1  355.12
  2327.6  345.43  2355.9  341.41  2377.1  340.67  2405.9  337.70  2433.2  333.04
  2497.6  326.94  2498.6  322.00  2499.8  321.40  2552.9  322.00  7448.3  322.00
  7465.6  322.00  7474.6  323.12  7480.6  322.23  7495.6  324.17  7563.1  327.35
  7609.8  328.91  7640.1  332.13  7673.0  334.53  7733.1  337.91  7748.1  340.09
  7856.3  347.10  7985.7  352.74  8051.7  356.63  8093.7  355.32  8173.4  355.92
#Mann=8,-1,0
  2014.4    0.16       0  2498.6   0.033       0  2552.9    0.16       0
  7448.3   0.063       0  7563.1   0.035       0  7640.1   0.063       0
  7673.0   0.035       0  7985.7   0.063       0
Bank Sta=2498.6,2552.9
Exp/Cntr=0.3,0.1

Type RM Length L Ch R = 1,16875,504,504,504
BEGIN DESCRIPTION:
North Twin Creek16875.212
END DESCRIPTION:
XS GIS Cut Line= 3
      2710625.97      6802761.02      2708226.00      6804361.00
      2706626.03      6806760.96
#Sta/Elev= 30
  2115.5  359.52  2133.2  359.17  2210.1  358.45  2230.2  356.87  2345.3  347.42
  2474.1  333.05  2489.5  329.54  2498.6  329.91  2512.1  334.90  2534.6  339.00
  2592.9  344.64  2644.5  343.29  2735.9  330.73  2741.9  329.34  2750.4  322.00
  2751.6  321.30  2805.6  322.00  7051.5  322.00  7134.7  322.00  7191.8  325.45
  7292.7  327.75  7372.1  330.07  7387.1  328.94  7537.3  336.94  7567.4  336.42
  7588.4  338.75  7660.5  342.75  7675.5  342.07  7696.6  344.30  7884.3  347.87
#Mann=10,-1,0
  2115.5   0.035       0  2133.2    0.16       0  2230.2    0.12       0
  2474.1    0.16       0  2592.9    0.12       0  2644.5    0.16       0
  2750.4   0.033       0  2805.6    0.16       0  7051.5   0.063       0
  7292.7   0.035       0
Bank Sta=2750.4,2805.6
Exp/Cntr=0.3,0.1

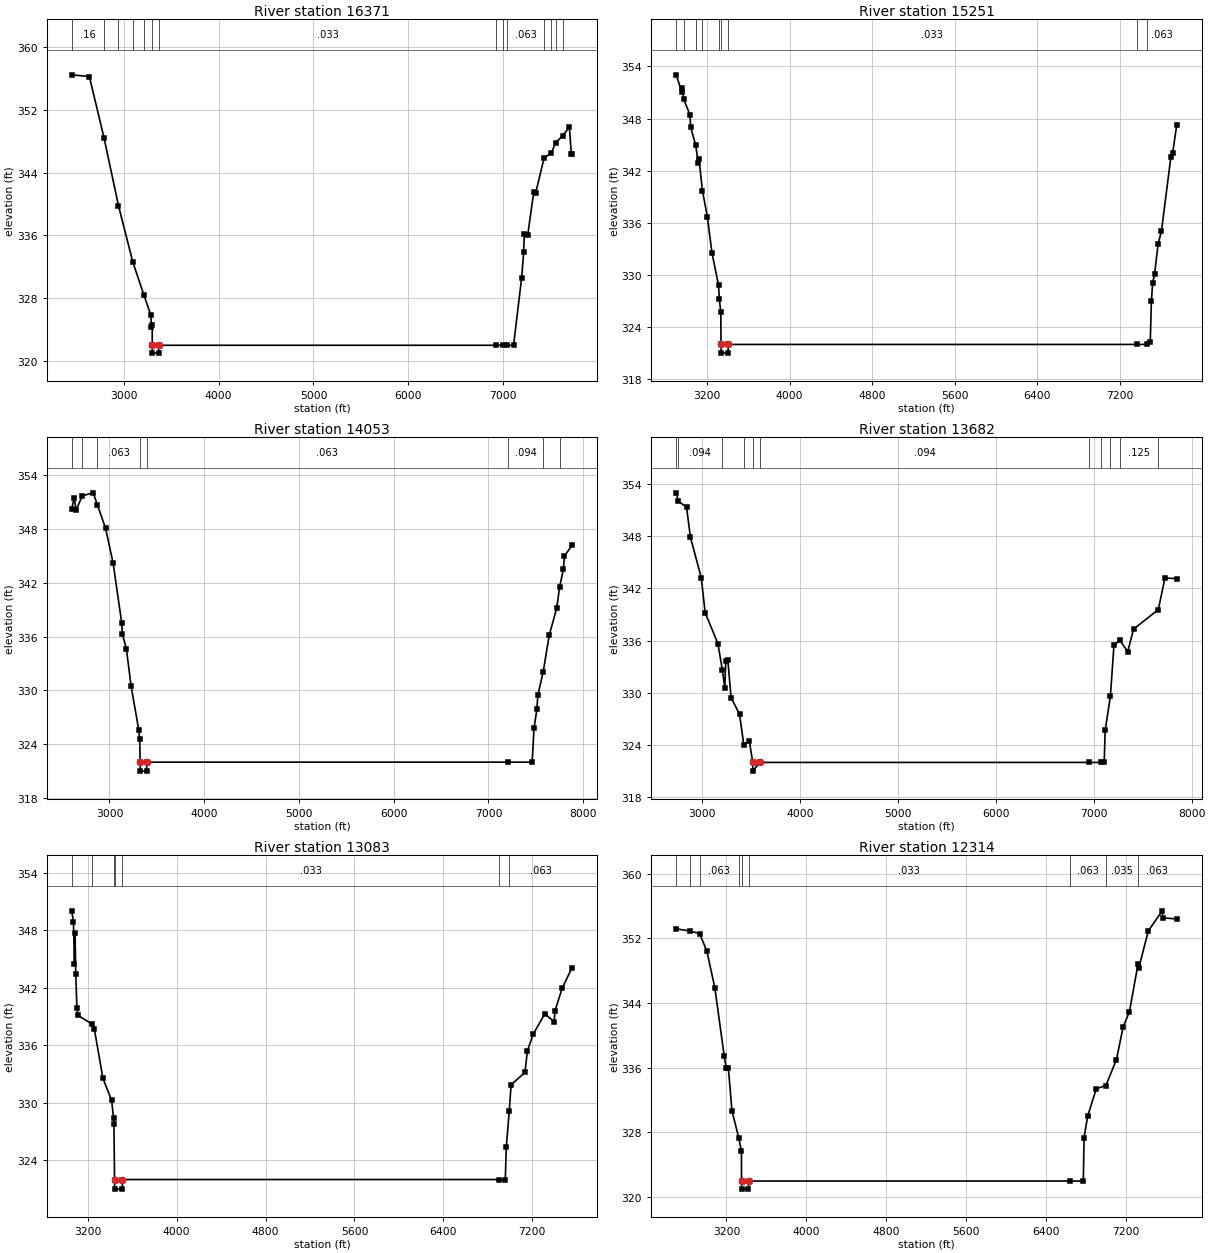
Type RM Length L Ch R = 1,16371,1120,1120,1120
BEGIN DESCRIPTION:
Mapping XS 76f9cb57
END DESCRIPTION:
XS GIS Cut Line= 3
      2709986.91      6802339.43      2707964.23      6803968.78
      2706154.57      6805940.77
#Sta/Elev= 30
  2452.1  356.44  2638.7  356.22  2793.7  348.37  2945.3  339.77  3096.9  332.58
  3213.1  328.40  3286.5  325.82  3292.9  324.39  3300.8  324.64  3301.1  322.00
  3302.6  321.00  3369.6  321.00  3371.1  322.00  6928.9  322.00  6996.3  322.00
  7038.3  322.00  7109.3  322.00  7194.4  330.59  7215.4  333.83  7222.8  336.21
  7257.9  336.00  7321.4  341.46  7343.0  341.43  7431.6  345.88  7506.2  346.45
  7552.0  347.79  7626.0  348.66  7696.9  349.80  7717.9  346.40  7725.9  346.36
#Mann=14,-1,0
  2452.1    0.16       0  2793.7    0.12       0  2945.3   0.035       0
  3096.9    0.16       0  3213.1   0.033       0  3301.1   0.033       0
  3371.1   0.033       0  6928.9   0.094       0  6996.3   0.033       0
  7038.3   0.063       0  7431.6   0.094       0  7506.2   0.125       0
  7552.0   0.094       0  7626.0   0.125       0
Bank Sta=3301.1,3371.1
Exp/Cntr=0.3,0.1

Type RM Length L Ch R = 1,15251,1198,1198,1198
BEGIN DESCRIPTION:
Mapping XS 6706fce1
END DESCRIPTION:
XS GIS Cut Line= 3
      2709226.01      6801989.56      2707399.99      6803056.28
      2706328.19      6805576.80
#Sta/Elev= 30
  2900.8  353.04  2953.1  351.07  2958.9  351.50  2972.6  350.23  3033.3  348.45
  3039.8  347.03  3088.8  344.95  3113.4  342.92  3120.9  343.33  3154.4  339.70
  3201.9  336.70  3246.5  332.57  3311.0  328.79  3317.7  327.23  3332.5  325.75
  3334.7  322.00  3336.2  321.00  3403.2  321.00  3404.7  322.00  7365.0  322.00
  7470.3  322.00  7498.3  322.29  7509.1  326.99  7521.4  329.08  7539.6  330.06
  7574.3  333.58  7606.9  335.05  7697.8  343.57  7715.6  344.08  7754.5  347.21
#Mann=9,-1,0
  2900.8   0.063       0  2972.6   0.035       0  3088.8    0.16       0
  3154.4    0.07       0  3311.0   0.033       0  3334.7   0.033       0
  3404.7   0.033       0  7365.0   0.094       0  7470.3   0.063       0
Bank Sta=3334.7,3404.7
Exp/Cntr=0.3,0.1

Type RM Length L Ch R = 1,14053,371,371,371
BEGIN DESCRIPTION:
North Twin Creek14053.431
END DESCRIPTION:
XS GIS Cut Line= 3
      2706446.86      6800263.75      2706376.00      6802661.00
      2706290.07      6805542.03
#Sta/Elev= 30
  2601.7  350.23  2629.0  351.47  2649.0  350.09  2713.4  351.68  2829.0  352.01
  2872.2  350.69  2959.1  348.07  3039.1  344.17  3129.2  337.55  3136.3  336.30
  3179.2  334.59  3229.2  330.45  3309.3  325.59  3319.3  324.62  3324.1  322.00
  3325.6  321.00  3393.0  321.00  3394.5  322.00  7203.5  322.00  7461.1  322.00
  7481.1  325.81  7510.9  327.89  7521.1  329.49  7577.3  332.04  7641.2  336.15
  7721.2  339.20  7750.0  341.48  7791.2  343.54  7801.2  344.96  7882.3  346.16
#Mann=8,-1,0
  2601.7   0.063       0  2713.4   0.094       0  2872.2   0.063       0
  3324.1   0.033       0  3394.5   0.063       0  7203.5   0.094       0
  7577.3   0.063       0  7750.0   0.125       0
Bank Sta=3324.1,3394.5
Exp/Cntr=0.3,0.1

Type RM Length L Ch R = 1,13682,599,599,599
BEGIN DESCRIPTION:
North Twin Creek13106.42
END DESCRIPTION:
XS GIS Cut Line= 3
      2706144.38      6800386.74      2706009.43      6802644.11
      2705954.82      6805491.18
#Sta/Elev= 30
  2738.6  352.99  2759.3  352.01  2843.0  351.36  2883.1  347.87  2993.3  343.25
  3033.4  339.21  3163.6  335.66  3207.9  332.68  3233.7  330.61  3243.8  333.61
  3263.8  333.83  3298.4  329.43  3384.0  327.55  3427.2  324.06  3484.2  324.46
  3519.1  322.00  3520.6  321.00  3589.5  322.00  6956.5  322.00  7076.9  322.00
  7107.3  322.00  7117.3  325.68  7170.7  329.59  7207.3  335.49  7268.6  336.02
  7347.3  334.74  7407.3  337.32  7660.2  339.57  7727.4  343.20  7847.6  343.13
#Mann=11,-1,0
  2738.6   0.063       0  2759.3   0.094       0  3207.9   0.063       0
  3427.2   0.094       0  3519.1   0.033       0  3589.5   0.094       0
  6956.5   0.094       0  7076.9   0.063       0  7170.7   0.094       0
  7268.6   0.125       0  7660.2   0.094       0
Bank Sta=3519.1,3589.5
Exp/Cntr=0.3,0.1

Type RM Length L Ch R = 1,13083,769,769,769
BEGIN DESCRIPTION:
Mapping XS 25734f83
END DESCRIPTION:
XS GIS Cut Line= 3
      2705999.22      6800625.92      2705456.54      6802501.22
      2704695.37      6804934.40
#Sta/Elev= 30
  3055.8  350.01  3071.5  348.87  3081.0  344.50  3086.2  347.65  3092.3  343.44
  3102.7  339.89  3113.1  339.11  3238.4  338.21  3258.9  337.73  3337.1  332.54
  3415.0  330.25  3432.3  328.44  3435.9  327.81  3441.3  322.00  3442.8  321.00
  3510.5  321.00  3512.0  322.00  6901.7  322.00  6956.7  322.00  6965.6  325.34
  6992.5  329.19  7009.1  331.88  7133.2  333.16  7155.8  335.42  7208.6  337.17
  7313.0  339.29  7396.8  338.43  7403.3  339.57  7468.3  341.94  7557.5  344.09
#Mann=7,-1,0
  3055.8   0.094       0  3238.4   0.063       0  3432.3   0.033       0
  3441.3   0.033       0  3512.0   0.033       0  6901.7   0.094       0
  6992.5   0.063       0
Bank Sta=3441.3,3512
Exp/Cntr=0.3,0.1

Type RM Length L Ch R = 1,12314,836,836,836
BEGIN DESCRIPTION:
North Twin Creek12313.94
END DESCRIPTION:
XS GIS Cut Line= 3
      2706039.10      6800379.26      2704735.66      6802319.55
      2703305.62      6804581.69
#Sta/Elev= 30
  2697.9  353.17  2833.9  352.91  2930.4  352.59  3003.3  350.46  3084.2  345.88
  3177.3  337.51  3198.3  335.98  3219.3  336.03  3255.3  330.69  3324.9  327.28
  3350.5  325.70  3351.3  322.00  3352.8  321.00  3420.5  321.00  3422.0  322.00
  6640.9  322.00  6776.2  322.00  6783.3  327.34  6819.8  330.04  6906.3  333.42
  7002.3  333.80  7108.0  337.02  7175.0  341.04  7238.6  342.95  7323.6  348.78
  7332.7  348.36  7426.8  352.91  7566.7  355.40  7572.6  354.53  7711.6  354.40
#Mann=9,-1,0
  2697.9   0.063       0  2833.9   0.094       0  2930.4   0.063       0
  3324.9   0.033       0  3351.3   0.033       0  3422.0   0.033       0
  6640.9   0.063       0  7002.3   0.035       0  7323.6   0.063       0
Bank Sta=3351.3,3422
Exp/Cntr=0.3,0.1

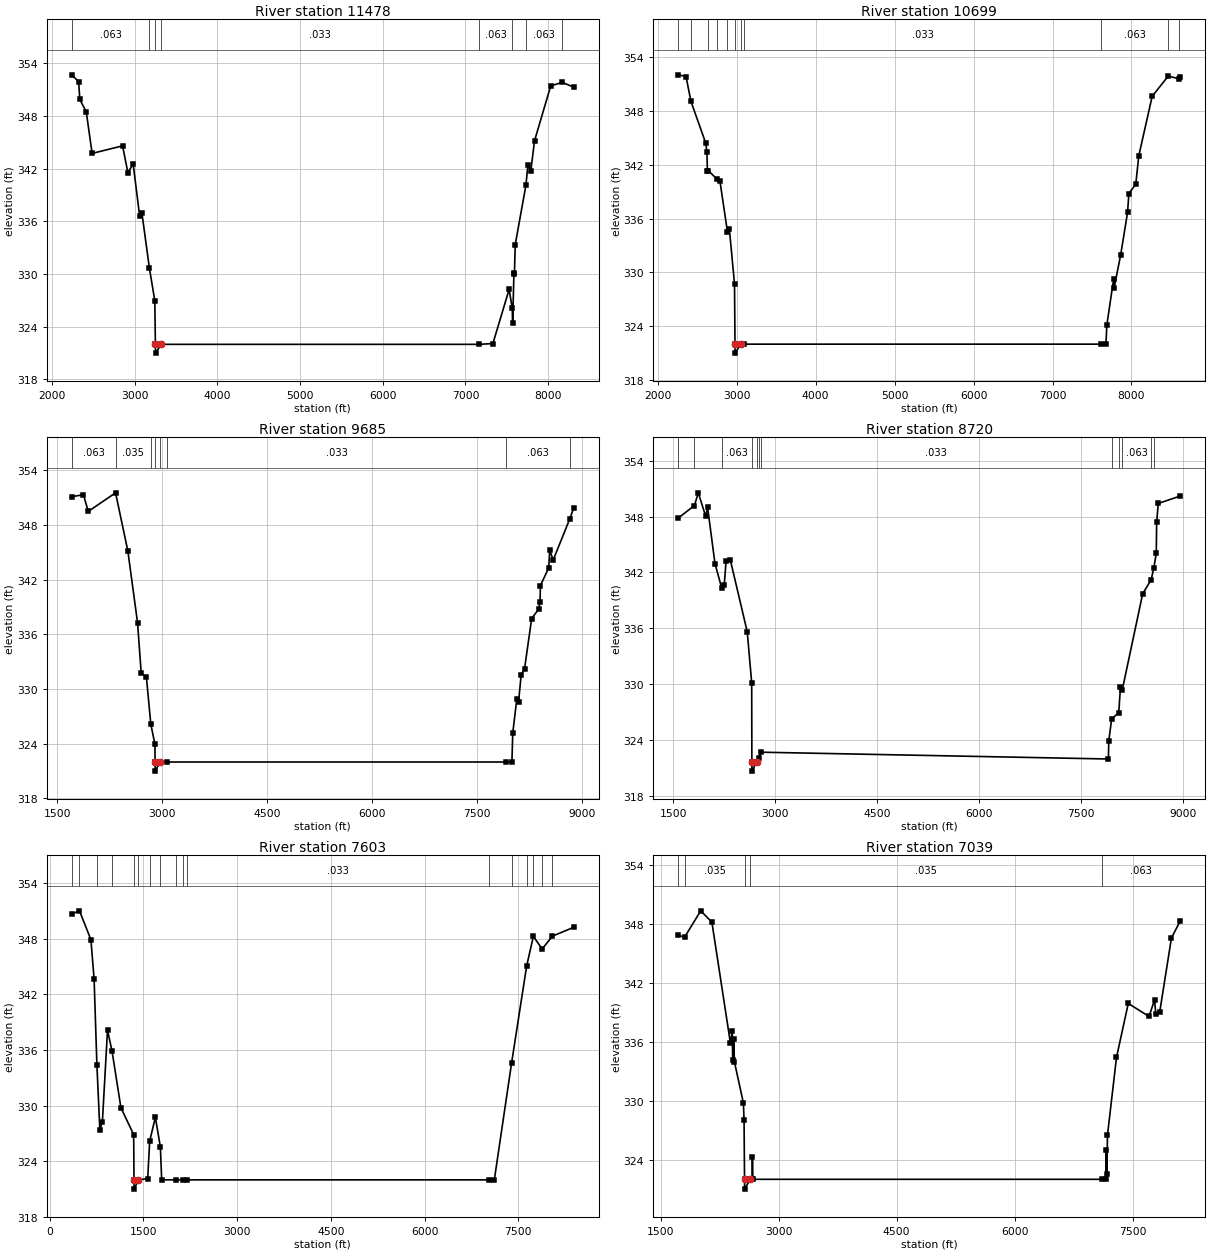
Type RM Length L Ch R = 1,11478,779,779,779
BEGIN DESCRIPTION:
North Twin Creek11477.89
END DESCRIPTION:
XS GIS Cut Line= 3
      2705884.03      6799921.16      2704007.78      6801989.16
      2702317.69      6804796.71
#Sta/Elev= 30
  2240.5  352.70  2323.7  351.91  2337.9  349.89  2415.8  348.48  2486.6  343.75
  2854.9  344.61  2918.4  341.57  2982.6  342.54  3060.4  336.66  3088.7  336.94
  3178.1  330.73  3244.2  326.97  3251.4  322.00  3252.9  321.00  3322.1  322.00
  7160.4  322.00  7331.2  322.09  7527.4  328.25  7564.8  326.15  7570.1  324.44
  7585.6  330.13  7591.5  329.99  7601.2  333.36  7731.2  340.16  7754.6  342.47
  7789.6  341.75  7834.2  345.18  8030.4  351.44  8169.0  351.84  8309.8  351.29
#Mann=8,-1,0
  2240.5   0.063       0  3178.1   0.033       0  3251.4   0.033       0
  3322.1   0.033       0  7160.4   0.063       0  7564.8   0.035       0
  7731.2   0.063       0  8169.0   0.035       0
Bank Sta=3251.4,3322.1
Exp/Cntr=0.3,0.1

Type RM Length L Ch R = 1,10699,1014,1014,1014
BEGIN DESCRIPTION:
North Twin Creek10698.72
END DESCRIPTION:
XS GIS Cut Line= 3
      2705666.98      6799764.69      2703450.40      6801435.36
      2701752.06      6804589.86
#Sta/Elev= 30
  2260.0  352.03  2358.5  351.84  2420.7  349.08  2608.3  344.41  2622.9  343.48
  2629.2  341.36  2642.6  341.34  2752.7  340.38  2787.2  340.24  2883.1  334.53
  2908.1  334.79  2972.7  328.71  2978.9  322.00  2980.4  321.00  3049.7  322.00
  3099.0  322.00  7610.5  322.00  7676.9  322.00  7687.5  324.11  7775.1  329.32
  7780.8  328.31  7862.7  331.94  7950.3  336.69  7966.6  338.79  8054.2  339.84
  8092.3  343.00  8261.9  349.63  8465.3  351.89  8599.8  351.59  8618.3  351.77
#Mann=11,-1,0
  2260.0   0.094       0  2420.7   0.063       0  2642.6   0.094       0
  2752.7   0.063       0  2883.1   0.094       0  2978.9   0.033       0
  3049.7   0.094       0  3099.0   0.033       0  7610.5   0.063       0
  8465.3   0.035       0  8599.8   0.063       0
Bank Sta=2978.9,3049.7
Exp/Cntr=0.3,0.1

Type RM Length L Ch R = 1,9685,965,965,965
BEGIN DESCRIPTION:
North Twin Creek9684.863
END DESCRIPTION:
XS GIS Cut Line= 3
      2705793.24      6799328.14      2702759.34      6800694.55
      2701504.94      6804327.06
#Sta/Elev= 30
  1710.5  351.10  1876.6  351.33  1946.0  349.49  2335.8  351.53  2511.2  345.16
  2650.1  337.27  2701.9  331.77  2776.8  331.28  2839.4  326.15  2898.0  323.95
  2900.4  322.00  2901.9  321.00  2971.3  322.00  3065.8  322.00  7917.6  322.00
  7996.4  322.00  8008.4  325.17  8065.5  328.88  8091.4  328.60  8127.9  331.52
  8176.2  332.20  8278.5  337.74  8377.3  338.76  8398.0  339.55  8403.2  341.35
  8522.7  343.31  8535.9  345.28  8585.1  344.15  8819.5  348.61  8880.9  349.91
#Mann=8,-1,0
  1710.5   0.063       0  2335.8   0.035       0  2839.4   0.033       0
  2900.4   0.033       0  2971.3   0.033       0  3065.8   0.033       0
  7917.6   0.063       0  8819.5   0.035       0
Bank Sta=2900.4,2971.3
Exp/Cntr=0.3,0.1

Type RM Length L Ch R = 1,8720,1117,1117,1117
BEGIN DESCRIPTION:
North Twin Creek8719.684
END DESCRIPTION:
XS GIS Cut Line= 3
      2705638.64      6798848.40      2702365.24      6799851.32
      2700845.11      6803502.19
#Sta/Elev= 30
  1576.4  347.83  1814.3  349.18  1871.1  350.54  1979.8  348.02  2007.4  349.02
  2116.1  342.96  2216.2  340.30  2252.3  340.65  2279.9  343.26  2342.7  343.32
  2590.4  335.64  2655.9  330.18  2658.4  321.70  2659.9  320.70  2729.3  321.70
  2766.9  322.13  2787.0  322.73  7898.0  322.00  7903.4  323.95  7946.6  326.32
  8049.6  326.94  8075.7  329.75  8102.6  329.44  8401.0  339.70  8526.7  341.23
  8563.7  342.43  8601.3  344.05  8606.8  347.36  8630.5  349.40  8954.7  350.20
#Mann=12,-1,0
  1576.4   0.063       0  1814.3   0.035       0  2216.2   0.063       0
  2658.4   0.033       0  2729.3   0.063       0  2766.9   0.035       0
  2787.0   0.033       0  7946.6   0.063       0  8049.6   0.094       0
  8102.6   0.063       0  8526.7   0.094       0  8563.7   0.063       0
Bank Sta=2658.4,2729.3
Exp/Cntr=0.3,0.1

Type RM Length L Ch R = 1,7603,564,564,564
BEGIN DESCRIPTION:
North Twin Creek7602.73
END DESCRIPTION:
XS GIS Cut Line= 3
      2706125.98      6798111.00      2701576.00      6799061.00
      2700151.02      6802135.97
#Sta/Elev= 30
   351.9  350.66   475.5  351.00   658.4  347.88   709.4  343.65   754.4  334.35
   801.4  327.39   842.2  328.29   924.0  338.13   996.8  335.87  1138.5  329.78
  1342.8  326.88  1348.1  322.00  1349.6  321.00  1419.2  322.00  1567.5  322.14
  1599.1  326.17  1690.1  328.75  1770.5  325.53  1791.2  322.00  2024.4  322.00
  2125.7  322.00  2191.2  322.00  7032.1  322.00  7116.1  322.00  7392.2  334.58
  7633.7  345.06  7741.1  348.24  7881.9  346.89  8046.1  348.27  8389.1  349.23
#Mann=17,-1,0
   351.9   0.035       0   475.5   0.063       0   754.4   0.035       0
   996.8   0.063       0  1348.1   0.033       0  1419.2   0.063       0
  1599.1   0.094       0  1770.5   0.063       0  2024.4   0.033       0
  2125.7   0.063       0  2191.2   0.033       0  7032.1    0.07       0
  7392.2   0.063       0  7633.7    0.07       0  7741.1    0.16       0
  7881.9    0.07       0  8046.1   0.063       0
Bank Sta=1348.1,1419.2
Exp/Cntr=0.3,0.1

Type RM Length L Ch R = 1,7039,1094,1094,1094
BEGIN DESCRIPTION:
North Twin Creek7039.11
END DESCRIPTION:
XS GIS Cut Line= 3
      2703012.41      6796277.83      2701040.03      6798939.10
      2699183.34      6801386.28
#Sta/Elev= 30
  1722.3  346.86  1802.5  346.65  2008.2  349.34  2150.1  348.19  2385.9  335.87
  2408.9  337.08  2415.1  334.19  2429.8  336.26  2436.0  333.99  2550.8  329.77
  2559.2  328.07  2565.3  322.00  2566.8  321.00  2636.5  322.00  2659.3  322.00
  2665.6  324.30  2672.2  322.00  7106.4  322.00  7158.5  322.00  7166.1  325.00
  7172.4  322.56  7180.7  326.52  7295.1  334.41  7444.8  339.91  7709.0  338.58
  7779.7  340.29  7794.3  338.86  7844.2  339.01  7994.0  346.58  8106.6  348.32
#Mann=5,-1,0
  1722.3   0.063       0  1802.5   0.035       0  2565.3   0.033       0
  2636.5   0.035       0  7106.4   0.063       0
Bank Sta=2565.3,2636.5
Exp/Cntr=0.3,0.1