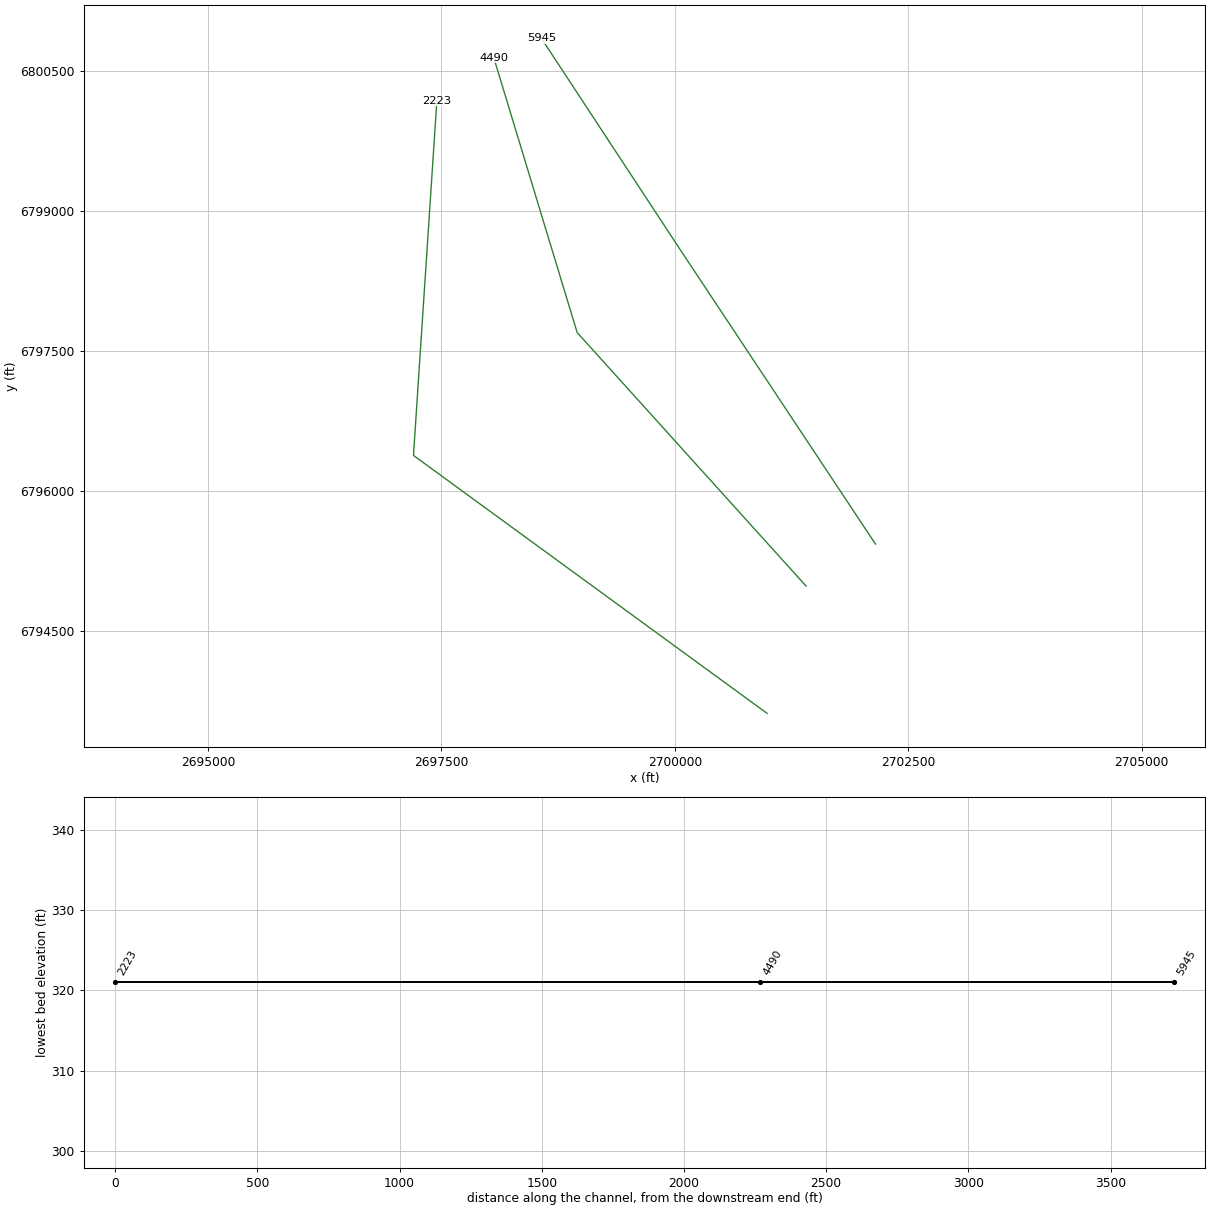
HEC-RAS study North Twin Creek.prj: North Twin Creek Base Level Engineering

--- North Twin Creek.g01 (geometry) --- (continued)

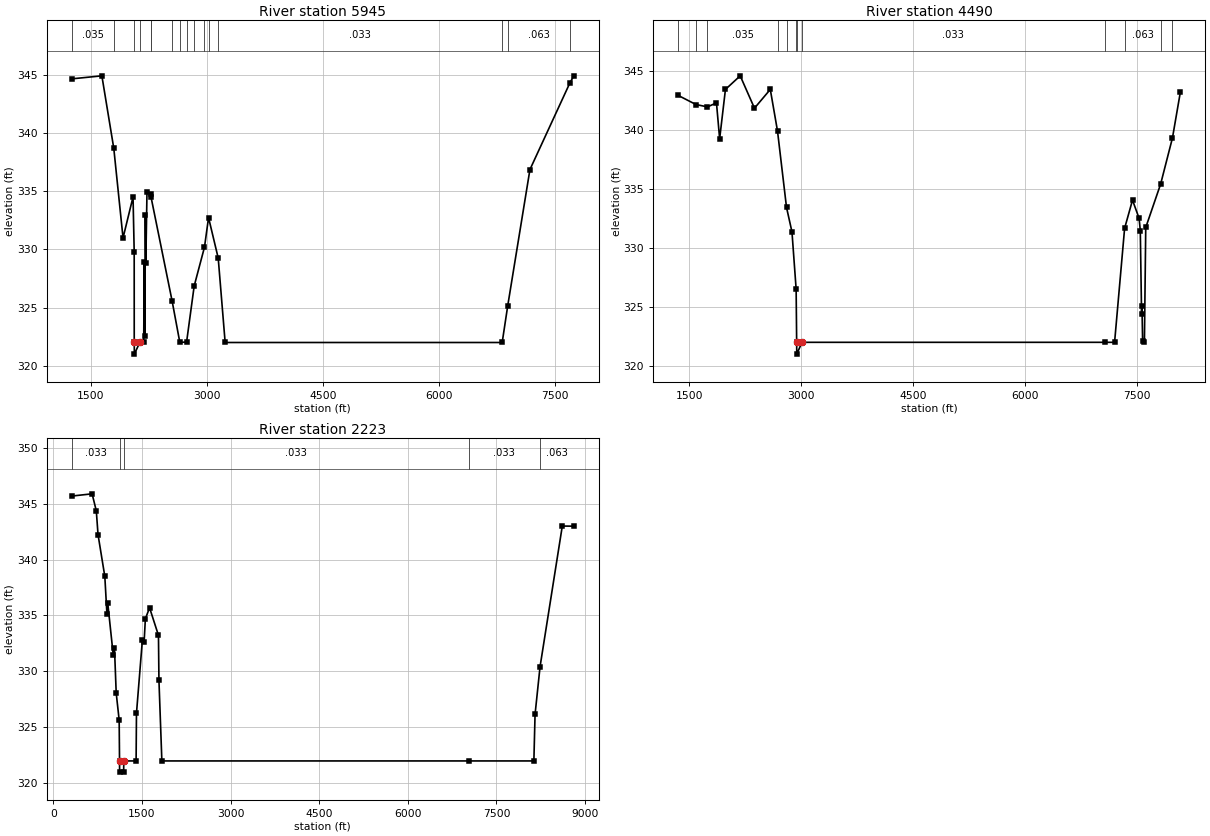
Type RM Length L Ch R = 1,5945,1455,1455,1455
BEGIN DESCRIPTION:
North Twin Creek5945.13
END DESCRIPTION:
XS GIS Cut Line= 3
      2702148.83      6795435.72      2700055.00      6798592.18
      2698570.52      6800852.50
#Sta/Elev= 30
  1254.0  344.67  1643.2  344.93  1797.4  338.69  1916.9  330.99  2046.2  334.52
  2061.2  329.78  2061.7  322.00  2063.2  321.00  2133.0  322.00  2184.3  322.00
  2190.6  328.88  2196.6  322.56  2205.6  332.96  2211.6  328.87  2226.6  334.97
  2276.7  334.73  2279.7  334.48  2551.7  325.56  2651.1  322.01  2738.7  322.04
  2836.9  326.86  2970.1  330.20  3022.6  332.74  3147.5  329.26  3237.2  322.00
  6819.4  322.00  6891.6  325.18  7178.2  336.87  7695.5  344.33  7746.0  344.93
#Mann=16,-1,0
  1254.0   0.035       0  1797.4   0.063       0  2061.7   0.033       0
  2133.0   0.063       0  2276.7   0.035       0  2279.7    0.16       0
  2551.7   0.063       0  2651.1   0.125       0  2738.7   0.063       0
  2836.9   0.125       0  2970.1   0.063       0  3022.6    0.16       0
  3147.5   0.033       0  6819.4    0.16       0  6891.6   0.063       0
  7695.5   0.035       0
Bank Sta=2061.7,2133
Exp/Cntr=0.3,0.1

Type RM Length L Ch R = 1,4490,2267,2267,2267
BEGIN DESCRIPTION:
North Twin Creek4490.28
END DESCRIPTION:
XS GIS Cut Line= 3
      2701405.10      6794985.94      2698953.47      6797701.49
      2698060.57      6800644.61
#Sta/Elev= 30
  1350.9  342.90  1588.8  342.13  1743.3  341.93  1863.7  342.27  1906.3  339.23
  1984.0  343.41  2182.0  344.56  2373.3  341.82  2585.6  343.41  2682.3  339.89
  2803.2  333.42  2876.3  331.35  2932.3  326.50  2939.2  322.00  2940.7  321.00
  3010.6  322.00  7070.8  322.00  7203.4  322.00  7337.9  331.65  7443.8  334.04
  7532.5  332.49  7548.3  331.46  7565.4  324.39  7570.6  325.08  7579.6  322.08
  7603.5  322.00  7621.4  331.72  7821.6  335.41  7979.8  339.31  8085.0  343.16
#Mann=12,-1,0
  1350.9   0.035       0  1588.8   0.063       0  1743.3   0.035       0
  2682.3   0.063       0  2803.2    0.16       0  2932.3   0.033       0
  2939.2   0.033       0  3010.6   0.033       0  7070.8    0.07       0
  7337.9   0.063       0  7821.6   0.035       0  7979.8   0.063       0
Bank Sta=2939.2,3010.6
Exp/Cntr=0.3,0.1

Type RM Length L Ch R = 1,2223,0,0,0
BEGIN DESCRIPTION:
North Twin Creek2223.283
END DESCRIPTION:
XS GIS Cut Line= 3
      2700987.89      6793622.33      2697200.19      6796385.18
      2697451.00      6800186.03
#Sta/Elev= 30
   311.7  345.67   655.9  345.87   726.9  344.35   756.3  342.22   871.0  338.49
   906.9  335.13   920.5  336.11  1013.5  331.47  1034.4  332.10  1063.7  328.07
  1113.9  325.65  1120.0  322.00  1121.5  321.00  1190.0  321.00  1191.5  322.00
  1400.5  322.00  1406.7  326.25  1507.1  332.83  1536.5  332.66  1557.3  334.70
  1628.4  335.69  1779.0  333.22  1787.0  329.21  1836.5  322.00  7030.6  322.00
  8132.6  322.00  8152.6  326.16  8237.1  330.42  8613.6  342.99  8809.1  342.98
#Mann=5,-1,0
   311.7   0.033       0  1120.0   0.033       0  1191.5   0.033       0
  7030.6   0.033       0  8237.1   0.063       0
Bank Sta=1120,1191.5
Exp/Cntr=0.3,0.1

Chan Stop Cuts=-1