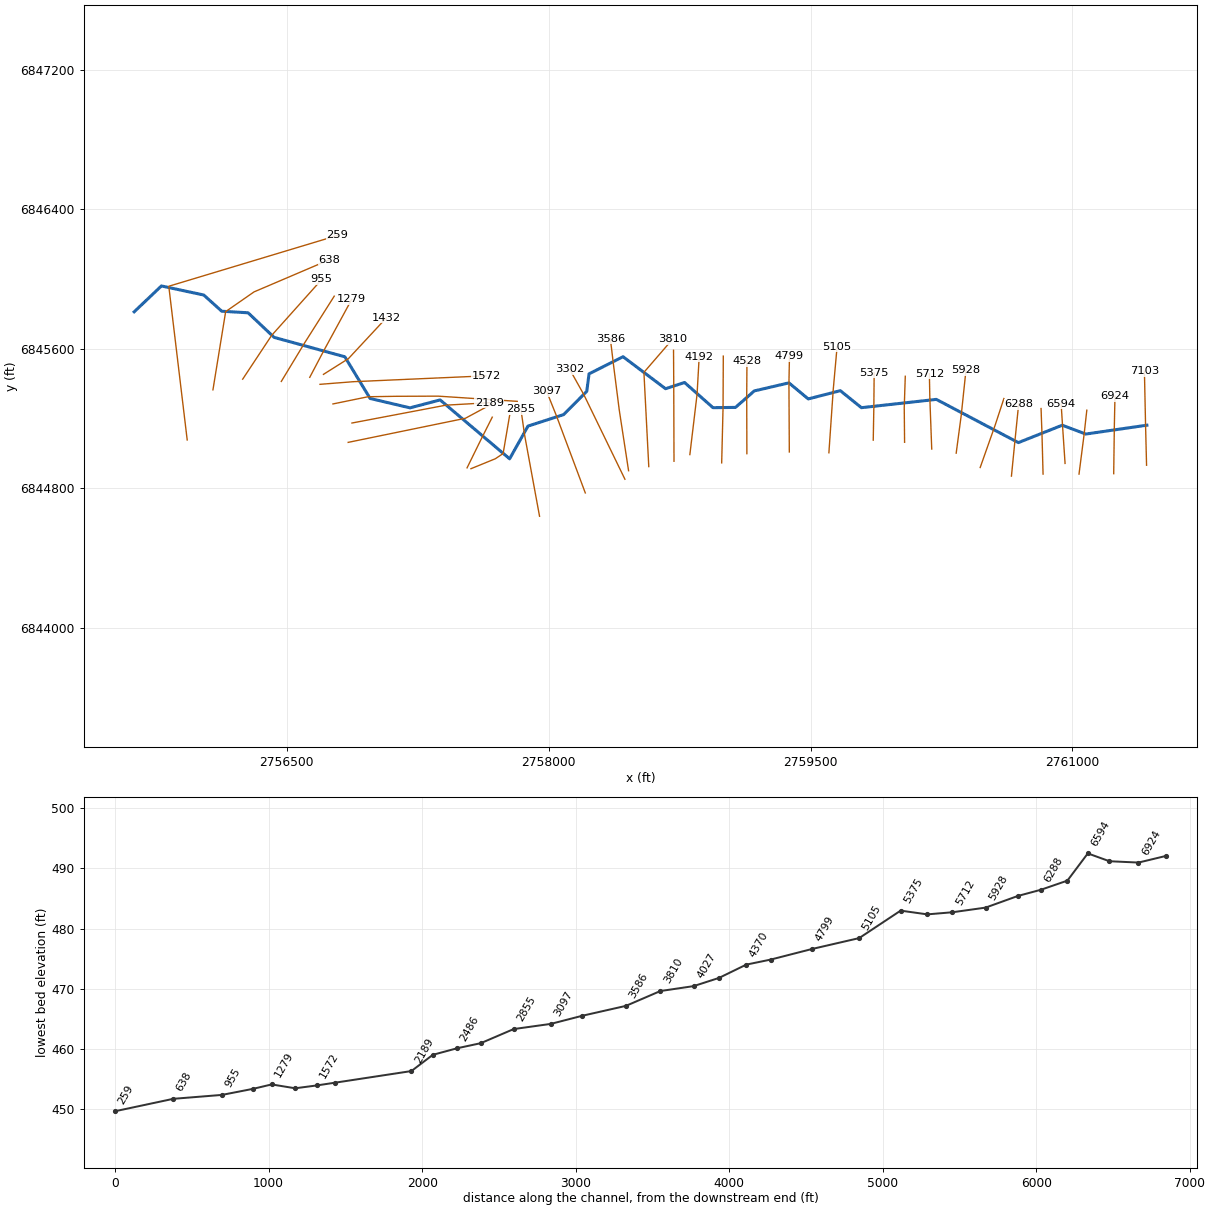
--- North Twin Creek Trib A.prj (project) ---

Proj Title=North Twin Creek Trib A Base Level Engineering
Current Plan=p01
Default Exp/Contr=0.3,0.1
English Units
Geom File=g01
Flow File=f01
Plan File=p01
BEGIN DESCRIPTION:
North Twin Creek Trib A
END DESCRIPTION:

--- North Twin Creek Trib A.p01 (plan) ---

Plan Title=Multiple Run
Short Identifier=Multiple
Geom File=g01
Flow File=f01
Subcritical Flow
K Sum by GR= 0
Std Step Tol= 0.01
Critical Tol= 0.01
Num of Std Step Trials= 20
Max Error Tol= 0.3
Flow Tol Ratio= 0.001
Split Flow NTrial= 30
Split Flow Tol= 0.02
Split Flow Ratio= 0.02
Log Output Level= 0
Friction Slope Method= 1
Unsteady Friction Slope Method= 2
Unsteady Bridges Friction Slope Method= 1
Parabolic Critical Depth
Global Vel Dist=  1 , 1 , 1
Global Log Level= 0
CheckData=True
Encroach Param= -1, 0, 0, 0
BEGIN DESCRIPTION:
Multiple Run
END DESCRIPTION:

--- North Twin Creek Trib A.f01 (steady flow) ---

Flow Title=Multiple
Number of Profiles=7
Profile Names=10-year,25-year,50-year,1pct_min,100-year,1pct_plu,500-year
River Rch & RM= North Twin Creek,Reach-1,7103
     520     699     844     508    1013    2022    1463
River Rch & RM= North Twin Creek,Reach-1,3586
     756    1037    1271     774    1544    3081    2286
River Rch & RM= North Twin Creek,Reach-1,1692
    1058    1479    1835    1130    2255    4498    3414
Boundary for River Rch & Prof#=North Twin Creek,Reach-1,1
Up Type=0
Dn Type=3
Dn Slope=0.005
Boundary for River Rch & Prof#=North Twin Creek,Reach-1,2
Up Type=0
Dn Type=3
Dn Slope=0.005
Boundary for River Rch & Prof#=North Twin Creek,Reach-1,3
Up Type=0
Dn Type=3
Dn Slope=0.005
Boundary for River Rch & Prof#=North Twin Creek,Reach-1,4
Up Type=0
Dn Type=3
Dn Slope=0.005
Boundary for River Rch & Prof#=North Twin Creek,Reach-1,5
Up Type=0
Dn Type=3
Dn Slope=0.005
Boundary for River Rch & Prof#=North Twin Creek,Reach-1,6
Up Type=0
Dn Type=3
Dn Slope=0.005
Boundary for River Rch & Prof#=North Twin Creek,Reach-1,7
Up Type=0
Dn Type=3
Dn Slope=0.005

--- North Twin Creek Trib A.g01 (geometry) ---

Geom Title=Existing Conditions

River Reach=North Twin Creek,Reach-1
Reach XY= 30
      2761426.00      6845161.00      2761076.00      6845110.19
      2760941.39      6845160.91      2760690.04      6845061.10
      2760220.11      6845309.03      2759791.16      6845261.39
      2759670.51      6845358.91      2759486.62      6845311.61
      2759376.10      6845403.67      2759177.47      6845357.44
      2759070.14      6845263.06      2758941.16      6845261.36
      2758778.29      6845405.88      2758669.28      6845370.17
      2758426.08      6845553.70      2758231.25      6845455.56
      2758218.12      6845354.88      2758085.68      6845221.76
      2757881.44      6845155.75      2757776.30      6844968.20
      2757378.29      6845305.90      2757205.95      6845260.40
      2756977.34      6845314.27      2756832.50      6845553.27
      2756427.47      6845664.54      2756278.45      6845805.53
      2756127.47      6845814.56      2756024.53      6845907.44
      2755782.03      6845959.39      2755626.00      6845811.00

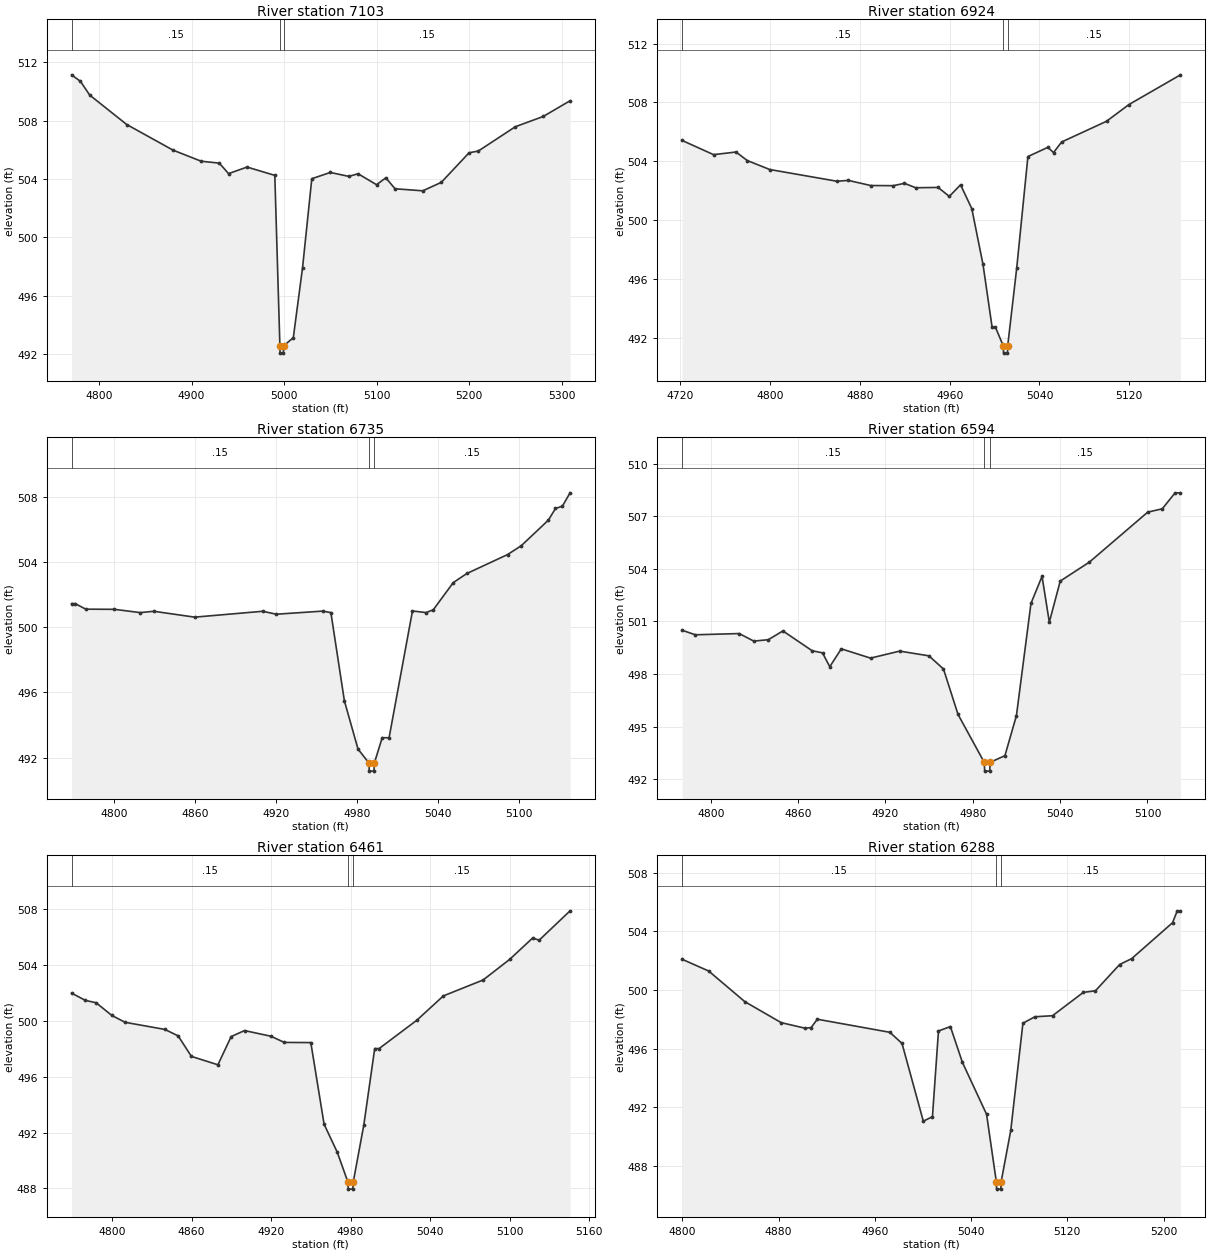
Type RM Length L Ch R = 1,7103,179,179,179
BEGIN DESCRIPTION:
North Twin Creek Trib A7102.721
END DESCRIPTION:
XS GIS Cut Line= 3
      2761424.35      6844931.37      2761418.67      6845161.00
      2761412.09      6845470.13
#Sta/Elev= 30
  4770.3  511.15  4779.9  510.70  4789.9  509.76  4829.9  507.74  4880.0  505.98
  4910.4  505.22  4930.0  505.09  4940.0  504.37  4960.0  504.82  4990.0  504.25
  4995.5  492.55  4995.7  492.05  4999.2  492.05  4999.5  492.55  5010.0  493.11
  5020.0  497.92  5030.0  504.02  5050.0  504.45  5070.0  504.18  5080.0  504.36
  5100.0  503.61  5110.0  504.08  5120.0  503.33  5150.0  503.19  5170.0  503.77
  5200.0  505.80  5210.0  505.92  5250.1  507.59  5280.1  508.29  5309.2  509.37
#Mann=3,-1,0
  4770.3    0.15       0  4995.5    0.05       0  4999.5    0.15       0
Bank Sta=4995.5,4999.5
Exp/Cntr=0.3,0.1

Type RM Length L Ch R = 1,6924,189,189,189
BEGIN DESCRIPTION:
Mapping XS e3c242c3
END DESCRIPTION:
XS GIS Cut Line= 3
      2761236.18      6844882.92      2761239.93      6845162.15
      2761243.49      6845326.86
#Sta/Elev= 30
  4721.6  505.42  4749.7  504.45  4769.7  504.63  4779.7  504.05  4799.7  503.44
  4859.7  502.64  4869.7  502.70  4889.7  502.35  4909.7  502.34  4919.7  502.50
  4929.7  502.20  4949.7  502.22  4959.7  501.61  4969.7  502.40  4979.7  500.78
  4989.7  496.98  4997.8  492.71  5000.8  492.71  5007.7  491.45  5008.0  490.95
  5011.5  490.95  5011.7  491.45  5019.7  496.72  5029.7  504.32  5047.5  504.95
  5052.5  504.59  5059.7  505.31  5099.7  506.72  5119.7  507.86  5165.6  509.88
#Mann=3,-1,0
  4721.6    0.15       0  5007.7    0.05       0  5011.7    0.15       0
Bank Sta=5007.7,5011.7
Exp/Cntr=0.3,0.1

Type RM Length L Ch R = 1,6735,141,141,141
BEGIN DESCRIPTION:
Mapping XS 56321eab
END DESCRIPTION:
XS GIS Cut Line= 3
      2761037.49      6844880.61      2761067.10      6845111.51
      2761082.16      6845246.98
#Sta/Elev= 30
  4768.5  501.45  4771.2  501.45  4779.0  501.11  4800.1  501.10  4819.3  500.90
  4829.4  500.98  4859.6  500.62  4910.0  500.98  4920.1  500.80  4954.4  500.99
  4960.5  500.90  4970.5  495.48  4980.6  492.52  4988.7  491.67  4988.9  491.17
  4992.4  491.17  4992.7  491.67  4998.5  493.22  5003.6  493.22  5020.9  501.00
  5031.0  500.90  5036.3  501.07  5051.1  502.74  5061.2  503.30  5091.3  504.46
  5101.4  505.00  5121.5  506.57  5126.8  507.29  5131.9  507.43  5137.6  508.25
#Mann=3,-1,0
  4768.5    0.15       0  4988.7    0.05       0  4992.7    0.15       0
Bank Sta=4988.7,4992.7
Exp/Cntr=0.3,0.1

Type RM Length L Ch R = 1,6594,133,133,133
BEGIN DESCRIPTION:
Mapping XS eea83e28
END DESCRIPTION:
XS GIS Cut Line= 3
      2760957.59      6844941.82      2760942.78      6845163.15
      2760935.13      6845283.48
#Sta/Elev= 30
  4780.3  500.50  4789.5  500.24  4819.6  500.31  4829.6  499.88  4839.6  499.96
  4849.6  500.46  4869.7  499.33  4876.8  499.21  4881.8  498.42  4889.7  499.44
  4909.8  498.91  4929.8  499.31  4949.9  499.04  4959.9  498.29  4969.9  495.70
  4987.9  492.97  4988.2  492.47  4991.7  492.47  4991.9  492.97  5002.1  493.35
  5010.0  495.63  5020.0  502.03  5027.6  503.57  5032.6  500.96  5040.1  503.30
  5060.1  504.38  5100.2  507.23  5110.2  507.42  5119.0  508.33  5122.7  508.33
#Mann=3,-1,0
  4780.3    0.15       0  4987.9    0.05       0  4991.9    0.15       0
Bank Sta=4987.9,4991.9
Exp/Cntr=0.3,0.1

Type RM Length L Ch R = 1,6461,173,173,173
BEGIN DESCRIPTION:
Mapping XS 702464a9
END DESCRIPTION:
XS GIS Cut Line= 3
      2760831.58      6844880.60      2760825.32      6845112.48
      2760820.05      6845256.52
#Sta/Elev= 30
  4769.5  501.98  4779.9  501.46  4788.0  501.29  4799.9  500.38  4809.9  499.89
  4839.9  499.38  4849.9  498.92  4859.9  497.45  4879.9  496.85  4889.9  498.87
  4900.0  499.30  4920.0  498.89  4930.0  498.45  4950.0  498.44  4960.0  492.60
  4970.0  490.58  4978.0  488.45  4978.2  487.95  4981.7  487.95  4982.0  488.45
  4990.0  492.55  4998.2  498.01  5001.5  498.01  5030.0  500.04  5050.0  501.78
  5080.0  502.92  5100.1  504.40  5117.3  505.92  5122.3  505.77  5145.6  507.87
#Mann=3,-1,0
  4769.5    0.15       0  4978.0    0.05       0  4982.0    0.15       0
Bank Sta=4978,4982
Exp/Cntr=0.3,0.1

Type RM Length L Ch R = 1,6288,149,149,149
BEGIN DESCRIPTION:
Mapping XS 157f428a
END DESCRIPTION:
XS GIS Cut Line= 3
      2760650.45      6844869.02      2760670.48      6845071.23
      2760691.79      6845281.35
#Sta/Elev= 30
  4799.7  502.10  4821.8  501.30  4851.9  499.21  4882.1  497.78  4901.9  497.40
  4907.0  497.44  4912.2  498.01  4972.5  497.12  4982.6  496.36  5000.3  491.06
  5007.9  491.37  5012.9  497.21  5022.8  497.51  5032.8  495.07  5052.9  491.53
  5061.0  486.93  5061.2  486.43  5064.7  486.43  5065.0  486.93  5073.0  490.43
  5083.1  497.74  5093.1  498.18  5107.7  498.25  5133.3  499.84  5143.4  499.95
  5163.5  501.74  5173.5  502.14  5207.5  504.59  5211.4  505.40  5214.1  505.40
#Mann=3,-1,0
  4799.7    0.15       0  5061.0    0.05       0  5065.0    0.15       0
Bank Sta=5061,5065
Exp/Cntr=0.3,0.1

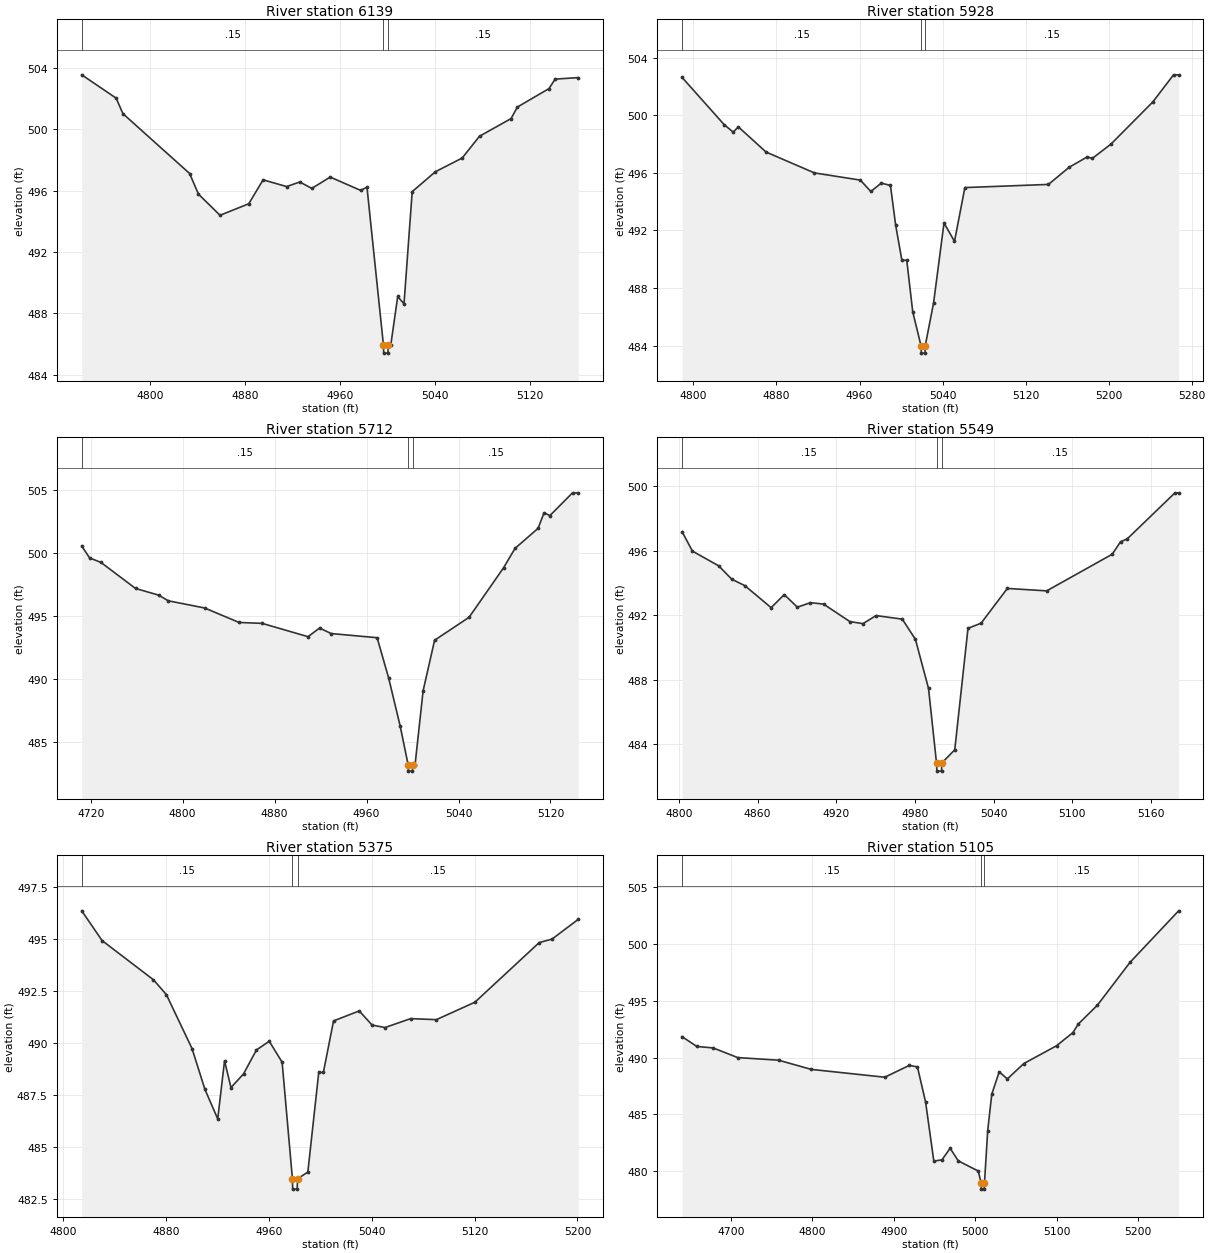
Type RM Length L Ch R = 1,6139,211,211,211
BEGIN DESCRIPTION:
Mapping XS f825e005
END DESCRIPTION:
XS GIS Cut Line= 3
      2760471.49      6844918.27      2760558.05      6845163.74
      2760607.27      6845313.90
#Sta/Elev= 30
  4742.7  503.54  4771.7  502.02  4777.4  501.01  4833.6  497.11  4841.0  495.77
  4859.2  494.39  4883.4  495.14  4895.5  496.70  4915.3  496.26  4926.4  496.56
  4936.5  496.14  4952.0  496.88  4977.7  496.01  4983.0  496.22  4996.9  485.91
  4997.1  485.41  5000.6  485.41  5000.9  485.91  5003.0  485.91  5008.9  489.10
  5014.2  488.62  5021.1  495.93  5040.7  497.23  5063.2  498.12  5077.8  499.54
  5104.4  500.69  5109.7  501.44  5136.3  502.64  5141.5  503.26  5161.0  503.36
#Mann=3,-1,0
  4742.7    0.15       0  4996.9    0.05       0  5000.9    0.15       0
Bank Sta=4996.9,5000.9
Exp/Cntr=0.3,0.1

Type RM Length L Ch R = 1,5928,216,216,216
BEGIN DESCRIPTION:
Mapping XS fb6ebc75
END DESCRIPTION:
XS GIS Cut Line= 3
      2760334.04      6845000.76      2760362.58      6845215.32
      2760390.00      6845475.74
#Sta/Elev= 30
  4789.1  502.64  4829.7  499.35  4838.3  498.84  4843.3  499.20  4870.0  497.45
  4916.6  496.00  4960.8  495.50  4970.9  494.71  4981.0  495.29  4989.8  495.13
  4994.8  492.38  5000.8  489.93  5005.5  489.93  5011.3  486.33  5019.3  483.97
  5019.6  483.47  5023.1  483.47  5023.3  483.97  5031.4  486.98  5041.4  492.52
  5051.5  491.24  5061.5  494.98  5142.0  495.20  5162.1  496.40  5179.3  497.11
  5184.3  497.01  5202.3  498.01  5242.5  500.93  5262.5  502.82  5267.4  502.82
#Mann=3,-1,0
  4789.1    0.15       0  5019.3    0.05       0  5023.3    0.15       0
Bank Sta=5019.3,5023.3
Exp/Cntr=0.3,0.1

Type RM Length L Ch R = 1,5712,163,163,163
BEGIN DESCRIPTION:
Mapping XS 73c84bd7
END DESCRIPTION:
XS GIS Cut Line= 3
      2760193.92      6845024.19      2760183.17      6845313.98
      2760180.43      6845455.97
#Sta/Elev= 30
  4712.2  500.57  4719.0  499.63  4729.0  499.26  4759.0  497.20  4779.1  496.67
  4787.5  496.22  4819.1  495.65  4849.1  494.50  4869.1  494.43  4909.1  493.37
  4919.1  494.06  4929.2  493.62  4969.2  493.29  4979.2  490.10  4989.2  486.30
  4996.2  483.20  4996.4  482.70  4999.9  482.70  5000.2  483.20  5002.2  483.20
  5009.2  489.07  5019.2  493.09  5049.2  494.91  5079.2  498.84  5089.2  500.38
  5109.2  501.97  5114.5  503.21  5119.5  502.98  5139.2  504.79  5144.2  504.79
#Mann=3,-1,0
  4712.2    0.15       0  4996.2    0.05       0  5000.2    0.15       0
Bank Sta=4996.2,5000.2
Exp/Cntr=0.3,0.1

Type RM Length L Ch R = 1,5549,174,174,174
BEGIN DESCRIPTION:
Mapping XS 4524139e
END DESCRIPTION:
XS GIS Cut Line= 3
      2760038.44      6845063.07      2760036.51      6845262.19
      2760042.41      6845441.56
#Sta/Elev= 30
  4802.5  497.17  4810.4  495.97  4830.4  495.06  4840.4  494.23  4850.4  493.83
  4870.4  492.47  4880.4  493.28  4890.4  492.50  4900.4  492.78  4910.4  492.69
  4930.4  491.61  4940.4  491.48  4950.4  491.98  4970.4  491.76  4980.4  490.51
  4990.4  487.47  4996.5  482.85  4996.8  482.35  5000.3  482.35  5000.5  482.85
  5010.4  483.67  5020.5  491.19  5030.5  491.51  5050.5  493.66  5080.5  493.51
  5130.5  495.78  5136.8  496.55  5141.8  496.72  5178.3  499.58  5181.1  499.58
#Mann=3,-1,0
  4802.5    0.15       0  4996.5    0.05       0  5000.5    0.15       0
Bank Sta=4996.5,5000.5
Exp/Cntr=0.3,0.1

Type RM Length L Ch R = 1,5375,270,270,270
BEGIN DESCRIPTION:
Mapping XS e573b0ae
END DESCRIPTION:
XS GIS Cut Line= 3
      2759858.93      6845075.17      2759862.42      6845263.13
      2759864.19      6845461.43
#Sta/Elev= 30
  4814.3  496.37  4830.1  494.94  4870.1  493.05  4880.1  492.34  4900.1  489.74
  4910.1  487.78  4920.1  486.35  4925.4  489.15  4930.4  487.86  4940.2  488.52
  4950.2  489.67  4960.2  490.09  4970.2  489.08  4978.2  483.47  4978.4  482.97
  4981.9  482.97  4982.2  483.47  4990.2  483.79  4998.7  488.59  5002.3  488.59
  5010.2  491.07  5030.2  491.55  5040.2  490.87  5050.2  490.75  5070.2  491.18
  5090.2  491.13  5120.2  491.97  5170.2  494.84  5180.2  495.01  5200.6  495.96
#Mann=3,-1,0
  4814.3    0.15       0  4978.2    0.05       0  4982.2    0.15       0
Bank Sta=4978.2,4982.2
Exp/Cntr=0.3,0.1

Type RM Length L Ch R = 1,5105,306,306,306
BEGIN DESCRIPTION:
Mapping XS 49b83ec5
END DESCRIPTION:
XS GIS Cut Line= 3
      2759604.95      6845002.97      2759629.89      6845365.52
      2759651.82      6845610.23
#Sta/Elev= 30
  4640.3  491.84  4658.4  490.98  4678.4  490.85  4708.5  490.00  4758.6  489.77
  4798.7  488.96  4888.9  488.27  4919.0  489.31  4929.0  489.18  4939.0  486.08
  4949.1  480.88  4959.1  480.99  4969.1  482.01  4979.1  480.90  5003.7  480.00
  5007.2  478.91  5007.5  478.41  5011.0  478.41  5011.2  478.91  5015.2  483.57
  5020.2  486.78  5029.3  488.74  5039.3  488.12  5059.4  489.47  5099.6  491.04
  5119.7  492.20  5126.4  492.96  5149.8  494.62  5189.9  498.40  5249.4  502.93
#Mann=3,-1,0
  4640.3    0.15       0  5007.2    0.05       0  5011.2    0.15       0
Bank Sta=5007.2,5011.2
Exp/Cntr=0.3,0.1

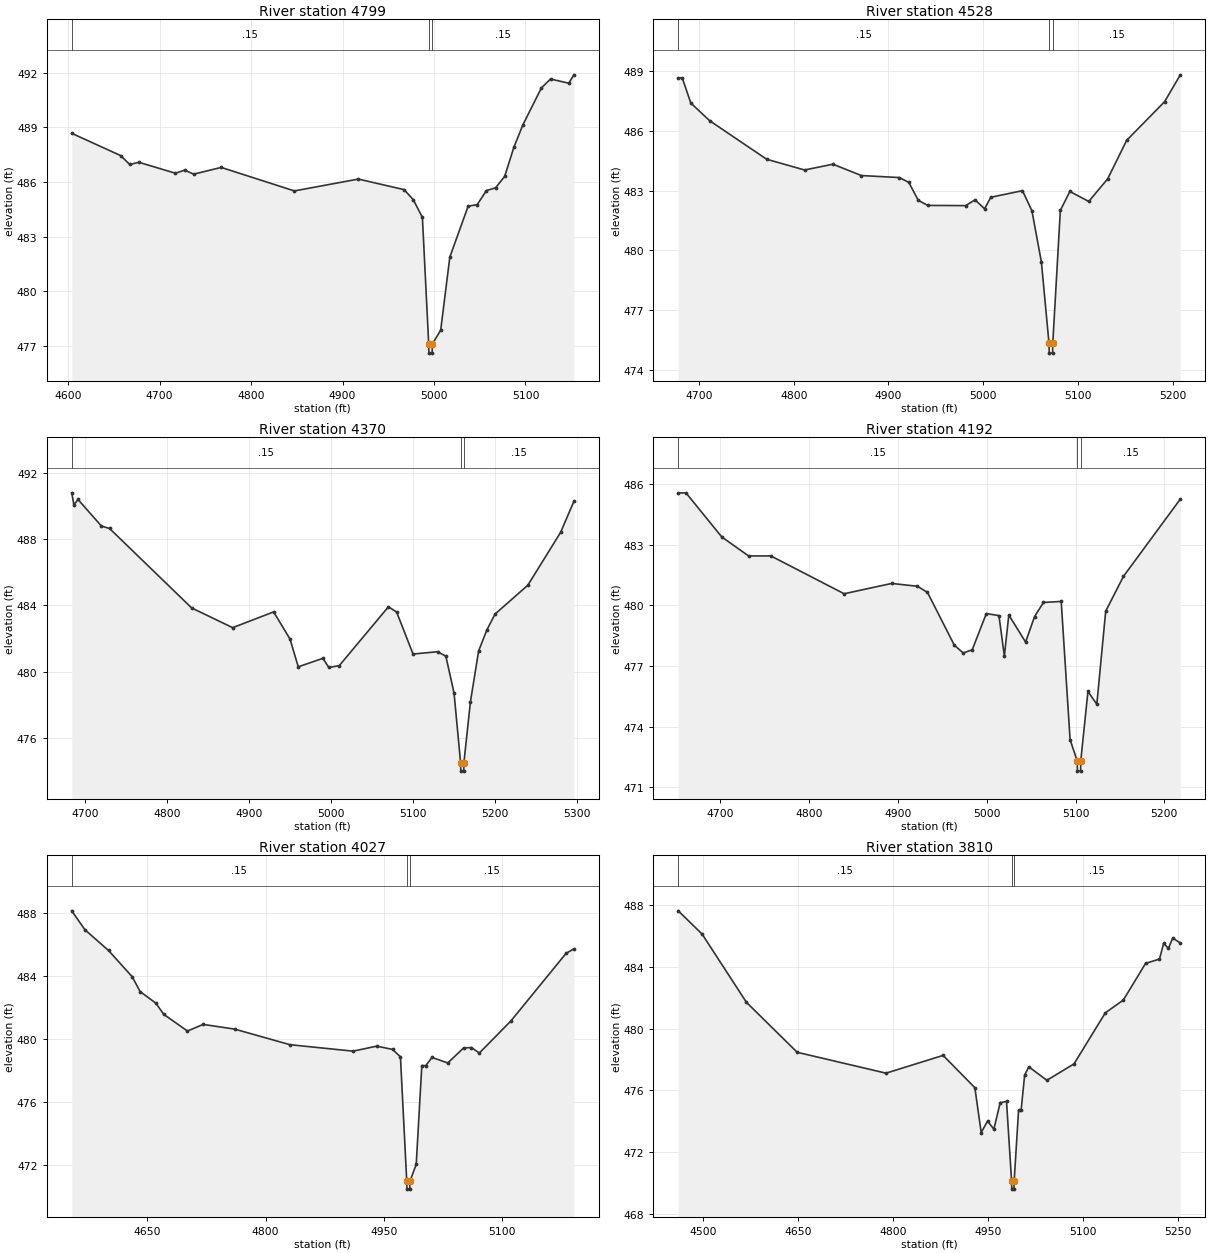
Type RM Length L Ch R = 1,4799,271,271,271
BEGIN DESCRIPTION:
Mapping XS 381fa5cf
END DESCRIPTION:
XS GIS Cut Line= 3
      2759378.27      6845007.58      2759376.10      6845403.67
      2759379.18      6845556.54
#Sta/Elev= 30
  4603.9  488.67  4657.3  487.45  4667.3  486.96  4677.3  487.08  4717.3  486.48
  4727.3  486.65  4737.3  486.43  4767.3  486.80  4847.3  485.51  4917.3  486.16
  4967.3  485.58  4977.3  485.03  4987.3  484.06  4994.2  477.11  4994.4  476.61
  4997.9  476.61  4998.2  477.11  5007.3  477.87  5017.3  481.88  5037.3  484.67
  5047.3  484.76  5057.3  485.53  5067.3  485.68  5077.3  486.31  5087.3  487.90
  5097.3  489.15  5117.4  491.16  5127.4  491.65  5147.4  491.42  5152.9  491.88
#Mann=3,-1,0
  4603.9    0.15       0  4994.2    0.05       0  4998.2    0.15       0
Bank Sta=4994.2,4998.2
Exp/Cntr=0.3,0.1

Type RM Length L Ch R = 1,4528,158,158,158
BEGIN DESCRIPTION:
Mapping XS c845a024
END DESCRIPTION:
XS GIS Cut Line= 3
      2759135.22      6844997.66      2759134.28      6845329.18
      2759135.71      6845527.56
#Sta/Elev= 30
  4678.1  488.67  4682.3  488.67  4691.4  487.40  4711.4  486.51  4771.4  484.58
  4811.4  484.04  4841.4  484.33  4871.4  483.76  4911.4  483.66  4921.4  483.42
  4931.4  482.52  4941.4  482.26  4981.4  482.25  4991.4  482.54  5001.4  482.09
  5008.0  482.67  5041.4  483.00  5051.4  481.99  5061.4  479.41  5069.4  475.34
  5069.7  474.84  5073.2  474.84  5073.4  475.34  5081.4  482.01  5091.4  482.96
  5111.4  482.46  5131.4  483.60  5151.4  485.53  5191.4  487.47  5208.0  488.82
#Mann=3,-1,0
  4678.1    0.15       0  5069.4    0.05       0  5073.4    0.15       0
Bank Sta=5069.4,5073.4
Exp/Cntr=0.3,0.1

Type RM Length L Ch R = 1,4370,178,178,178
BEGIN DESCRIPTION:
Mapping XS 9922b354
END DESCRIPTION:
XS GIS Cut Line= 3
      2758990.90      6844944.87      2758998.71      6845260.58
      2759000.17      6845557.07
#Sta/Elev= 30
  4684.2  490.79  4686.8  490.06  4691.8  490.39  4720.3  488.79  4730.3  488.64
  4830.4  483.85  4880.4  482.66  4930.4  483.61  4950.4  481.97  4960.4  480.30
  4990.4  480.81  4997.7  480.26  5010.4  480.37  5070.4  483.92  5080.4  483.60
  5100.4  481.07  5130.4  481.21  5140.4  480.94  5150.4  478.72  5158.4  474.51
  5158.7  474.01  5162.2  474.01  5162.4  474.51  5170.4  478.20  5180.4  481.26
  5190.4  482.52  5200.4  483.48  5240.4  485.22  5280.4  488.41  5296.5  490.27
#Mann=3,-1,0
  4684.2    0.15       0  5158.4    0.05       0  5162.4    0.15       0
Bank Sta=5158.4,5162.4
Exp/Cntr=0.3,0.1

Type RM Length L Ch R = 1,4192,165,165,165
BEGIN DESCRIPTION:
Mapping XS 59ae5509
END DESCRIPTION:
XS GIS Cut Line= 3
      2758808.67      6844992.38      2758849.83      6845337.63
      2758862.17      6845554.88
#Sta/Elev= 30
  4652.7  485.55  4661.4  485.56  4701.7  483.38  4731.9  482.44  4757.0  482.44
  4839.5  480.57  4893.0  481.08  4922.0  480.94  4933.3  480.64  4963.5  478.03
  4973.6  477.64  4983.7  477.80  4999.6  479.59  5013.8  479.49  5019.9  477.49
  5024.9  479.52  5043.8  478.18  5053.9  479.44  5063.9  480.14  5083.9  480.19
  5093.9  473.36  5101.9  472.30  5102.2  471.80  5105.7  471.80  5105.9  472.30
  5114.0  475.74  5124.0  475.11  5134.0  479.71  5154.0  481.43  5218.0  485.25
#Mann=3,-1,0
  4652.7    0.15       0  5101.9    0.05       0  5105.9    0.15       0
Bank Sta=5101.9,5105.9
Exp/Cntr=0.3,0.1

Type RM Length L Ch R = 1,4027,217,217,217
BEGIN DESCRIPTION:
Mapping XS 5fdb9300
END DESCRIPTION:
XS GIS Cut Line= 3
      2758717.81      6844954.38      2758716.32      6845400.07
      2758715.15      6845590.77
#Sta/Elev= 30
  4554.3  488.13  4570.9  486.93  4600.9  485.61  4630.9  483.94  4640.9  483.00
  4660.9  482.26  4670.9  481.55  4700.9  480.49  4720.9  480.91  4760.9  480.61
  4830.9  479.62  4910.9  479.21  4940.9  479.53  4960.9  479.32  4970.9  478.85
  4978.9  470.94  4979.2  470.44  4982.7  470.44  4982.9  470.94  4990.9  472.01
  4998.0  478.29  5003.0  478.29  5010.9  478.81  5030.9  478.46  5050.9  479.41
  5060.9  479.44  5070.9  479.09  5110.9  481.13  5180.9  485.43  5190.7  485.71
#Mann=3,-1,0
  4554.3    0.15       0  4978.9    0.05       0  4982.9    0.15       0
Bank Sta=4978.9,4982.9
Exp/Cntr=0.3,0.1

Type RM Length L Ch R = 1,3810,224,224,224
BEGIN DESCRIPTION:
Mapping XS 5abaec0e
END DESCRIPTION:
XS GIS Cut Line= 3
      2758573.35      6844923.47      2758545.48      6845463.99
      2758709.73      6845654.13
#Sta/Elev= 30
  4461.3  487.62  4498.9  486.12  4569.0  481.70  4649.1  478.47  4789.3  477.12
  4879.4  478.27  4929.5  476.18  4939.5  473.28  4949.5  474.02  4959.5  473.50
  4969.5  475.21  4979.5  475.29  4987.5  470.12  4987.8  469.62  4991.3  469.62
  4991.5  470.12  4998.5  474.72  5002.5  474.72  5008.1  477.00  5014.7  477.53
  5043.2  476.66  5086.0  477.72  5135.4  481.02  5163.9  481.85  5199.0  484.22
  5220.9  484.50  5227.5  485.51  5235.1  485.20  5241.8  485.86  5253.8  485.54
#Mann=3,-1,0
  4461.3    0.15       0  4987.5    0.05       0  4991.5    0.15       0
Bank Sta=4987.5,4991.5
Exp/Cntr=0.3,0.1

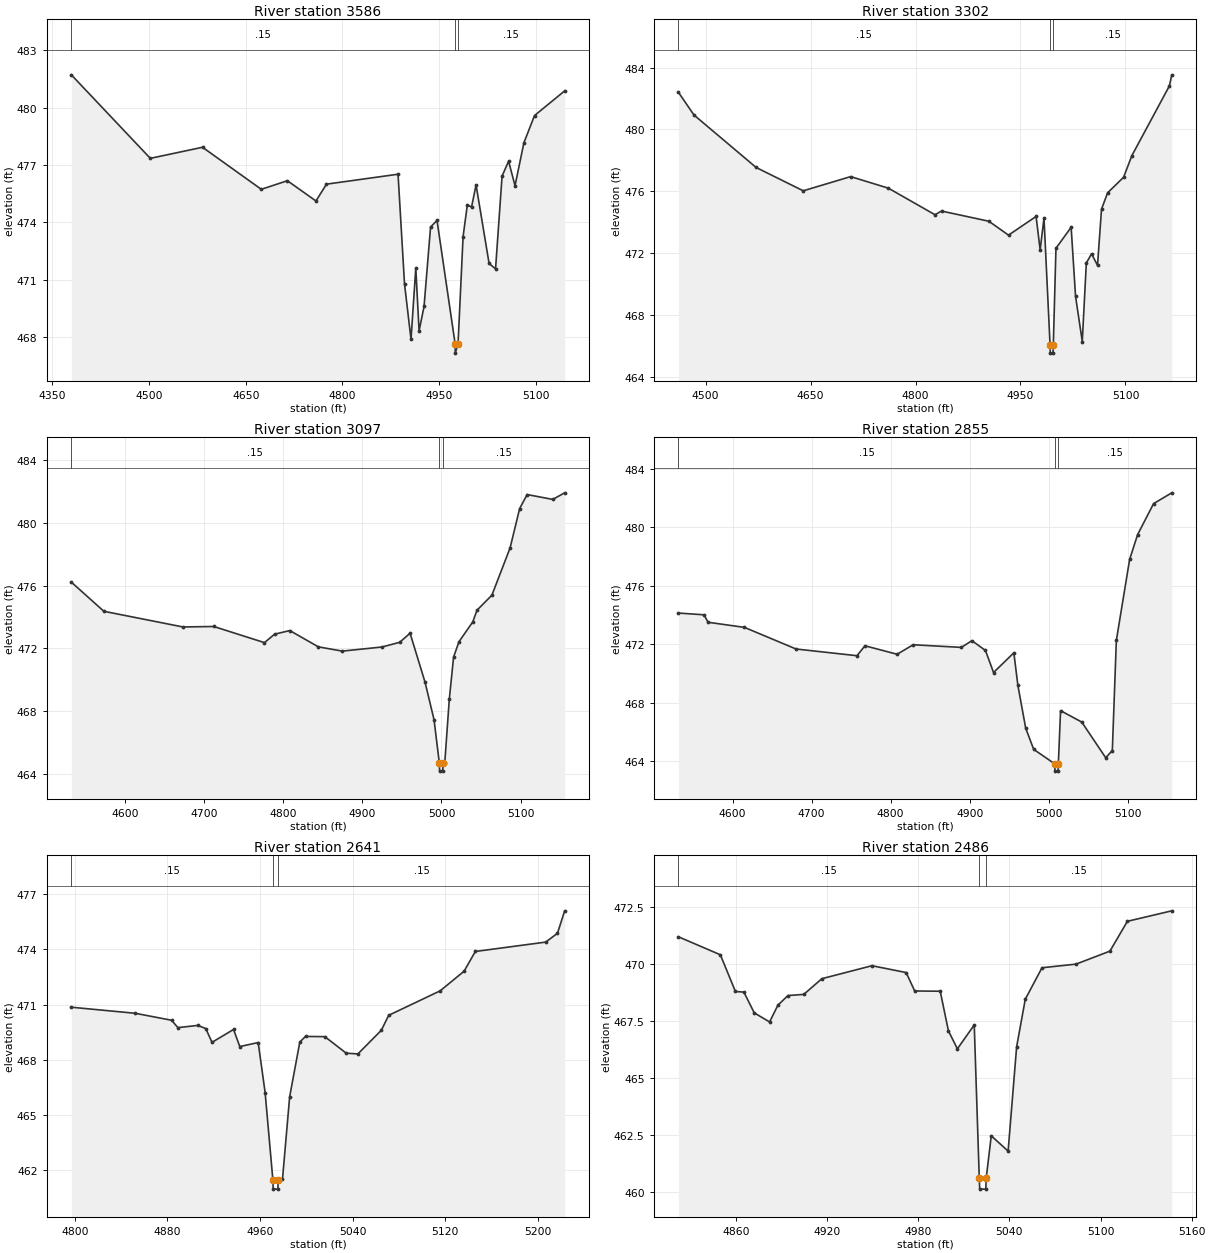
Type RM Length L Ch R = 1,3586,284,284,284
BEGIN DESCRIPTION:
Mapping XS 07c391ff
END DESCRIPTION:
XS GIS Cut Line= 4
      2758457.59      6844900.04      2758404.38      6845247.34
      2758370.37      6845514.03      2758353.40      6845657.33
#Sta/Elev= 30
  4379.8  481.72  4502.2  477.35  4583.1  477.93  4674.2  475.73  4714.6  476.18
  4758.9  475.12  4775.2  476.00  4886.1  476.52  4896.1  470.79  4906.2  467.88
  4913.6  471.61  4918.7  468.32  4926.4  469.60  4936.5  473.76  4946.5  474.10
  4974.5  467.66  4974.8  467.16  4979.1  467.66  4986.9  473.26  4993.5  474.92
  5000.0  474.80  5007.0  475.96  5027.2  471.85  5037.2  471.57  5047.3  476.42
  5057.4  477.20  5067.4  475.92  5081.1  478.16  5097.6  479.59  5144.3  480.88
#Mann=3,-1,0
  4379.8    0.15       0  4974.5    0.05       0  4979.1    0.15       0
Bank Sta=4974.5,4979.1
Exp/Cntr=0.3,0.1

Type RM Length L Ch R = 1,3302,205,205,205
BEGIN DESCRIPTION:
Mapping XS 4695d0db
END DESCRIPTION:
XS GIS Cut Line= 3
      2758436.75      6844851.04      2758200.76      6845337.45
      2758120.57      6845481.04
#Sta/Elev= 30
  4461.1  482.41  4483.3  480.94  4572.2  477.54  4639.5  476.03  4707.3  476.95
  4761.2  476.20  4827.8  474.48  4837.1  474.72  4904.8  474.06  4932.9  473.16
  4972.3  474.37  4978.1  472.20  4983.6  474.27  4992.3  466.02  4992.6  465.52
  4996.5  465.52  4996.9  466.02  5000.7  472.31  5022.4  473.67  5028.7  469.20
  5038.3  466.27  5044.1  471.36  5051.6  471.95  5060.1  471.20  5065.8  474.84
  5074.5  475.90  5097.4  476.91  5109.2  478.31  5162.9  482.83  5166.2  483.54
#Mann=3,-1,0
  4461.1    0.15       0  4992.3    0.05       0  4996.9    0.15       0
Bank Sta=4992.3,4996.9
Exp/Cntr=0.3,0.1

Type RM Length L Ch R = 1,3097,242,242,242
BEGIN DESCRIPTION:
Mapping XS acd3f5c1
END DESCRIPTION:
XS GIS Cut Line= 3
      2758209.81      6844772.49      2758044.66      6845214.29
      2757988.33      6845354.97
#Sta/Elev= 30
  4532.4  476.23  4573.5  474.37  4673.4  473.37  4712.3  473.40  4776.4  472.37
  4789.2  472.91  4808.4  473.14  4844.5  472.10  4874.7  471.83  4924.7  472.09
  4947.2  472.39  4960.3  472.97  4979.2  469.85  4990.6  467.45  4997.3  464.67
  4997.6  464.17  5001.6  464.17  5001.9  464.67  5004.1  464.67  5009.9  468.78
  5015.3  471.45  5022.1  472.43  5039.5  473.69  5044.9  474.44  5063.7  475.40
  5086.7  478.42  5098.7  480.92  5108.2  481.82  5140.6  481.51  5155.6  481.93
#Mann=3,-1,0
  4532.4    0.15       0  4997.3    0.05       0  5001.9    0.15       0
Bank Sta=4997.3,5001.9
Exp/Cntr=0.3,0.1

Type RM Length L Ch R = 1,2855,214,214,214
BEGIN DESCRIPTION:
Mapping XS 0ab550b4
END DESCRIPTION:
XS GIS Cut Line= 3
      2757947.72      6844638.86      2757862.25      6845104.21
      2757840.79      6845253.75
#Sta/Elev= 30
  4531.5  474.13  4563.9  474.01  4569.0  473.50  4615.0  473.15  4680.3  471.67
  4757.4  471.21  4767.5  471.89  4808.2  471.31  4828.5  471.96  4889.5  471.78
  4902.8  472.24  4920.0  471.57  4930.2  470.06  4955.9  471.41  4961.0  469.18
  4970.9  466.25  4981.0  464.80  5007.6  463.81  5007.9  463.31  5011.9  463.31
  5012.2  463.81  5015.0  467.45  5041.8  466.67  5072.1  464.23  5080.5  464.72
  5085.6  472.26  5102.4  477.80  5112.5  479.50  5132.7  481.62  5155.7  482.36
#Mann=3,-1,0
  4531.5    0.15       0  5007.6    0.05       0  5012.2    0.15       0
Bank Sta=5007.6,5012.2
Exp/Cntr=0.3,0.1

Type RM Length L Ch R = 1,2641,155,155,155
BEGIN DESCRIPTION:
Mapping XS 697953e6
END DESCRIPTION:
XS GIS Cut Line= 4
      2757554.86      6844911.48      2757694.48      6844968.56
      2757739.09      6844998.34      2757776.35      6845217.12
#Sta/Elev= 30
  4796.9  470.86  4852.1  470.53  4883.6  470.15  4889.0  469.75  4906.2  469.87
  4913.1  469.70  4918.5  468.95  4937.1  469.65  4942.5  468.72  4958.4  468.94
  4964.4  466.22  4971.1  461.47  4971.4  460.97  4975.4  460.97  4975.7  461.47
  4979.4  461.50  4985.6  465.99  4994.4  468.97  4999.3  469.27  5016.0  469.26
  5034.5  468.36  5044.6  468.32  5064.9  469.61  5071.2  470.42  5115.7  471.75
  5136.4  472.82  5146.1  473.89  5206.9  474.40  5217.1  474.88  5223.3  476.10
#Mann=3,-1,0
  4796.9    0.15       0  4971.1    0.05       0  4975.7    0.15       0
Bank Sta=4971.1,4975.7
Exp/Cntr=0.3,0.1

Type RM Length L Ch R = 1,2486,158,158,158
BEGIN DESCRIPTION:
Mapping XS 675cde1c
END DESCRIPTION:
XS GIS Cut Line= 3
      2757532.57      6844916.25      2757610.88      6845075.75
      2757676.92      6845207.10
#Sta/Elev= 30
  4822.2  471.20  4849.8  470.41  4859.7  468.80  4865.3  468.77  4872.1  467.86
  4882.2  467.46  4887.7  468.20  4894.3  468.62  4904.7  468.67  4916.6  469.36
  4949.6  469.93  4972.1  469.63  4977.7  468.82  4994.5  468.81  4999.9  467.07
  5005.8  466.28  5016.9  467.33  5020.2  460.62  5020.5  460.12  5024.5  460.12
  5024.8  460.62  5028.1  462.46  5039.2  461.79  5044.8  466.37  5050.5  468.46
  5061.5  469.84  5083.9  470.00  5106.2  470.57  5117.7  471.88  5146.9  472.34
#Mann=3,-1,0
  4822.2    0.15       0  5020.2    0.05       0  5024.8    0.15       0
Bank Sta=5020.2,5024.8
Exp/Cntr=0.3,0.1

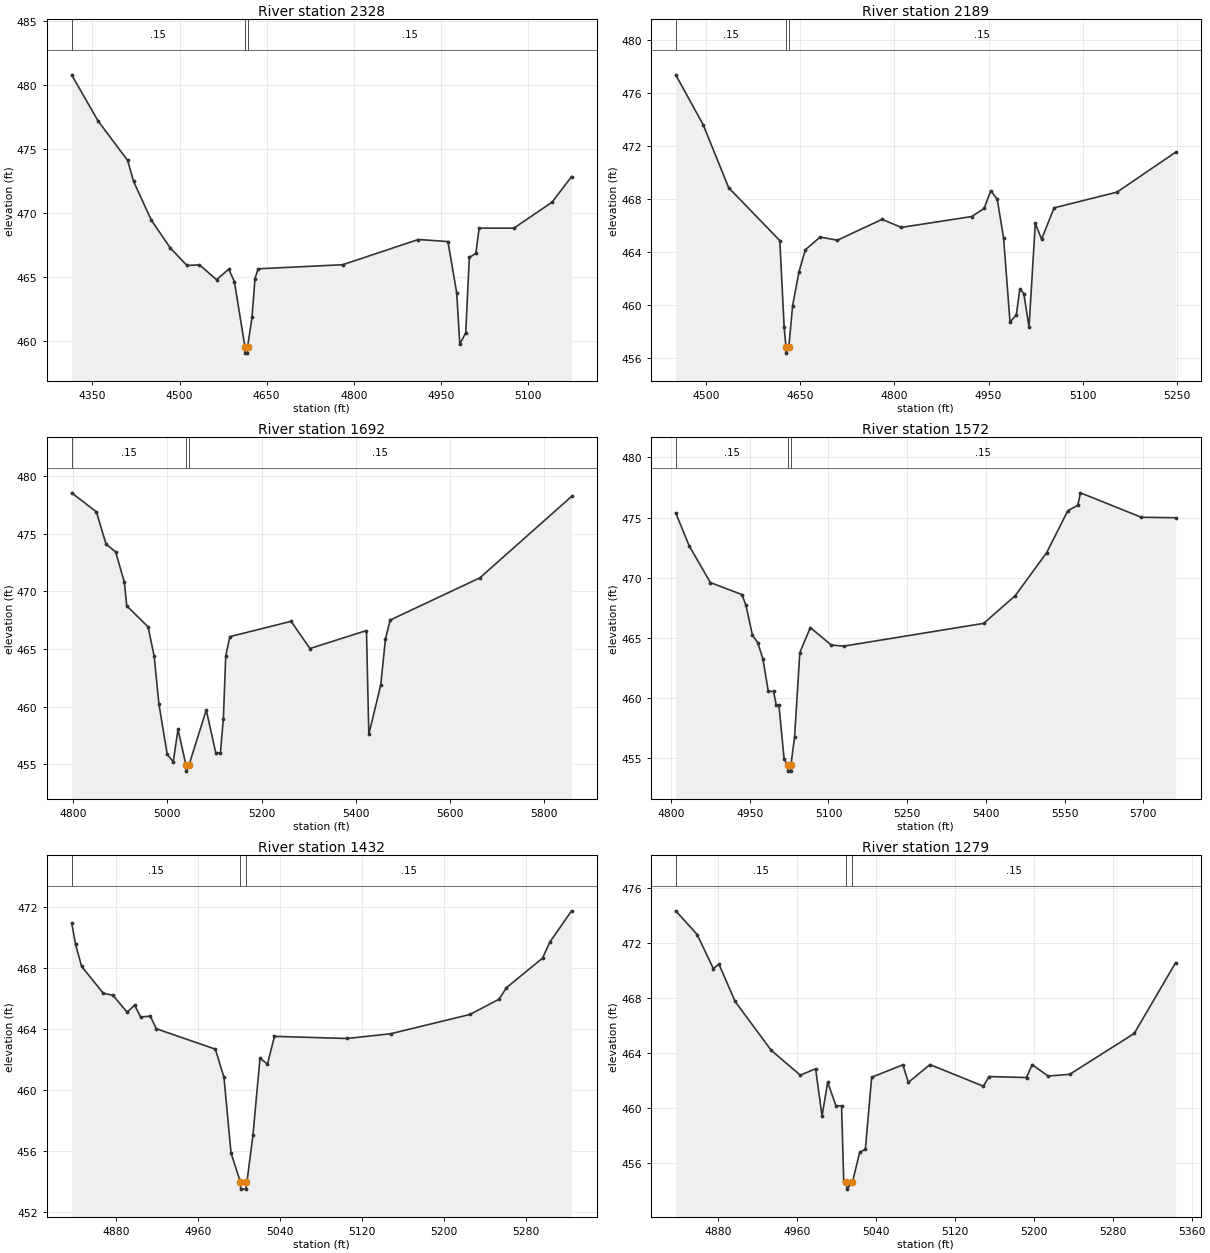
Type RM Length L Ch R = 1,2328,139,139,139
BEGIN DESCRIPTION:
North Twin Creek Trib A2328.28
END DESCRIPTION:
XS GIS Cut Line= 3
      2756851.68      6845062.48      2757523.02      6845200.62
      2757676.94      6845283.88
#Sta/Elev= 30
  4314.4  480.78  4359.6  477.19  4410.7  474.09  4420.9  472.46  4451.5  469.42
  4484.0  467.26  4512.8  465.88  4534.3  465.93  4563.8  464.77  4584.7  465.59
  4594.5  464.62  4612.6  459.53  4612.9  459.03  4616.9  459.03  4617.2  459.53
  4624.8  461.82  4629.9  464.86  4635.3  465.62  4780.9  465.94  4911.0  467.91
  4962.0  467.75  4977.1  463.74  4982.4  459.74  4992.6  460.61  4998.8  466.51
  5010.0  466.82  5015.7  468.80  5075.6  468.80  5141.3  470.83  5174.8  472.83
#Mann=3,-1,0
  4314.4    0.15       0  4612.6    0.05       0  4617.2    0.15       0
Bank Sta=4612.6,4617.2
Exp/Cntr=0.3,0.1

Type RM Length L Ch R = 1,2189,497,497,497
BEGIN DESCRIPTION:
North Twin Creek Trib A2188.65
END DESCRIPTION:
XS GIS Cut Line= 3
      2756873.21      6845173.40      2757411.75      6845275.84
      2757659.16      6845289.94
#Sta/Elev= 30
  4451.9  477.39  4495.5  473.62  4536.2  468.85  4617.6  464.85  4624.5  458.30
  4627.3  456.84  4627.6  456.34  4632.0  456.84  4638.0  459.94  4648.1  462.49
  4658.3  464.16  4681.8  465.12  4709.2  464.88  4780.5  466.46  4811.0  465.85
  4923.0  466.67  4942.8  467.28  4953.5  468.62  4963.7  468.00  4973.9  465.06
  4984.1  458.69  4994.2  459.23  4999.7  461.18  5006.1  460.85  5014.4  458.31
  5024.4  466.16  5034.4  464.96  5054.4  467.33  5154.6  468.52  5247.9  471.54
#Mann=3,-1,0
  4451.9    0.15       0  4627.3    0.05       0  4632.0    0.15       0
Bank Sta=4627.3,4632
Exp/Cntr=0.3,0.1

Type RM Length L Ch R = 1,1692,120,120,120
BEGIN DESCRIPTION:
North Twin Creek Trib A1691.72
END DESCRIPTION:
XS GIS Cut Line= 5
      2756764.58      6845282.85      2756965.20      6845324.10
      2757122.68      6845326.63      2757367.33      6845327.54
      2757820.09      6845297.76
#Sta/Elev= 30
  4796.9  478.54  4849.4  476.89  4869.8  474.10  4890.2  473.42  4908.7  470.79
  4913.8  468.74  4959.0  466.92  4971.9  464.39  4982.1  460.20  4999.6  455.87
  5012.5  455.22  5022.5  458.04  5039.5  454.91  5040.0  454.41  5045.6  454.91
  5082.5  459.71  5102.5  456.02  5112.5  455.98  5118.8  458.97  5123.8  464.38
  5132.5  466.07  5262.5  467.40  5302.5  465.04  5422.4  466.60  5427.4  457.61
  5452.6  461.86  5462.7  465.87  5472.7  467.51  5663.1  471.17  5857.6  478.23
#Mann=3,-1,0
  4796.9    0.15       0  5039.5    0.05       0  5045.6    0.15       0
Bank Sta=5039.5,5045.6
Exp/Cntr=0.3,0.1

Type RM Length L Ch R = 1,1572,140,140,140
BEGIN DESCRIPTION:
North Twin Creek Trib A1571.59
END DESCRIPTION:
XS GIS Cut Line= 3
      2756690.25      6845395.34      2756881.58      6845410.39
      2757641.41      6845444.07
#Sta/Elev= 30
  4809.0  475.39  4834.8  472.64  4875.0  469.61  4935.1  468.61  4942.6  467.74
  4955.2  465.23  4965.2  464.63  4975.3  463.22  4985.3  460.58  4995.3  460.57
  5000.6  459.42  5005.6  459.42  5015.4  454.97  5022.3  454.45  5022.8  453.95
  5027.9  453.95  5028.4  454.45  5035.4  456.79  5045.4  463.79  5065.4  465.87
  5105.4  464.42  5129.1  464.33  5395.7  466.22  5455.8  468.52  5515.8  472.10
  5555.9  475.57  5575.1  476.03  5580.1  477.06  5696.0  475.03  5761.5  474.99
#Mann=3,-1,0
  4809.0    0.15       0  5022.3    0.05       0  5028.4    0.15       0
Bank Sta=5022.3,5028.4
Exp/Cntr=0.3,0.1

Type RM Length L Ch R = 1,1432,153,153,153
BEGIN DESCRIPTION:
North Twin Creek Trib A1432.48
END DESCRIPTION:
XS GIS Cut Line= 3
      2756710.11      6845452.49      2756853.00      6845542.57
      2757070.55      6845776.55
#Sta/Elev= 30
  4836.4  470.98  4840.2  469.57  4846.1  468.12  4867.3  466.35  4876.7  466.22
  4890.6  465.11  4897.9  465.57  4903.8  464.79  4913.2  464.85  4919.1  464.02
  4976.8  462.68  4985.2  460.82  4992.1  455.85  5001.1  453.98  5001.6  453.48
  5006.7  453.48  5007.2  453.98  5007.7  453.98  5013.5  457.02  5020.4  462.08
  5027.7  461.70  5034.5  463.52  5105.4  463.38  5147.9  463.69  5225.6  464.96
  5253.9  465.96  5261.2  466.72  5296.4  468.66  5303.6  469.72  5324.8  471.77
#Mann=3,-1,0
  4836.4    0.15       0  5001.1    0.05       0  5007.2    0.15       0
Bank Sta=5001.1,5007.2
Exp/Cntr=0.3,0.1

Type RM Length L Ch R = 1,1279,121,121,121
BEGIN DESCRIPTION:
North Twin Creek Trib A1279.48
END DESCRIPTION:
XS GIS Cut Line= 3
      2756631.59      6845435.44      2756708.81      6845582.36
      2756871.64      6845881.77
#Sta/Elev= 30
  4837.0  474.32  4858.7  472.60  4875.1  470.13  4880.8  470.45  4897.2  467.74
  4933.7  464.20  4963.3  462.39  4978.8  462.86  4985.3  459.42  4991.0  461.88
  4999.4  460.17  5005.1  460.17  5007.3  454.69  5010.0  454.62  5010.5  454.12
  5016.1  454.62  5023.5  456.80  5029.2  457.01  5035.6  462.24  5067.2  463.14
  5072.9  461.87  5094.7  463.16  5148.9  461.59  5154.6  462.29  5192.6  462.22
  5198.3  463.16  5214.4  462.33  5236.3  462.45  5301.8  465.42  5343.8  470.56
#Mann=3,-1,0
  4837.0    0.15       0  5010.0    0.05       0  5016.1    0.15       0
Bank Sta=5010,5016.1
Exp/Cntr=0.3,0.1

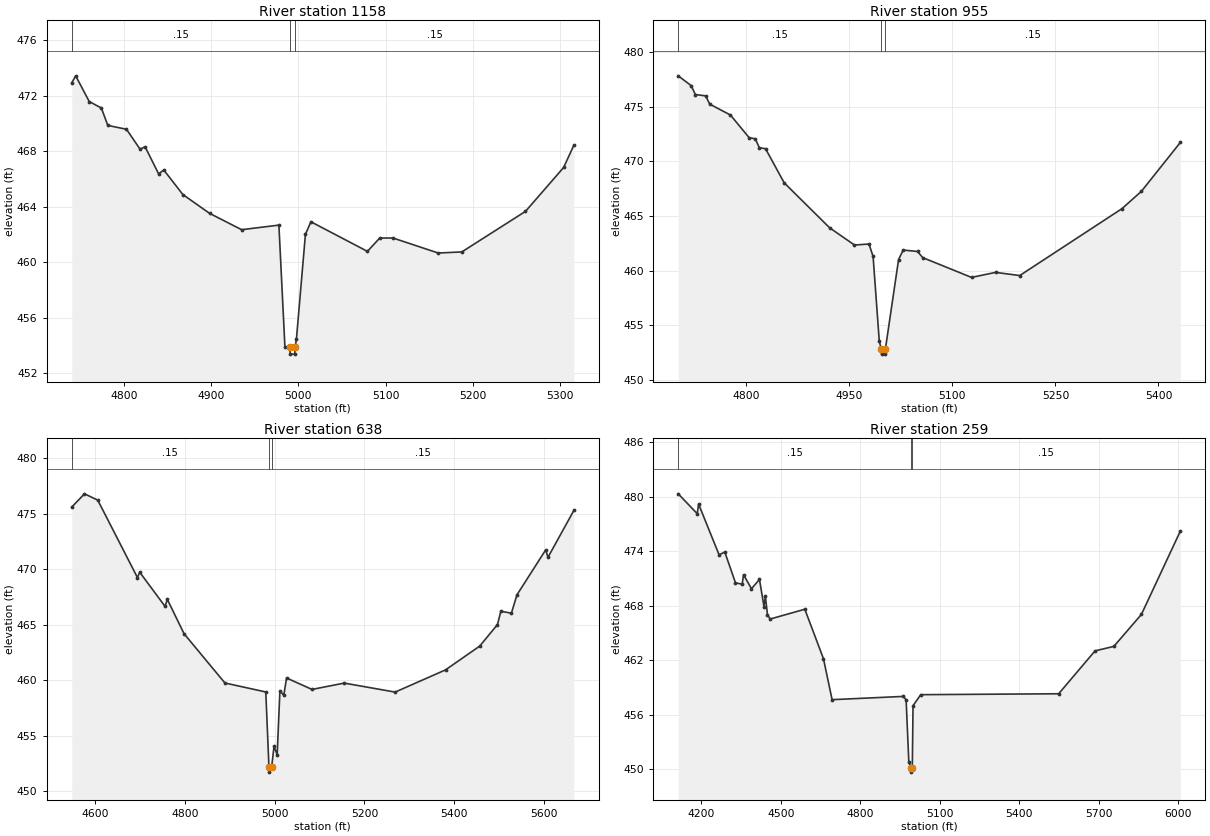
Type RM Length L Ch R = 1,1158,203,203,203
BEGIN DESCRIPTION:
North Twin Creek Trib A1157.7
END DESCRIPTION:
XS GIS Cut Line= 3
      2756468.77      6845412.02      2756602.90      6845633.91
      2756771.84      6845900.87
#Sta/Elev= 30
  4740.4  472.93  4744.9  473.43  4760.4  471.58  4774.3  471.11  4781.7  469.86
  4803.1  469.58  4818.6  468.15  4824.4  468.32  4839.9  466.37  4845.8  466.65
  4867.7  464.88  4898.2  463.53  4935.0  462.35  4977.7  462.68  4984.6  453.91
  4990.2  453.89  4990.7  453.39  4995.8  453.39  4996.3  453.89  4997.8  454.49
  5008.1  462.02  5014.4  462.92  5079.1  460.79  5093.2  461.75  5108.5  461.75
  5160.2  460.67  5187.3  460.75  5260.2  463.67  5303.9  466.83  5315.6  468.43
#Mann=3,-1,0
  4740.4    0.15       0  4990.2    0.05       0  4996.3    0.15       0
Bank Sta=4990.2,4996.3
Exp/Cntr=0.3,0.1

Type RM Length L Ch R = 1,955,317,317,317
BEGIN DESCRIPTION:
North Twin Creek Trib A954.77
END DESCRIPTION:
XS GIS Cut Line= 3
      2756247.49      6845424.96      2756413.27      6845675.80
      2756700.18      6845996.53
#Sta/Elev= 30
  4700.8  477.81  4719.7  476.91  4725.7  476.10  4740.7  475.98  4746.7  475.22
  4776.8  474.23  4803.9  472.17  4813.0  472.05  4818.9  471.24  4827.9  471.15
  4855.1  468.03  4921.3  463.92  4957.4  462.35  4978.5  462.44  4984.5  461.31
  4993.5  453.57  4996.3  452.88  4996.8  452.38  5002.0  452.38  5002.5  452.88
  5021.6  461.02  5028.3  461.89  5049.2  461.76  5056.7  461.20  5127.8  459.39
  5162.9  459.85  5198.0  459.56  5346.8  465.67  5375.2  467.26  5431.8  471.72
#Mann=3,-1,0
  4700.8    0.15       0  4996.3    0.05       0  5002.5    0.15       0
Bank Sta=4996.3,5002.5
Exp/Cntr=0.3,0.1

Type RM Length L Ch R = 1,638,379,379,379
BEGIN DESCRIPTION:
North Twin Creek Trib A637.59
END DESCRIPTION:
XS GIS Cut Line= 4
      2756077.14      6845363.74      2756149.96      6845812.27
      2756312.46      6845925.33      2756742.66      6846109.20
#Sta/Elev= 30
  4547.1  475.61  4575.5  476.80  4605.1  476.23  4693.6  469.26  4698.7  469.74
  4755.2  466.66  4760.3  467.29  4797.6  464.20  4888.8  459.76  4980.0  458.95
  4987.0  452.23  4987.5  451.73  4993.2  452.23  4998.3  454.05  5005.4  453.30
  5011.5  459.06  5020.2  458.65  5026.3  460.21  5083.1  459.18  5155.0  459.75
  5268.6  458.94  5381.0  460.94  5457.2  463.08  5496.9  465.02  5504.4  466.22
  5528.0  466.05  5540.4  467.70  5604.3  471.74  5609.7  471.09  5667.3  475.30
#Mann=3,-1,0
  4547.1    0.15       0  4987.0    0.05       0  4993.2    0.15       0
Bank Sta=4987,4993.2
Exp/Cntr=0.3,0.1

Type RM Length L Ch R = 1,259,0,0,0
BEGIN DESCRIPTION:
North Twin Creek Trib A258.989
END DESCRIPTION:
XS GIS Cut Line= 3
      2755929.74      6845076.35      2755824.25      6845957.66
      2756789.88      6846248.94
#Sta/Elev= 30
  4112.4  480.32  4184.2  478.13  4189.3  479.19  4266.6  473.61  4288.3  473.90
  4328.6  470.52  4354.0  470.37  4359.0  471.41  4389.0  469.87  4419.2  470.89
  4436.3  467.90  4441.4  469.07  4449.4  467.01  4459.5  466.53  4590.4  467.61
  4660.9  462.16  4693.5  457.65  4963.1  458.01  4973.1  457.62  4983.2  450.83
  4990.1  450.17  4990.6  449.67  4996.4  450.17  4999.2  456.99  5028.4  458.20
  5549.2  458.30  5686.4  463.02  5757.6  463.52  5861.7  467.04  6008.6  476.21
#Mann=3,-1,0
  4112.4    0.15       0  4990.1    0.05       0  4996.4    0.15       0
Bank Sta=4990.1,4996.4
Exp/Cntr=0.3,0.1

Chan Stop Cuts=-1