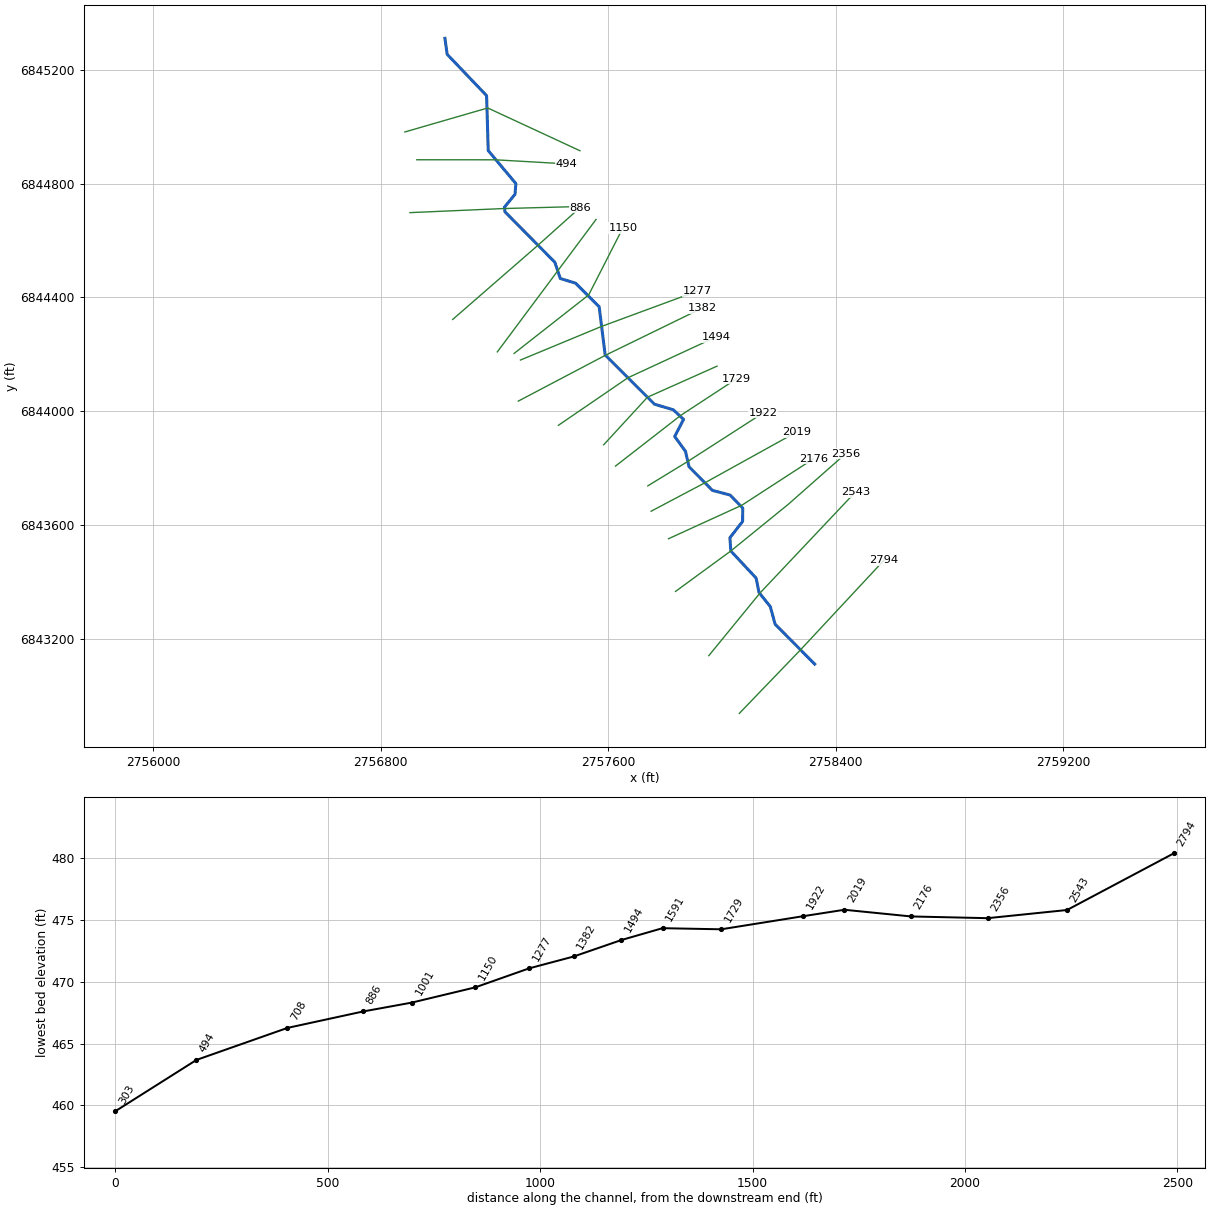
--- North Twin Creek Trib A1.prj (project) ---

Proj Title=North Twin Creek Trib A1 Base Level Engineering
Current Plan=p01
Default Exp/Contr=0.3,0.1
English Units
Geom File=g01
Flow File=f01
Plan File=p01
BEGIN DESCRIPTION:
North Twin Creek Trib A1
END DESCRIPTION:

--- North Twin Creek Trib A1.p01 (plan) ---

Plan Title=Multiple Run
Short Identifier=Multiple
Geom File=g01
Flow File=f01
Subcritical Flow
K Sum by GR= 0
Std Step Tol= 0.01
Critical Tol= 0.01
Num of Std Step Trials= 20
Max Error Tol= 0.3
Flow Tol Ratio= 0.001
Split Flow NTrial= 30
Split Flow Tol= 0.02
Split Flow Ratio= 0.02
Log Output Level= 0
Friction Slope Method= 1
Unsteady Friction Slope Method= 2
Unsteady Bridges Friction Slope Method= 1
Parabolic Critical Depth
Global Vel Dist=  1 , 1 , 1
Global Log Level= 0
CheckData=True
Encroach Param= -1, 0, 0, 0
BEGIN DESCRIPTION:
Multiple Run
END DESCRIPTION:

--- North Twin Creek Trib A1.f01 (steady flow) ---

Flow Title=Multiple
Number of Profiles=7
Profile Names=10-year,25-year,50-year,1pct_min,100-year,1pct_plu,500-year
River Rch & RM= North Twin Creek,Reach-1,2794
     439     583     700     418     834    1663    1185
Boundary for River Rch & Prof#=North Twin Creek,Reach-1,1
Up Type=0
Dn Type=3
Dn Slope=0.005
Boundary for River Rch & Prof#=North Twin Creek,Reach-1,2
Up Type=0
Dn Type=3
Dn Slope=0.005
Boundary for River Rch & Prof#=North Twin Creek,Reach-1,3
Up Type=0
Dn Type=3
Dn Slope=0.005
Boundary for River Rch & Prof#=North Twin Creek,Reach-1,4
Up Type=0
Dn Type=3
Dn Slope=0.005
Boundary for River Rch & Prof#=North Twin Creek,Reach-1,5
Up Type=0
Dn Type=3
Dn Slope=0.005
Boundary for River Rch & Prof#=North Twin Creek,Reach-1,6
Up Type=0
Dn Type=3
Dn Slope=0.005
Boundary for River Rch & Prof#=North Twin Creek,Reach-1,7
Up Type=0
Dn Type=3
Dn Slope=0.005

--- North Twin Creek Trib A1.g01 (geometry) ---

Geom Title=Existing Conditions

River Reach=North Twin Creek,Reach-1
Reach XY= 30
      2758326.00      6843111.00      2758186.76      6843251.31
      2758169.90      6843313.19      2758130.19      6843362.73
      2758120.15      6843413.29      2758031.11      6843508.71
      2758027.93      6843555.28      2758072.64      6843612.76
      2758072.96      6843659.58      2758028.61      6843705.25
      2757966.32      6843721.78      2757884.11      6843804.93
      2757871.56      6843859.35      2757833.78      6843911.10
      2757864.89      6843971.32      2757828.83      6844005.14
      2757762.82      6844024.63      2757589.37      6844197.68
      2757568.19      6844367.21      2757485.44      6844450.12
      2757431.62      6844466.62      2757412.27      6844523.98
      2757237.11      6844700.95      2757235.33      6844717.55
      2757272.41      6844762.65      2757275.35      6844800.36
      2757178.18      6844916.45      2757172.46      6845109.54
      2757033.76      6845254.79      2757026.00      6845311.00

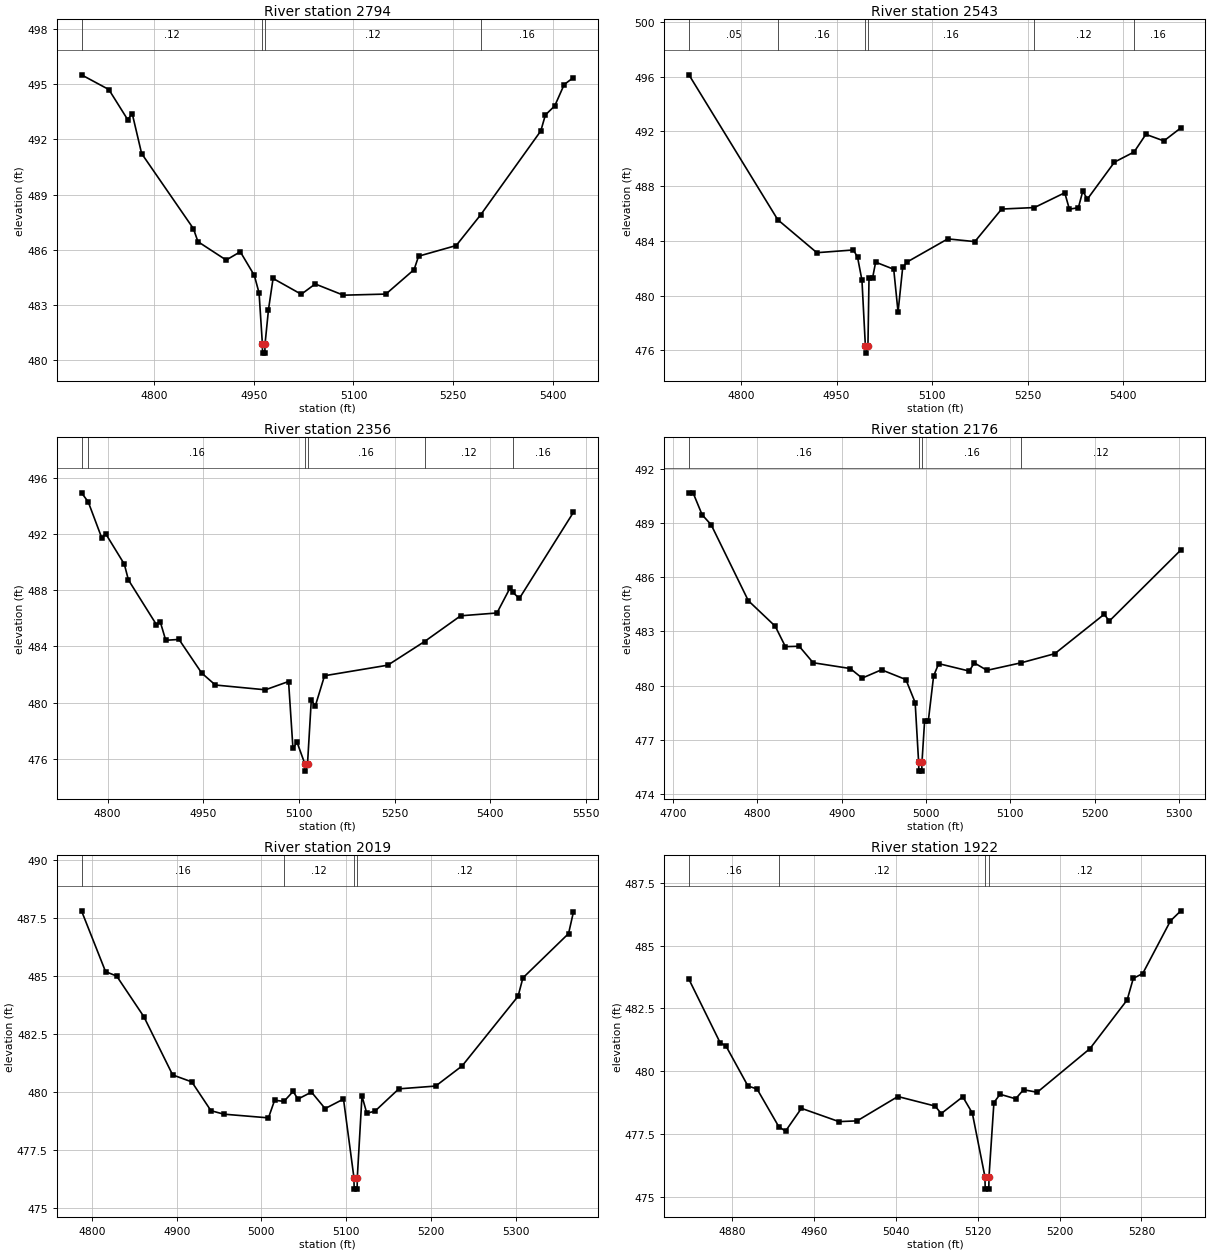
Type RM Length L Ch R = 1,2794,251,251,251
BEGIN DESCRIPTION:
North Twin Creek Trib A12794.25
END DESCRIPTION:
XS GIS Cut Line= 3
      2758061.02      6842937.73      2758276.00      6843161.00
      2758570.05      6843476.61
#Sta/Elev= 30
  4690.1  495.51  4731.3  494.71  4759.6  493.08  4766.6  493.39  4780.7  491.23
  4858.7  487.15  4865.6  486.44  4908.1  485.44  4929.4  485.89  4950.5  484.61
  4957.7  483.65  4962.7  480.88  4962.9  480.38  4966.4  480.38  4966.7  480.88
  4971.9  482.75  4978.8  484.44  5021.3  483.58  5042.3  484.14  5084.8  483.53
  5148.8  483.59  5191.3  484.92  5198.1  485.65  5254.8  486.23  5291.9  487.91
  5382.3  492.46  5389.2  493.33  5403.3  493.82  5417.5  494.98  5431.4  495.36
#Mann=4,-1,0
  4690.1    0.12       0  4962.7    0.07       0  4966.7    0.12       0
  5291.9    0.16       0
Bank Sta=4962.7,4966.7
Exp/Cntr=0.3,0.1

Type RM Length L Ch R = 1,2543,187,187,187
BEGIN DESCRIPTION:
North Twin Creek Trib A12542.69
END DESCRIPTION:
XS GIS Cut Line= 3
      2757953.72      6843140.66      2758134.49      6843361.75
      2758468.89      6843715.68
#Sta/Elev= 30
  4718.2  496.14  4857.7  485.55  4919.1  483.14  4976.5  483.34  4983.0  482.81
  4989.9  481.13  4995.3  476.30  4995.6  475.80  4999.3  476.30  5001.0  481.32
  5006.7  481.32  5011.4  482.45  5039.8  481.93  5046.6  478.80  5053.9  482.06
  5060.8  482.46  5124.7  484.15  5167.2  483.95  5209.3  486.33  5260.8  486.44
  5308.4  487.52  5315.7  486.32  5329.8  486.43  5336.7  487.63  5344.0  487.06
  5386.5  489.76  5417.3  490.50  5435.8  491.79  5464.1  491.31  5490.7  492.26
#Mann=6,-1,0
  4718.2    0.05       0  4857.7    0.16       0  4995.3    0.07       0
  4999.3    0.16       0  5260.8    0.12       0  5417.3    0.16       0
Bank Sta=4995.3,4999.3
Exp/Cntr=0.3,0.1

Type RM Length L Ch R = 1,2356,180,180,180
BEGIN DESCRIPTION:
North Twin Creek Trib A12321.66
END DESCRIPTION:
XS GIS Cut Line= 4
      2757836.70      6843366.44      2758031.11      6843508.71
      2758232.69      6843672.40      2758435.38      6843851.26
#Sta/Elev= 30
  4759.1  494.92  4769.6  494.28  4790.7  491.73  4796.9  492.02  4826.2  489.85
  4832.6  488.73  4876.4  485.56  4882.6  485.74  4891.1  484.44  4911.9  484.50
  4947.5  482.11  4968.9  481.26  5047.3  480.92  5083.6  481.51  5090.5  476.76
  5096.9  477.19  5109.3  475.64  5109.5  475.14  5113.3  475.64  5119.2  480.17
  5125.6  479.78  5140.0  481.92  5239.1  482.67  5296.7  484.35  5353.3  486.18
  5410.2  486.38  5431.1  488.19  5434.6  487.87  5445.3  487.41  5530.0  493.53
#Mann=6,-1,0
  4759.1    0.05       0  4769.6    0.16       0  5109.3    0.07       0
  5113.3    0.16       0  5296.7    0.12       0  5434.6    0.16       0
Bank Sta=5109.3,5113.3
Exp/Cntr=0.3,0.1

Type RM Length L Ch R = 1,2176,157,157,157
BEGIN DESCRIPTION:
North Twin Creek Trib A12176.48
END DESCRIPTION:
XS GIS Cut Line= 3
      2757811.98      6843551.68      2758070.19      6843669.67
      2758321.43      6843832.71
#Sta/Elev= 30
  4718.8  490.66  4723.7  490.66  4734.4  489.45  4745.2  488.89  4789.2  484.70
  4821.1  483.29  4833.2  482.16  4849.6  482.18  4866.1  481.27  4910.1  480.95
  4924.2  480.42  4947.2  480.88  4976.1  480.34  4987.1  479.07  4991.2  475.78
  4991.5  475.28  4995.0  475.28  4995.2  475.78  4998.3  478.05  5002.7  478.05
  5009.0  480.54  5015.0  481.22  5051.2  480.81  5057.3  481.26  5072.3  480.85
  5113.1  481.27  5152.7  481.77  5211.4  483.95  5217.3  483.57  5302.2  487.50
#Mann=4,-1,0
  4718.8    0.16       0  4991.2    0.07       0  4995.2    0.16       0
  5113.1    0.12       0
Bank Sta=4991.2,4995.2
Exp/Cntr=0.3,0.1

Type RM Length L Ch R = 1,2019,97,97,97
BEGIN DESCRIPTION:
North Twin Creek Trib A12019.17
END DESCRIPTION:
XS GIS Cut Line= 3
      2757750.91      6843648.43      2757939.98      6843748.40
      2758260.91      6843926.07
#Sta/Elev= 30
  4787.6  487.81  4816.0  485.19  4829.1  485.00  4861.2  483.25  4895.2  480.74
  4917.8  480.44  4940.4  479.20  4955.5  479.05  5008.3  478.89  5015.6  479.65
  5026.6  479.60  5037.4  480.03  5043.1  479.70  5059.1  480.00  5075.2  479.29
  5096.9  479.70  5109.2  476.32  5109.5  475.82  5113.0  475.82  5113.2  476.32
  5118.7  479.83  5124.4  479.09  5134.1  479.18  5162.2  480.14  5205.7  480.26
  5237.0  481.13  5303.0  484.13  5308.7  484.92  5362.6  486.83  5368.3  487.75
#Mann=4,-1,0
  4787.6    0.16       0  5026.6    0.12       0  5109.2    0.07       0
  5113.2    0.12       0
Bank Sta=5109.2,5113.2
Exp/Cntr=0.3,0.1

Type RM Length L Ch R = 1,1922,193,193,193
BEGIN DESCRIPTION:
North Twin Creek Trib A11921.52
END DESCRIPTION:
XS GIS Cut Line= 3
      2757739.25      6843737.61      2757877.62      6843822.14
      2758145.19      6843994.26
#Sta/Elev= 30
  4838.1  483.66  4868.5  481.14  4874.3  481.00  4895.7  479.41  4904.6  479.29
  4925.8  477.79  4932.4  477.61  4947.9  478.52  4984.6  477.99  5002.3  478.02
  5042.1  478.99  5078.5  478.61  5084.4  478.31  5105.5  478.98  5114.8  478.33
  5127.1  475.80  5127.4  475.30  5130.9  475.30  5131.1  475.80  5135.9  478.75
  5141.9  479.08  5157.1  478.90  5164.8  479.26  5178.2  479.16  5229.7  480.90
  5266.0  482.84  5272.0  483.70  5281.2  483.89  5308.3  485.99  5318.4  486.39
#Mann=4,-1,0
  4838.1    0.16       0  4925.8    0.12       0  5127.1    0.07       0
  5131.1    0.12       0
Bank Sta=5127.1,5131.1
Exp/Cntr=0.3,0.1

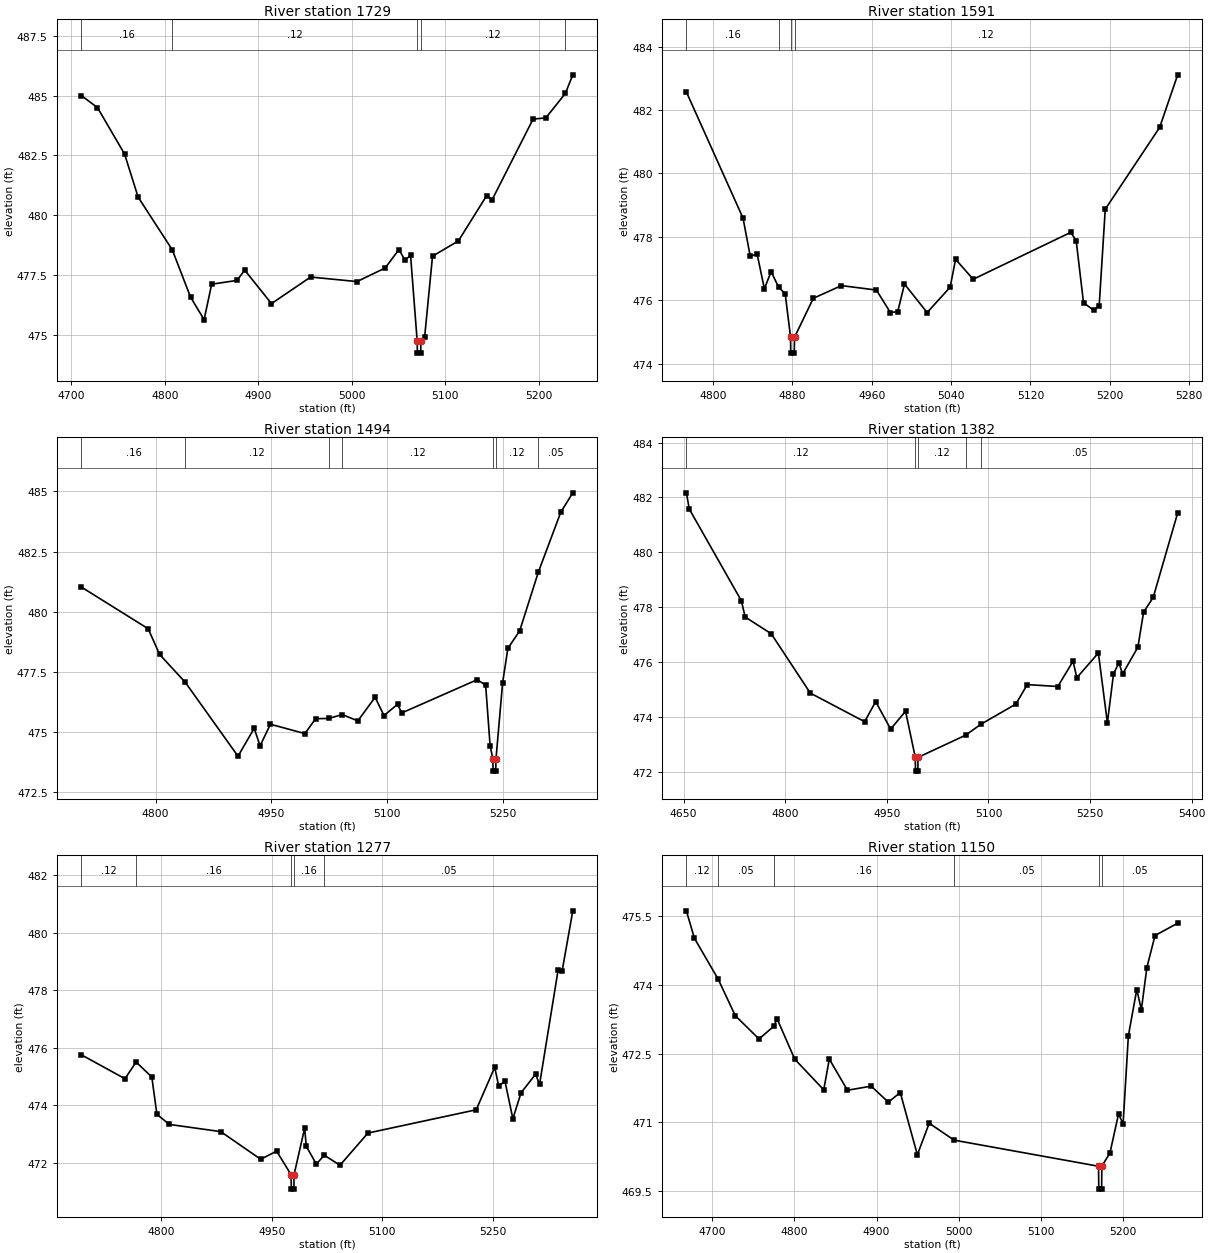
Type RM Length L Ch R = 1,1729,138,138,138
BEGIN DESCRIPTION:
North Twin Creek Trib A11728.54
END DESCRIPTION:
XS GIS Cut Line= 3
      2757625.49      6843807.02      2757854.88      6843985.32
      2758051.58      6844114.21
#Sta/Elev= 30
  4710.8  485.00  4727.9  484.50  4756.9  482.56  4771.4  480.76  4807.9  478.56
  4827.5  476.58  4842.0  475.64  4850.1  477.12  4877.3  477.28  4885.4  477.71
  4914.1  476.31  4956.0  477.42  5005.6  477.23  5035.8  477.80  5050.5  478.57
  5056.9  478.12  5062.9  478.33  5070.0  474.74  5070.2  474.24  5073.7  474.24
  5074.0  474.74  5078.0  474.93  5086.4  478.29  5114.1  478.93  5144.3  480.82
  5150.3  480.66  5194.0  484.02  5207.6  484.07  5228.5  485.09  5236.5  485.87
#Mann=5,-1,0
  4710.8    0.16       0  4807.9    0.12       0  5070.0    0.07       0
  5074.0    0.12       0  5228.5    0.16       0
Bank Sta=5070,5074
Exp/Cntr=0.3,0.1

Type RM Length L Ch R = 1,1591,97,97,97
BEGIN DESCRIPTION:
North Twin Creek Trib A11590.88
END DESCRIPTION:
XS GIS Cut Line= 3
      2757584.17      6843882.06      2757738.04      6844049.28
      2757982.62      6844158.49
#Sta/Elev= 30
  4773.3  482.57  4830.4  478.59  4837.7  477.38  4844.5  477.47  4851.9  476.36
  4858.7  476.90  4866.3  476.41  4872.9  476.20  4878.3  474.83  4878.5  474.33
  4882.0  474.33  4882.3  474.83  4901.2  476.06  4929.6  476.46  4964.8  476.32
  4978.9  475.61  4986.3  475.64  4993.1  476.51  5015.9  475.61  5039.1  476.41
  5044.6  477.29  5062.3  476.66  5160.6  478.14  5166.1  477.88  5173.5  475.92
  5183.9  475.68  5189.3  475.83  5195.4  478.87  5250.2  481.45  5268.4  483.11
#Mann=4,-1,0
  4773.3    0.16       0  4866.3    0.12       0  4878.3    0.07       0
  4882.3    0.12       0
Bank Sta=4878.3,4882.3
Exp/Cntr=0.3,0.1

Type RM Length L Ch R = 1,1494,112,112,112
BEGIN DESCRIPTION:
North Twin Creek Trib A11458.88
END DESCRIPTION:
XS GIS Cut Line= 3
      2757424.90      6843950.51      2757669.31      6844117.65
      2757978.55      6844260.89
#Sta/Elev= 30
  4703.9  481.02  4790.3  479.29  4805.2  478.22  4838.5  477.06  4906.8  473.99
  4927.8  475.15  4935.4  474.42  4948.8  475.32  4993.5  474.93  5007.4  475.55
  5024.3  475.56  5041.9  475.72  5062.2  475.46  5084.5  476.44  5096.1  475.68
  5113.6  476.15  5119.1  475.79  5216.8  477.17  5227.8  476.95  5233.6  474.43
  5237.2  473.87  5237.4  473.37  5240.9  473.37  5241.2  473.87  5249.8  477.04
  5256.6  478.47  5271.9  479.20  5296.3  481.66  5325.3  484.14  5340.8  484.94
#Mann=7,-1,0
  4703.9    0.16       0  4838.5    0.12       0  5024.3    0.16       0
  5041.9    0.12       0  5237.2    0.07       0  5241.2    0.12       0
  5296.3    0.05       0
Bank Sta=5237.2,5241.2
Exp/Cntr=0.3,0.1

Type RM Length L Ch R = 1,1382,105,105,105
BEGIN DESCRIPTION:
North Twin Creek Trib A11382.07
END DESCRIPTION:
XS GIS Cut Line= 3
      2757284.00      6844035.65      2757591.22      6844197.24
      2757931.25      6844362.99
#Sta/Elev= 30
  4654.0  482.17  4658.3  481.58  4735.2  478.24  4740.8  477.65  4779.3  477.04
  4837.0  474.88  4917.2  473.84  4933.5  474.57  4955.6  473.57  4977.6  474.22
  4992.0  472.54  4992.3  472.04  4995.8  472.04  4996.0  472.54  5066.4  473.35
  5089.1  473.75  5140.4  474.48  5157.3  475.19  5202.4  475.12  5224.9  476.04
  5230.5  475.44  5262.3  476.34  5275.6  473.80  5284.6  475.57  5292.5  475.98
  5298.1  475.58  5320.6  476.55  5329.1  477.83  5343.2  478.36  5379.4  481.44
#Mann=5,-1,0
  4654.0    0.12       0  4992.0    0.07       0  4996.0    0.12       0
  5066.4    0.16       0  5089.1    0.05       0
Bank Sta=4992,4996
Exp/Cntr=0.3,0.1

Type RM Length L Ch R = 1,1277,127,127,127
BEGIN DESCRIPTION:
North Twin Creek Trib A11277.02
END DESCRIPTION:
XS GIS Cut Line= 3
      2757291.51      6844180.00      2757575.00      6844297.51
      2757912.29      6844421.97
#Sta/Elev= 30
  4691.9  475.75  4750.9  474.92  4766.0  475.50  4787.3  474.98  4794.2  473.68
  4811.2  473.33  4880.8  473.08  4934.9  472.12  4956.6  472.40  4976.2  471.58
  4976.5  471.08  4980.0  471.08  4980.2  471.58  4994.6  473.20  4996.8  472.57
  5010.5  471.95  5021.2  472.26  5042.5  471.91  5080.4  473.03  5227.3  473.84
  5252.4  475.32  5257.7  474.67  5266.3  474.83  5277.0  473.53  5288.1  474.43
  5307.9  475.08  5313.2  474.72  5338.3  478.69  5343.7  478.65  5358.3  480.76
#Mann=5,-1,0
  4691.9    0.12       0  4766.0    0.16       0  4976.2    0.07       0
  4980.2    0.16       0  5021.2    0.05       0
Bank Sta=4976.2,4980.2
Exp/Cntr=0.3,0.1

Type RM Length L Ch R = 1,1150,149,149,149
BEGIN DESCRIPTION:
North Twin Creek Trib A11151
END DESCRIPTION:
XS GIS Cut Line= 3
      2757269.16      6844203.19      2757531.48      6844409.00
      2757651.54      6844644.44
#Sta/Elev= 30
  4668.6  475.62  4678.4  475.02  4707.2  474.13  4728.1  473.33  4757.0  472.82
  4775.0  473.10  4779.0  473.26  4800.4  472.38  4835.7  471.71  4842.5  472.38
  4864.6  471.70  4893.4  471.79  4914.3  471.44  4928.8  471.65  4949.6  470.29
  4964.0  470.98  4994.3  470.61  5170.0  470.04  5170.3  469.54  5173.8  469.54
  5174.0  470.04  5183.9  470.33  5194.3  471.18  5199.9  470.97  5206.3  472.89
  5216.5  473.90  5222.1  473.46  5228.8  474.38  5238.7  475.08  5266.3  475.35
#Mann=6,-1,0
  4668.6    0.12       0  4707.2    0.05       0  4775.0    0.16       0
  4994.3    0.05       0  5170.0    0.05       0  5174.0    0.05       0
Bank Sta=5170,5174
Exp/Cntr=0.3,0.1

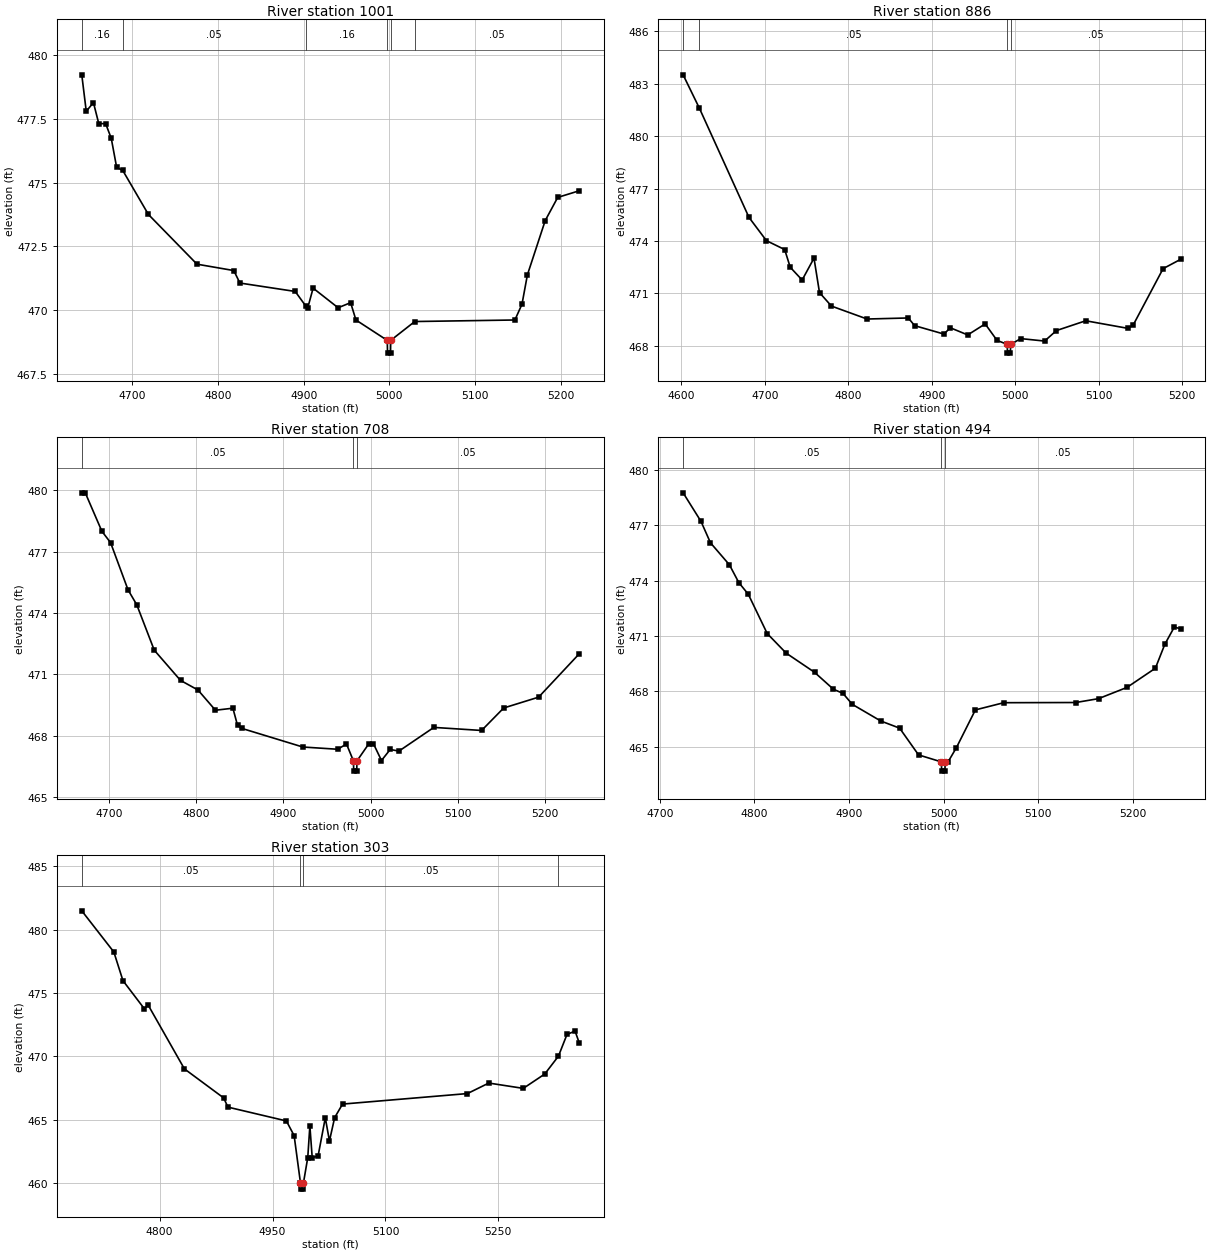
Type RM Length L Ch R = 1,1001,115,115,115
BEGIN DESCRIPTION:
North Twin Creek Trib A1976.59
END DESCRIPTION:
XS GIS Cut Line= 3
      2757210.23      6844208.64      2757424.82      6844496.58
      2757557.34      6844674.31
#Sta/Elev= 30
  4640.9  479.23  4646.1  477.80  4654.5  478.14  4660.7  477.32  4668.8  477.31
  4675.3  476.74  4681.6  475.60  4688.7  475.48  4718.7  473.75  4775.4  471.80
  4818.4  471.55  4825.5  471.06  4890.1  470.73  4902.4  470.16  4904.7  470.08
  4911.0  470.86  4940.2  470.09  4954.8  470.29  4961.0  469.61  4997.6  468.81
  4997.9  468.31  5001.4  468.31  5001.6  468.81  5029.7  469.55  5146.6  469.61
  5154.9  470.23  5161.2  471.38  5182.0  473.51  5196.6  474.42  5221.7  474.68
#Mann=6,-1,0
  4640.9    0.16       0  4688.7    0.05       0  4902.4    0.16       0
  4997.6    0.07       0  5001.6    0.16       0  5029.7    0.05       0
Bank Sta=4997.6,5001.6
Exp/Cntr=0.3,0.1

Type RM Length L Ch R = 1,886,178,178,178
BEGIN DESCRIPTION:
North Twin Creek Trib A1885.83
END DESCRIPTION:
XS GIS Cut Line= 3
      2757053.24      6844322.61      2757354.60      6844584.81
      2757501.03      6844715.91
#Sta/Elev= 30
  4602.2  483.50  4621.8  481.58  4681.1  475.35  4702.0  474.02  4723.9  473.51
  4730.5  472.50  4744.8  471.77  4759.0  473.02  4765.6  471.05  4779.9  470.28
  4822.6  469.54  4872.0  469.60  4879.6  469.16  4914.7  468.68  4922.3  469.04
  4943.2  468.63  4964.1  469.26  4978.3  468.32  4990.6  468.09  4990.8  467.59
  4994.3  467.59  4994.6  468.09  5006.8  468.42  5035.3  468.28  5049.5  468.88
  5084.6  469.44  5134.7  469.01  5141.4  469.19  5177.3  472.42  5198.2  472.95
#Mann=4,-1,0
  4602.2    0.16       0  4621.8    0.05       0  4990.6    0.05       0
  4994.6    0.05       0
Bank Sta=4990.6,4994.6
Exp/Cntr=0.3,0.1

Type RM Length L Ch R = 1,708,214,214,214
BEGIN DESCRIPTION:
North Twin Creek Trib A1708.34
END DESCRIPTION:
XS GIS Cut Line= 3
      2756903.05      6844698.21      2757232.50      6844712.59
      2757472.45      6844718.99
#Sta/Elev= 30
  4669.1  479.88  4673.1  479.88  4692.1  478.00  4702.1  477.44  4722.1  475.13
  4732.1  474.40  4752.1  472.18  4782.2  470.70  4802.2  470.23  4822.2  469.24
  4842.2  469.34  4847.5  468.50  4852.5  468.35  4922.3  467.44  4962.3  467.33
  4972.3  467.59  4980.3  466.76  4980.6  466.26  4984.1  466.26  4984.3  466.76
  4998.1  467.61  5003.1  467.61  5012.4  466.78  5022.4  467.32  5032.4  467.24
  5072.4  468.40  5127.1  468.25  5152.4  469.35  5192.4  469.88  5238.9  472.00
#Mann=3,-1,0
  4669.1    0.05       0  4980.3    0.05       0  4984.3    0.05       0
Bank Sta=4980.3,4984.3
Exp/Cntr=0.3,0.1

Type RM Length L Ch R = 1,494,191,191,191
BEGIN DESCRIPTION:
North Twin Creek Trib A1493.89
END DESCRIPTION:
XS GIS Cut Line= 3
      2756927.06      6844884.10      2757203.28      6844883.96
      2757452.55      6844869.74
#Sta/Elev= 30
  4724.6  478.76  4743.5  477.21  4753.5  476.05  4773.5  474.86  4783.5  473.89
  4793.5  473.26  4813.5  471.13  4833.5  470.07  4863.5  469.03  4883.5  468.11
  4893.5  467.89  4903.5  467.29  4933.5  466.39  4953.5  466.00  4973.5  464.55
  4997.7  464.17  4997.9  463.67  5001.4  463.67  5001.7  464.17  5004.7  464.17
  5013.6  464.95  5033.6  466.99  5063.6  467.38  5139.7  467.39  5163.8  467.60
  5193.9  468.21  5223.9  469.25  5233.9  470.55  5243.9  471.48  5250.5  471.39
#Mann=3,-1,0
  4724.6    0.05       0  4997.7    0.05       0  5001.7    0.05       0
Bank Sta=4997.7,5001.7
Exp/Cntr=0.3,0.1

Type RM Length L Ch R = 1,303,0,0,0
BEGIN DESCRIPTION:
North Twin Creek Trib A1394.05
END DESCRIPTION:
XS GIS Cut Line= 3
      2756885.05      6844981.79      2757176.47      6845066.20
      2757500.71      6844915.84
#Sta/Elev= 30
  4696.6  481.48  4739.2  478.23  4751.3  475.97  4779.6  473.76  4784.9  474.03
  4832.9  469.01  4885.0  466.72  4890.8  465.99  4968.4  464.90  4978.7  463.74
  4987.1  460.02  4987.3  459.52  4990.8  459.52  4991.1  460.02  4996.8  462.01
  4999.6  464.51  5002.7  462.01  5010.5  462.13  5020.1  465.15  5025.6  463.32
  5032.5  465.16  5043.0  466.23  5208.9  467.06  5237.3  467.89  5283.1  467.47
  5311.6  468.60  5329.8  470.01  5341.2  471.73  5351.9  471.99  5357.4  471.07
#Mann=4,-1,0
  4696.6    0.05       0  4987.1    0.05       0  4991.1    0.05       0
  5329.8    0.16       0
Bank Sta=4987.1,4991.1
Exp/Cntr=0.3,0.1

Chan Stop Cuts=-1