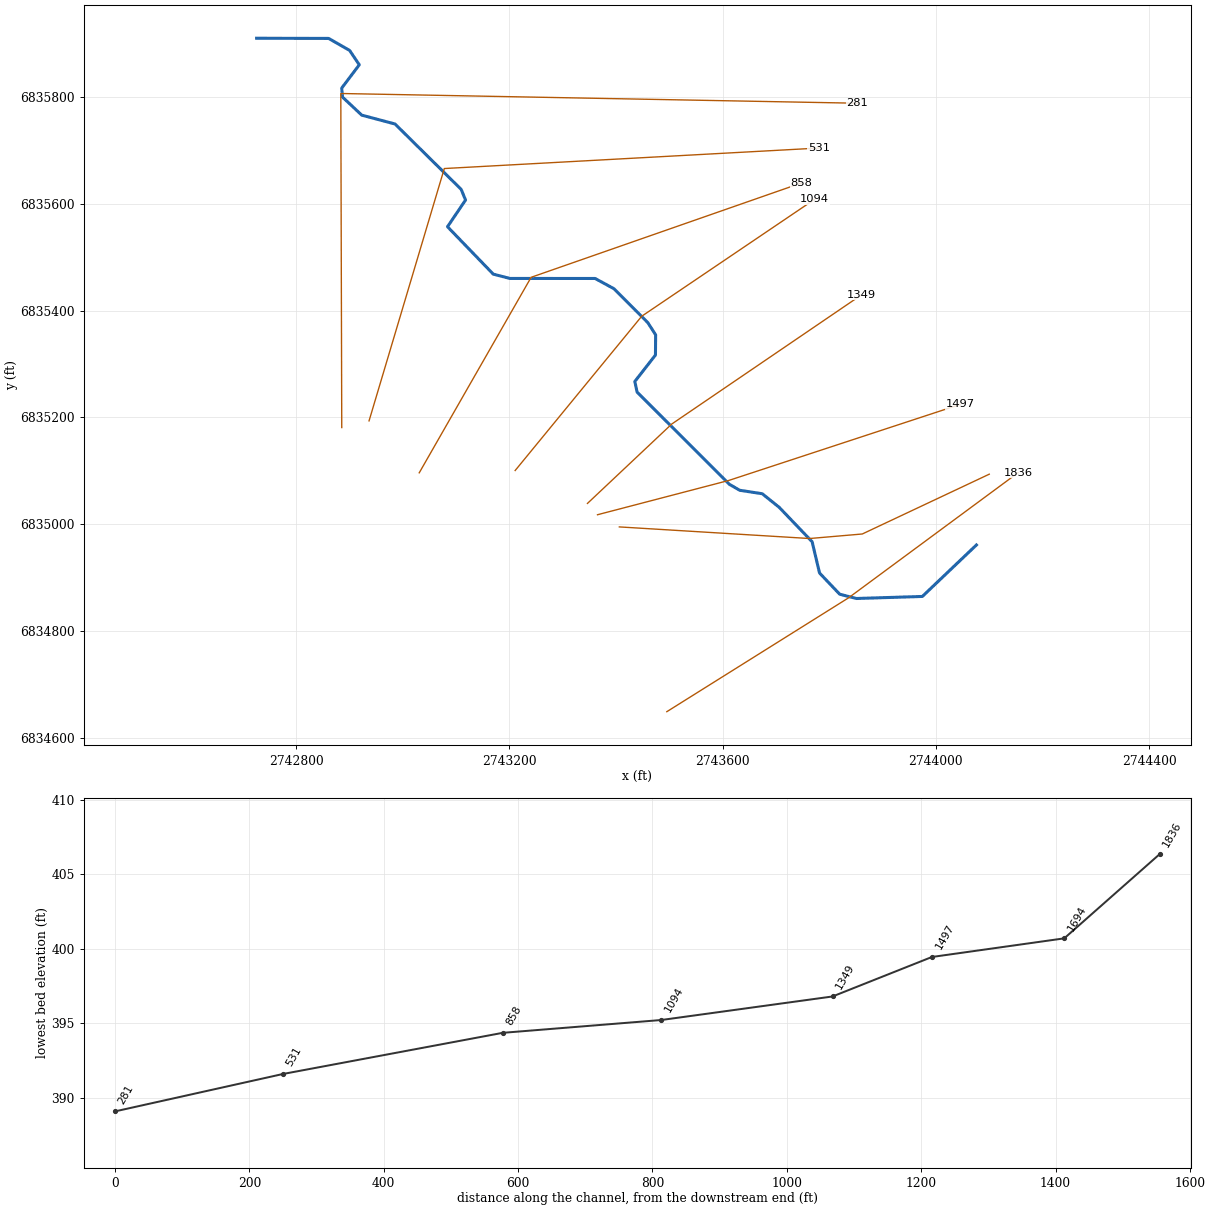
--- North Twin Creek Trib B.prj (project) ---

Proj Title=North Twin Creek Trib B Base Level Engineering
Current Plan=p01
Default Exp/Contr=0.3,0.1
English Units
Geom File=g01
Flow File=f01
Plan File=p01
BEGIN DESCRIPTION:
North Twin Creek Trib B
END DESCRIPTION:

--- North Twin Creek Trib B.p01 (plan) ---

Plan Title=Multiple Run
Short Identifier=Multiple
Geom File=g01
Flow File=f01
Subcritical Flow
K Sum by GR= 0
Std Step Tol= 0.01
Critical Tol= 0.01
Num of Std Step Trials= 20
Max Error Tol= 0.3
Flow Tol Ratio= 0.001
Split Flow NTrial= 30
Split Flow Tol= 0.02
Split Flow Ratio= 0.02
Log Output Level= 0
Friction Slope Method= 1
Unsteady Friction Slope Method= 2
Unsteady Bridges Friction Slope Method= 1
Parabolic Critical Depth
Global Vel Dist=  1 , 1 , 1
Global Log Level= 0
CheckData=True
Encroach Param= -1, 0, 0, 0
BEGIN DESCRIPTION:
Multiple Run
END DESCRIPTION:

--- North Twin Creek Trib B.f01 (steady flow) ---

Flow Title=Multiple
Number of Profiles=7
Profile Names=10-year,25-year,50-year,1pct_min,100-year,1pct_plu,500-year
River Rch & RM= North Twin Creek,Reach-1,1836
     334     436     516     304     607    1211     841
Boundary for River Rch & Prof#=North Twin Creek,Reach-1,1
Up Type=0
Dn Type=3
Dn Slope=0.005
Boundary for River Rch & Prof#=North Twin Creek,Reach-1,2
Up Type=0
Dn Type=3
Dn Slope=0.005
Boundary for River Rch & Prof#=North Twin Creek,Reach-1,3
Up Type=0
Dn Type=3
Dn Slope=0.005
Boundary for River Rch & Prof#=North Twin Creek,Reach-1,4
Up Type=0
Dn Type=3
Dn Slope=0.005
Boundary for River Rch & Prof#=North Twin Creek,Reach-1,5
Up Type=0
Dn Type=3
Dn Slope=0.005
Boundary for River Rch & Prof#=North Twin Creek,Reach-1,6
Up Type=0
Dn Type=3
Dn Slope=0.005
Boundary for River Rch & Prof#=North Twin Creek,Reach-1,7
Up Type=0
Dn Type=3
Dn Slope=0.005

--- North Twin Creek Trib B.g01 (geometry) ---

Geom Title=Existing Conditions

River Reach=North Twin Creek,Reach-1
Reach XY= 30
      2744076.00      6834961.00      2743974.55      6834864.48
      2743850.80      6834860.64      2743819.53      6834868.69
      2743781.74      6834908.43      2743767.84      6834967.04
      2743706.23      6835031.42      2743674.36      6835057.03
      2743632.05      6835063.54      2743612.79      6835074.63
      2743439.54      6835247.62      2743435.33      6835267.55
      2743474.01      6835317.05      2743474.35      6835354.96
      2743459.79      6835377.71      2743396.21      6835441.41
      2743360.85      6835460.62      2743200.87      6835460.71
      2743169.77      6835468.81      2743084.00      6835557.65
      2743117.84      6835607.67      2743109.61      6835627.67
      2742985.65      6835750.22      2742923.17      6835766.86
      2742887.11      6835800.69      2742885.56      6835817.53
      2742918.54      6835861.23      2742900.44      6835888.14
      2742861.16      6835910.69      2742726.00      6835911.00

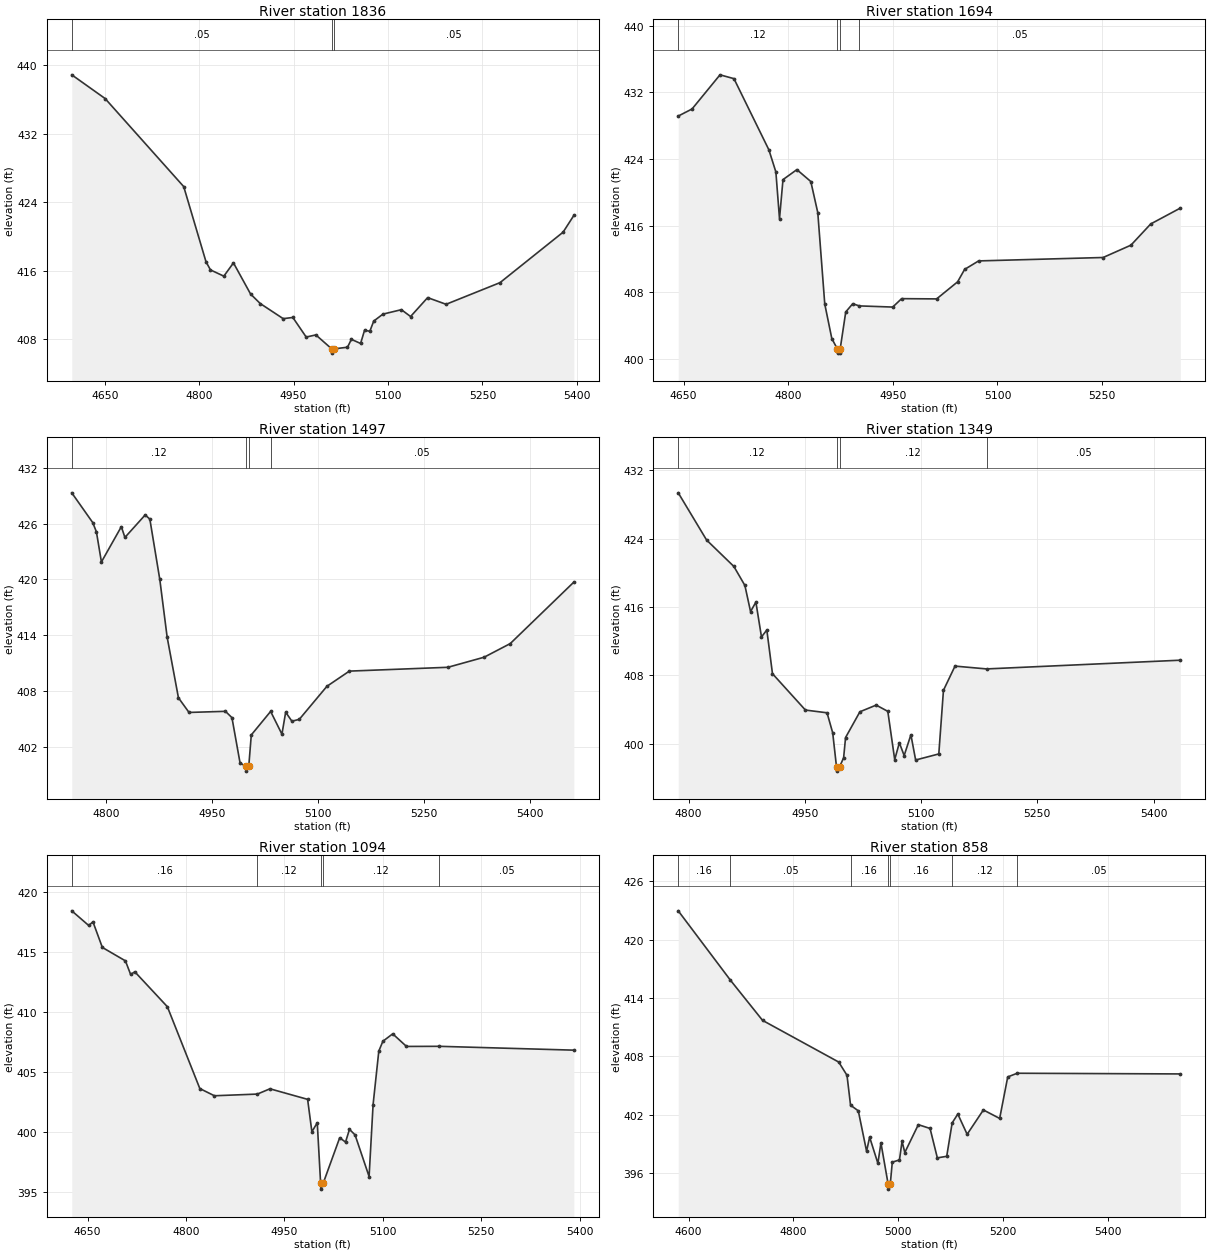
Type RM Length L Ch R = 1,1836,142,142,142
BEGIN DESCRIPTION:
North Twin Creek Trib B1835.977
END DESCRIPTION:
XS GIS Cut Line= 3
      2743495.34      6834648.44      2743836.29      6834861.97
      2744154.20      6835096.57
#Sta/Elev= 30
  4597.7  438.90  4650.6  436.13  4775.5  425.83  4810.9  417.04  4818.0  416.09
  4839.2  415.36  4854.5  416.91  4881.7  413.27  4897.0  412.16  4933.5  410.39
  4948.8  410.53  4970.0  408.24  4985.4  408.49  5010.5  406.86  5010.8  406.36
  5014.5  406.86  5035.6  407.05  5041.8  407.97  5056.4  407.49  5062.7  409.03
  5071.1  408.92  5077.3  410.11  5091.9  410.92  5121.2  411.44  5135.8  410.64
  5162.9  412.85  5192.2  412.07  5277.8  414.60  5378.0  420.50  5395.1  422.46
#Mann=3,-1,0
  4597.7    0.05       0  5010.5    0.05       0  5014.5    0.05       0
Bank Sta=5010.5,5014.5
Exp/Cntr=0.3,0.1

Type RM Length L Ch R = 1,1694,197,197,197
BEGIN DESCRIPTION:
North Twin Creek Trib B1694.1
END DESCRIPTION:
XS GIS Cut Line= 4
      2743406.25      6834994.86      2743763.12      6834973.08
      2743861.92      6834981.58      2744100.04      6835093.71
#Sta/Elev= 30
  4642.3  429.17  4662.1  430.02  4702.2  434.12  4722.2  433.66  4772.3  425.11
  4782.3  422.46  4787.5  416.84  4792.5  421.54  4812.4  422.74  4832.4  421.31
  4842.4  417.57  4852.4  406.60  4862.5  402.46  4870.5  401.21  4870.7  400.71
  4874.2  400.71  4874.5  401.21  4882.5  405.66  4892.5  406.64  4901.8  406.38
  4949.8  406.24  4962.6  407.25  5012.8  407.22  5042.9  409.27  5052.9  410.76
  5073.0  411.78  5251.5  412.19  5291.4  413.67  5319.8  416.22  5362.2  418.12
#Mann=4,-1,0
  4642.3    0.12       0  4870.5    0.05       0  4874.5    0.12       0
  4901.8    0.05       0
Bank Sta=4870.5,4874.5
Exp/Cntr=0.3,0.1

Type RM Length L Ch R = 1,1497,148,148,148
BEGIN DESCRIPTION:
North Twin Creek Trib B1497.13
END DESCRIPTION:
XS GIS Cut Line= 3
      2743365.33      6835017.69      2743611.74      6835082.03
      2744045.48      6835224.46
#Sta/Elev= 30
  4751.1  429.29  4780.8  426.10  4786.0  425.11  4793.1  421.88  4821.3  425.66
  4826.4  424.51  4855.1  426.92  4861.7  426.47  4875.8  420.00  4886.2  413.82
  4902.2  407.32  4917.2  405.75  4968.8  405.87  4978.0  405.19  4989.5  400.33
  4997.8  399.96  4998.1  399.46  5001.8  399.96  5005.4  403.34  5032.8  405.86
  5048.8  403.42  5054.1  405.78  5062.9  404.81  5073.4  405.01  5112.5  408.55
  5144.3  410.18  5283.9  410.59  5335.2  411.67  5372.2  413.13  5462.3  419.72
#Mann=4,-1,0
  4751.1    0.12       0  4997.8    0.07       0  5001.8    0.12       0
  5032.8    0.05       0
Bank Sta=4997.8,5001.8
Exp/Cntr=0.3,0.1

Type RM Length L Ch R = 1,1349,255,255,255
BEGIN DESCRIPTION:
North Twin Creek Trib B1349.39
END DESCRIPTION:
XS GIS Cut Line= 3
      2743346.45      6835038.88      2743504.52      6835187.70
      2743860.58      6835430.03
#Sta/Elev= 30
  4786.7  429.35  4823.3  423.83  4858.5  420.74  4872.7  418.52  4880.0  415.47
  4886.9  416.57  4894.1  412.50  4901.0  413.31  4908.3  408.20  4950.8  403.95
  4978.7  403.63  4986.0  401.29  4990.9  397.31  4991.1  396.81  4994.9  397.31
  5000.1  398.38  5002.6  400.74  5021.1  403.75  5042.1  404.53  5057.1  403.80
  5066.0  398.16  5072.0  400.12  5078.2  398.63  5086.9  401.06  5093.0  398.11
  5122.9  398.82  5128.9  406.26  5143.8  409.09  5184.6  408.76  5434.5  409.78
#Mann=4,-1,0
  4786.7    0.12       0  4990.9    0.07       0  4994.9    0.12       0
  5184.6    0.05       0
Bank Sta=4990.9,4994.9
Exp/Cntr=0.3,0.1

Type RM Length L Ch R = 1,1094,236,236,236
BEGIN DESCRIPTION:
North Twin Creek Trib B1093.7
END DESCRIPTION:
XS GIS Cut Line= 3
      2743210.90      6835100.59      2743448.26      6835389.84
      2743772.30      6835608.88
#Sta/Elev= 30
  4626.0  418.42  4651.8  417.20  4658.3  417.50  4672.6  415.37  4707.8  414.25
  4715.7  413.12  4722.1  413.34  4771.7  410.43  4821.2  403.61  4843.4  403.01
  4908.9  403.15  4928.1  403.59  4985.5  402.71  4992.0  400.01  5000.2  400.76
  5005.3  395.73  5005.6  395.23  5009.3  395.73  5034.4  399.51  5043.3  399.15
  5049.3  400.21  5057.8  399.75  5079.2  396.28  5085.3  402.28  5094.0  406.73
  5100.2  407.55  5115.2  408.17  5136.2  407.12  5186.3  407.13  5391.3  406.81
#Mann=5,-1,0
  4626.0    0.16       0  4908.9    0.12       0  5005.3    0.07       0
  5009.3    0.12       0  5186.3    0.05       0
Bank Sta=5005.3,5009.3
Exp/Cntr=0.3,0.1

Type RM Length L Ch R = 1,858,327,327,327
BEGIN DESCRIPTION:
North Twin Creek Trib B857.92
END DESCRIPTION:
XS GIS Cut Line= 3
      2743030.99      6835096.27      2743240.81      6835462.81
      2743747.14      6835639.43
#Sta/Elev= 30
  4580.1  422.95  4679.7  415.83  4741.1  411.70  4886.5  407.42  4902.3  406.06
  4909.1  402.99  4923.9  402.41  4939.7  398.26  4945.5  399.71  4961.3  397.02
  4967.1  399.12  4980.9  394.87  4981.1  394.37  4984.9  394.87  4988.8  397.14
  5002.5  397.37  5007.4  399.28  5012.7  398.13  5038.5  400.99  5060.9  400.60
  5074.8  397.58  5092.7  397.74  5103.1  401.17  5113.9  402.08  5131.7  400.00
  5162.7  402.50  5193.8  401.63  5209.2  405.89  5227.2  406.27  5538.7  406.20
#Mann=7,-1,0
  4580.1    0.16       0  4679.7    0.05       0  4909.1    0.16       0
  4980.9    0.07       0  4984.9    0.16       0  5103.1    0.12       0
  5227.2    0.05       0
Bank Sta=4980.9,4984.9
Exp/Cntr=0.3,0.1

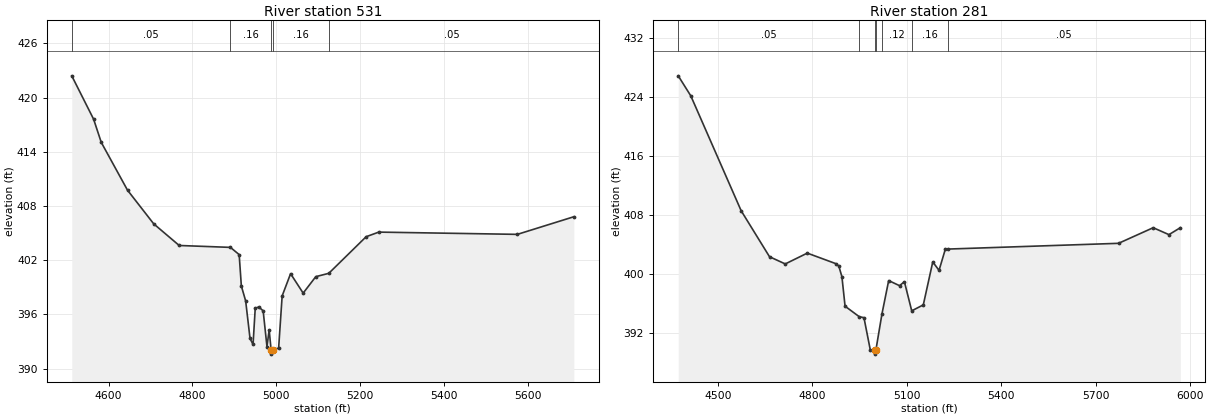
Type RM Length L Ch R = 1,531,250,250,250
BEGIN DESCRIPTION:
North Twin Creek Trib B530.6
END DESCRIPTION:
XS GIS Cut Line= 3
      2742936.85      6835193.63      2743077.99      6835666.74
      2743780.53      6835705.18
#Sta/Elev= 30
  4512.1  422.40  4564.2  417.60  4582.4  415.04  4645.0  409.75  4707.6  406.02
  4768.3  403.63  4890.5  403.42  4911.3  402.62  4916.5  399.15  4926.8  397.49
  4937.2  393.34  4944.4  392.68  4949.6  396.68  4958.1  396.83  4968.5  396.40
  4977.6  392.44  4982.8  394.30  4987.4  392.11  4987.6  391.61  4991.4  392.11
  5005.4  392.27  5013.8  398.05  5033.9  400.51  5063.9  398.36  5094.0  400.18
  5125.0  400.55  5214.1  404.60  5244.2  405.11  5574.7  404.86  5709.4  406.81
#Mann=5,-1,0
  4512.1    0.05       0  4890.5    0.16       0  4987.4    0.07       0
  4991.4    0.16       0  5125.0    0.05       0
Bank Sta=4987.4,4991.4
Exp/Cntr=0.3,0.1

Type RM Length L Ch R = 1,281,0,0,0
BEGIN DESCRIPTION:
North Twin Creek Trib B280.572
END DESCRIPTION:
XS GIS Cut Line= 3
      2742885.66      6835181.13      2742883.90      6835807.43
      2743852.13      6835789.20
#Sta/Elev= 30
  4373.7  426.90  4413.6  424.18  4573.6  408.57  4663.6  402.33  4713.6  401.35
  4783.6  402.82  4873.6  401.40  4883.6  401.08  4893.6  399.61  4903.6  395.61
  4948.4  394.19  4963.6  394.05  4983.6  389.70  4997.3  389.60  4997.5  389.10
  5001.3  389.60  5020.8  394.57  5042.1  399.09  5076.5  398.40  5092.1  398.93
  5115.3  394.98  5152.1  395.79  5182.1  401.62  5202.1  400.48  5222.1  403.36
  5230.6  403.37  5772.2  404.15  5882.3  406.27  5932.3  405.33  5968.4  406.27
#Mann=7,-1,0
  4373.7    0.05       0  4948.4    0.16       0  4997.3    0.07       0
  5001.3    0.16       0  5020.8    0.12       0  5115.3    0.16       0
  5230.6    0.05       0
Bank Sta=4997.3,5001.3
Exp/Cntr=0.3,0.1

Chan Stop Cuts=-1