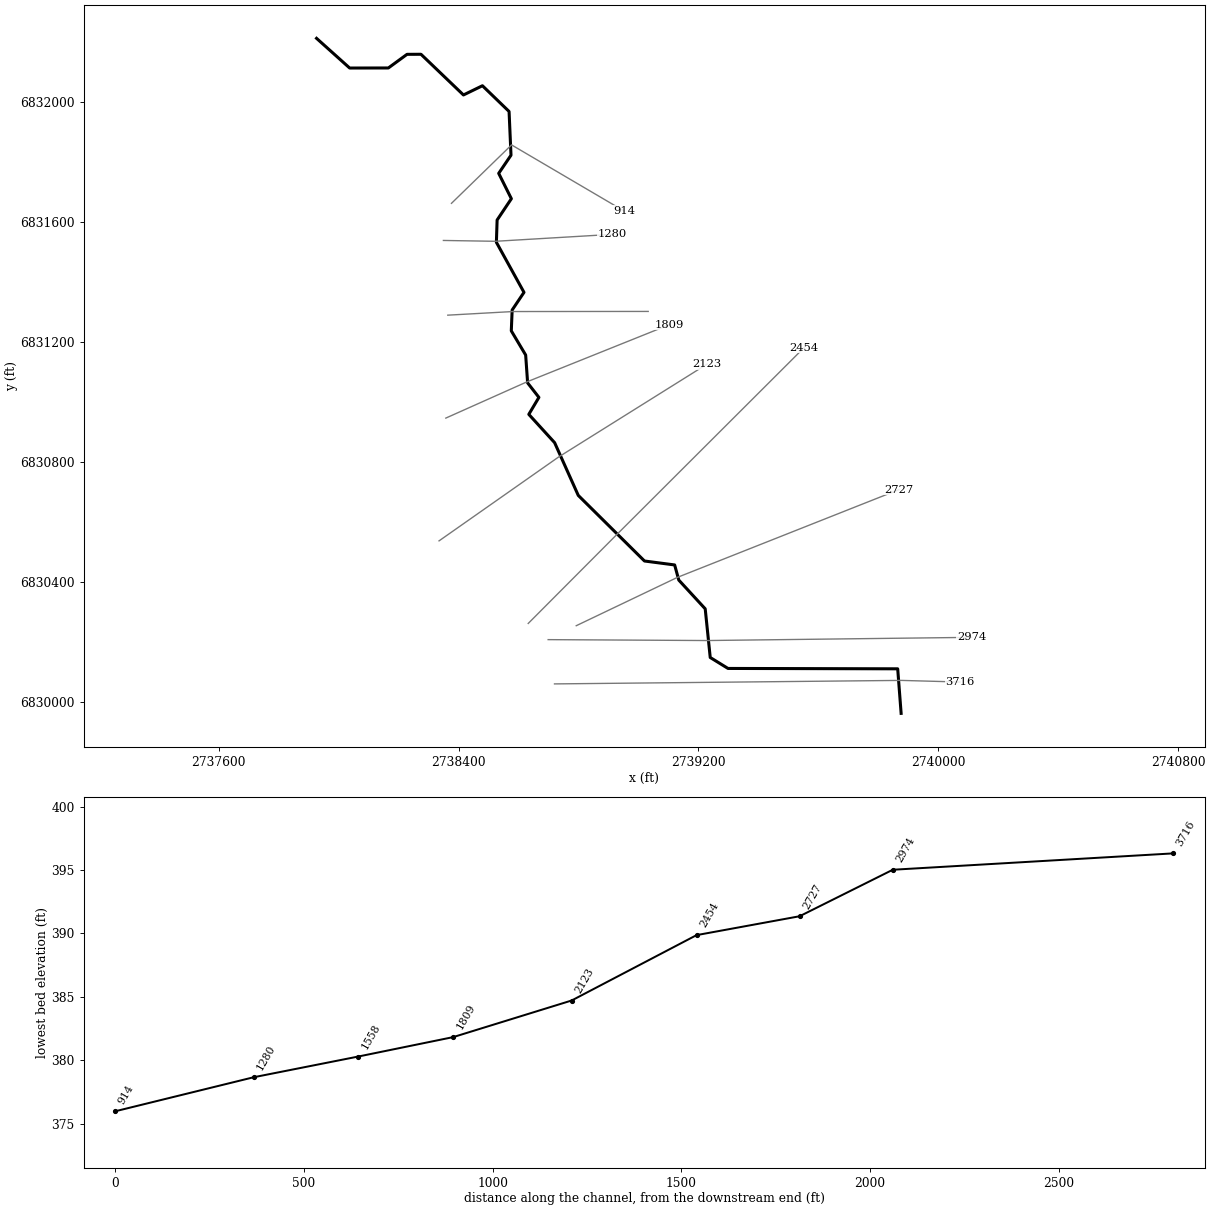
--- North Twin Creek Trib C.prj (project) ---

Proj Title=North Twin Creek Trib C Base Level Engineering
Current Plan=p01
Default Exp/Contr=0.3,0.1
English Units
Geom File=g01
Flow File=f01
Plan File=p01
BEGIN DESCRIPTION:
North Twin Creek Trib C
END DESCRIPTION:

--- North Twin Creek Trib C.p01 (plan) ---

Plan Title=Multiple Run
Short Identifier=Multiple
Geom File=g01
Flow File=f01
Subcritical Flow
K Sum by GR= 0
Std Step Tol= 0.01
Critical Tol= 0.01
Num of Std Step Trials= 20
Max Error Tol= 0.3
Flow Tol Ratio= 0.001
Split Flow NTrial= 30
Split Flow Tol= 0.02
Split Flow Ratio= 0.02
Log Output Level= 0
Friction Slope Method= 1
Unsteady Friction Slope Method= 2
Unsteady Bridges Friction Slope Method= 1
Parabolic Critical Depth
Global Vel Dist=  1 , 1 , 1
Global Log Level= 0
CheckData=True
Encroach Param= -1, 0, 0, 0
BEGIN DESCRIPTION:
Multiple Run
END DESCRIPTION:

--- North Twin Creek Trib C.f01 (steady flow) ---

Flow Title=Multiple
Number of Profiles=7
Profile Names=10-year,25-year,50-year,1pct_min,100-year,1pct_plu,500-year
River Rch & RM= North Twin Creek,Reach-1,3716
     438     581     696     415     828    1652    1174
Boundary for River Rch & Prof#=North Twin Creek,Reach-1,1
Up Type=0
Dn Type=3
Dn Slope=0.005
Boundary for River Rch & Prof#=North Twin Creek,Reach-1,2
Up Type=0
Dn Type=3
Dn Slope=0.005
Boundary for River Rch & Prof#=North Twin Creek,Reach-1,3
Up Type=0
Dn Type=3
Dn Slope=0.005
Boundary for River Rch & Prof#=North Twin Creek,Reach-1,4
Up Type=0
Dn Type=3
Dn Slope=0.005
Boundary for River Rch & Prof#=North Twin Creek,Reach-1,5
Up Type=0
Dn Type=3
Dn Slope=0.005
Boundary for River Rch & Prof#=North Twin Creek,Reach-1,6
Up Type=0
Dn Type=3
Dn Slope=0.005
Boundary for River Rch & Prof#=North Twin Creek,Reach-1,7
Up Type=0
Dn Type=3
Dn Slope=0.005

--- North Twin Creek Trib C.g01 (geometry) ---

Geom Title=Existing Conditions

River Reach=North Twin Creek,Reach-1
Reach XY= 30
      2739876.00      6829961.00      2739864.55      6830109.55
      2739298.54      6830110.76      2739239.20      6830147.26
      2739222.45      6830309.53      2739134.32      6830405.30
      2739120.53      6830455.74      2739019.88      6830468.88
      2738799.01      6830687.53      2738720.14      6830863.30
      2738634.01      6830957.67      2738667.71      6831014.22
      2738630.08      6831062.50      2738623.53      6831155.43
      2738575.61      6831236.00      2738578.49      6831305.51
      2738617.95      6831364.32      2738525.89      6831531.09
      2738528.31      6831605.44      2738575.85      6831676.42
      2738533.59      6831760.99      2738574.63      6831821.44
      2738568.19      6831967.23      2738479.35      6832053.00
      2738416.00      6832022.24      2738274.37      6832157.87
      2738227.75      6832157.66      2738165.50      6832112.23
      2738036.43      6832112.01      2737926.00      6832211.00

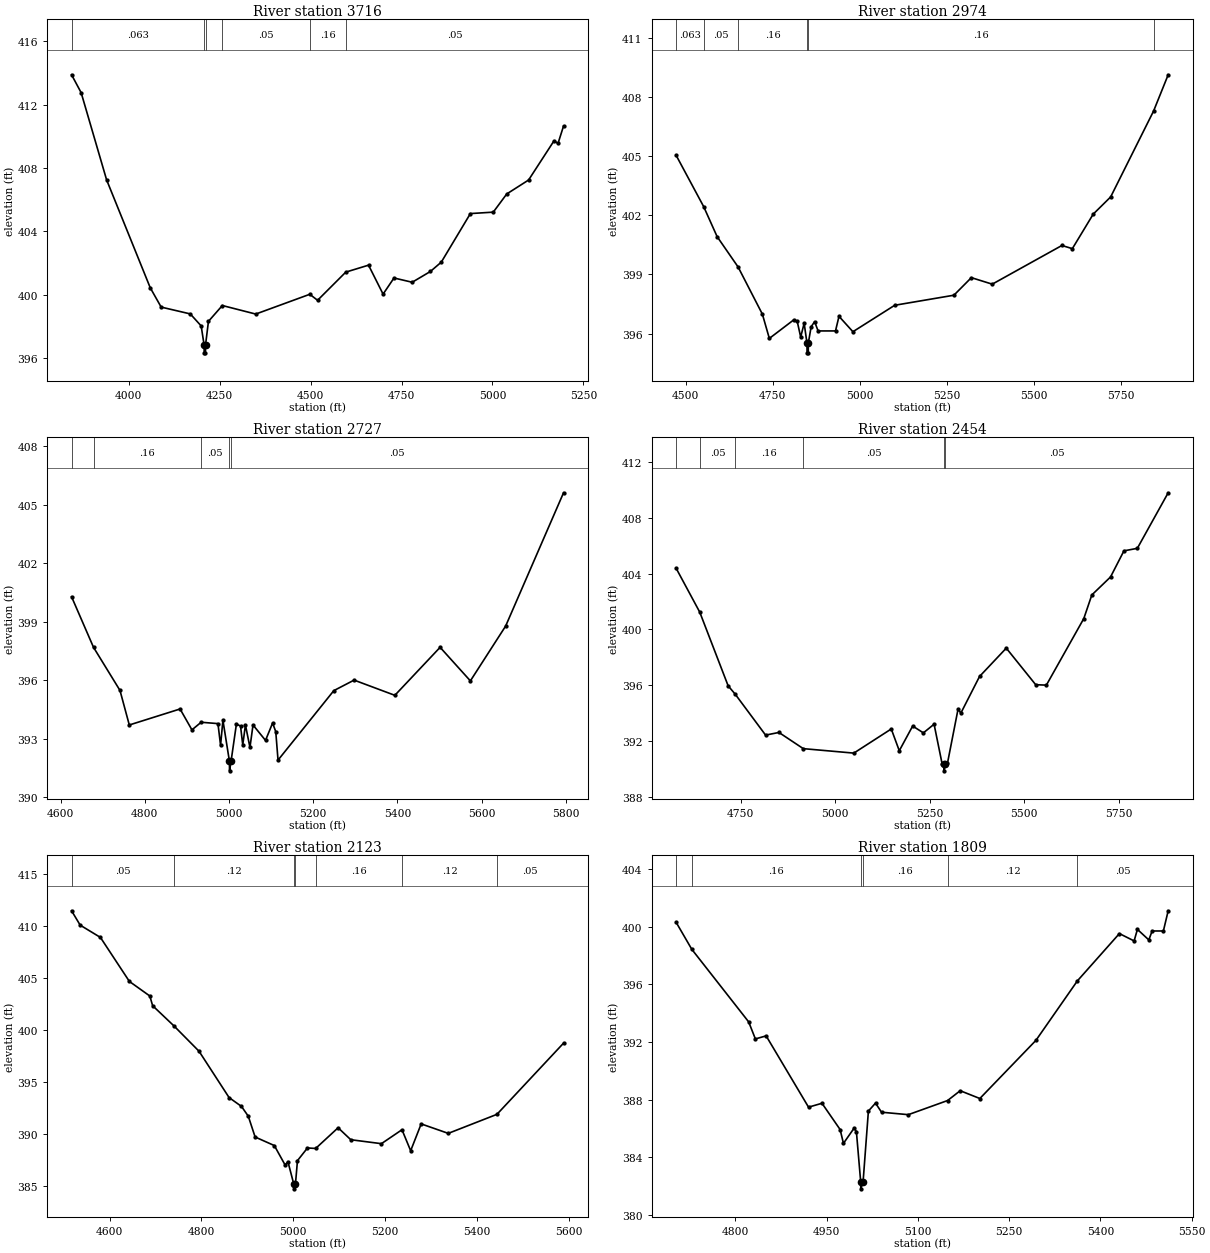
Type RM Length L Ch R = 1,3716,742,742,742
BEGIN DESCRIPTION:
North Twin Creek Trib C3634.61
END DESCRIPTION:
XS GIS Cut Line= 3
      2738719.69      6830059.23      2739876.83      6830070.92
      2740072.05      6830065.46
#Sta/Elev= 30
  3842.8  413.89  3869.1  412.76  3939.1  407.25  4059.1  400.43  4089.1  399.21
  4169.1  398.78  4199.1  398.02  4207.1  396.82  4207.4  396.32  4210.9  396.32
  4211.1  396.82  4219.1  398.31  4257.3  399.31  4349.1  398.77  4497.7  400.02
  4519.1  399.64  4596.6  401.42  4659.2  401.86  4699.2  400.03  4729.2  401.05
  4779.2  400.78  4829.2  401.46  4859.2  402.05  4939.2  405.12  5002.1  405.21
  5039.2  406.36  5099.2  407.24  5169.2  409.72  5180.1  409.55  5195.3  410.65
#Mann=6,-1,0
  3842.8   0.063       0  4207.1    0.05       0  4211.1   0.063       0
  4257.3    0.05       0  4497.7    0.16       0  4596.6    0.05       0
Bank Sta=4207.1,4211.1
Exp/Cntr=0.3,0.1

Type RM Length L Ch R = 1,2974,247,247,247
BEGIN DESCRIPTION:
Mapping XS 43a0a398
END DESCRIPTION:
XS GIS Cut Line= 3
      2738698.58      6830206.80      2739227.68      6830203.78
      2740111.21      6830214.41
#Sta/Elev= 30
  4473.0  405.03  4551.8  402.44  4590.4  400.92  4650.7  399.38  4720.4  396.99
  4740.4  395.76  4810.4  396.70  4820.4  396.63  4830.4  395.83  4840.4  396.53
  4848.4  395.53  4848.7  395.03  4852.2  395.03  4852.4  395.53  4860.4  396.35
  4870.4  396.61  4880.4  396.14  4930.4  396.14  4940.4  396.88  4980.4  396.10
  5100.4  397.44  5270.4  397.95  5320.5  398.84  5380.5  398.51  5580.5  400.47
  5610.5  400.31  5670.5  402.06  5720.5  402.93  5843.7  407.28  5885.7  409.12
#Mann=6,-1,0
  4473.0   0.063       0  4551.8    0.05       0  4650.7    0.16       0
  4848.4    0.05       0  4852.4    0.16       0  5843.7   0.063       0
Bank Sta=4848.4,4852.4
Exp/Cntr=0.3,0.1

Type RM Length L Ch R = 1,2727,273,273,273
BEGIN DESCRIPTION:
Mapping XS 1ea16084
END DESCRIPTION:
XS GIS Cut Line= 3
      2738792.26      6830253.19      2739130.09      6830414.47
      2739868.61      6830706.73
#Sta/Elev= 30
  4626.0  400.28  4678.1  397.69  4741.0  395.48  4763.1  393.71  4883.7  394.53
  4911.9  393.46  4933.8  393.85  4973.7  393.78  4979.9  392.67  4985.5  393.95
  5000.9  391.86  5001.2  391.36  5004.9  391.86  5017.5  393.75  5027.3  393.66
  5032.6  392.69  5039.0  393.71  5049.7  392.56  5057.0  393.71  5086.7  392.92
  5103.5  393.81  5111.0  393.37  5116.4  391.91  5248.9  395.47  5297.1  396.01
  5393.9  395.23  5501.4  397.69  5573.3  395.97  5657.1  398.78  5794.6  405.61
#Mann=5,-1,0
  4626.0    0.05       0  4678.1    0.16       0  4933.8    0.05       0
  5000.9    0.05       0  5004.9    0.05       0
Bank Sta=5000.9,5004.9
Exp/Cntr=0.3,0.1

Type RM Length L Ch R = 1,2454,331,331,331
BEGIN DESCRIPTION:
North Twin Creek Trib C2453.54
END DESCRIPTION:
XS GIS Cut Line= 3
      2738632.10      6830260.76      2738929.25      6830558.78
      2739552.33      6831180.13
#Sta/Elev= 30
  4579.9  404.37  4642.1  401.24  4717.2  395.96  4735.9  395.36  4816.2  392.43
  4851.5  392.62  4915.9  391.46  5049.5  391.14  5148.5  392.87  5169.7  391.31
  5205.1  393.08  5233.4  392.59  5261.7  393.21  5282.9  390.38  5287.9  390.37
  5288.2  389.87  5291.9  390.37  5297.0  390.40  5325.3  394.32  5332.4  394.00
  5381.9  396.63  5452.6  398.66  5530.4  396.04  5558.6  396.01  5657.6  400.78
  5678.8  402.47  5728.3  403.76  5763.7  405.63  5799.1  405.81  5880.7  409.79
#Mann=6,-1,0
  4579.9   0.063       0  4642.1    0.05       0  4735.9    0.16       0
  4915.9    0.05       0  5287.9    0.05       0  5291.9    0.05       0
Bank Sta=5287.9,5291.9
Exp/Cntr=0.3,0.1

Type RM Length L Ch R = 1,2123,314,314,314
BEGIN DESCRIPTION:
North Twin Creek Trib C2122.64
END DESCRIPTION:
XS GIS Cut Line= 3
      2738334.61      6830535.99      2738733.57      6830815.63
      2739228.83      6831125.29
#Sta/Elev= 30
  4517.1  411.43  4535.8  410.05  4579.9  408.87  4643.0  404.64  4687.5  403.24
  4693.6  402.31  4740.2  400.36  4794.7  397.93  4860.1  393.48  4887.1  392.63
  4901.9  391.69  4916.8  389.69  4958.6  388.87  4982.1  387.00  4988.2  387.33
  5000.7  385.21  5001.0  384.71  5004.7  385.21  5009.0  387.42  5030.8  388.64
  5048.6  388.59  5097.5  390.58  5125.1  389.43  5191.8  389.05  5236.6  390.39
  5255.5  388.37  5278.4  390.95  5337.4  390.04  5443.4  391.87  5588.4  398.71
#Mann=7,-1,0
  4517.1    0.05       0  4740.2    0.12       0  5000.7    0.07       0
  5004.7    0.12       0  5048.6    0.16       0  5236.6    0.12       0
  5443.4    0.05       0
Bank Sta=5000.7,5004.7
Exp/Cntr=0.3,0.1

Type RM Length L Ch R = 1,1809,251,251,251
BEGIN DESCRIPTION:
North Twin Creek Trib C1808.59
END DESCRIPTION:
XS GIS Cut Line= 3
      2738357.20      6830945.22      2738627.70      6831065.96
      2739103.36      6831256.69
#Sta/Elev= 30
  4702.7  400.28  4728.3  398.42  4821.8  393.39  4832.8  392.21  4850.5  392.42
  4920.2  387.48  4942.3  387.75  4972.1  385.93  4977.6  384.97  4995.3  386.04
  4998.9  385.78  5005.9  382.32  5006.1  381.82  5009.9  382.32  5018.6  387.21
  5030.3  387.76  5040.2  387.13  5084.2  386.96  5148.8  387.94  5169.5  388.62
  5201.8  388.08  5294.0  392.11  5362.1  396.23  5431.2  399.51  5455.4  399.00
  5460.8  399.80  5479.6  399.07  5485.0  399.69  5503.5  399.69  5511.4  401.09
#Mann=6,-1,0
  4702.7    0.05       0  4728.3    0.16       0  5005.9    0.07       0
  5009.9    0.16       0  5148.8    0.12       0  5362.1    0.05       0
Bank Sta=5005.9,5009.9
Exp/Cntr=0.3,0.1

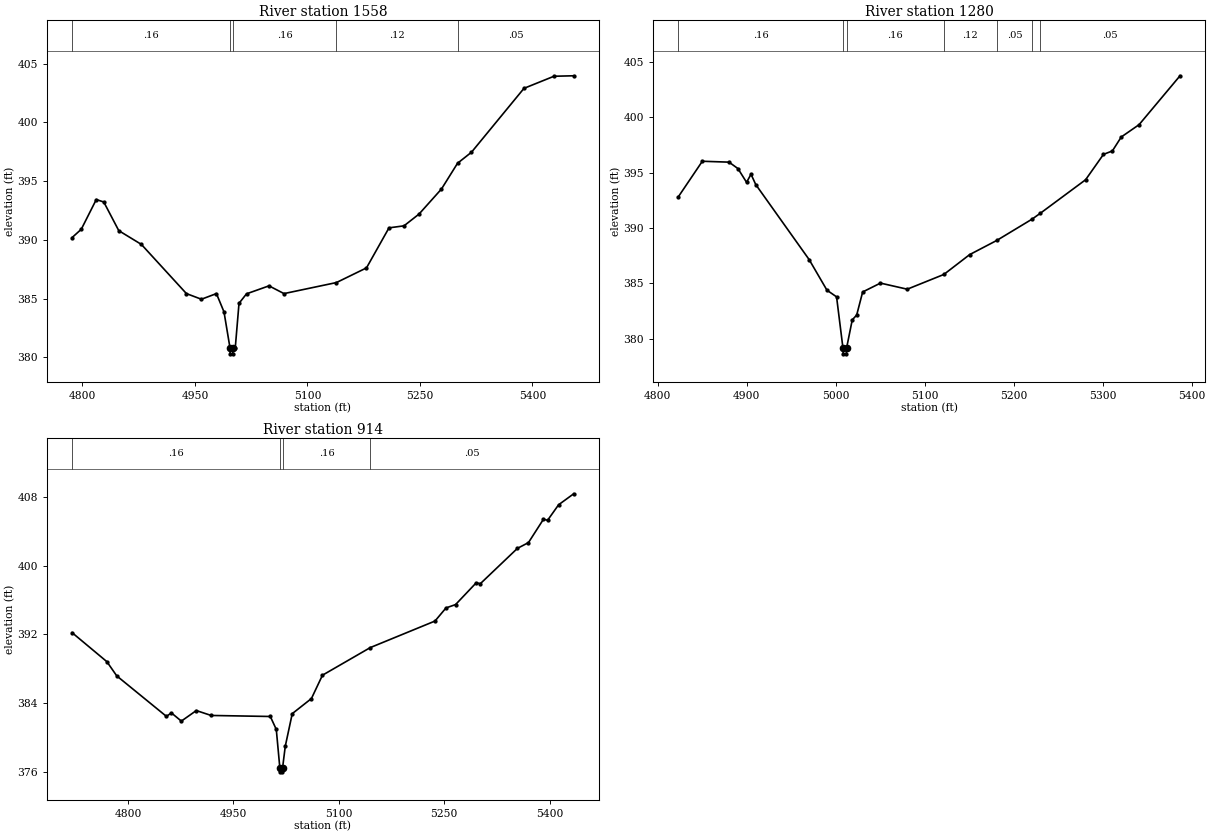
Type RM Length L Ch R = 1,1558,278,278,278
BEGIN DESCRIPTION:
North Twin Creek Trib C1558.34
END DESCRIPTION:
XS GIS Cut Line= 3
      2738363.76      6831288.29      2738580.99      6831300.37
      2739032.32      6831300.74
#Sta/Elev= 30
  4786.2  390.19  4798.5  390.90  4818.5  393.43  4828.5  393.22  4848.5  390.78
  4878.6  389.61  4938.7  385.42  4958.7  384.94  4978.7  385.42  4988.8  383.86
  4996.8  380.79  4997.0  380.29  5000.5  380.29  5000.8  380.79  5003.8  380.79
  5008.8  384.59  5018.8  385.40  5048.8  386.08  5068.8  385.42  5138.7  386.36
  5178.8  387.61  5208.8  391.02  5228.8  391.19  5248.8  392.19  5278.8  394.33
  5300.2  396.52  5318.8  397.46  5388.8  402.90  5428.8  403.93  5455.1  403.97
#Mann=5,-1,0
  4786.2    0.16       0  4996.8    0.07       0  5000.8    0.16       0
  5138.7    0.12       0  5300.2    0.05       0
Bank Sta=4996.8,5000.8
Exp/Cntr=0.3,0.1

Type RM Length L Ch R = 1,1280,366,366,366
BEGIN DESCRIPTION:
North Twin Creek Trib C1280.09
END DESCRIPTION:
XS GIS Cut Line= 3
      2738349.10      6831537.32      2738522.52      6831534.51
      2738911.89      6831557.58
#Sta/Elev= 30
  4823.4  392.82  4850.3  396.02  4880.3  395.94  4890.3  395.36  4900.0  394.12
  4905.0  394.85  4910.3  393.92  4970.3  387.15  4990.3  384.39  5001.1  383.79
  5008.3  379.15  5008.6  378.65  5012.1  378.65  5012.3  379.15  5018.7  381.71
  5023.7  382.15  5030.4  384.23  5050.4  385.03  5080.5  384.48  5121.6  385.81
  5150.6  387.60  5181.1  388.88  5220.7  390.80  5230.0  391.33  5280.8  394.35
  5300.9  396.64  5310.9  396.95  5320.9  398.21  5340.9  399.32  5386.9  403.73
#Mann=7,-1,0
  4823.4    0.16       0  5008.3    0.07       0  5012.3    0.16       0
  5121.6    0.12       0  5181.1    0.05       0  5220.7    0.12       0
  5230.0    0.05       0
Bank Sta=5008.3,5012.3
Exp/Cntr=0.3,0.1

Type RM Length L Ch R = 1,914,0,0,0
BEGIN DESCRIPTION:
North Twin Creek Trib C914.346
END DESCRIPTION:
XS GIS Cut Line= 3
      2738376.03      6831661.03      2738576.46      6831855.83
      2738951.01      6831635.99
#Sta/Elev= 30
  4720.5  392.19  4770.0  388.81  4784.1  387.15  4854.8  382.43  4861.8  382.84
  4876.0  381.88  4897.3  383.11  4918.4  382.54  5002.6  382.42  5011.1  380.91
  5016.1  376.47  5016.4  375.97  5019.9  375.97  5020.1  376.47  5023.9  378.96
  5033.8  382.75  5061.1  384.51  5076.8  387.23  5144.9  390.45  5236.9  393.54
  5252.6  395.07  5266.2  395.46  5295.6  398.00  5301.4  397.89  5354.2  402.01
  5369.9  402.68  5391.3  405.41  5397.1  405.28  5412.8  407.09  5434.3  408.37
#Mann=4,-1,0
  4720.5    0.16       0  5016.1    0.07       0  5020.1    0.16       0
  5144.9    0.05       0
Bank Sta=5016.1,5020.1
Exp/Cntr=0.3,0.1

Chan Stop Cuts=-1