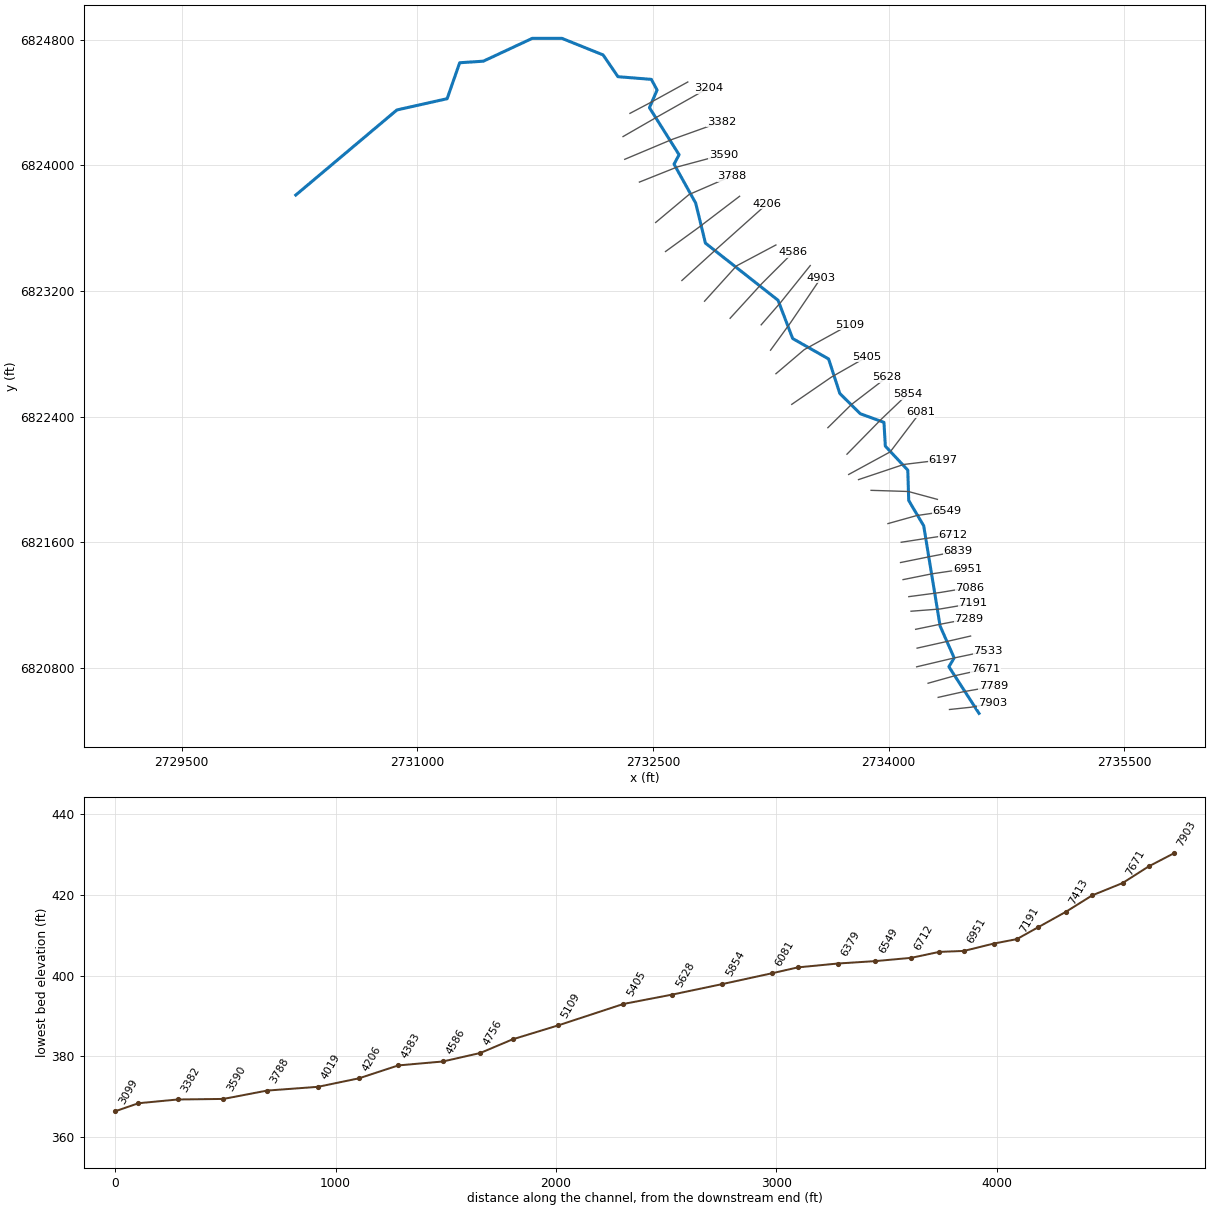
--- North Twin Creek Trib D.prj (project) ---

Proj Title=North Twin Creek Trib D Base Level Engineering
Current Plan=p01
Default Exp/Contr=0.3,0.1
English Units
Geom File=g01
Flow File=f01
Plan File=p01
BEGIN DESCRIPTION:
North Twin Creek Trib D
END DESCRIPTION:

--- North Twin Creek Trib D.p01 (plan) ---

Plan Title=Multiple Run
Short Identifier=Multiple
Geom File=g01
Flow File=f01
Subcritical Flow
K Sum by GR= 0
Std Step Tol= 0.01
Critical Tol= 0.01
Num of Std Step Trials= 20
Max Error Tol= 0.3
Flow Tol Ratio= 0.001
Split Flow NTrial= 30
Split Flow Tol= 0.02
Split Flow Ratio= 0.02
Log Output Level= 0
Friction Slope Method= 1
Unsteady Friction Slope Method= 2
Unsteady Bridges Friction Slope Method= 1
Parabolic Critical Depth
Global Vel Dist=  1 , 1 , 1
Global Log Level= 0
CheckData=True
Encroach Param= -1, 0, 0, 0
BEGIN DESCRIPTION:
Multiple Run
END DESCRIPTION:

--- North Twin Creek Trib D.f01 (steady flow) ---

Flow Title=Multiple
Number of Profiles=7
Profile Names=10-year,25-year,50-year,1pct_min,100-year,1pct_plu,500-year
River Rch & RM= North Twin Creek,Reach-1,7903
     421     551     654     385     769    1534    1061
Boundary for River Rch & Prof#=North Twin Creek,Reach-1,1
Up Type=0
Dn Type=3
Dn Slope=0.005
Boundary for River Rch & Prof#=North Twin Creek,Reach-1,2
Up Type=0
Dn Type=3
Dn Slope=0.005
Boundary for River Rch & Prof#=North Twin Creek,Reach-1,3
Up Type=0
Dn Type=3
Dn Slope=0.005
Boundary for River Rch & Prof#=North Twin Creek,Reach-1,4
Up Type=0
Dn Type=3
Dn Slope=0.005
Boundary for River Rch & Prof#=North Twin Creek,Reach-1,5
Up Type=0
Dn Type=3
Dn Slope=0.005
Boundary for River Rch & Prof#=North Twin Creek,Reach-1,6
Up Type=0
Dn Type=3
Dn Slope=0.005
Boundary for River Rch & Prof#=North Twin Creek,Reach-1,7
Up Type=0
Dn Type=3
Dn Slope=0.005

--- North Twin Creek Trib D.g01 (geometry) ---

Geom Title=Existing Conditions

River Reach=North Twin Creek,Reach-1
Reach XY= 30
      2734576.00      6820511.00      2734384.24      6820807.77
      2734417.72      6820864.22      2734328.26      6821066.94
      2734223.75      6821705.07      2734128.35      6821866.52
      2734122.46      6822059.54      2733979.54      6822212.47
      2733970.65      6822363.73      2733819.83      6822418.86
      2733689.62      6822547.78      2733618.27      6822767.50
      2733389.39      6822897.67      2733296.39      6823141.16
      2732834.13      6823504.93      2732772.24      6823759.44
      2732634.24      6824007.77      2732666.42      6824067.55
      2732477.80      6824367.11      2732526.24      6824479.59
      2732489.83      6824547.50      2732277.28      6824564.52
      2732182.45      6824703.25      2731920.07      6824808.76
      2731731.94      6824808.74      2731420.07      6824663.25
      2731269.48      6824653.32      2731189.64      6824424.44
      2730869.95      6824352.88      2730226.00      6823811.00

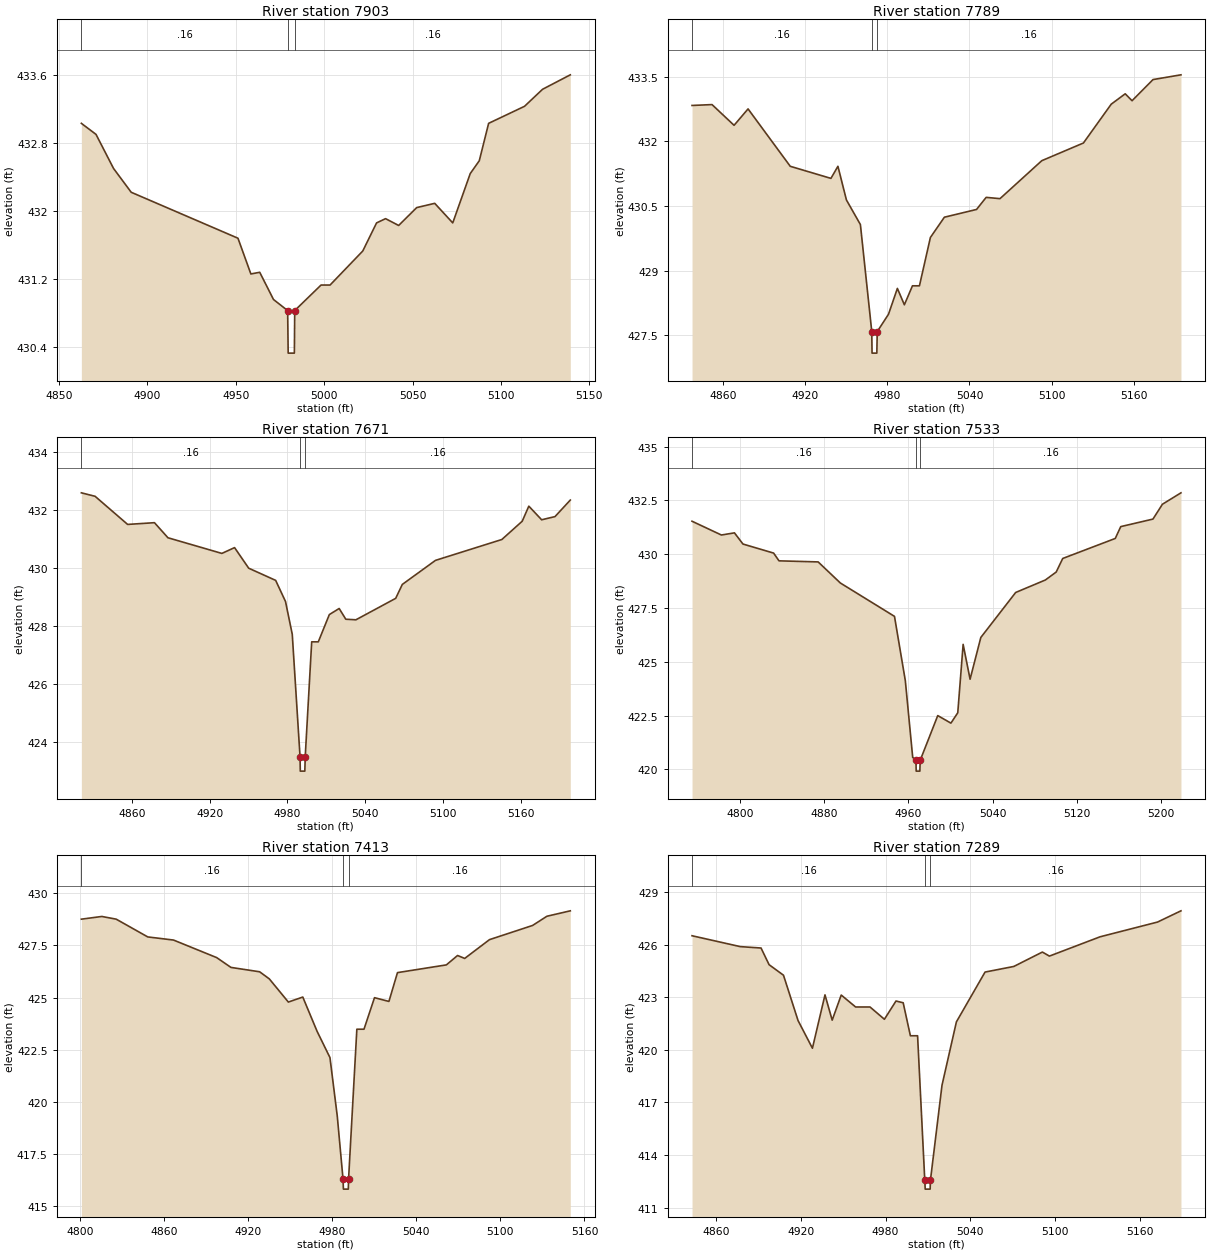
Type RM Length L Ch R = 1,7903,114,114,114
BEGIN DESCRIPTION:
North Twin Creek Trib D7903.16
END DESCRIPTION:
XS GIS Cut Line= 3
      2734387.92      6820535.63      2734524.55      6820550.13
      2734661.44      6820575.36
#Sta/Elev= 27
  4862.6  433.03  4870.9  432.90  4880.8  432.50  4890.8  432.22  4951.2  431.68
  4958.5  431.26  4963.5  431.28  4971.3  430.96  4979.3  430.83  4979.6  430.33
  4983.1  430.33  4983.3  430.83  4998.2  431.13  5003.3  431.13  5021.8  431.53
  5029.6  431.86  5034.7  431.91  5042.1  431.83  5052.3  432.04  5062.5  432.09
  5072.7  431.86  5082.6  432.44  5087.7  432.59  5093.0  433.03  5113.3  433.23
  5123.5  433.43  5139.2  433.60
#Mann=3,-1,0
  4862.6    0.16       0  4979.3    0.07       0  4983.3    0.16       0
Bank Sta=4979.3,4983.3
Exp/Cntr=0.3,0.1

Type RM Length L Ch R = 1,7789,118,118,118
BEGIN DESCRIPTION:
North Twin Creek Trib D7789.18
END DESCRIPTION:
XS GIS Cut Line= 3
      2734316.06      6820612.96      2734475.15      6820648.58
      2734666.08      6820682.19
#Sta/Elev= 30
  4837.5  432.83  4852.1  432.85  4868.2  432.37  4878.4  432.75  4909.2  431.42
  4938.9  431.14  4944.0  431.42  4950.2  430.64  4960.4  430.07  4968.7  427.59
  4968.9  427.09  4972.4  427.09  4972.7  427.59  4980.9  427.99  4987.4  428.59
  4992.5  428.21  4998.4  428.65  5003.5  428.65  5011.5  429.77  5021.7  430.24
  5045.2  430.42  5052.2  430.70  5062.3  430.67  5092.8  431.55  5123.2  431.96
  5143.5  432.86  5153.7  433.10  5158.7  432.94  5174.0  433.43  5194.4  433.54
#Mann=3,-1,0
  4837.5    0.16       0  4968.7    0.07       0  4972.7    0.16       0
Bank Sta=4968.7,4972.7
Exp/Cntr=0.3,0.1

Type RM Length L Ch R = 1,7671,138,138,138
BEGIN DESCRIPTION:
North Twin Creek Trib D7670.82
END DESCRIPTION:
XS GIS Cut Line= 3
      2734251.65      6820702.89      2734424.51      6820751.29
      2734617.54      6820793.95
#Sta/Elev= 30
  4821.0  432.58  4831.6  432.46  4856.7  431.49  4877.4  431.55  4887.8  431.03
  4929.4  430.49  4939.2  430.69  4950.1  429.98  4970.9  429.56  4978.5  428.83
  4983.7  427.70  4989.7  423.48  4989.9  422.98  4993.4  422.98  4993.7  423.48
  4998.7  427.44  5003.8  427.44  5012.3  428.38  5019.9  428.59  5025.0  428.22
  5032.8  428.20  5063.5  428.94  5068.6  429.42  5094.2  430.25  5145.4  430.97
  5161.1  431.60  5166.2  432.12  5176.1  431.65  5186.4  431.76  5198.2  432.33
#Mann=3,-1,0
  4821.0    0.16       0  4989.7    0.07       0  4993.7    0.16       0
Bank Sta=4989.7,4993.7
Exp/Cntr=0.3,0.1

Type RM Length L Ch R = 1,7533,120,120,120
BEGIN DESCRIPTION:
North Twin Creek Trib D7532.74
END DESCRIPTION:
XS GIS Cut Line= 3
      2734178.85      6820807.42      2734418.22      6820863.94
      2734632.00      6820908.84
#Sta/Elev= 30
  4754.5  431.53  4782.4  430.89  4794.8  430.99  4802.9  430.47  4832.0  430.05
  4837.1  429.69  4874.3  429.64  4895.4  428.66  4946.8  427.11  4957.1  424.12
  4964.1  420.56  4967.2  420.42  4967.4  419.92  4970.9  419.92  4971.2  420.42
  4987.9  422.50  5000.4  422.15  5006.9  422.63  5012.0  425.81  5018.6  424.19
  5028.8  426.13  5061.9  428.22  5090.1  428.80  5100.4  429.17  5106.6  429.80
  5156.5  430.73  5161.7  431.28  5192.3  431.63  5201.3  432.32  5218.9  432.85
#Mann=3,-1,0
  4754.5    0.16       0  4967.2    0.07       0  4971.2    0.16       0
Bank Sta=4967.2,4971.2
Exp/Cntr=0.3,0.1

Type RM Length L Ch R = 1,7413,124,124,124
BEGIN DESCRIPTION:
North Twin Creek Trib D7412.95
END DESCRIPTION:
XS GIS Cut Line= 3
      2734181.74      6820926.33      2734376.39      6820969.89
      2734522.23      6821003.38
#Sta/Elev= 30
  4800.8  428.76  4815.4  428.89  4825.7  428.76  4848.2  427.91  4866.6  427.76
  4897.4  426.92  4907.6  426.45  4928.1  426.24  4935.0  425.90  4948.6  424.79
  4958.9  425.03  4969.1  423.39  4978.3  422.13  4983.5  419.34  4987.6  416.33
  4987.9  415.83  4991.4  415.83  4991.6  416.33  4997.5  423.49  5002.6  423.49
  5010.1  425.00  5020.4  424.82  5026.5  426.20  5061.4  426.57  5069.4  427.02
  5074.5  426.88  5092.2  427.78  5123.0  428.46  5133.2  428.90  5149.9  429.16
#Mann=3,-1,0
  4800.8    0.16       0  4987.6    0.07       0  4991.6    0.16       0
Bank Sta=4987.6,4991.6
Exp/Cntr=0.3,0.1

Type RM Length L Ch R = 1,7289,98,98,98
BEGIN DESCRIPTION:
North Twin Creek Trib D7288.82
END DESCRIPTION:
XS GIS Cut Line= 3
      2734172.49      6821046.26      2734326.98      6821078.04
      2734512.27      6821113.59
#Sta/Elev= 30
  4842.9  426.50  4877.1  425.88  4891.8  425.80  4897.5  424.85  4907.7  424.25
  4918.0  421.67  4928.2  420.09  4937.1  423.13  4942.2  421.69  4948.6  423.12
  4958.8  422.44  4969.0  422.44  4979.2  421.74  4987.4  422.78  4992.5  422.68
  4997.6  420.80  5002.7  420.80  5007.8  412.56  5008.1  412.06  5011.6  412.06
  5011.8  412.56  5020.0  417.98  5030.2  421.59  5050.5  424.43  5070.9  424.75
  5091.1  425.57  5096.1  425.34  5132.0  426.44  5172.7  427.28  5189.3  427.92
#Mann=3,-1,0
  4842.9    0.16       0  5007.8    0.07       0  5011.8    0.16       0
Bank Sta=5007.8,5011.8
Exp/Cntr=0.3,0.1

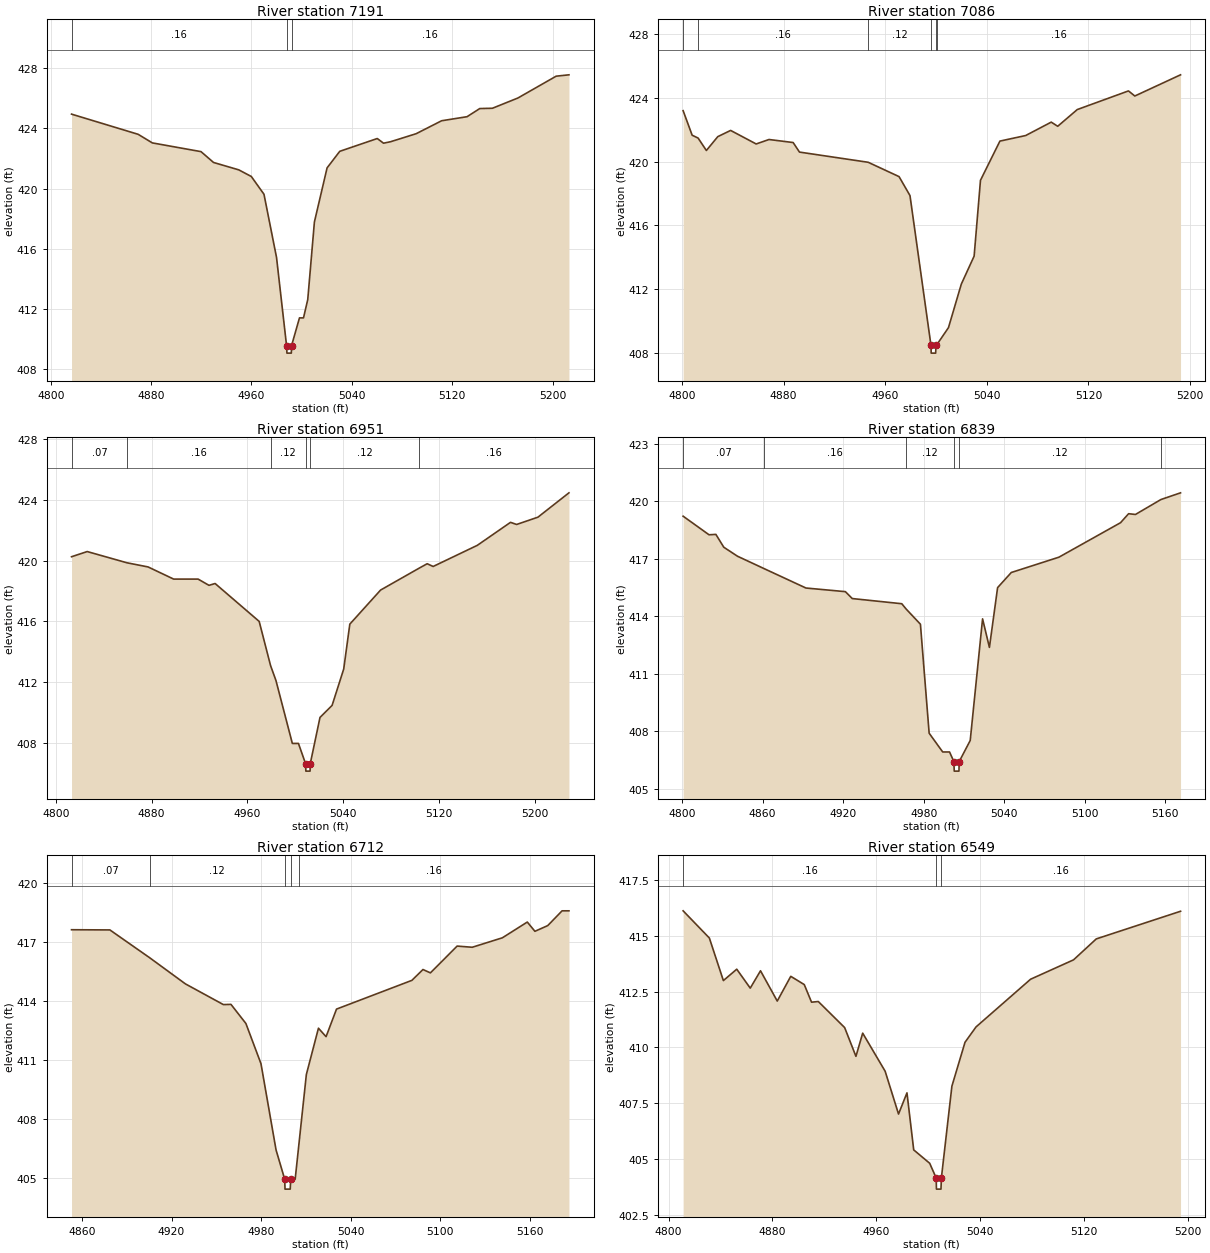
Type RM Length L Ch R = 1,7191,105,105,105
BEGIN DESCRIPTION:
North Twin Creek Trib D7191.36
END DESCRIPTION:
XS GIS Cut Line= 3
      2734143.10      6821161.37      2734327.44      6821175.47
      2734536.10      6821210.71
#Sta/Elev= 30
  4816.6  424.95  4869.7  423.61  4881.0  423.04  4919.8  422.46  4929.8  421.74
  4949.9  421.25  4959.9  420.81  4970.0  419.63  4980.0  415.44  4988.0  409.58
  4988.3  409.08  4991.8  409.08  4992.0  409.58  4998.3  411.42  5001.5  411.42
  5004.9  412.64  5010.2  417.79  5020.3  421.38  5030.4  422.48  5060.3  423.33
  5065.3  423.02  5071.0  423.12  5091.3  423.65  5111.6  424.51  5131.9  424.78
  5142.0  425.32  5152.1  425.34  5172.4  426.02  5202.9  427.47  5213.1  427.56
#Mann=3,-1,0
  4816.6    0.16       0  4988.0    0.07       0  4992.0    0.16       0
Bank Sta=4988,4992
Exp/Cntr=0.3,0.1

Type RM Length L Ch R = 1,7086,135,135,135
BEGIN DESCRIPTION:
North Twin Creek Trib D7086.43
END DESCRIPTION:
XS GIS Cut Line= 3
      2734128.97      6821254.12      2734327.71      6821280.46
      2734516.22      6821311.97
#Sta/Elev= 30
  4800.9  423.20  4808.0  421.66  4812.7  421.48  4819.2  420.70  4828.2  421.57
  4838.3  421.96  4858.4  421.11  4868.5  421.39  4887.5  421.20  4892.5  420.60
  4946.6  419.96  4970.9  419.06  4979.5  417.87  4996.0  408.48  4996.2  407.98
  4999.7  407.98  5000.0  408.48  5000.4  408.48  5009.8  409.58  5019.9  412.31
  5030.0  414.07  5035.0  418.83  5050.3  421.29  5070.6  421.64  5090.7  422.48
  5095.8  422.22  5111.2  423.27  5151.5  424.44  5156.5  424.12  5192.5  425.45
#Mann=6,-1,0
  4800.9    0.07       0  4812.7    0.16       0  4946.6    0.12       0
  4996.0    0.07       0  5000.0    0.12       0  5000.4    0.16       0
Bank Sta=4996,5000
Exp/Cntr=0.3,0.1

Type RM Length L Ch R = 1,6951,112,112,112
BEGIN DESCRIPTION:
North Twin Creek Trib D6951.17
END DESCRIPTION:
XS GIS Cut Line= 3
      2734092.38      6821362.57      2734275.30      6821399.37
      2734501.66      6821432.77
#Sta/Elev= 30
  4813.1  420.25  4826.2  420.59  4859.5  419.85  4877.0  419.58  4898.4  418.78
  4918.8  418.78  4927.9  418.37  4933.0  418.49  4969.8  416.00  4979.3  413.10
  4983.8  412.12  4997.5  407.98  5002.6  407.98  5008.5  406.66  5008.8  406.16
  5012.3  406.16  5012.5  406.66  5020.6  409.69  5030.7  410.48  5040.4  412.87
  5045.5  415.82  5071.2  418.06  5103.2  419.49  5110.1  419.79  5115.1  419.61
  5152.0  421.00  5179.7  422.51  5184.8  422.37  5202.6  422.85  5228.5  424.45
#Mann=6,-1,0
  4813.1    0.07       0  4859.5    0.16       0  4979.3    0.12       0
  5008.5    0.07       0  5012.5    0.12       0  5103.2    0.16       0
Bank Sta=5008.5,5012.5
Exp/Cntr=0.3,0.1

Type RM Length L Ch R = 1,6839,127,127,127
BEGIN DESCRIPTION:
North Twin Creek Trib D6839.26
END DESCRIPTION:
XS GIS Cut Line= 3
      2734076.29      6821471.35      2734270.83      6821510.57
      2734439.87      6821543.14
#Sta/Elev= 30
  4800.8  419.23  4820.1  418.26  4825.2  418.28  4831.1  417.61  4841.3  417.14
  4860.9  416.50  4892.3  415.48  4921.7  415.29  4926.8  414.93  4963.7  414.66
  4967.0  414.38  4977.6  413.59  4984.1  407.90  4994.2  406.92  4999.3  406.92
  5002.5  406.42  5002.8  405.92  5006.3  405.92  5006.5  406.42  5014.7  407.52
  5023.9  413.87  5029.0  412.38  5035.1  415.50  5045.3  416.29  5080.8  417.09
  5126.7  418.89  5132.7  419.36  5137.8  419.32  5156.8  420.10  5171.4  420.45
#Mann=6,-1,0
  4800.8    0.07       0  4860.9    0.16       0  4967.0    0.12       0
  5002.5    0.07       0  5006.5    0.12       0  5156.8    0.16       0
Bank Sta=5002.5,5006.5
Exp/Cntr=0.3,0.1

Type RM Length L Ch R = 1,6712,163,163,163
BEGIN DESCRIPTION:
North Twin Creek Trib D6711.57
END DESCRIPTION:
XS GIS Cut Line= 3
      2734080.56      6821600.46      2734226.29      6821622.95
      2734410.08      6821649.80
#Sta/Elev= 30
  4853.0  417.62  4878.7  417.61  4905.3  416.20  4929.3  414.87  4954.7  413.82
  4959.8  413.83  4969.8  412.86  4979.9  410.82  4990.0  406.44  4995.8  404.95
  4996.0  404.45  4999.5  404.45  4999.8  404.95  5002.8  404.95  5005.1  406.58
  5010.3  410.27  5018.4  412.62  5023.5  412.19  5030.5  413.59  5081.0  415.05
  5088.4  415.60  5093.4  415.43  5111.3  416.79  5121.4  416.73  5141.6  417.21
  5158.3  418.01  5163.4  417.54  5172.0  417.83  5181.6  418.58  5186.2  418.58
#Mann=5,-1,0
  4853.0    0.07       0  4905.3    0.12       0  4995.8    0.07       0
  4999.8    0.12       0  5005.1    0.16       0
Bank Sta=4995.8,4999.8
Exp/Cntr=0.3,0.1

Type RM Length L Ch R = 1,6549,170,170,170
BEGIN DESCRIPTION:
North Twin Creek Trib D6548.68
END DESCRIPTION:
XS GIS Cut Line= 3
      2733996.18      6821719.27      2734179.08      6821770.34
      2734370.26      6821798.24
#Sta/Elev= 30
  4811.2  416.13  4831.4  414.91  4842.2  413.00  4852.5  413.51  4862.9  412.66
  4870.8  413.44  4883.7  412.08  4894.1  413.19  4904.5  412.82  4910.1  412.03
  4915.3  412.06  4935.6  410.89  4944.3  409.60  4949.5  410.64  4966.8  408.93
  4977.1  407.01  4983.6  407.96  4988.8  405.40  5001.1  404.80  5006.1  404.14
  5006.3  403.64  5009.8  403.64  5010.1  404.14  5018.2  408.26  5028.3  410.23
  5036.8  410.92  5078.8  413.06  5111.9  413.93  5129.4  414.87  5194.3  416.11
#Mann=3,-1,0
  4811.2    0.16       0  5006.1    0.07       0  5010.1    0.16       0
Bank Sta=5006.1,5010.1
Exp/Cntr=0.3,0.1

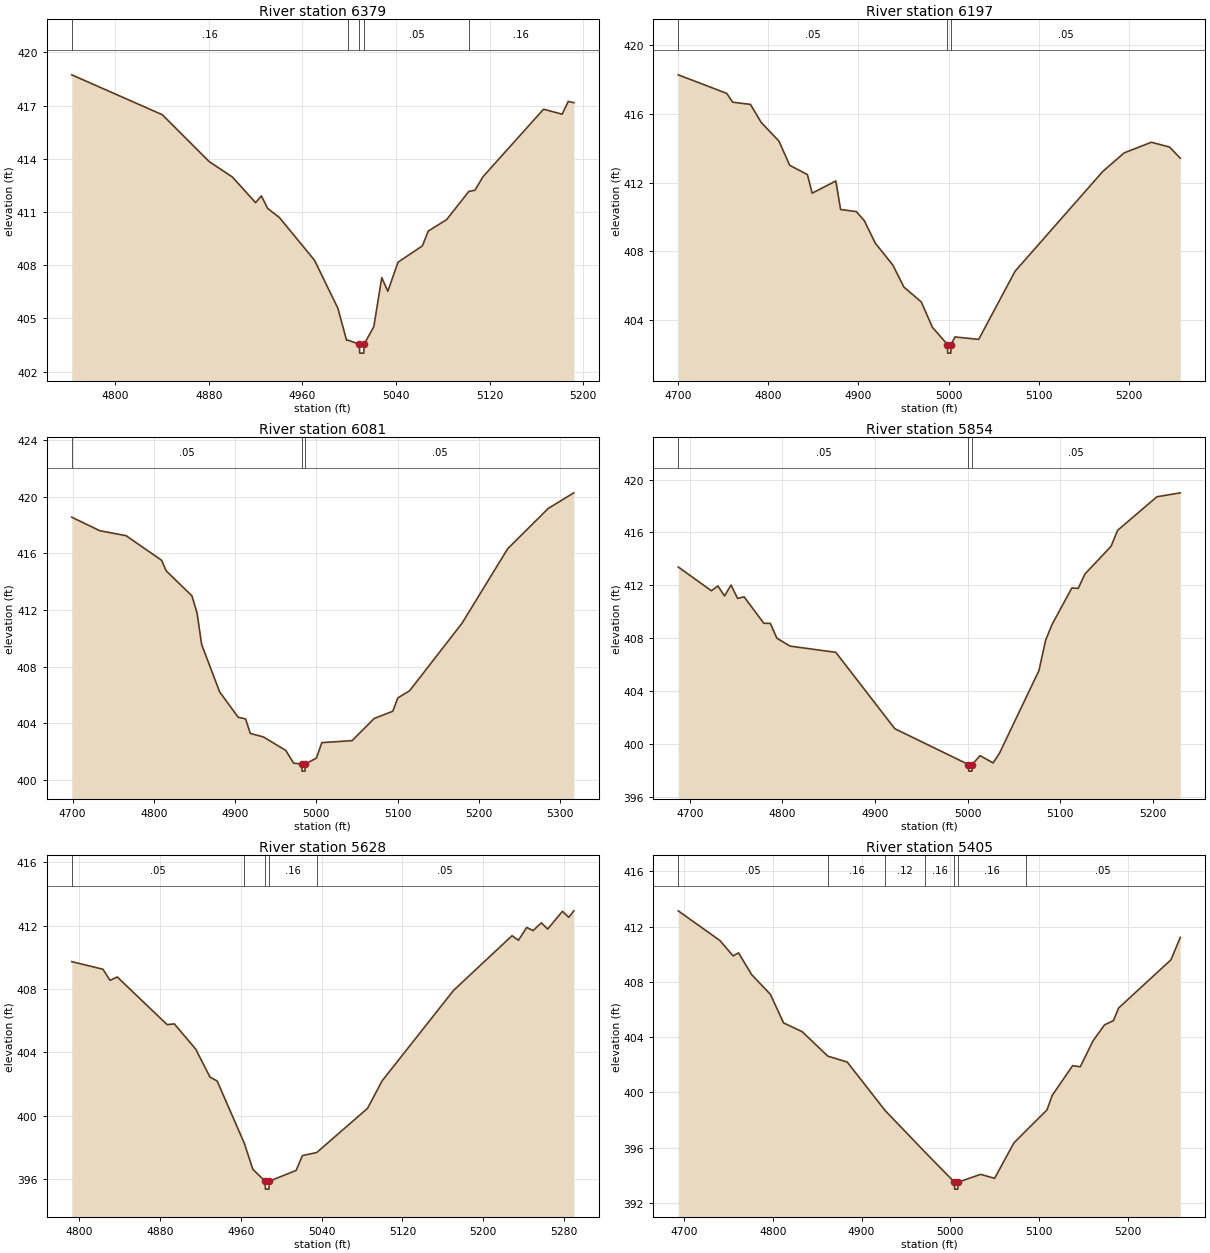
Type RM Length L Ch R = 1,6379,182,182,182
BEGIN DESCRIPTION:
North Twin Creek Trib D6379.07
END DESCRIPTION:
XS GIS Cut Line= 3
      2733888.62      6821931.04      2734125.85      6821923.65
      2734311.03      6821873.50
#Sta/Elev= 30
  4762.8  418.74  4840.2  416.49  4880.2  413.85  4900.2  412.97  4919.9  411.53
  4924.9  411.91  4930.3  411.20  4940.3  410.69  4970.3  408.28  4990.3  405.57
  4997.7  403.77  4999.0  403.77  5008.7  403.54  5008.9  403.04  5012.4  403.04
  5012.7  403.54  5021.0  404.53  5027.8  407.30  5033.0  406.53  5041.7  408.17
  5062.5  409.09  5067.6  409.93  5083.2  410.57  5102.2  412.16  5107.5  412.23
  5114.3  412.99  5166.1  416.80  5182.0  416.52  5187.2  417.24  5192.0  417.17
#Mann=5,-1,0
  4762.8    0.16       0  4999.0    0.05       0  5008.7    0.05       0
  5012.7    0.05       0  5102.2    0.16       0
Bank Sta=5008.7,5012.7
Exp/Cntr=0.3,0.1

Type RM Length L Ch R = 1,6197,116,116,116
BEGIN DESCRIPTION:
North Twin Creek Trib D6196.77
END DESCRIPTION:
XS GIS Cut Line= 3
      2733808.81      6821999.30      2734096.43      6822095.70
      2734347.85      6822126.17
#Sta/Elev= 30
  4700.2  418.26  4754.0  417.18  4760.5  416.67  4780.3  416.54  4792.2  415.49
  4811.8  414.41  4823.8  413.00  4843.4  412.46  4848.7  411.38  4874.9  412.09
  4880.2  410.43  4897.6  410.31  4906.5  409.78  4918.7  408.47  4938.0  407.21
  4950.4  405.92  4969.6  405.06  4982.0  403.58  4998.7  402.58  4998.9  402.08
  5002.4  402.08  5002.7  402.58  5007.1  403.02  5033.3  402.88  5073.6  406.84
  5170.8  412.64  5194.5  413.72  5224.7  414.34  5244.9  414.06  5256.8  413.41
#Mann=3,-1,0
  4700.2    0.05       0  4998.7    0.05       0  5002.7    0.05       0
Bank Sta=4998.7,5002.7
Exp/Cntr=0.3,0.1

Type RM Length L Ch R = 1,6081,227,227,227
BEGIN DESCRIPTION:
North Twin Creek Trib D6080.9
END DESCRIPTION:
XS GIS Cut Line= 3
      2733746.12      6822032.00      2734010.58      6822175.90
      2734201.97      6822428.52
#Sta/Elev= 30
  4699.0  418.54  4733.5  417.59  4765.8  417.24  4809.5  415.51  4815.2  414.76
  4846.9  413.00  4853.2  411.79  4858.9  409.56  4881.0  406.23  4903.8  404.44
  4913.0  404.32  4918.7  403.30  4934.9  403.05  4962.4  402.10  4972.1  401.20
  4982.3  401.14  4982.5  400.64  4986.0  400.64  4986.3  401.14  5000.1  401.56
  5006.8  402.65  5044.1  402.79  5071.2  404.35  5094.1  404.86  5100.3  405.80
  5114.9  406.31  5179.4  411.07  5235.6  416.32  5285.5  419.16  5317.0  420.26
#Mann=3,-1,0
  4699.0    0.05       0  4982.3    0.05       0  4986.3    0.05       0
Bank Sta=4982.3,4986.3
Exp/Cntr=0.3,0.1

Type RM Length L Ch R = 1,5854,226,226,226
BEGIN DESCRIPTION:
North Twin Creek Trib D5853.82
END DESCRIPTION:
XS GIS Cut Line= 3
      2733735.20      6822161.16      2733956.25      6822386.30
      2734120.16      6822542.60
#Sta/Elev= 30
  4687.5  413.39  4723.3  411.59  4730.3  411.95  4737.5  411.20  4744.5  412.02
  4751.6  411.01  4758.6  411.13  4779.9  409.13  4786.9  409.12  4794.0  408.00
  4808.2  407.40  4857.6  406.93  4921.3  401.15  5000.8  398.44  5001.1  397.94
  5004.6  397.94  5004.8  398.44  5013.3  399.11  5027.5  398.56  5034.4  399.31
  5076.9  405.55  5084.1  407.85  5091.0  409.03  5112.4  411.80  5119.3  411.77
  5126.6  412.86  5154.7  414.95  5161.8  416.16  5204.2  418.70  5229.5  419.00
#Mann=3,-1,0
  4687.5    0.05       0  5000.8    0.05       0  5004.8    0.05       0
Bank Sta=5000.8,5004.8
Exp/Cntr=0.3,0.1

Type RM Length L Ch R = 1,5628,223,223,223
BEGIN DESCRIPTION:
North Twin Creek Trib D5627.86
END DESCRIPTION:
XS GIS Cut Line= 3
      2733613.62      6822329.72      2733763.02      6822476.99
      2733991.09      6822652.06
#Sta/Elev= 30
  4792.5  409.72  4823.4  409.24  4830.4  408.54  4837.6  408.75  4887.0  405.74
  4894.1  405.79  4915.3  404.19  4929.4  402.43  4936.5  402.18  4963.3  398.26
  4971.9  396.60  4984.0  395.85  4984.3  395.35  4987.8  395.35  4988.0  395.85
  5014.7  396.53  5021.0  397.47  5035.1  397.66  5085.4  400.45  5099.9  402.19
  5170.6  407.90  5228.6  411.36  5234.9  411.07  5243.1  411.88  5249.4  411.68
  5257.6  412.17  5263.9  411.78  5278.5  412.90  5284.8  412.52  5289.8  412.93
#Mann=5,-1,0
  4792.5    0.05       0  4963.3    0.16       0  4984.0    0.07       0
  4988.0    0.16       0  5035.1    0.05       0
Bank Sta=4984,4988
Exp/Cntr=0.3,0.1

Type RM Length L Ch R = 1,5405,296,296,296
BEGIN DESCRIPTION:
North Twin Creek Trib D5404.84
END DESCRIPTION:
XS GIS Cut Line= 3
      2733383.74      6822478.42      2733636.88      6822652.39
      2733861.36      6822780.46
#Sta/Elev= 30
  4693.5  413.14  4740.5  410.99  4755.3  409.88  4761.4  410.10  4776.3  408.52
  4797.3  407.10  4812.2  405.03  4833.1  404.40  4862.0  402.63  4883.9  402.20
  4926.5  398.70  4971.6  395.68  5004.7  393.51  5004.9  393.01  5008.4  393.01
  5008.7  393.51  5034.2  394.08  5049.9  393.79  5071.5  396.34  5085.4  397.24
  5108.9  398.74  5114.8  399.79  5137.8  401.94  5146.4  401.86  5160.8  403.74
  5173.7  404.89  5183.8  405.20  5189.6  406.11  5248.6  409.60  5259.1  411.22
#Mann=7,-1,0
  4693.5    0.05       0  4862.0    0.16       0  4926.5    0.12       0
  4971.6    0.16       0  5004.7    0.07       0  5008.7    0.16       0
  5085.4    0.05       0
Bank Sta=5004.7,5008.7
Exp/Cntr=0.3,0.1

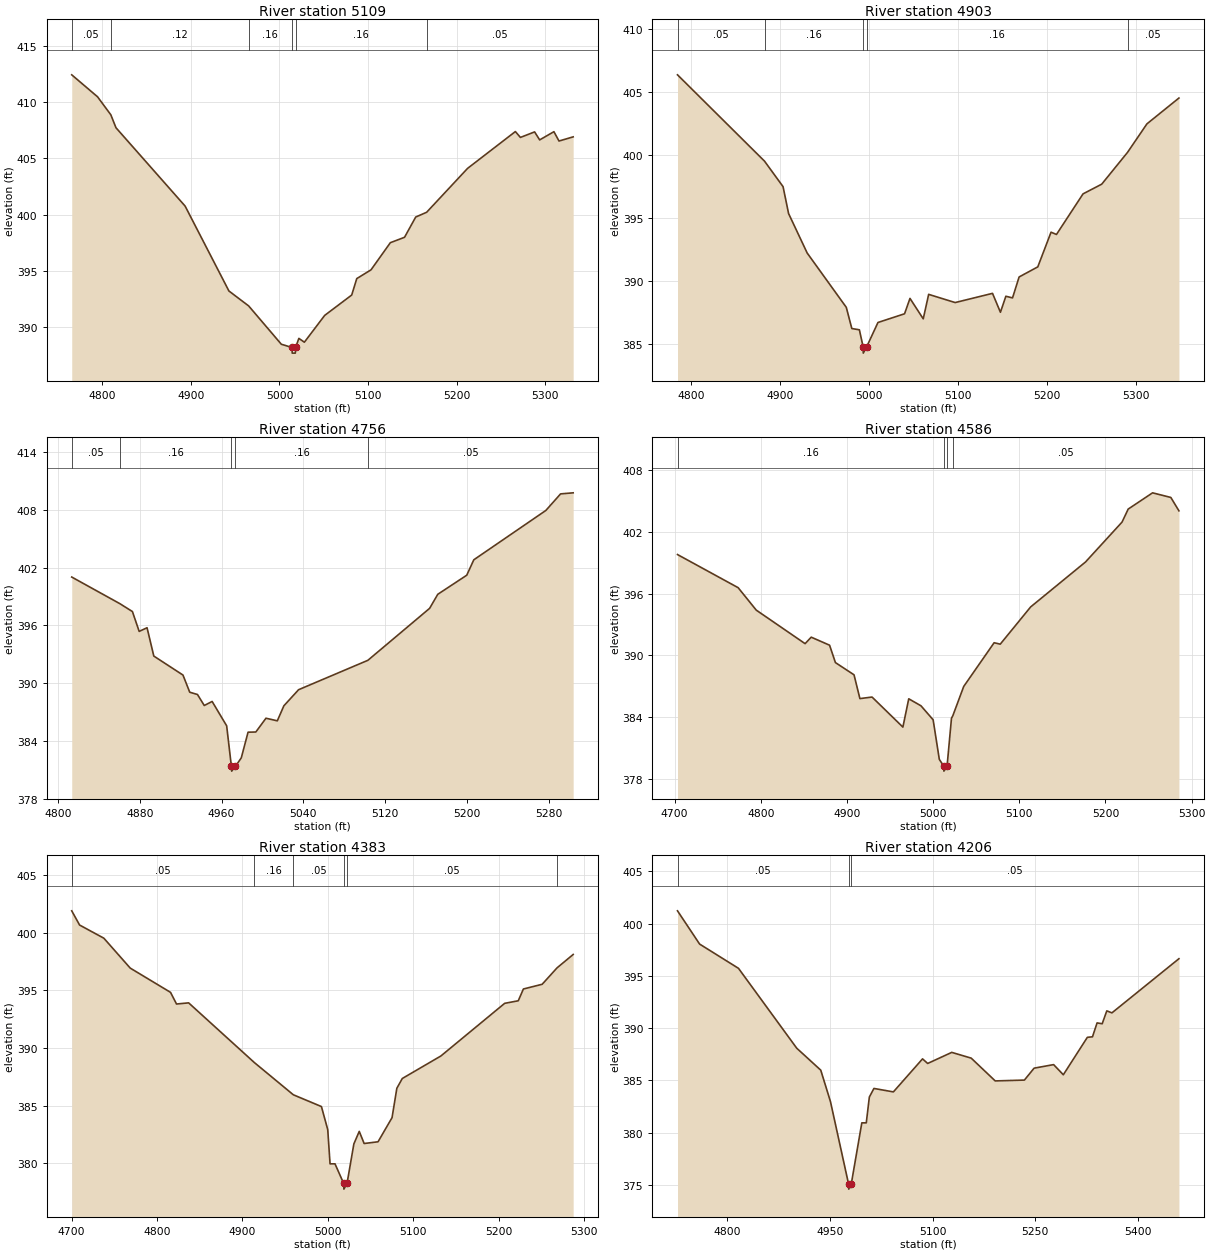
Type RM Length L Ch R = 1,5109,206,206,206
BEGIN DESCRIPTION:
North Twin Creek Trib D5108.64
END DESCRIPTION:
XS GIS Cut Line= 3
      2733283.12      6822673.54      2733463.24      6822826.72
      2733751.48      6822985.65
#Sta/Elev= 30
  4765.7  412.42  4794.8  410.47  4809.8  408.87  4815.6  407.72  4893.6  400.76
  4943.0  393.22  4965.3  391.89  5002.1  388.49  5014.2  388.20  5014.4  387.70
  5017.9  387.70  5018.2  388.20  5021.9  389.01  5028.1  388.67  5051.0  391.05
  5081.5  392.86  5087.2  394.32  5103.3  395.10  5125.1  397.51  5141.1  397.99
  5153.7  399.79  5166.0  400.21  5212.2  404.11  5266.1  407.38  5271.8  406.86
  5287.8  407.35  5293.5  406.64  5309.6  407.37  5315.3  406.54  5331.3  406.91
#Mann=6,-1,0
  4765.7    0.05       0  4809.8    0.12       0  4965.3    0.16       0
  5014.2    0.07       0  5018.2    0.16       0  5166.0    0.05       0
Bank Sta=5014.2,5018.2
Exp/Cntr=0.3,0.1

Type RM Length L Ch R = 1,4903,147,147,147
BEGIN DESCRIPTION:
North Twin Creek Trib D4903.35
END DESCRIPTION:
XS GIS Cut Line= 3
      2733248.71      6822823.38      2733376.85      6822999.60
      2733571.20      6823285.76
#Sta/Elev= 30
  4785.0  406.33  4882.9  399.48  4903.7  397.46  4909.9  395.33  4930.8  392.20
  4974.8  387.89  4981.0  386.21  4989.5  386.11  4993.7  384.76  4993.9  384.26
  4997.7  384.76  5010.4  386.69  5040.3  387.38  5046.4  388.60  5061.3  386.98
  5067.4  388.92  5097.2  388.27  5139.2  389.00  5148.1  387.50  5154.2  388.77
  5161.7  388.64  5169.1  390.30  5190.1  391.10  5205.0  393.85  5211.1  393.67
  5241.0  396.89  5262.0  397.66  5291.0  400.18  5312.8  402.44  5348.8  404.49
#Mann=5,-1,0
  4785.0    0.05       0  4882.9    0.16       0  4993.7    0.07       0
  4997.7    0.16       0  5291.0    0.05       0
Bank Sta=4993.7,4997.7
Exp/Cntr=0.3,0.1

Type RM Length L Ch R = 1,4756,170,170,170
BEGIN DESCRIPTION:
North Twin Creek Trib D4755.69
END DESCRIPTION:
XS GIS Cut Line= 3
      2733189.03      6822984.75      2733313.56      6823127.99
      2733501.50      6823362.08
#Sta/Elev= 30
  4813.6  401.01  4860.6  398.25  4872.9  397.43  4879.5  395.37  4887.2  395.75
  4893.8  392.81  4922.3  390.84  4928.9  389.06  4936.5  388.82  4943.1  387.68
  4950.8  388.10  4965.0  385.57  4969.6  381.37  4969.9  380.87  4973.6  381.37
  4979.3  382.25  4985.9  384.91  4993.5  384.93  5003.4  386.36  5014.5  386.09
  5020.9  387.65  5035.3  389.32  5103.0  392.37  5163.3  397.76  5171.3  399.22
  5199.6  401.20  5206.5  402.80  5276.9  407.92  5291.3  409.64  5303.6  409.75
#Mann=5,-1,0
  4813.6    0.05       0  4860.6    0.16       0  4969.6    0.07       0
  4973.6    0.16       0  5103.0    0.05       0
Bank Sta=4969.6,4973.6
Exp/Cntr=0.3,0.1

Type RM Length L Ch R = 1,4586,203,203,203
BEGIN DESCRIPTION:
North Twin Creek Trib D4585.99
END DESCRIPTION:
XS GIS Cut Line= 3
      2732991.22      6823026.46      2733191.86      6823245.97
      2733393.26      6823447.08
#Sta/Elev= 30
  4703.3  399.81  4773.7  396.59  4794.7  394.41  4851.4  391.15  4858.5  391.78
  4879.8  391.00  4886.6  389.31  4908.2  388.12  4915.0  385.81  4929.1  385.96
  4964.9  383.04  4971.7  385.79  4985.9  385.11  5000.0  383.75  5007.2  379.90
  5012.2  379.26  5012.5  378.76  5016.2  379.26  5021.3  383.90  5022.9  384.15
  5035.5  386.99  5070.8  391.24  5077.9  391.10  5113.2  394.72  5176.9  399.09
  5219.3  402.97  5226.4  404.23  5254.7  405.81  5275.9  405.36  5285.3  404.06
#Mann=4,-1,0
  4703.3    0.16       0  5012.2    0.07       0  5016.2    0.16       0
  5022.9    0.05       0
Bank Sta=5012.2,5016.2
Exp/Cntr=0.3,0.1

Type RM Length L Ch R = 1,4383,177,177,177
BEGIN DESCRIPTION:
North Twin Creek Trib D4382.57
END DESCRIPTION:
XS GIS Cut Line= 3
      2732828.45      6823135.20      2733031.90      6823359.96
      2733282.77      6823493.15
#Sta/Elev= 30
  4700.1  401.88  4709.3  400.65  4737.7  399.51  4768.6  396.92  4815.8  394.82
  4822.8  393.81  4837.0  393.91  4913.8  388.75  4959.6  385.95  4992.5  384.93
  4999.9  382.93  5002.6  379.97  5008.4  379.97  5018.5  378.28  5018.8  377.78
  5022.5  378.28  5030.5  381.70  5036.8  382.78  5042.5  381.73  5058.8  381.88
  5075.2  383.97  5080.8  386.51  5087.2  387.36  5132.4  389.31  5207.1  393.87
  5223.0  394.09  5229.0  395.11  5251.0  395.52  5268.4  396.94  5287.3  398.10
#Mann=6,-1,0
  4700.1    0.05       0  4913.8    0.16       0  4959.6    0.05       0
  5018.5    0.05       0  5022.5    0.05       0  5268.4    0.16       0
Bank Sta=5018.5,5022.5
Exp/Cntr=0.3,0.1

Type RM Length L Ch R = 1,4206,187,187,187
BEGIN DESCRIPTION:
North Twin Creek Trib D4205.53
END DESCRIPTION:
XS GIS Cut Line= 3
      2732684.24      6823266.88      2732885.73      6823450.03
      2733228.83      6823756.90
#Sta/Elev= 30
  4727.3  401.22  4759.6  398.04  4816.4  395.72  4901.5  388.08  4936.6  385.98
  4950.8  382.97  4977.2  375.10  4977.5  374.60  4981.2  375.10  4996.6  380.94
  5003.1  380.94  5007.6  383.41  5014.3  384.23  5042.7  383.90  5085.3  387.06
  5092.8  386.62  5128.0  387.68  5156.4  387.13  5191.5  384.95  5234.1  385.03
  5248.3  386.17  5276.8  386.51  5291.0  385.54  5326.1  389.12  5333.6  389.17
  5340.3  390.50  5347.8  390.42  5354.5  391.65  5362.0  391.46  5459.9  396.64
#Mann=3,-1,0
  4727.3    0.05       0  4977.2    0.05       0  4981.2    0.05       0
Bank Sta=4977.2,4981.2
Exp/Cntr=0.3,0.1

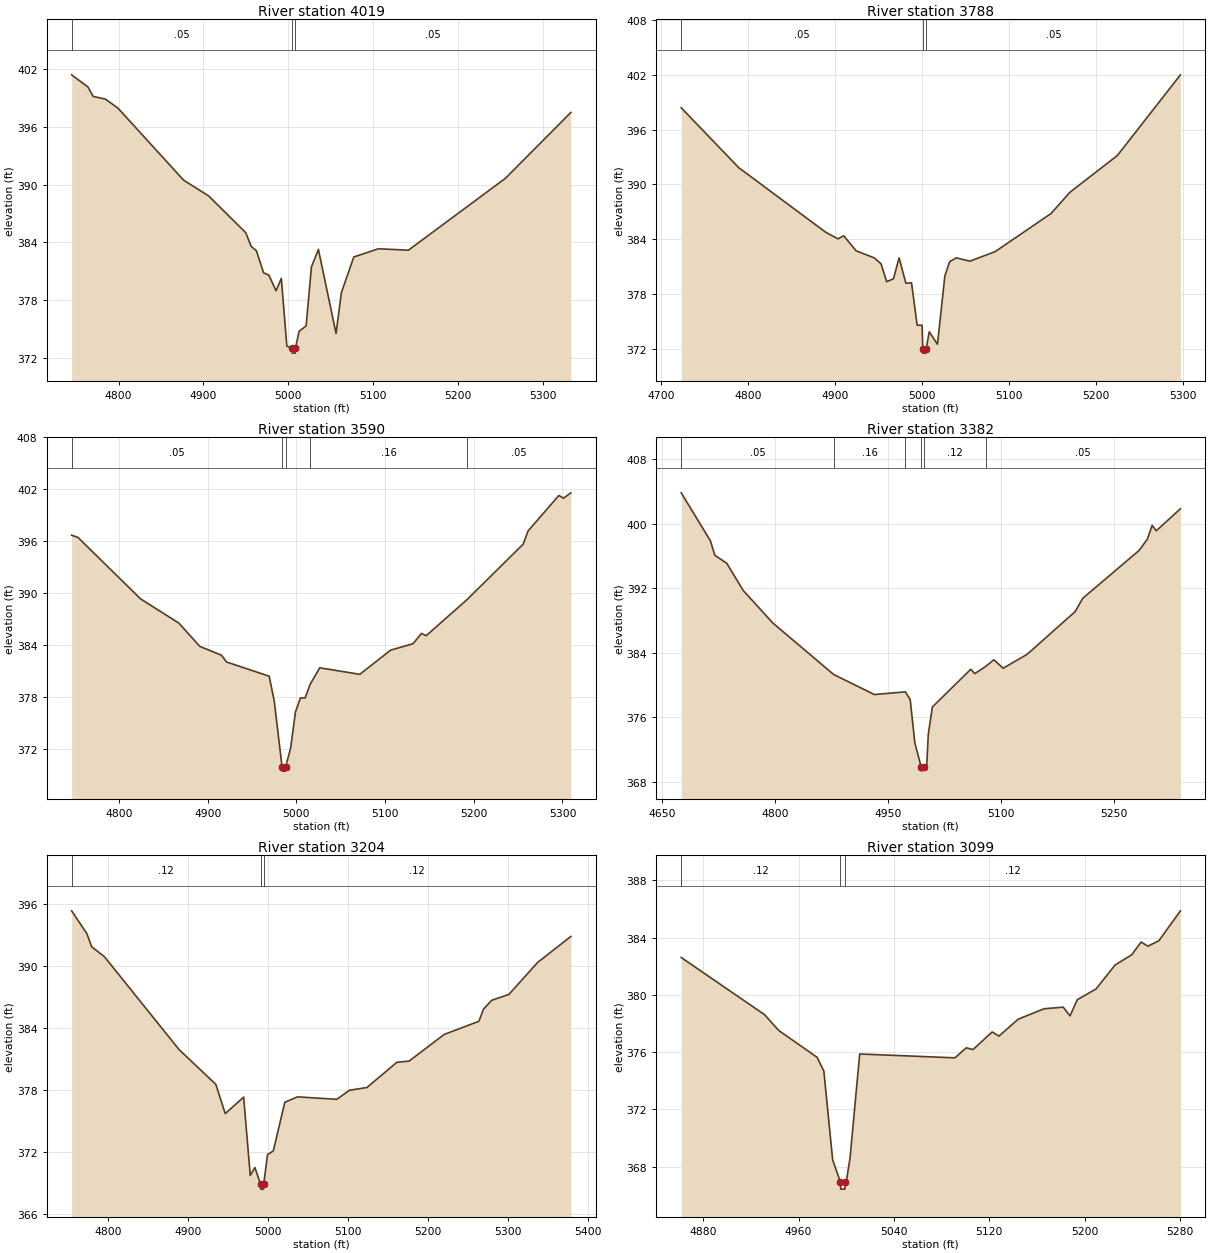
Type RM Length L Ch R = 1,4019,231,231,231
BEGIN DESCRIPTION:
North Twin Creek Trib D4018.61
END DESCRIPTION:
XS GIS Cut Line= 3
      2732579.97      6823451.48      2732789.51      6823603.62
      2733051.68      6823803.30
#Sta/Elev= 30
  4744.6  401.41  4763.8  400.15  4769.9  399.17  4784.6  398.88  4799.3  397.94
  4876.6  390.46  4906.0  388.83  4949.8  385.01  4956.2  383.59  4962.4  383.12
  4970.9  380.83  4977.1  380.59  4985.6  378.96  4991.8  380.25  4998.3  373.21
  5004.4  372.98  5004.7  372.48  5008.2  372.48  5008.4  372.98  5012.7  374.74
  5021.0  375.31  5027.3  381.45  5035.5  383.26  5056.3  374.53  5062.6  378.77
  5077.2  382.47  5106.2  383.33  5141.6  383.18  5255.9  390.65  5333.1  397.50
#Mann=3,-1,0
  4744.6    0.05       0  5004.4    0.05       0  5008.4    0.05       0
Bank Sta=5004.4,5008.4
Exp/Cntr=0.3,0.1

Type RM Length L Ch R = 1,3788,198,198,198
BEGIN DESCRIPTION:
North Twin Creek Trib D3787.91
END DESCRIPTION:
XS GIS Cut Line= 3
      2732517.13      6823636.17      2732729.77      6823814.38
      2733002.68      6823932.68
#Sta/Elev= 30
  4722.7  398.39  4788.9  391.84  4889.0  384.78  4903.3  384.05  4909.8  384.39
  4924.1  382.74  4945.0  381.97  4952.8  381.32  4959.3  379.37  4967.1  379.67
  4973.6  381.97  4981.4  379.19  4987.9  379.25  4994.4  374.60  5000.1  374.60
  5000.9  372.05  5001.1  371.55  5004.6  371.55  5004.9  372.05  5008.3  373.88
  5017.8  372.52  5026.3  379.98  5031.8  381.55  5039.6  381.97  5055.2  381.61
  5084.2  382.65  5148.6  386.82  5170.4  389.15  5224.9  393.16  5297.6  401.99
#Mann=3,-1,0
  4722.7    0.05       0  5000.9    0.05       0  5004.9    0.05       0
Bank Sta=5000.9,5004.9
Exp/Cntr=0.3,0.1

Type RM Length L Ch R = 1,3590,208,208,208
BEGIN DESCRIPTION:
North Twin Creek Trib D3590.2
END DESCRIPTION:
XS GIS Cut Line= 3
      2732413.77      6823893.54      2732655.81      6823990.15
      2732947.88      6824068.46
#Sta/Elev= 30
  4746.5  396.70  4753.7  396.44  4824.3  389.35  4867.3  386.57  4891.1  383.87
  4915.4  382.86  4921.2  382.07  4969.3  380.43  4975.0  377.56  4983.8  369.98
  4984.0  369.48  4987.5  369.48  4987.8  369.98  4993.5  372.15  4998.9  376.29
  5004.5  377.92  5009.8  377.92  5015.4  379.48  5026.3  381.40  5071.5  380.65
  5106.3  383.44  5131.5  384.18  5141.1  385.37  5146.3  385.10  5192.2  389.25
  5255.8  395.68  5261.2  397.19  5296.0  401.29  5301.2  400.97  5309.5  401.59
#Mann=5,-1,0
  4746.5    0.05       0  4983.8    0.05       0  4987.8    0.05       0
  5015.4    0.16       0  5192.2    0.05       0
Bank Sta=4983.8,4987.8
Exp/Cntr=0.3,0.1

Type RM Length L Ch R = 1,3382,178,178,178
BEGIN DESCRIPTION:
North Twin Creek Trib D3381.75
END DESCRIPTION:
XS GIS Cut Line= 3
      2732320.31      6824038.54      2732620.46      6824164.66
      2732937.47      6824278.20
#Sta/Elev= 30
  4675.4  403.80  4714.1  397.87  4720.0  396.07  4735.8  395.08  4757.5  391.73
  4796.7  387.70  4877.6  381.31  4931.7  378.82  4972.8  379.16  4979.2  378.19
  4985.3  372.86  4993.8  369.84  4994.1  369.34  4997.8  369.84  5001.0  369.84
  5003.2  373.90  5008.6  377.28  5059.5  381.95  5064.8  381.41  5079.2  382.29
  5090.2  383.13  5102.5  382.08  5134.3  383.80  5198.1  389.10  5208.0  390.73
  5283.0  396.68  5293.7  398.05  5300.2  399.77  5305.6  399.10  5337.7  401.83
#Mann=6,-1,0
  4675.4    0.05       0  4877.6    0.16       0  4972.8    0.12       0
  4993.8    0.07       0  4997.8    0.12       0  5079.2    0.05       0
Bank Sta=4993.8,4997.8
Exp/Cntr=0.3,0.1

Type RM Length L Ch R = 1,3204,105,105,105
BEGIN DESCRIPTION:
North Twin Creek Trib D3204.05
END DESCRIPTION:
XS GIS Cut Line= 3
      2732309.53      6824183.32      2732525.23      6824307.45
      2732852.17      6824492.00
#Sta/Elev= 30
  4753.9  395.34  4772.9  393.14  4779.0  391.86  4794.8  390.91  4888.3  381.91
  4934.2  378.55  4946.0  375.72  4969.0  377.31  4977.3  369.73  4983.1  370.50
  4990.1  368.91  4990.4  368.41  4993.9  368.41  4994.1  368.91  4998.9  371.75
  5006.1  372.11  5020.5  376.82  5036.4  377.34  5085.5  377.10  5101.4  377.98
  5123.1  378.24  5160.6  380.68  5175.9  380.80  5219.8  383.38  5263.2  384.65
  5268.9  385.82  5279.1  386.68  5300.7  387.25  5336.7  390.35  5378.2  392.86
#Mann=3,-1,0
  4753.9    0.12       0  4990.1    0.07       0  4994.1    0.12       0
Bank Sta=4990.1,4994.1
Exp/Cntr=0.3,0.1

Type RM Length L Ch R = 1,3099,187,187,187
BEGIN DESCRIPTION:
Mapping XS e24b29e4
END DESCRIPTION:
XS GIS Cut Line= 3
      2732353.56      6824331.07      2732476.10      6824395.61
      2732721.84      6824530.87
#Sta/Elev= 30
  4861.5  382.61  4931.4  378.62  4943.4  377.51  4975.5  375.64  4981.2  374.68
  4988.6  368.48  4995.1  366.93  4995.4  366.43  4998.9  366.43  4999.1  366.93
  5000.0  366.93  5003.2  368.61  5011.3  375.87  5091.2  375.60  5100.7  376.30
  5106.4  376.18  5122.5  377.41  5128.2  377.12  5144.3  378.30  5166.1  379.03
  5182.1  379.14  5187.8  378.53  5193.9  379.66  5209.6  380.41  5225.7  382.09
  5239.6  382.80  5247.5  383.69  5253.2  383.40  5262.4  383.78  5280.5  385.87
#Mann=3,-1,0
  4861.5    0.12       0  4995.1    0.07       0  4999.1    0.12       0
Bank Sta=4995.1,4999.1
Exp/Cntr=0.3,0.1