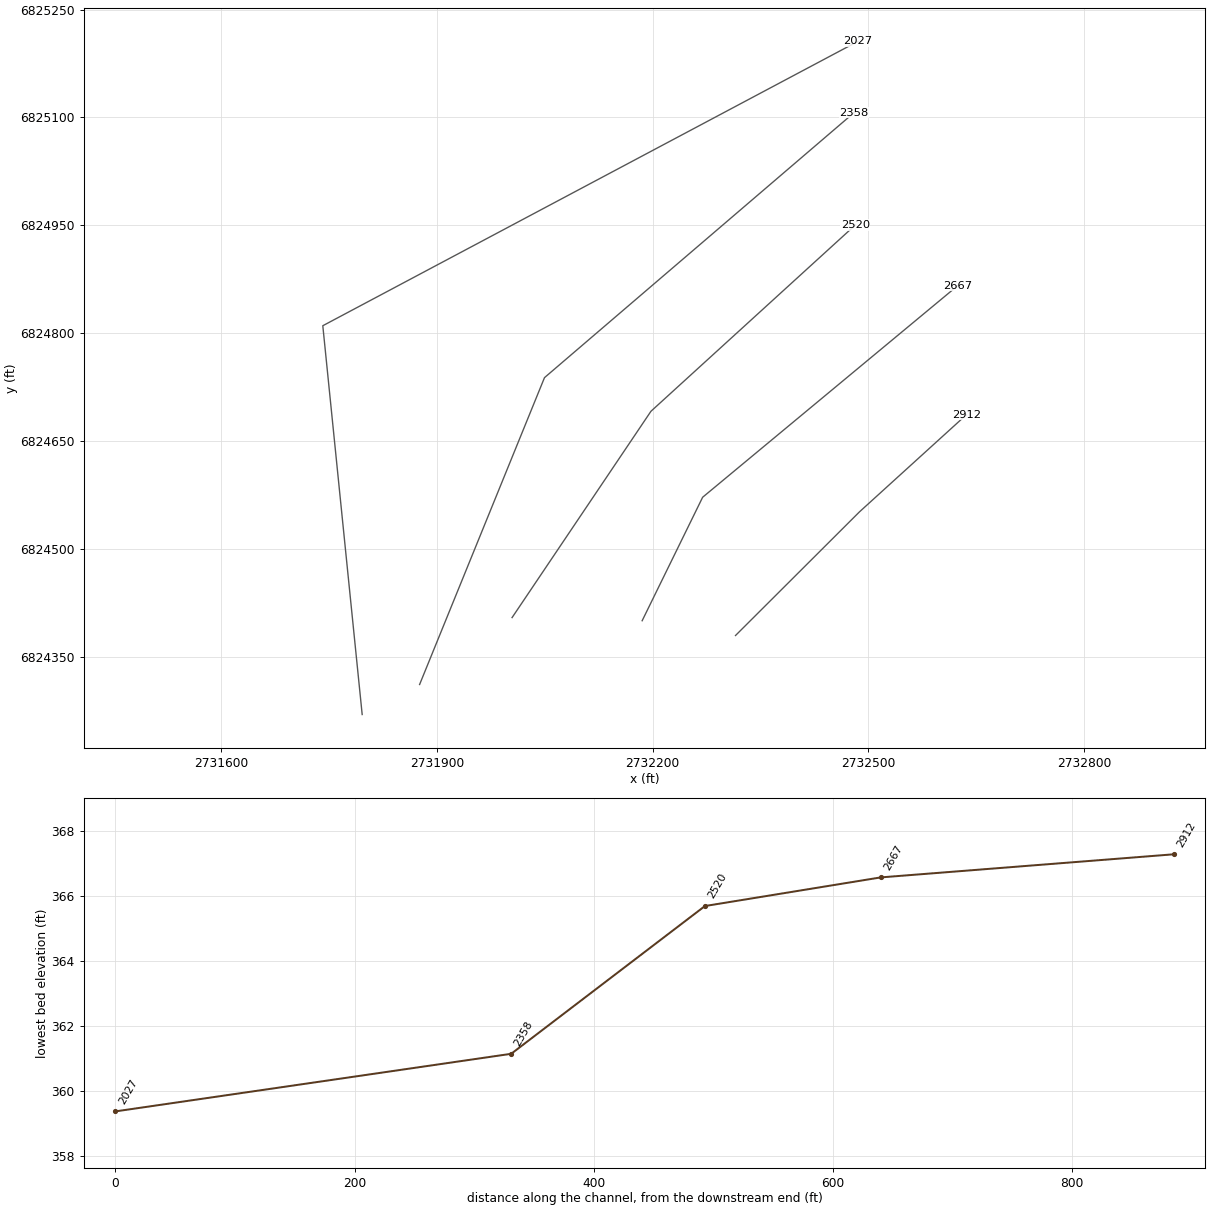
HEC-RAS study North Twin Creek Trib D.prj: North Twin Creek Trib D Base Level Engineering

--- North Twin Creek Trib D.g01 (geometry) --- (continued)

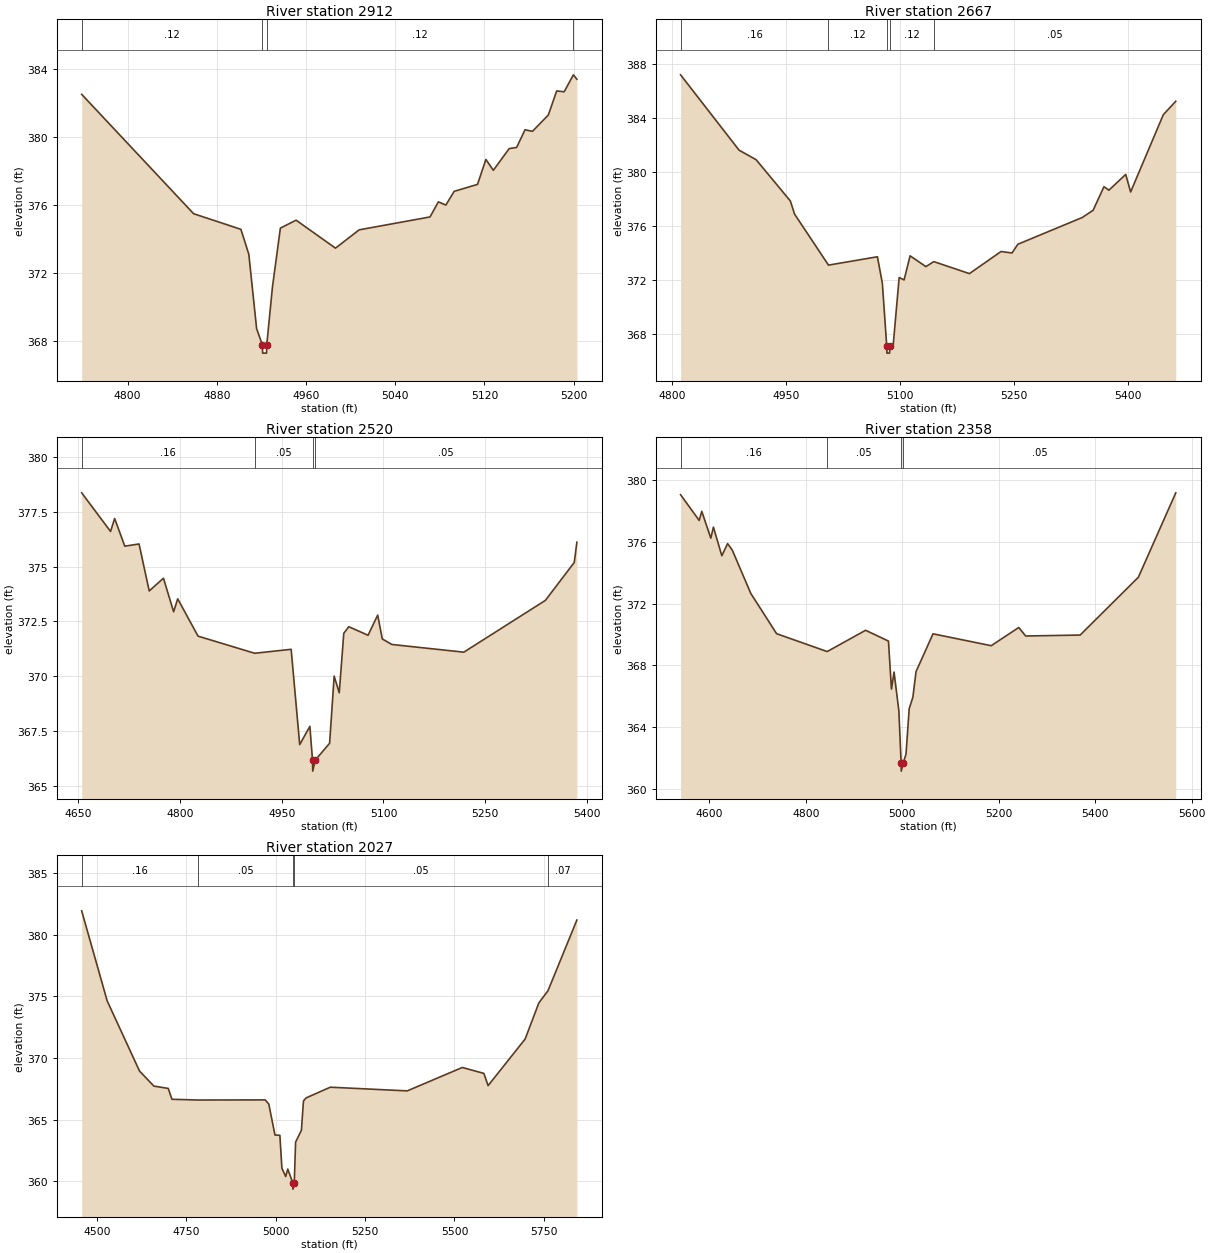
Type RM Length L Ch R = 1,2912,245,245,245
BEGIN DESCRIPTION:
Mapping XS 724519b6
END DESCRIPTION:
XS GIS Cut Line= 3
      2732315.22      6824379.82      2732487.57      6824551.67
      2732636.17      6824686.60
#Sta/Elev= 30
  4758.8  382.53  4859.2  375.49  4901.6  374.57  4908.7  373.10  4915.7  368.71
  4920.8  367.77  4921.1  367.27  4924.6  367.27  4924.8  367.77  4929.9  371.17
  4937.0  374.64  4951.1  375.11  4986.4  373.46  5007.7  374.54  5071.2  375.30
  5078.7  376.19  5085.4  376.00  5092.9  376.81  5113.8  377.22  5121.3  378.69
  5128.0  378.05  5142.2  379.33  5148.9  379.40  5156.4  380.44  5163.1  380.35
  5177.3  381.31  5184.8  382.73  5191.5  382.68  5199.8  383.68  5202.9  383.42
#Mann=4,-1,0
  4758.8    0.12       0  4920.8    0.07       0  4924.8    0.12       0
  5199.8    0.05       0
Bank Sta=4920.8,4924.8
Exp/Cntr=0.3,0.1

Type RM Length L Ch R = 1,2667,147,147,147
BEGIN DESCRIPTION:
North Twin Creek Trib D2666.52
END DESCRIPTION:
XS GIS Cut Line= 3
      2732185.38      6824400.36      2732269.50      6824572.02
      2732624.08      6824866.06
#Sta/Elev= 30
  4811.5  387.21  4888.5  381.62  4911.0  380.91  4956.0  377.85  4961.6  376.87
  5006.2  373.09  5070.6  373.71  5077.1  371.74  5082.9  367.06  5083.1  366.56
  5086.6  366.56  5086.9  367.06  5091.4  367.17  5099.2  372.17  5105.7  371.99
  5113.6  373.78  5134.4  372.98  5144.8  373.35  5191.7  372.46  5233.3  374.10
  5247.7  373.99  5255.5  374.64  5340.1  376.62  5354.5  377.16  5368.8  378.91
  5375.3  378.65  5397.4  379.82  5403.9  378.52  5446.9  384.25  5463.3  385.25
#Mann=5,-1,0
  4811.5    0.16       0  5006.2    0.12       0  5082.9    0.07       0
  5086.9    0.12       0  5144.8    0.05       0
Bank Sta=5082.9,5086.9
Exp/Cntr=0.3,0.1

Type RM Length L Ch R = 1,2520,162,162,162
BEGIN DESCRIPTION:
North Twin Creek Trib D2520.23
END DESCRIPTION:
XS GIS Cut Line= 3
      2732004.47      6824404.73      2732197.61      6824691.55
      2732481.78      6824950.44
#Sta/Elev= 30
  4655.0  378.36  4697.6  376.60  4703.6  377.19  4718.6  375.93  4739.6  376.03
  4754.6  373.89  4775.6  374.47  4790.6  372.94  4796.6  373.53  4826.6  371.83
  4910.1  371.05  4963.9  371.23  4976.5  366.89  4991.5  367.72  4995.4  366.18
  4995.7  365.68  4999.4  366.18  5020.6  366.95  5027.3  370.01  5034.8  369.25
  5041.5  371.96  5048.9  372.26  5077.3  371.87  5091.5  372.79  5098.3  371.70
  5112.5  371.45  5218.5  371.10  5338.8  373.46  5381.4  375.19  5385.2  376.11
#Mann=4,-1,0
  4655.0    0.16       0  4910.1    0.05       0  4995.4    0.05       0
  4999.4    0.05       0
Bank Sta=4995.4,4999.4
Exp/Cntr=0.3,0.1

Type RM Length L Ch R = 1,2358,331,331,331
BEGIN DESCRIPTION:
North Twin Creek Trib D2357.69
END DESCRIPTION:
XS GIS Cut Line= 3
      2731875.86      6824311.69      2732049.53      6824738.29
      2732479.80      6825106.48
#Sta/Elev= 30
  4540.2  379.06  4578.8  377.39  4584.2  377.98  4602.9  376.24  4608.3  376.96
  4625.8  375.10  4637.7  375.89  4647.4  375.47  4685.8  372.66  4739.3  370.05
  4844.2  368.89  4923.9  370.27  4971.3  369.57  4977.5  366.46  4982.9  367.56
  4992.9  365.04  4997.6  361.64  4997.8  361.14  5001.6  361.64  5007.7  362.24
  5014.3  365.18  5022.0  365.94  5028.5  367.59  5063.7  370.04  5184.4  369.27
  5241.5  370.45  5255.8  369.90  5368.8  369.96  5489.6  373.71  5567.1  379.18
#Mann=4,-1,0
  4540.2    0.16       0  4844.2    0.05       0  4997.6    0.05       0
  5001.6    0.05       0
Bank Sta=4997.6,5001.6
Exp/Cntr=0.3,0.1

Type RM Length L Ch R = 1,2027,0,0,0
BEGIN DESCRIPTION:
North Twin Creek Trib D2026.577
END DESCRIPTION:
XS GIS Cut Line= 3
      2731795.99      6824269.95      2731741.22      6824810.48
      2732485.35      6825205.75
#Sta/Elev= 30
  4456.7  381.95  4528.1  374.64  4618.6  368.95  4658.8  367.73  4699.0  367.54
  4709.3  366.66  4782.5  366.60  4970.4  366.61  4980.4  366.27  4997.7  363.76
  5011.4  363.74  5017.1  361.06  5027.7  360.39  5033.4  361.00  5047.7  359.87
  5048.0  359.37  5051.7  359.87  5055.4  363.18  5071.7  364.15  5077.4  366.52
  5084.7  366.77  5152.6  367.64  5367.8  367.34  5522.0  369.24  5582.3  368.76
  5594.2  367.77  5697.9  371.55  5736.2  374.48  5761.8  375.47  5842.6  381.20
#Mann=5,-1,0
  4456.7    0.16       0  4782.5    0.05       0  5047.7    0.05       0
  5051.7    0.05       0  5761.8    0.07       0
Bank Sta=5047.7,5051.7
Exp/Cntr=0.3,0.1

Chan Stop Cuts=-1