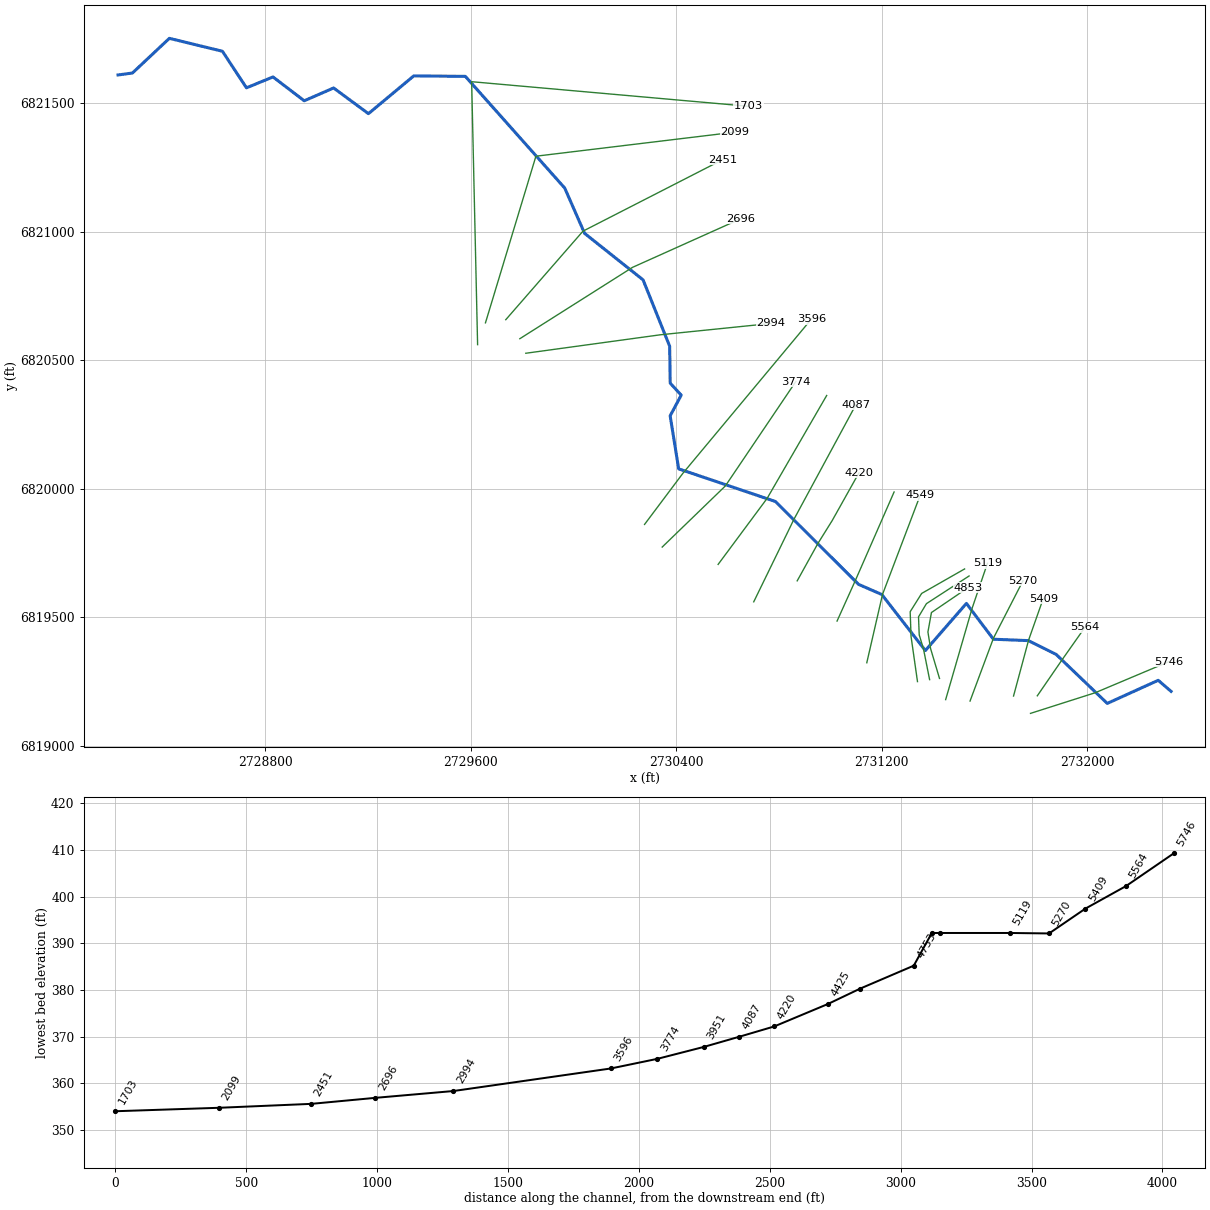
--- North Twin Creek Trib E.prj (project) ---

Proj Title=North Twin Creek Trib E Base Level Engineering
Current Plan=p01
Default Exp/Contr=0.3,0.1
English Units
Geom File=g01
Flow File=f01
Plan File=p01
BEGIN DESCRIPTION:
North Twin Creek Trib E
END DESCRIPTION:

--- North Twin Creek Trib E.p01 (plan) ---

Plan Title=Multiple Run
Short Identifier=Multiple
Geom File=g01
Flow File=f01
Subcritical Flow
K Sum by GR= 0
Std Step Tol= 0.01
Critical Tol= 0.01
Num of Std Step Trials= 20
Max Error Tol= 0.3
Flow Tol Ratio= 0.001
Split Flow NTrial= 30
Split Flow Tol= 0.02
Split Flow Ratio= 0.02
Log Output Level= 0
Friction Slope Method= 1
Unsteady Friction Slope Method= 2
Unsteady Bridges Friction Slope Method= 1
Parabolic Critical Depth
Global Vel Dist=  1 , 1 , 1
Global Log Level= 0
CheckData=True
Encroach Param= -1, 0, 0, 0
BEGIN DESCRIPTION:
Multiple Run
END DESCRIPTION:

--- North Twin Creek Trib E.f01 (steady flow) ---

Flow Title=Multiple
Number of Profiles=7
Profile Names=10-year,25-year,50-year,1pct_min,100-year,1pct_plu,500-year
River Rch & RM= North Twin Creek,Reach-1,5746
     186     232     267     153     306     611     400
River Rch & RM= North Twin Creek,Reach-1,2994
     387     504     596     350     699    1394     959
Boundary for River Rch & Prof#=North Twin Creek,Reach-1,1
Up Type=0
Dn Type=3
Dn Slope=0.005
Boundary for River Rch & Prof#=North Twin Creek,Reach-1,2
Up Type=0
Dn Type=3
Dn Slope=0.005
Boundary for River Rch & Prof#=North Twin Creek,Reach-1,3
Up Type=0
Dn Type=3
Dn Slope=0.005
Boundary for River Rch & Prof#=North Twin Creek,Reach-1,4
Up Type=0
Dn Type=3
Dn Slope=0.005
Boundary for River Rch & Prof#=North Twin Creek,Reach-1,5
Up Type=0
Dn Type=3
Dn Slope=0.005
Boundary for River Rch & Prof#=North Twin Creek,Reach-1,6
Up Type=0
Dn Type=3
Dn Slope=0.005
Boundary for River Rch & Prof#=North Twin Creek,Reach-1,7
Up Type=0
Dn Type=3
Dn Slope=0.005

--- North Twin Creek Trib E.g01 (geometry) ---

Geom Title=Existing Conditions

River Reach=North Twin Creek,Reach-1
Reach XY= 30
      2732326.00      6819211.00      2732276.12      6819254.13
      2732077.63      6819164.12      2731878.30      6819355.17
      2731770.47      6819408.63      2731634.30      6819414.08
      2731529.16      6819553.49      2731369.34      6819369.95
      2731199.84      6819588.14      2731109.34      6819627.66
      2730785.68      6819950.24      2730408.86      6820077.45
      2730375.77      6820283.88      2730418.77      6820364.45
      2730376.00      6820411.00      2730373.78      6820555.08
      2730270.18      6820813.31      2730042.63      6820994.29
      2729965.24      6821170.68      2729578.45      6821605.54
      2729377.46      6821607.46      2729201.00      6821460.41
      2729065.37      6821560.39      2728950.97      6821510.52
      2728829.38      6821603.40      2728726.00      6821561.00
      2728632.48      6821703.32      2728425.90      6821753.68
      2728282.21      6821618.76      2728226.00      6821611.00

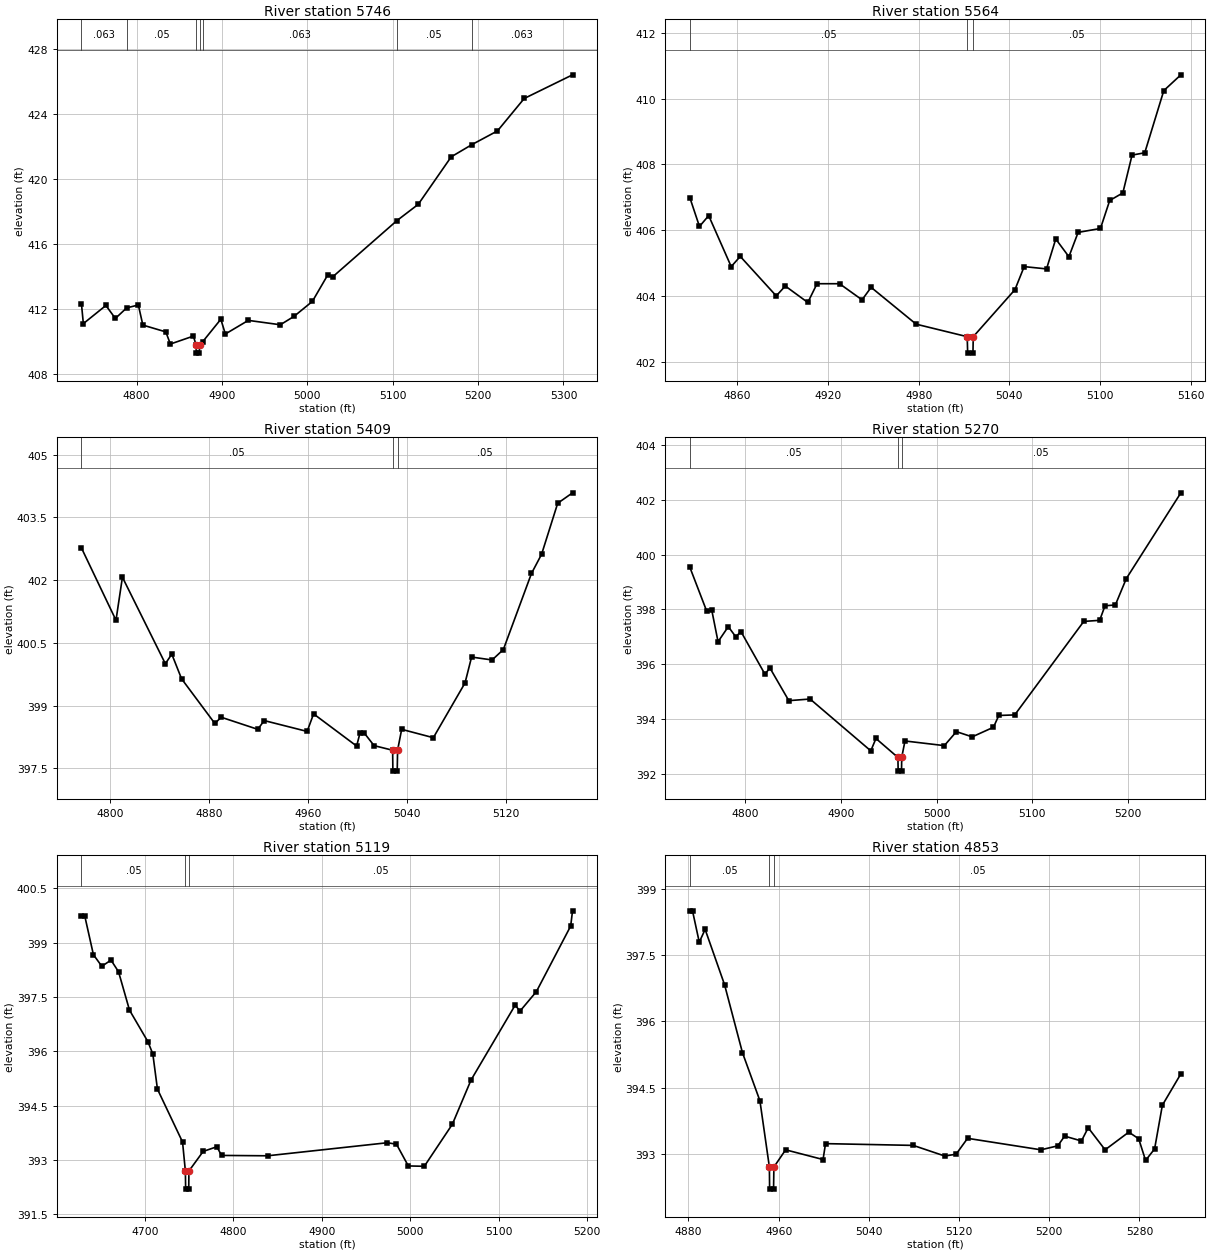
Type RM Length L Ch R = 1,5746,182,182,182
BEGIN DESCRIPTION:
North Twin Creek Trib E5746.267
END DESCRIPTION:
XS GIS Cut Line= 3
      2731778.76      6819125.36      2732030.75      6819205.74
      2732316.96      6819326.41
#Sta/Elev= 30
  4735.5  412.29  4737.7  411.08  4764.1  412.20  4775.2  411.40  4788.4  412.05
  4802.1  412.23  4807.4  410.99  4834.3  410.57  4839.6  409.82  4866.5  410.31
  4869.8  409.76  4870.0  409.26  4873.5  409.26  4873.8  409.76  4877.4  409.96
  4898.7  411.35  4904.0  410.44  4930.9  411.28  4968.4  411.01  4984.5  411.53
  5005.9  412.45  5024.2  414.11  5029.6  413.96  5104.8  417.43  5129.9  418.44
  5168.5  421.37  5192.6  422.12  5222.7  422.97  5254.0  424.97  5310.6  426.43
#Mann=7,-1,0
  4735.5   0.063       0  4788.4    0.05       0  4869.8   0.063       0
  4873.8    0.05       0  4877.4   0.063       0  5104.8    0.05       0
  5192.6   0.063       0
Bank Sta=4869.8,4873.8
Exp/Cntr=0.3,0.1

Type RM Length L Ch R = 1,5564,155,155,155
BEGIN DESCRIPTION:
North Twin Creek Trib E5564.13
END DESCRIPTION:
XS GIS Cut Line= 3
      2731805.28      6819193.75      2731903.38      6819336.37
      2731990.88      6819460.53
#Sta/Elev= 30
  4828.5  406.99  4834.9  406.11  4841.0  406.44  4855.9  404.89  4861.9  405.20
  4885.7  404.00  4891.7  404.30  4906.6  403.80  4912.7  404.37  4927.6  404.37
  4942.5  403.88  4948.5  404.26  4978.3  403.14  5012.1  402.76  5012.4  402.26
  5015.9  402.26  5016.1  402.76  5043.7  404.19  5049.8  404.89  5064.6  404.82
  5070.7  405.73  5079.4  405.19  5085.5  405.93  5100.3  406.05  5106.4  406.90
  5115.1  407.13  5121.2  408.28  5129.6  408.35  5142.2  410.24  5153.5  410.72
#Mann=3,-1,0
  4828.5    0.05       0  5012.1    0.05       0  5016.1    0.05       0
Bank Sta=5012.1,5016.1
Exp/Cntr=0.3,0.1

Type RM Length L Ch R = 1,5409,139,139,139
BEGIN DESCRIPTION:
North Twin Creek Trib E5408.63
END DESCRIPTION:
XS GIS Cut Line= 3
      2731712.71      6819192.90      2731771.52      6819411.20
      2731828.37      6819572.29
#Sta/Elev= 30
  4776.7  402.77  4804.6  401.04  4809.8  402.07  4844.5  400.00  4849.7  400.23
  4857.6  399.64  4884.5  398.57  4889.6  398.72  4919.2  398.43  4924.4  398.64
  4959.1  398.38  4964.3  398.80  4999.1  398.03  5001.8  398.34  5005.3  398.34
  5013.2  398.04  5028.2  397.93  5028.4  397.43  5031.9  397.43  5032.2  397.93
  5035.5  398.43  5061.1  398.23  5086.7  399.54  5092.0  400.16  5108.6  400.09
  5117.7  400.34  5140.4  402.16  5148.6  402.62  5161.6  403.84  5173.6  404.09
#Mann=3,-1,0
  4776.7    0.05       0  5028.2    0.05       0  5032.2    0.05       0
Bank Sta=5028.2,5032.2
Exp/Cntr=0.3,0.1

Type RM Length L Ch R = 1,5270,151,151,151
BEGIN DESCRIPTION:
North Twin Creek Trib E5270.21
END DESCRIPTION:
XS GIS Cut Line= 3
      2731543.37      6819173.32      2731634.64      6819418.37
      2731749.55      6819641.86
#Sta/Elev= 30
  4742.3  399.54  4760.0  397.93  4765.3  397.96  4771.8  396.82  4782.5  397.37
  4790.3  397.00  4795.7  397.19  4820.7  395.64  4826.0  395.86  4845.7  394.67
  4867.9  394.73  4931.3  392.84  4936.7  393.29  4959.6  392.60  4959.9  392.10
  4963.4  392.10  4963.6  392.60  4967.0  393.20  5008.1  393.03  5020.7  393.54
  5037.2  393.35  5059.4  393.70  5065.0  394.13  5081.6  394.15  5153.7  397.56
  5170.3  397.60  5175.9  398.13  5186.7  398.16  5198.1  399.12  5255.1  402.25
#Mann=3,-1,0
  4742.3    0.05       0  4959.6    0.05       0  4963.6    0.05       0
Bank Sta=4959.6,4963.6
Exp/Cntr=0.3,0.1

Type RM Length L Ch R = 1,5119,266,266,266
BEGIN DESCRIPTION:
North Twin Creek Trib E5119.1
END DESCRIPTION:
XS GIS Cut Line= 3
      2731448.43      6819178.88      2731551.42      6819534.60
      2731611.11      6819709.67
#Sta/Elev= 30
  4628.1  399.74  4631.8  399.74  4641.6  398.67  4651.1  398.35  4661.5  398.52
  4670.0  398.20  4682.4  397.14  4703.2  396.27  4708.8  395.93  4714.0  394.96
  4742.4  393.50  4745.6  392.70  4745.9  392.20  4749.4  392.20  4749.6  392.70
  4765.7  393.24  4781.2  393.37  4786.5  393.13  4838.5  393.12  4973.9  393.48
  4984.3  393.44  4997.7  392.84  5015.8  392.83  5047.5  393.99  5068.6  395.21
  5118.6  397.28  5123.9  397.11  5142.5  397.65  5181.3  399.46  5183.4  399.88
#Mann=3,-1,0
  4628.1    0.05       0  4745.6    0.05       0  4749.6    0.05       0
Bank Sta=4745.6,4749.6
Exp/Cntr=0.3,0.1

Type RM Length L Ch R = 1,4853,31,31,31
BEGIN DESCRIPTION:
North Twin Creek Trib E4853.47
END DESCRIPTION:
XS GIS Cut Line= 5
      2731424.44      6819261.45      2731389.74      6819377.54
      2731379.39      6819442.23      2731393.05      6819517.89
      2731535.23      6819614.76
#Sta/Elev= 30
  4881.2  398.50  4883.6  398.50  4889.6  397.79  4894.8  398.08  4912.0  396.83
  4927.9  395.29  4943.4  394.20  4951.8  392.70  4952.0  392.20  4955.5  392.20
  4955.8  392.70  4966.2  393.09  4999.4  392.87  5001.6  393.23  5079.4  393.19
  5107.3  392.95  5117.4  392.99  5127.6  393.35  5192.7  393.09  5207.6  393.18
  5213.7  393.40  5228.6  393.29  5234.6  393.59  5249.6  393.09  5270.6  393.49
  5279.4  393.34  5285.5  392.85  5293.5  393.11  5300.4  394.10  5316.8  394.81
#Mann=3,-1,0
  4881.2    0.05       0  4951.8    0.05       0  4955.8    0.05       0
Bank Sta=4951.8,4955.8
Exp/Cntr=0.3,0.1

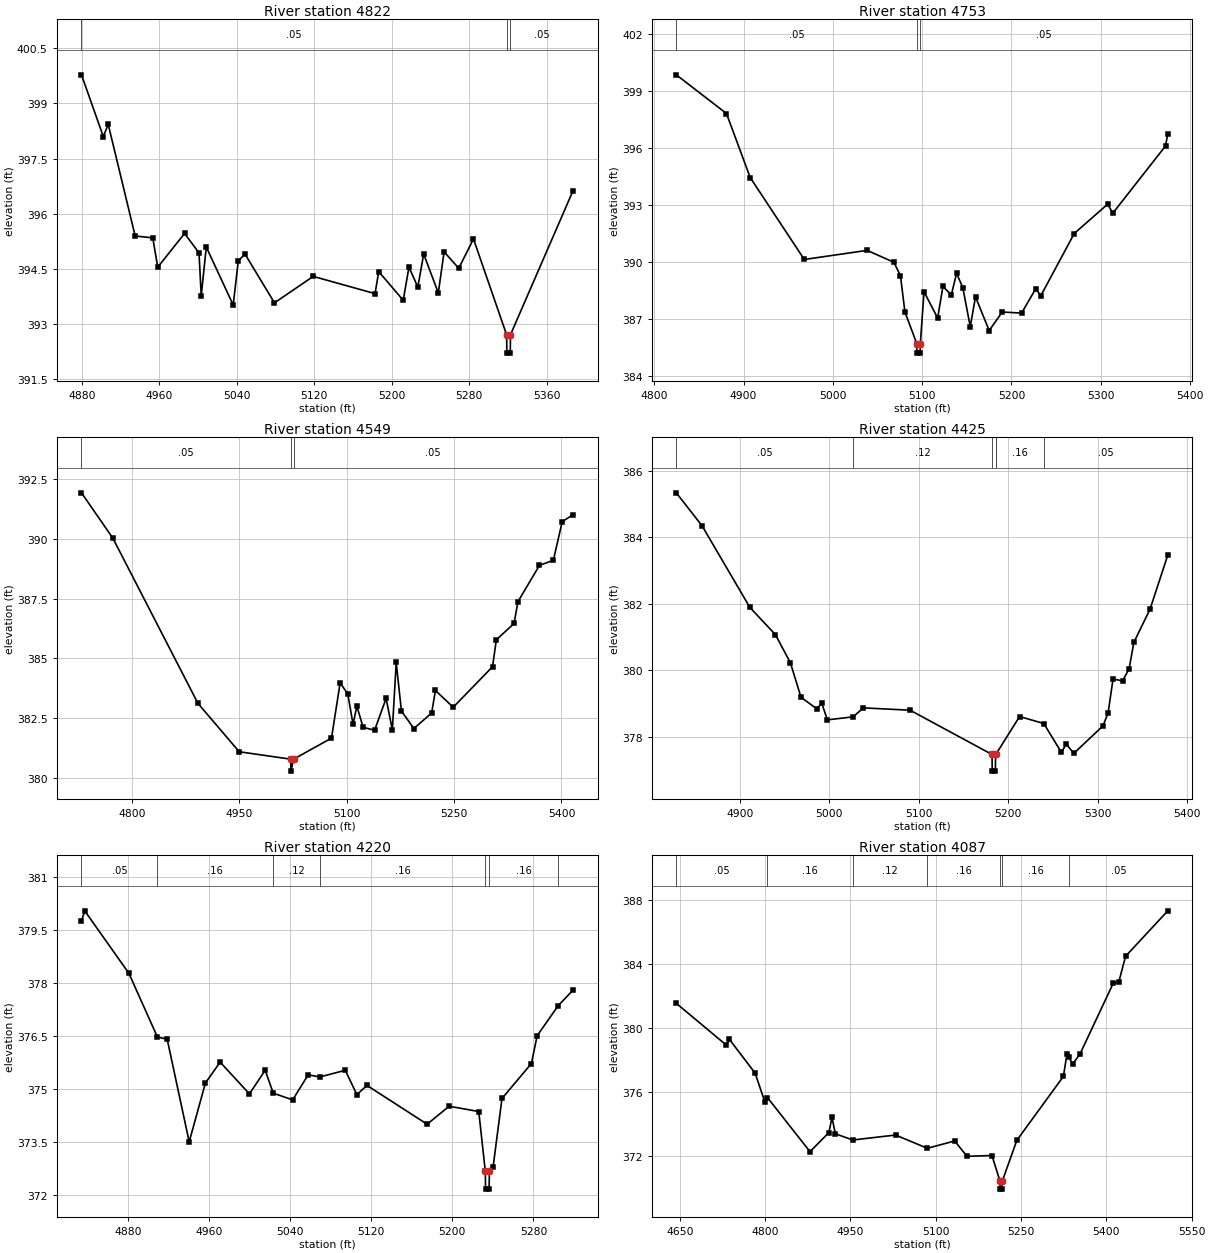
Type RM Length L Ch R = 1,4822,69,69,69
BEGIN DESCRIPTION:
North Twin Creek Trib E4821.74
END DESCRIPTION:
XS GIS Cut Line= 6
      2731385.97      6819256.65      2731362.22      6819375.59
      2731345.48      6819431.05      2731342.73      6819501.12
      2731373.49      6819552.50      2731539.65      6819660.32
#Sta/Elev= 30
  4879.7  399.78  4902.2  398.10  4907.3  398.43  4935.1  395.39  4953.3  395.34
  4958.4  394.54  4986.1  395.46  5001.0  394.93  5003.3  393.76  5008.5  395.09
  5036.3  393.51  5041.5  394.71  5048.4  394.90  5078.9  393.57  5118.9  394.29
  5182.7  393.82  5186.5  394.42  5211.8  393.64  5217.7  394.54  5226.9  394.00
  5232.9  394.90  5248.0  393.84  5254.0  394.96  5269.1  394.51  5284.3  395.31
  5318.5  392.70  5318.8  392.20  5322.3  392.20  5322.5  392.70  5387.0  396.62
#Mann=3,-1,0
  4879.7    0.05       0  5318.5    0.05       0  5322.5    0.05       0
Bank Sta=5318.5,5322.5
Exp/Cntr=0.3,0.1

Type RM Length L Ch R = 1,4753,204,204,204
BEGIN DESCRIPTION:
North Twin Creek Trib E4753.48
END DESCRIPTION:
XS GIS Cut Line= 5
      2731338.74      6819249.04      2731313.65      6819425.10
      2731310.28      6819521.14      2731354.92      6819592.32
      2731522.26      6819687.77
#Sta/Elev= 30
  4824.6  399.87  4880.8  397.83  4907.4  394.45  4968.0  390.13  5038.4  390.61
  5068.4  389.98  5075.7  389.28  5080.7  387.37  5094.0  385.69  5094.2  385.19
  5097.7  385.19  5098.0  385.69  5102.1  388.43  5117.4  387.04  5123.3  388.71
  5132.7  388.26  5138.6  389.40  5145.6  388.64  5153.9  386.59  5159.8  388.16
  5175.1  386.38  5189.8  387.36  5211.4  387.30  5227.2  388.58  5233.0  388.22
  5270.4  391.50  5307.9  393.05  5313.6  392.57  5372.7  396.12  5375.2  396.76
#Mann=3,-1,0
  4824.6    0.05       0  5094.0    0.05       0  5098.0    0.05       0
Bank Sta=5094,5098
Exp/Cntr=0.3,0.1

Type RM Length L Ch R = 1,4549,124,124,124
BEGIN DESCRIPTION:
North Twin Creek Trib E4548.89
END DESCRIPTION:
XS GIS Cut Line= 3
      2731141.31      6819322.43      2731202.66      6819588.80
      2731349.41      6819975.02
#Sta/Elev= 30
  4729.6  391.92  4773.5  390.02  4892.3  383.12  4949.9  381.10  5021.9  380.79
  5022.1  380.29  5025.9  380.79  5078.8  381.67  5090.9  383.98  5101.6  383.51
  5108.9  382.25  5114.3  383.00  5123.0  382.12  5139.0  382.00  5155.1  383.33
  5163.8  382.01  5169.2  384.83  5176.5  382.80  5193.9  382.07  5218.7  382.72
  5224.0  383.66  5248.8  382.96  5303.7  384.65  5309.1  385.78  5333.8  386.46
  5339.2  387.37  5369.3  388.89  5388.7  389.10  5401.1  390.72  5416.1  391.00
#Mann=3,-1,0
  4729.6    0.05       0  5021.9    0.05       0  5025.9    0.05       0
Bank Sta=5021.9,5025.9
Exp/Cntr=0.3,0.1

Type RM Length L Ch R = 1,4425,205,205,205
BEGIN DESCRIPTION:
Mapping XS 58d12e7a
END DESCRIPTION:
XS GIS Cut Line= 3
      2731025.57      6819484.73      2731096.20      6819641.40
      2731247.64      6819987.35
#Sta/Elev= 30
  4829.0  385.33  4857.8  384.34  4911.2  381.89  4939.8  381.07  4956.5  380.23
  4968.4  379.19  4986.1  378.84  4991.6  379.01  4997.9  378.51  5026.6  378.60
  5038.2  378.87  5090.4  378.80  5182.0  377.47  5182.2  376.97  5185.7  376.97
  5186.0  377.47  5186.2  377.47  5212.8  378.61  5239.9  378.40  5259.6  377.53
  5265.0  377.79  5273.3  377.50  5306.1  378.33  5311.8  378.72  5317.3  379.74
  5327.9  379.68  5335.2  380.04  5340.6  380.84  5358.6  381.83  5378.5  383.46
#Mann=6,-1,0
  4829.0    0.05       0  5026.6    0.12       0  5182.0    0.05       0
  5186.0    0.12       0  5186.2    0.16       0  5239.9    0.05       0
Bank Sta=5182,5186
Exp/Cntr=0.3,0.1

Type RM Length L Ch R = 1,4220,133,133,133
BEGIN DESCRIPTION:
Mapping XS 2af6102a
END DESCRIPTION:
XS GIS Cut Line= 4
      2730870.45      6819641.46      2730950.86      6819786.64
      2731006.82      6819876.36      2731110.91      6820062.08
#Sta/Elev= 30
  4834.4  379.76  4837.6  380.05  4881.1  378.28  4909.3  376.47  4918.9  376.41
  4940.6  373.50  4956.6  375.17  4971.1  375.76  5000.0  374.86  5015.5  375.53
  5023.5  374.88  5042.6  374.69  5057.9  375.40  5069.5  375.34  5094.5  375.53
  5105.9  374.84  5115.9  375.10  5175.2  374.00  5196.9  374.51  5226.1  374.36
  5232.6  372.66  5232.8  372.16  5236.3  372.16  5236.6  372.66  5240.3  372.80
  5249.0  374.73  5278.0  375.72  5283.7  376.51  5304.4  377.36  5319.0  377.80
#Mann=7,-1,0
  4834.4    0.05       0  4909.3    0.16       0  5023.5    0.12       0
  5069.5    0.16       0  5232.6    0.07       0  5236.6    0.16       0
  5304.4    0.05       0
Bank Sta=5232.6,5236.6
Exp/Cntr=0.3,0.1

Type RM Length L Ch R = 1,4087,136,136,136
BEGIN DESCRIPTION:
North Twin Creek Trib E4087.26
END DESCRIPTION:
XS GIS Cut Line= 3
      2730701.16      6819559.66      2730858.25      6819882.03
      2731098.71      6820326.78
#Sta/Elev= 30
  4643.8  381.57  4731.7  378.96  4737.3  379.31  4782.4  377.21  4799.4  375.42
  4804.1  375.68  4878.9  372.30  4912.0  373.49  4917.6  374.44  4923.4  373.42
  4954.0  373.03  5029.4  373.34  5085.3  372.51  5133.2  372.97  5155.0  372.01
  5198.8  372.06  5213.0  370.46  5213.2  369.96  5216.7  369.96  5217.0  370.46
  5242.6  373.01  5324.4  377.00  5330.9  378.43  5334.3  378.20  5340.6  377.77
  5353.6  378.40  5411.9  382.81  5421.9  382.91  5433.8  384.51  5508.0  387.35
#Mann=7,-1,0
  4643.8    0.05       0  4804.1    0.16       0  4954.0    0.12       0
  5085.3    0.16       0  5213.0    0.07       0  5217.0    0.16       0
  5334.3    0.05       0
Bank Sta=5213,5217
Exp/Cntr=0.3,0.1

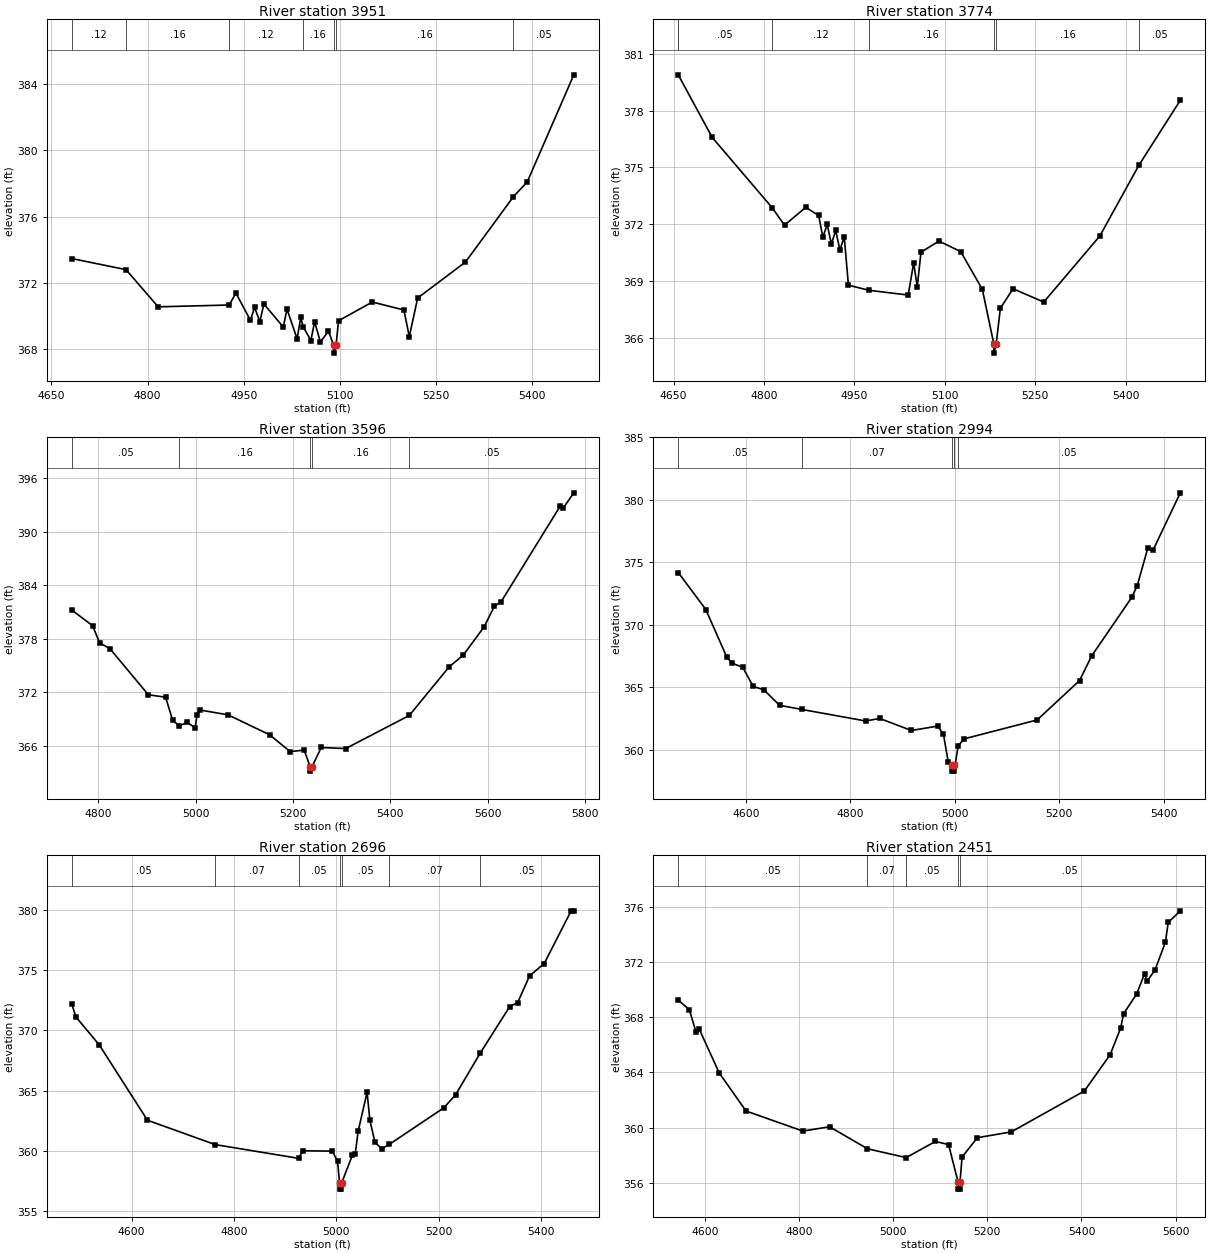
Type RM Length L Ch R = 1,3951,177,177,177
BEGIN DESCRIPTION:
North Twin Creek Trib E3951.05
END DESCRIPTION:
XS GIS Cut Line= 3
      2730562.52      6819705.38      2730753.45      6819962.70
      2730985.11      6820362.98
#Sta/Elev= 30
  4681.7  373.47  4766.3  372.80  4816.4  370.56  4927.2  370.67  4937.7  371.39
  4960.4  369.74  4966.7  370.53  4975.0  369.67  4981.3  370.73  5011.6  369.34
  5017.3  370.42  5033.1  368.64  5038.9  369.93  5042.4  369.37  5054.6  368.53
  5060.4  369.66  5069.5  368.43  5081.9  369.10  5089.9  368.27  5090.2  367.77
  5093.9  368.27  5097.7  369.72  5150.4  370.85  5199.6  370.37  5208.1  368.77
  5221.1  371.09  5295.7  373.26  5370.5  377.20  5391.9  378.08  5464.6  384.54
#Mann=7,-1,0
  4681.7    0.12       0  4766.3    0.16       0  4927.2    0.12       0
  5042.4    0.16       0  5089.9    0.07       0  5093.9    0.16       0
  5370.5    0.05       0
Bank Sta=5089.9,5093.9
Exp/Cntr=0.3,0.1

Type RM Length L Ch R = 1,3774,178,178,178
BEGIN DESCRIPTION:
North Twin Creek Trib E3773.68
END DESCRIPTION:
XS GIS Cut Line= 3
      2730344.83      6819772.99      2730590.62      6820010.82
      2730865.15      6820417.52
#Sta/Elev= 30
  4657.9  379.88  4714.0  376.59  4813.6  372.88  4834.1  371.96  4869.4  372.90
  4890.7  372.47  4897.7  371.33  4904.9  372.00  4911.8  370.97  4919.0  371.68
  4926.0  370.65  4933.2  371.35  4940.1  368.80  4974.0  368.53  5039.3  368.28
  5048.3  369.97  5054.3  368.72  5060.5  370.54  5090.3  371.12  5126.3  370.57
  5162.2  368.58  5181.2  365.72  5181.5  365.22  5185.2  365.72  5192.2  367.59
  5213.2  368.61  5264.1  367.91  5357.1  371.39  5422.5  375.15  5490.6  378.54
#Mann=6,-1,0
  4657.9    0.05       0  4813.6    0.12       0  4974.0    0.16       0
  5181.2    0.07       0  5185.2    0.16       0  5422.5    0.05       0
Bank Sta=5181.2,5185.2
Exp/Cntr=0.3,0.1

Type RM Length L Ch R = 1,3596,602,602,602
BEGIN DESCRIPTION:
North Twin Creek Trib E3595.669
END DESCRIPTION:
XS GIS Cut Line= 3
      2730276.00      6819860.99      2730426.00      6820061.00
      2730925.98      6820660.98
#Sta/Elev= 30
  4745.6  381.22  4788.3  379.46  4802.9  377.53  4823.7  376.90  4902.9  371.71
  4938.3  371.44  4952.9  368.83  4966.7  368.23  4982.1  368.61  4998.9  368.03
  5002.8  369.39  5009.3  370.00  5066.6  369.46  5151.8  367.23  5194.1  365.34
  5222.8  365.51  5235.1  363.65  5235.3  363.15  5239.1  363.65  5257.9  365.80
  5308.0  365.68  5438.7  369.39  5520.8  374.86  5549.5  376.15  5592.4  379.33
  5613.3  381.62  5627.6  382.17  5748.6  392.86  5755.2  392.68  5776.6  394.36
#Mann=5,-1,0
  4745.6    0.05       0  4966.7    0.16       0  5235.1    0.07       0
  5239.1    0.16       0  5438.7    0.05       0
Bank Sta=5235.1,5239.1
Exp/Cntr=0.3,0.1

Type RM Length L Ch R = 1,2994,298,298,298
BEGIN DESCRIPTION:
North Twin Creek Trib E2993.52
END DESCRIPTION:
XS GIS Cut Line= 3
      2729813.75      6820527.52      2730339.05      6820599.61
      2730767.99      6820643.46
#Sta/Elev= 30
  4470.4  374.19  4523.1  371.23  4563.5  367.41  4573.6  366.94  4593.8  366.61
  4614.0  365.08  4634.2  364.81  4664.5  363.57  4707.2  363.24  4829.0  362.32
  4856.2  362.52  4916.8  361.56  4967.3  361.91  4978.2  361.26  4987.4  359.03
  4994.6  358.81  4994.8  358.31  4998.3  358.31  4998.6  358.81  5000.6  358.81
  5006.4  360.34  5017.7  360.89  5157.6  362.40  5238.8  365.55  5262.0  367.52
  5339.3  372.23  5349.4  373.15  5369.5  376.14  5379.5  375.97  5431.8  380.56
#Mann=5,-1,0
  4470.4    0.05       0  4707.2    0.07       0  4994.6    0.07       0
  4998.6    0.07       0  5006.4    0.05       0
Bank Sta=4994.6,4998.6
Exp/Cntr=0.3,0.1

Type RM Length L Ch R = 1,2696,245,245,245
BEGIN DESCRIPTION:
North Twin Creek Trib E2695.89
END DESCRIPTION:
XS GIS Cut Line= 3
      2729790.39      6820584.13      2730229.25      6820861.99
      2730650.40      6821051.14
#Sta/Elev= 30
  4483.2  372.21  4491.2  371.13  4537.0  368.80  4631.1  362.56  4763.6  360.54
  4926.7  359.40  4934.5  360.03  4992.1  360.00  5002.6  359.19  5006.5  357.35
  5006.7  356.85  5010.2  356.85  5010.5  357.35  5031.6  359.66  5037.1  359.77
  5042.9  361.66  5060.3  364.88  5065.8  362.55  5075.8  360.73  5088.9  360.20
  5103.4  360.55  5210.3  363.59  5233.4  364.68  5281.2  368.11  5338.9  371.97
  5354.7  372.32  5377.9  374.53  5406.5  375.55  5459.1  379.92  5464.3  379.92
#Mann=7,-1,0
  4483.2    0.05       0  4763.6    0.07       0  4926.7    0.05       0
  5006.5    0.05       0  5010.5    0.05       0  5103.4    0.07       0
  5281.2    0.05       0
Bank Sta=5006.5,5010.5
Exp/Cntr=0.3,0.1

Type RM Length L Ch R = 1,2451,352,352,352
BEGIN DESCRIPTION:
North Twin Creek Trib E2450.5
END DESCRIPTION:
XS GIS Cut Line= 3
      2729735.71      6820658.16      2730036.32      6821002.93
      2730578.85      6821280.65
#Sta/Elev= 30
  4543.2  369.23  4566.7  368.54  4580.9  366.93  4587.5  367.15  4630.3  363.96
  4687.2  361.21  4807.8  359.76  4864.8  360.07  4945.2  358.48  5027.4  357.84
  5089.8  359.01  5117.7  358.78  5137.9  356.06  5138.1  355.56  5141.6  355.56
  5141.9  356.06  5146.3  357.88  5178.7  359.28  5250.9  359.70  5406.3  362.66
  5460.9  365.28  5483.3  367.21  5489.6  368.25  5517.4  369.68  5534.0  371.13
  5539.6  370.61  5556.2  371.40  5578.4  373.42  5584.4  374.85  5610.1  375.69
#Mann=5,-1,0
  4543.2    0.05       0  4945.2    0.07       0  5027.4    0.05       0
  5137.9    0.07       0  5141.9    0.05       0
Bank Sta=5137.9,5141.9
Exp/Cntr=0.3,0.1

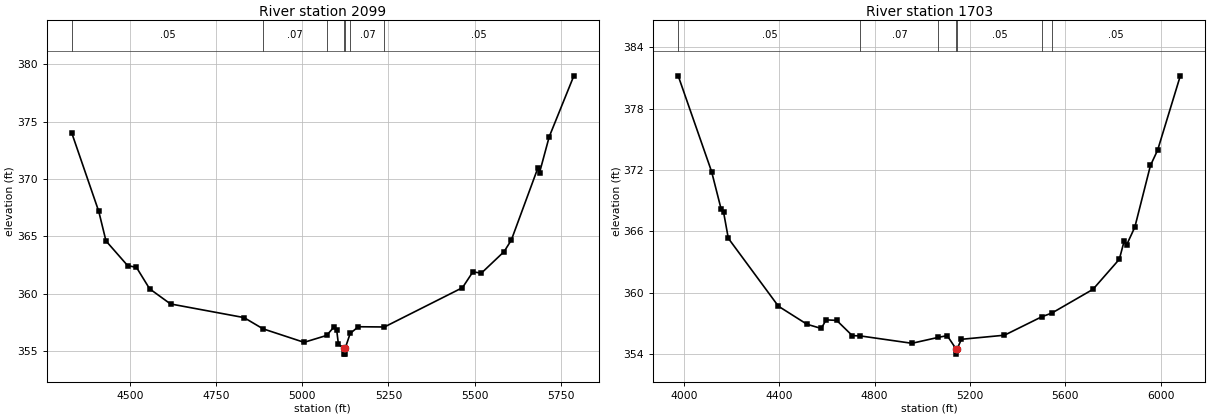
Type RM Length L Ch R = 1,2099,396,396,396
BEGIN DESCRIPTION:
North Twin Creek Trib E2099.3
END DESCRIPTION:
XS GIS Cut Line= 3
      2729656.64      6820645.96      2729853.07      6821294.76
      2730626.96      6821388.27
#Sta/Elev= 30
  4330.8  374.02  4409.2  367.17  4430.1  364.60  4492.8  362.45  4518.6  362.29
  4556.8  360.42  4617.4  359.10  4830.7  357.91  4885.8  356.93  5005.1  355.75
  5070.5  356.35  5092.2  357.10  5099.8  356.83  5104.8  355.58  5120.4  355.22
  5120.7  354.72  5124.2  354.72  5124.4  355.22  5139.0  356.53  5162.7  357.11
  5238.4  357.09  5464.9  360.52  5495.1  361.90  5519.8  361.79  5585.8  363.67
  5606.8  364.68  5683.7  370.96  5688.7  370.57  5716.7  373.69  5788.2  379.01
#Mann=7,-1,0
  4330.8    0.05       0  4885.8    0.07       0  5070.5    0.05       0
  5120.4    0.07       0  5124.4    0.05       0  5139.0    0.07       0
  5238.4    0.05       0
Bank Sta=5120.4,5124.4
Exp/Cntr=0.3,0.1

Type RM Length L Ch R = 1,1703,0,0,0
BEGIN DESCRIPTION:
North Twin Creek Trib E1703.331
END DESCRIPTION:
XS GIS Cut Line= 3
      2729626.00      6820561.00      2729602.88      6821584.84
      2730680.83      6821489.11
#Sta/Elev= 30
  3975.9  381.19  4115.9  371.83  4155.9  368.16  4166.0  367.88  4186.0  365.31
  4396.0  358.67  4516.0  356.90  4576.1  356.49  4596.1  357.33  4640.6  357.28
  4706.1  355.79  4740.1  355.76  4956.2  355.04  5067.2  355.62  5104.2  355.79
  5141.7  354.48  5141.9  353.98  5145.7  354.48  5163.8  355.43  5344.5  355.83
  5500.6  357.63  5543.6  358.00  5715.9  360.32  5826.4  363.26  5846.4  365.02
  5856.5  364.64  5891.4  366.40  5956.9  372.43  5987.0  373.93  6082.2  381.20
#Mann=7,-1,0
  3975.9    0.05       0  4740.1    0.07       0  5067.2    0.05       0
  5141.7    0.07       0  5145.7    0.05       0  5500.6    0.07       0
  5543.6    0.05       0
Bank Sta=5141.7,5145.7
Exp/Cntr=0.3,0.1

Chan Stop Cuts=-1