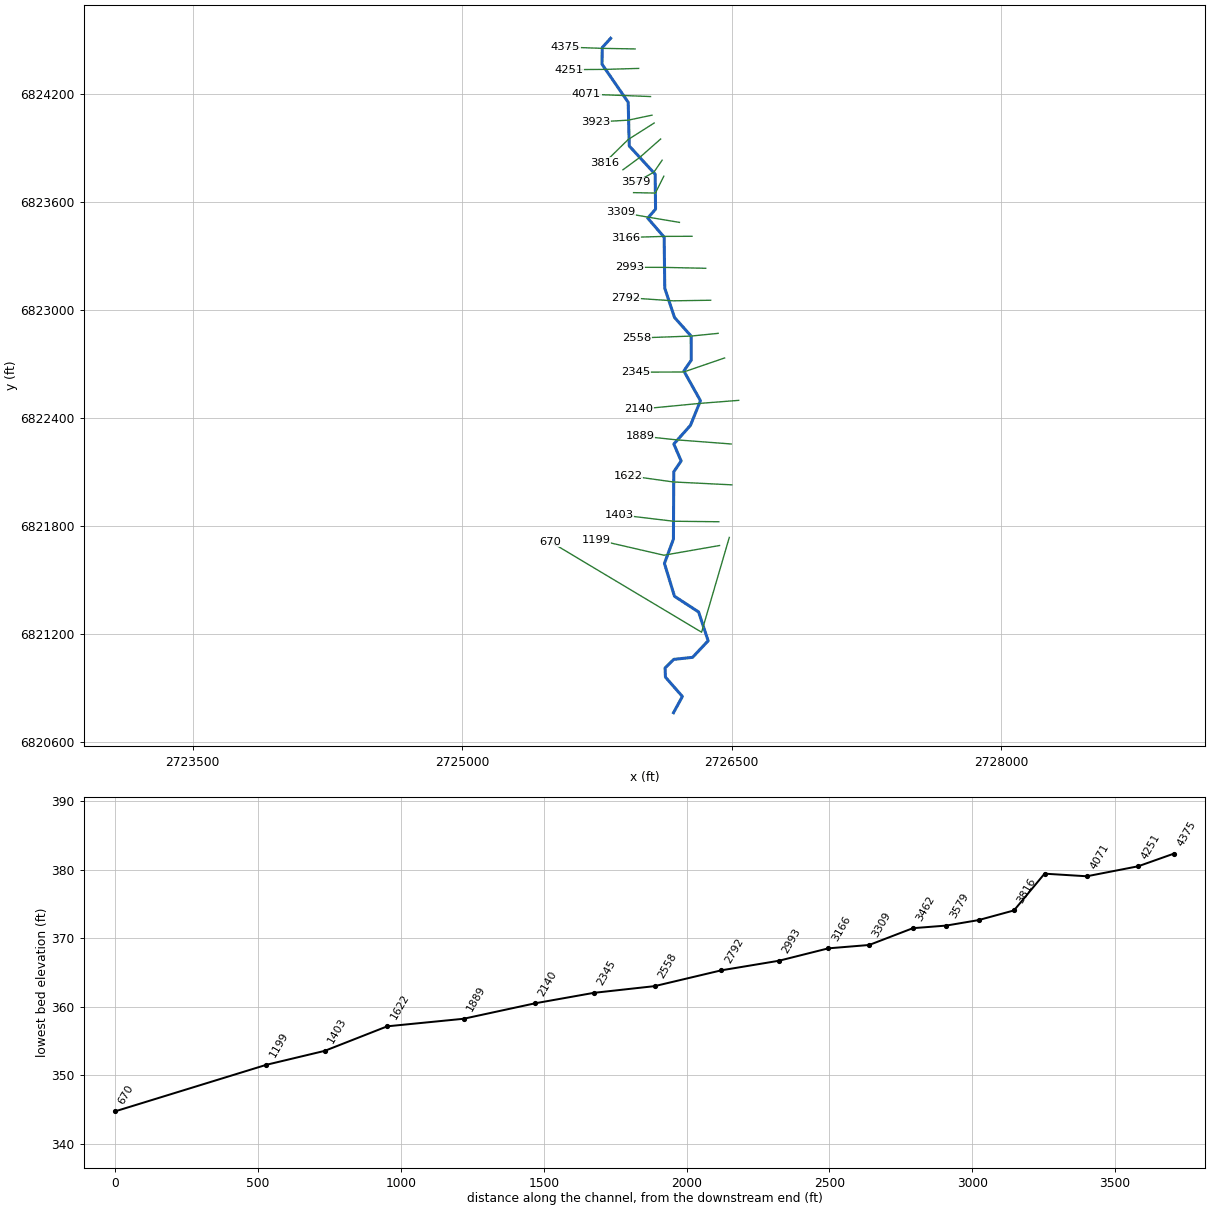
--- North Twin Creek Trib F.prj (project) ---

Proj Title=North Twin Creek Trib F Base Level Engineering
Current Plan=p01
Default Exp/Contr=0.3,0.1
English Units
Geom File=g01
Flow File=f01
Plan File=p01
BEGIN DESCRIPTION:
North Twin Creek Trib F
END DESCRIPTION:

--- North Twin Creek Trib F.p01 (plan) ---

Plan Title=Multiple Run
Short Identifier=Multiple
Geom File=g01
Flow File=f01
Subcritical Flow
K Sum by GR= 0
Std Step Tol= 0.01
Critical Tol= 0.01
Num of Std Step Trials= 20
Max Error Tol= 0.3
Flow Tol Ratio= 0.001
Split Flow NTrial= 30
Split Flow Tol= 0.02
Split Flow Ratio= 0.02
Log Output Level= 0
Friction Slope Method= 1
Unsteady Friction Slope Method= 2
Unsteady Bridges Friction Slope Method= 1
Parabolic Critical Depth
Global Vel Dist=  1 , 1 , 1
Global Log Level= 0
CheckData=True
Encroach Param= -1, 0, 0, 0
BEGIN DESCRIPTION:
Multiple Run
END DESCRIPTION:

--- North Twin Creek Trib F.f01 (steady flow) ---

Flow Title=Multiple
Number of Profiles=7
Profile Names=10-year,25-year,50-year,1pct_min,100-year,1pct_plu,500-year
River Rch & RM= North Twin Creek,Reach-1,4375
      78      90      99      54     108     215     127
River Rch & RM= North Twin Creek,Reach-1,3309
     487     647     775     461     920    1835    1294
Boundary for River Rch & Prof#=North Twin Creek,Reach-1,1
Up Type=0
Dn Type=3
Dn Slope=0.005
Boundary for River Rch & Prof#=North Twin Creek,Reach-1,2
Up Type=0
Dn Type=3
Dn Slope=0.005
Boundary for River Rch & Prof#=North Twin Creek,Reach-1,3
Up Type=0
Dn Type=3
Dn Slope=0.005
Boundary for River Rch & Prof#=North Twin Creek,Reach-1,4
Up Type=0
Dn Type=3
Dn Slope=0.005
Boundary for River Rch & Prof#=North Twin Creek,Reach-1,5
Up Type=0
Dn Type=3
Dn Slope=0.005
Boundary for River Rch & Prof#=North Twin Creek,Reach-1,6
Up Type=0
Dn Type=3
Dn Slope=0.005
Boundary for River Rch & Prof#=North Twin Creek,Reach-1,7
Up Type=0
Dn Type=3
Dn Slope=0.005

--- North Twin Creek Trib F.g01 (geometry) ---

Geom Title=Existing Conditions

River Reach=North Twin Creek,Reach-1
Reach XY= 30
      2725826.00      6824511.00      2725779.18      6824459.59
      2725777.96      6824366.88      2725923.76      6824155.07
      2725929.54      6823912.46      2726073.95      6823755.15
      2726076.00      6823561.00      2726032.59      6823511.01
      2726123.93      6823405.15      2726127.22      6823121.50
      2726181.54      6822958.58      2726273.94      6822855.14
      2726274.63      6822721.44      2726233.53      6822660.99
      2726325.93      6822495.61      2726270.16      6822358.71
      2726177.66      6822254.95      2726218.41      6822161.01
      2726177.38      6822100.56      2726175.48      6821726.22
      2726125.40      6821590.95      2726181.42      6821408.33
      2726315.61      6821321.10      2726368.69      6821160.89
      2726282.21      6821068.86      2726177.22      6821057.47
      2726129.00      6821009.60      2726131.07      6820958.74
      2726225.34      6820851.29      2726176.00      6820761.00

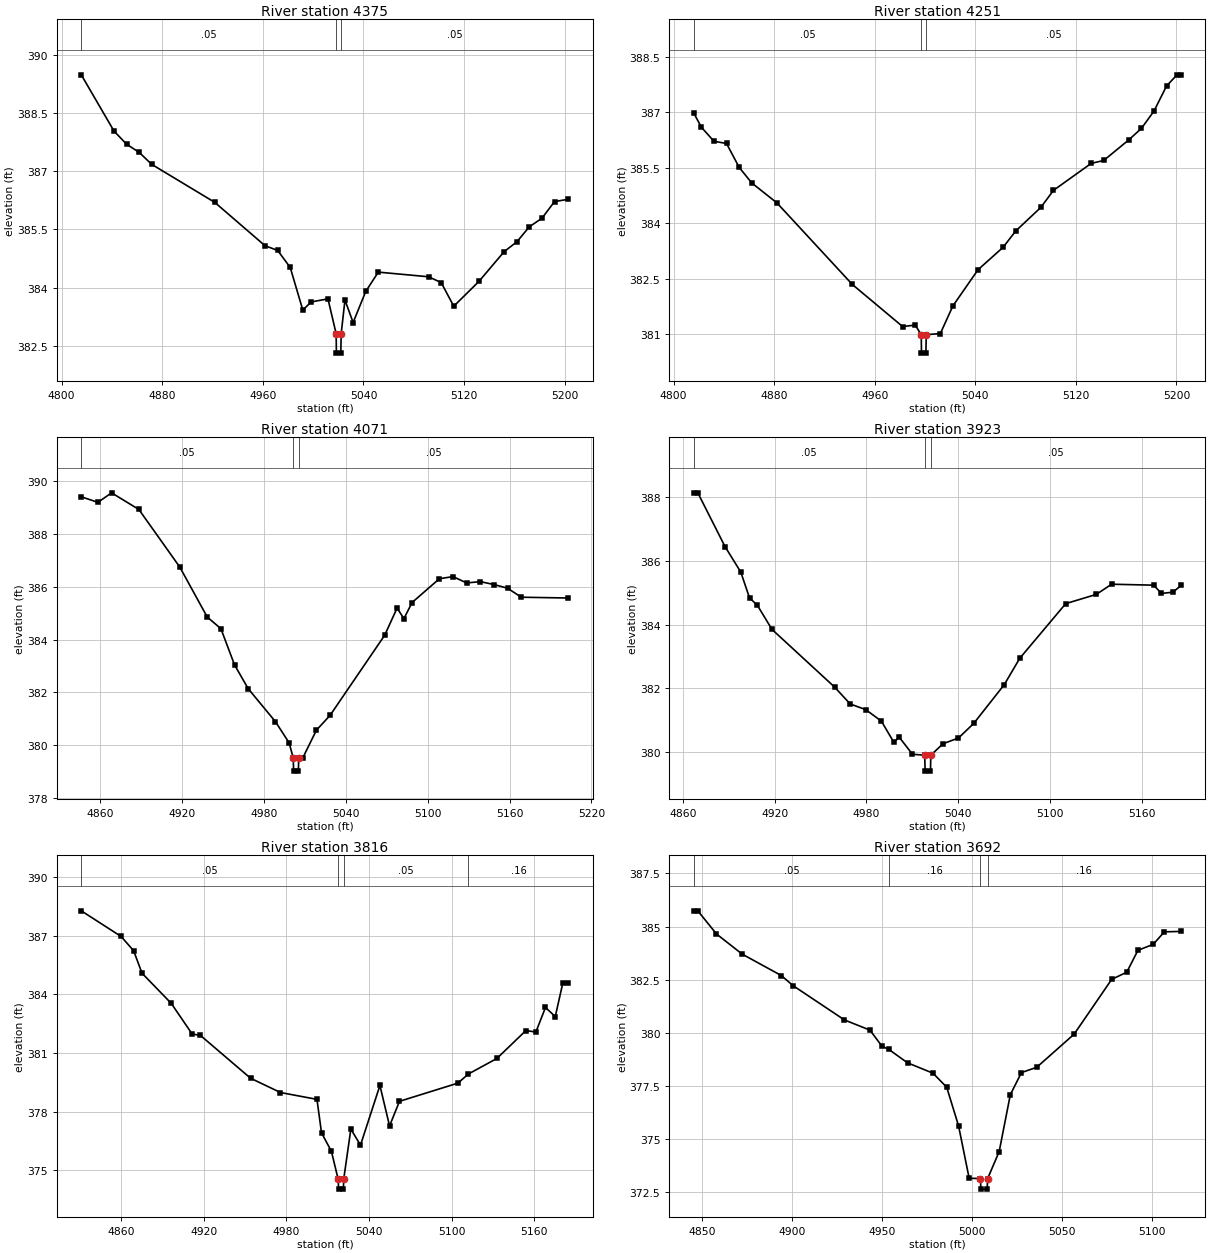
Type RM Length L Ch R = 1,4375,124,124,124
BEGIN DESCRIPTION:
North Twin Creek Trib F4375.379
END DESCRIPTION:
XS GIS Cut Line= 3
      2725962.04      6824451.87      2725777.77      6824455.16
      2725574.89      6824462.31
#Sta/Elev= 30
  4815.7  389.49  4841.7  388.04  4851.7  387.70  4861.7  387.49  4871.7  387.18
  4921.8  386.20  4961.8  385.08  4971.8  384.96  4981.8  384.52  4991.8  383.42
  4998.4  383.63  5011.8  383.71  5018.3  382.81  5018.5  382.31  5022.0  382.31
  5022.3  382.81  5025.3  383.68  5031.8  383.10  5041.8  383.90  5051.8  384.40
  5091.8  384.28  5101.8  384.13  5111.8  383.52  5131.8  384.16  5151.9  384.93
  5161.9  385.18  5171.9  385.57  5181.9  385.79  5191.9  386.22  5203.0  386.28
#Mann=3,-1,0
  4815.7    0.05       0  5018.3    0.05       0  5022.3    0.05       0
Bank Sta=5018.3,5022.3
Exp/Cntr=0.3,0.1

Type RM Length L Ch R = 1,4251,180,180,180
BEGIN DESCRIPTION:
North Twin Creek Trib F4251.24
END DESCRIPTION:
XS GIS Cut Line= 3
      2725982.04      6824343.58      2725797.51      6824338.19
      2725594.52      6824336.69
#Sta/Elev= 29
  4816.1  386.98  4822.1  386.60  4832.1  386.22  4842.1  386.16  4852.2  385.51
  4862.2  385.09  4882.2  384.55  4942.2  382.34  4982.2  381.20  4992.2  381.24
  4997.0  380.98  4997.2  380.48  5000.7  380.48  5001.0  380.98  5012.2  381.01
  5022.2  381.76  5042.2  382.74  5062.2  383.35  5072.2  383.79  5092.2  384.43
  5102.2  384.89  5132.2  385.62  5142.2  385.70  5162.2  386.26  5172.2  386.57
  5182.2  387.04  5192.2  387.72  5200.5  388.02  5203.7  388.02
#Mann=3,-1,0
  4816.1    0.05       0  4997.0    0.05       0  5001.0    0.05       0
Bank Sta=4997,5001
Exp/Cntr=0.3,0.1

Type RM Length L Ch R = 1,4071,148,148,148
BEGIN DESCRIPTION:
North Twin Creek Trib F4070.85
END DESCRIPTION:
XS GIS Cut Line= 3
      2726048.19      6824187.10      2725890.92      6824193.17
      2725691.44      6824200.41
#Sta/Elev= 30
  4846.2  389.40  4858.4  389.19  4868.4  389.55  4888.4  388.92  4918.4  386.74
  4938.5  384.85  4948.5  384.41  4958.5  383.04  4968.5  382.14  4988.5  380.89
  4998.5  380.09  5001.5  379.52  5001.8  379.02  5005.3  379.02  5005.5  379.52
  5008.5  379.52  5018.5  380.57  5028.5  381.13  5068.5  384.16  5077.6  385.19
  5082.6  384.79  5088.6  385.40  5108.6  386.30  5118.6  386.38  5128.6  386.14
  5138.6  386.19  5148.6  386.08  5158.6  385.94  5168.6  385.60  5203.2  385.57
#Mann=3,-1,0
  4846.2    0.05       0  5001.5    0.05       0  5005.5    0.05       0
Bank Sta=5001.5,5005.5
Exp/Cntr=0.3,0.1

Type RM Length L Ch R = 1,3923,107,107,107
BEGIN DESCRIPTION:
North Twin Creek Trib F3923.42
END DESCRIPTION:
XS GIS Cut Line= 3
      2726056.00      6824083.63      2725924.35      6824055.87
      2725740.71      6824045.10
#Sta/Elev= 30
  4867.2  388.14  4869.8  388.14  4887.6  386.45  4897.9  385.65  4903.6  384.84
  4908.7  384.61  4918.3  383.85  4959.2  382.04  4969.4  381.51  4979.6  381.33
  4989.8  380.97  4998.0  380.30  5001.4  380.47  5010.1  379.93  5018.1  379.90
  5018.4  379.40  5021.9  379.40  5022.1  379.90  5030.1  380.26  5040.2  380.44
  5050.2  380.90  5070.2  382.12  5080.2  382.94  5110.3  384.66  5130.3  384.95
  5140.3  385.27  5167.8  385.24  5172.9  384.98  5180.4  385.02  5185.7  385.23
#Mann=3,-1,0
  4867.2    0.05       0  5018.1    0.05       0  5022.1    0.05       0
Bank Sta=5018.1,5022.1
Exp/Cntr=0.3,0.1

Type RM Length L Ch R = 1,3816,124,124,124
BEGIN DESCRIPTION:
North Twin Creek Trib F3816.49
END DESCRIPTION:
XS GIS Cut Line= 3
      2726068.06      6824039.77      2725923.56      6823948.05
      2725793.15      6823820.31
#Sta/Elev= 30
  4831.2  388.27  4860.1  386.96  4869.2  386.23  4875.3  385.08  4896.5  383.54
  4911.7  381.97  4917.7  381.90  4954.1  379.71  4975.8  378.98  5002.3  378.63
  5005.6  376.92  5012.8  375.97  5017.7  374.54  5018.0  374.04  5021.5  374.04
  5021.7  374.54  5026.9  377.11  5033.9  376.29  5048.0  379.34  5055.0  377.27
  5062.2  378.53  5104.6  379.46  5112.3  379.93  5132.9  380.72  5154.0  382.15
  5161.2  382.07  5168.2  383.33  5175.3  382.86  5180.8  384.59  5184.9  384.59
#Mann=4,-1,0
  4831.2    0.05       0  5017.7    0.05       0  5021.7    0.05       0
  5112.3    0.16       0
Bank Sta=5017.7,5021.7
Exp/Cntr=0.3,0.1

Type RM Length L Ch R = 1,3692,113,113,113
BEGIN DESCRIPTION:
North Twin Creek Trib F3692.26
END DESCRIPTION:
XS GIS Cut Line= 3
      2726104.30      6823950.99      2725987.63      6823848.24
      2725894.41      6823779.81
#Sta/Elev= 30
  4845.2  385.74  4847.4  385.74  4857.8  384.65  4872.1  383.70  4893.9  382.69
  4900.5  382.21  4929.0  380.60  4943.2  380.12  4949.9  379.36  4953.7  379.21
  4964.1  378.58  4978.3  378.09  4985.9  377.43  4992.5  375.61  4998.4  373.14
  5004.7  373.13  5004.9  372.63  5008.4  372.63  5008.7  373.13  5015.1  374.40
  5021.3  377.08  5027.5  378.12  5036.0  378.37  5056.8  379.93  5077.7  382.51
  5086.1  382.85  5092.3  383.88  5100.8  384.16  5107.0  384.75  5116.3  384.77
#Mann=4,-1,0
  4845.2    0.05       0  4953.7    0.16       0  5004.7    0.07       0
  5008.7    0.16       0
Bank Sta=5004.7,5008.7
Exp/Cntr=0.3,0.1

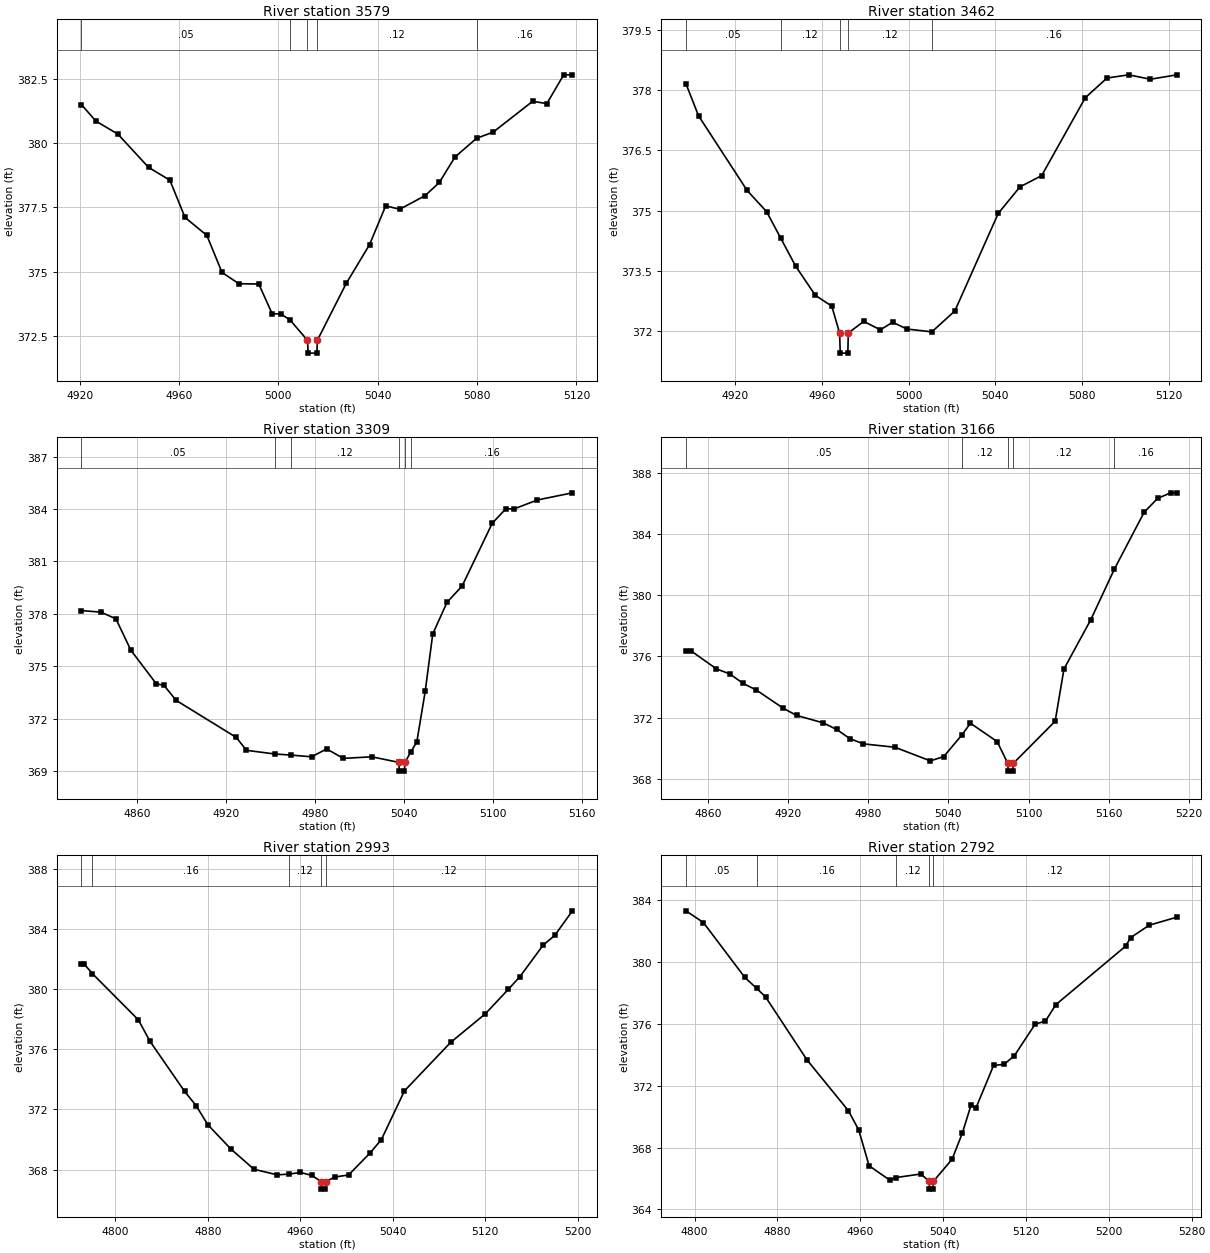
Type RM Length L Ch R = 1,3579,117,117,117
BEGIN DESCRIPTION:
Mapping XS a1de9b64
END DESCRIPTION:
XS GIS Cut Line= 3
      2726112.67      6823833.20      2726067.17      6823767.18
      2725964.86      6823709.36
#Sta/Elev= 30
  4920.7  381.50  4926.5  380.86  4935.4  380.35  4947.7  379.06  4956.3  378.56
  4962.4  377.11  4971.2  376.41  4977.3  374.97  4984.1  374.53  4992.1  374.52
  4997.5  373.36  5000.9  373.36  5004.7  373.12  5011.7  372.33  5012.0  371.83
  5015.5  371.83  5015.7  372.33  5027.3  374.54  5036.7  376.05  5043.2  377.56
  5048.9  377.43  5059.1  377.96  5064.8  378.47  5071.1  379.46  5079.8  380.19
  5086.5  380.43  5102.4  381.63  5108.1  381.54  5114.9  382.66  5118.4  382.66
#Mann=5,-1,0
  4920.7    0.05       0  5004.7    0.12       0  5011.7    0.05       0
  5015.7    0.12       0  5079.8    0.16       0
Bank Sta=5011.7,5015.7
Exp/Cntr=0.3,0.1

Type RM Length L Ch R = 1,3462,153,153,153
BEGIN DESCRIPTION:
Mapping XS afee067b
END DESCRIPTION:
XS GIS Cut Line= 3
      2726122.09      6823744.23      2726075.04      6823650.47
      2725953.76      6823652.83
#Sta/Elev= 26
  4897.4  378.16  4903.2  377.36  4925.6  375.50  4934.6  374.97  4941.0  374.32
  4947.9  373.62  4957.0  372.89  4964.6  372.62  4968.2  371.95  4968.5  371.45
  4972.0  371.45  4972.2  371.95  4979.3  372.24  4987.0  372.03  4992.6  372.22
  4999.2  372.05  5010.7  371.98  5021.3  372.50  5041.3  374.93  5051.3  375.59
  5061.3  375.87  5081.4  377.81  5091.4  378.30  5101.4  378.38  5111.4  378.27
  5123.6  378.38
#Mann=5,-1,0
  4897.4    0.05       0  4941.0    0.12       0  4968.2    0.07       0
  4972.2    0.12       0  5010.7    0.16       0
Bank Sta=4968.2,4972.2
Exp/Cntr=0.3,0.1

Type RM Length L Ch R = 1,3309,143,143,143
BEGIN DESCRIPTION:
Mapping XS 37f80355
END DESCRIPTION:
XS GIS Cut Line= 3
      2726208.89      6823487.35      2726031.85      6823516.98
      2725882.79      6823542.94
#Sta/Elev= 30
  4822.5  378.19  4835.6  378.10  4845.7  377.72  4855.8  375.92  4873.0  373.99
  4878.0  373.92  4886.3  373.05  4926.8  370.93  4933.7  370.19  4952.9  369.98
  4963.4  369.92  4977.5  369.82  4987.7  370.27  4999.0  369.73  5018.1  369.82
  5036.4  369.50  5036.6  369.00  5040.1  369.00  5040.4  369.50  5044.4  370.09
  5048.5  370.69  5054.1  373.56  5059.2  376.85  5068.8  378.66  5079.0  379.60
  5099.3  383.19  5108.6  384.03  5113.7  384.00  5129.7  384.52  5153.3  384.93
#Mann=6,-1,0
  4822.5    0.05       0  4952.9    0.16       0  4963.4    0.12       0
  5036.4    0.07       0  5040.4    0.12       0  5044.4    0.16       0
Bank Sta=5036.4,5040.4
Exp/Cntr=0.3,0.1

Type RM Length L Ch R = 1,3166,173,173,173
BEGIN DESCRIPTION:
North Twin Creek Trib F3166.195
END DESCRIPTION:
XS GIS Cut Line= 3
      2726278.85      6823410.08      2726122.45      6823409.54
      2725911.54      6823403.23
#Sta/Elev= 30
  4843.6  376.36  4847.5  376.36  4866.4  375.19  4876.4  374.86  4886.4  374.24
  4896.4  373.80  4916.4  372.62  4926.4  372.15  4946.4  371.66  4956.4  371.23
  4966.4  370.63  4976.4  370.29  5000.0  370.07  5026.5  369.18  5036.5  369.46
  5050.1  370.87  5056.5  371.64  5076.5  370.44  5084.5  369.01  5084.7  368.51
  5088.2  368.51  5088.5  369.01  5119.9  371.77  5126.5  375.18  5146.5  378.39
  5164.3  381.72  5186.5  385.42  5196.5  386.32  5206.3  386.69  5211.0  386.69
#Mann=5,-1,0
  4843.6    0.05       0  5050.1    0.12       0  5084.5    0.05       0
  5088.5    0.12       0  5164.3    0.16       0
Bank Sta=5084.5,5088.5
Exp/Cntr=0.3,0.1

Type RM Length L Ch R = 1,2993,201,201,201
BEGIN DESCRIPTION:
North Twin Creek Trib F2993.35
END DESCRIPTION:
XS GIS Cut Line= 3
      2726355.21      6823232.16      2726124.29      6823237.16
      2725930.67      6823237.82
#Sta/Elev= 30
  4770.7  381.69  4772.8  381.69  4780.2  381.03  4819.9  377.96  4829.9  376.54
  4859.9  373.20  4869.9  372.25  4879.9  370.99  4899.9  369.37  4919.9  368.02
  4940.0  367.65  4950.5  367.70  4960.0  367.81  4970.0  367.61  4978.0  367.20
  4978.2  366.70  4981.7  366.70  4982.0  367.20  4990.0  367.51  5001.7  367.64
  5020.0  369.08  5030.0  369.98  5050.0  373.23  5090.0  376.46  5120.0  378.36
  5140.0  380.00  5150.0  380.84  5170.0  382.93  5180.0  383.57  5195.3  385.21
#Mann=5,-1,0
  4770.7    0.05       0  4780.2    0.16       0  4950.5    0.12       0
  4978.0    0.07       0  4982.0    0.12       0
Bank Sta=4978,4982
Exp/Cntr=0.3,0.1

Type RM Length L Ch R = 1,2792,234,234,234
BEGIN DESCRIPTION:
North Twin Creek Trib F2791.55
END DESCRIPTION:
XS GIS Cut Line= 3
      2726382.85      6823054.44      2726174.20      6823051.29
      2725909.38      6823069.20
#Sta/Elev= 30
  4791.6  383.31  4808.5  382.55  4848.5  379.00  4860.0  378.29  4868.5  377.74
  4908.5  373.67  4948.5  370.38  4958.5  369.13  4968.5  366.82  4988.5  365.89
  4994.6  366.06  5018.5  366.29  5026.5  365.81  5026.8  365.31  5030.3  365.31
  5030.5  365.81  5048.6  367.24  5058.6  368.95  5066.8  370.72  5071.8  370.58
  5088.7  373.31  5098.7  373.38  5108.7  373.93  5128.8  375.98  5138.8  376.18
  5148.8  377.24  5216.1  381.02  5221.1  381.58  5239.0  382.38  5265.7  382.90
#Mann=5,-1,0
  4791.6    0.05       0  4860.0    0.16       0  4994.6    0.12       0
  5026.5    0.07       0  5030.5    0.12       0
Bank Sta=5026.5,5030.5
Exp/Cntr=0.3,0.1

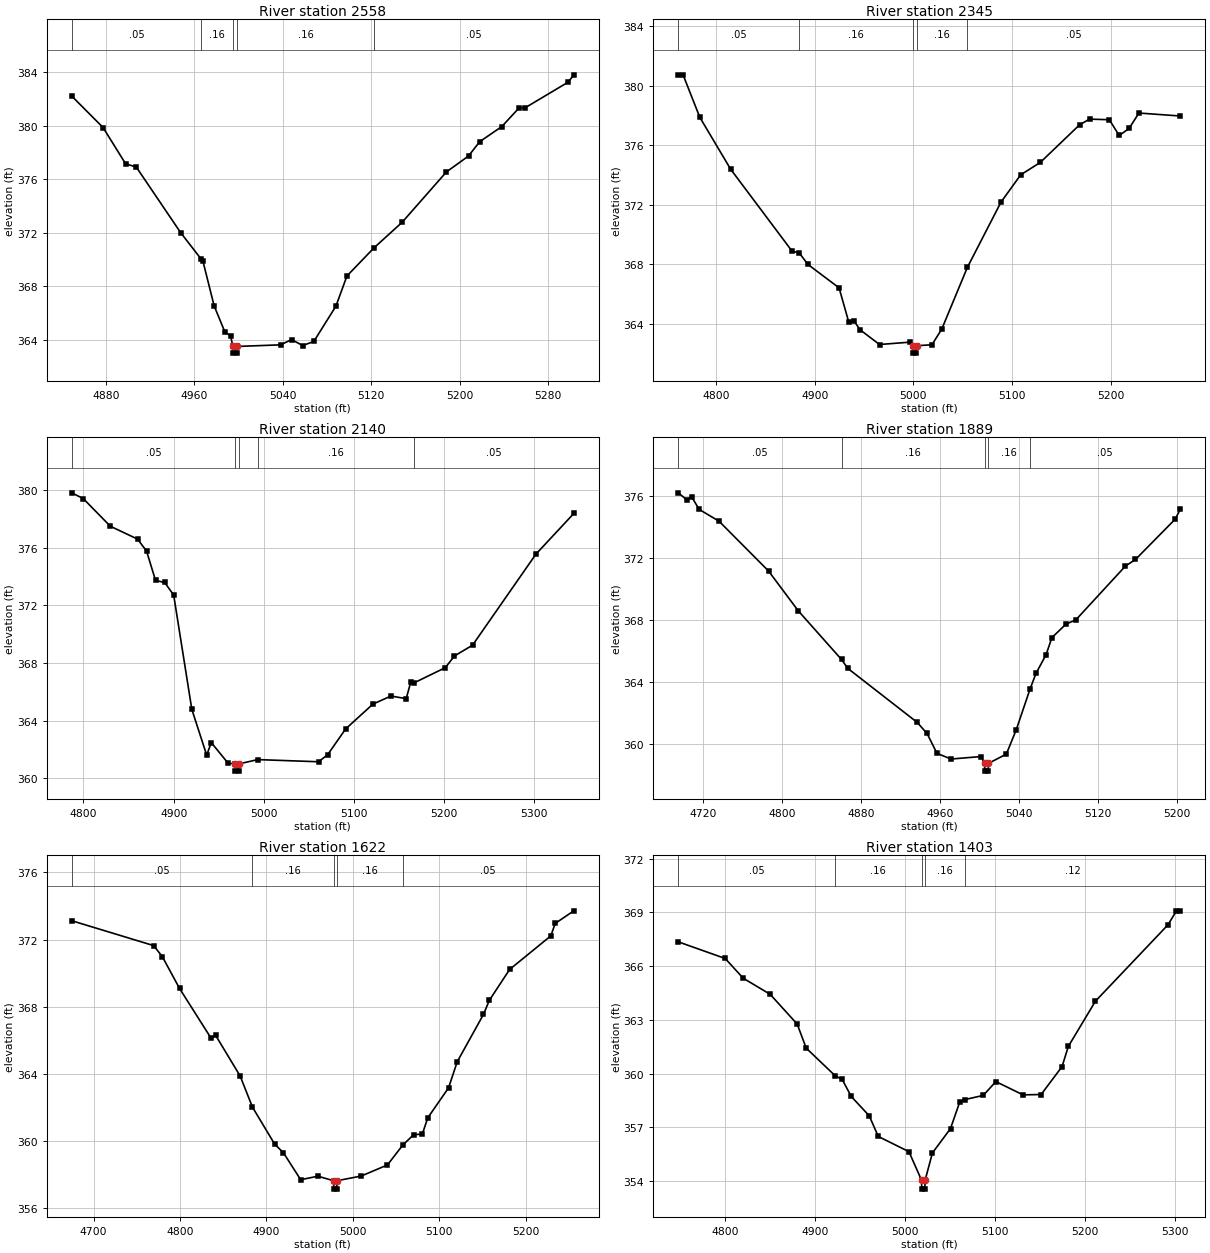
Type RM Length L Ch R = 1,2558,213,213,213
BEGIN DESCRIPTION:
North Twin Creek Trib F2558.42
END DESCRIPTION:
XS GIS Cut Line= 3
      2726424.14      6822870.42      2726273.44      6822855.21
      2725970.81      6822844.24
#Sta/Elev= 30
  4849.0  382.22  4877.3  379.87  4897.7  377.16  4907.4  376.91  4947.6  372.00
  4966.3  370.01  4967.7  369.87  4977.8  366.54  4987.7  364.55  4992.7  364.31
  4994.7  363.50  4994.9  363.00  4998.4  363.00  4998.7  363.50  5037.9  363.62
  5047.9  364.01  5057.9  363.57  5068.0  363.87  5088.0  366.51  5098.0  368.77
  5122.2  370.85  5148.0  372.79  5188.0  376.55  5208.0  377.74  5218.1  378.81
  5238.1  379.94  5253.9  381.35  5258.9  381.33  5298.1  383.26  5303.3  383.81
#Mann=5,-1,0
  4849.0    0.05       0  4966.3    0.16       0  4994.7    0.07       0
  4998.7    0.16       0  5122.2    0.05       0
Bank Sta=4994.7,4998.7
Exp/Cntr=0.3,0.1

Type RM Length L Ch R = 1,2345,205,205,205
BEGIN DESCRIPTION:
North Twin Creek Trib F2344.9
END DESCRIPTION:
XS GIS Cut Line= 3
      2726460.37      6822733.58      2726232.90      6822655.54
      2725963.98      6822654.45
#Sta/Elev= 30
  4761.4  380.74  4766.3  380.74  4783.3  377.88  4814.6  374.39  4877.1  368.86
  4884.0  368.78  4892.9  367.99  4924.6  366.41  4934.4  364.11  4939.6  364.21
  4945.7  363.60  4965.6  362.60  4996.9  362.76  4999.2  362.52  4999.4  362.02
  5002.9  362.02  5003.2  362.52  5018.8  362.58  5028.8  363.64  5054.7  367.78
  5088.8  372.17  5108.8  374.01  5128.8  374.85  5168.8  377.39  5178.8  377.76
  5198.8  377.72  5208.8  376.66  5218.8  377.13  5228.8  378.17  5270.8  377.97
#Mann=5,-1,0
  4761.4    0.05       0  4884.0    0.16       0  4999.2    0.07       0
  5003.2    0.16       0  5054.7    0.05       0
Bank Sta=4999.2,5003.2
Exp/Cntr=0.3,0.1

Type RM Length L Ch R = 1,2140,251,251,251
BEGIN DESCRIPTION:
North Twin Creek Trib F2140.25
END DESCRIPTION:
XS GIS Cut Line= 3
      2726538.66      6822497.73      2726324.07      6822481.03
      2725984.17      6822448.41
#Sta/Elev= 30
  4787.0  379.81  4799.7  379.41  4829.8  377.49  4859.9  376.60  4869.9  375.77
  4879.9  373.73  4890.0  373.59  4900.0  372.72  4920.1  364.79  4936.6  361.61
  4941.7  362.48  4960.2  361.06  4968.2  361.00  4968.5  360.50  4972.0  360.50
  4972.2  361.00  4993.2  361.30  5060.6  361.15  5070.6  361.63  5090.7  363.43
  5120.9  365.15  5140.9  365.71  5157.8  365.53  5162.8  366.66  5166.4  366.62
  5201.2  367.68  5211.3  368.49  5231.4  369.24  5301.7  375.56  5343.7  378.38
#Mann=5,-1,0
  4787.0    0.05       0  4968.2    0.07       0  4972.2    0.05       0
  4993.2    0.16       0  5166.4    0.05       0
Bank Sta=4968.2,4972.2
Exp/Cntr=0.3,0.1

Type RM Length L Ch R = 1,1889,267,267,267
BEGIN DESCRIPTION:
North Twin Creek Trib F1889.06
END DESCRIPTION:
XS GIS Cut Line= 3
      2726497.15      6822255.17      2726191.56      6822278.34
      2725990.85      6822299.62
#Sta/Elev= 30
  4694.8  376.19  4703.3  375.75  4708.4  375.93  4716.0  375.12  4736.1  374.36
  4786.2  371.15  4816.3  368.58  4860.1  365.44  4866.4  364.87  4936.6  361.39
  4946.7  360.67  4956.7  359.39  4971.0  359.02  5001.3  359.18  5004.9  358.74
  5005.1  358.24  5008.6  358.24  5008.9  358.74  5027.0  359.34  5037.0  360.91
  5051.0  363.54  5057.1  364.56  5067.2  365.75  5073.1  366.85  5087.3  367.72
  5097.4  368.00  5147.6  371.47  5157.7  371.89  5197.9  374.49  5203.1  375.13
#Mann=5,-1,0
  4694.8    0.05       0  4860.1    0.16       0  5004.9    0.07       0
  5008.9    0.16       0  5051.0    0.05       0
Bank Sta=5004.9,5008.9
Exp/Cntr=0.3,0.1

Type RM Length L Ch R = 1,1622,219,219,219
BEGIN DESCRIPTION:
North Twin Creek Trib F1621.61
END DESCRIPTION:
XS GIS Cut Line= 3
      2726500.56      6822027.96      2726173.14      6822044.12
      2725922.43      6822079.40
#Sta/Elev= 30
  4674.8  373.12  4769.5  371.64  4779.5  370.99  4799.5  369.09  4836.2  366.11
  4841.2  366.30  4869.6  363.88  4883.9  362.02  4909.7  359.81  4919.7  359.31
  4939.7  357.70  4959.7  357.91  4977.7  357.64  4978.0  357.14  4981.5  357.14
  4981.7  357.64  5009.8  357.92  5040.1  358.58  5057.8  359.76  5070.4  360.38
  5080.5  360.42  5086.7  361.38  5110.8  363.17  5120.9  364.73  5151.2  367.54
  5158.0  368.38  5181.5  370.22  5229.2  372.22  5234.2  372.96  5255.8  373.71
#Mann=5,-1,0
  4674.8    0.05       0  4883.9    0.16       0  4977.7    0.07       0
  4981.7    0.16       0  5057.8    0.05       0
Bank Sta=4977.7,4981.7
Exp/Cntr=0.3,0.1

Type RM Length L Ch R = 1,1403,204,204,204
BEGIN DESCRIPTION:
North Twin Creek Trib F1403.22
END DESCRIPTION:
XS GIS Cut Line= 3
      2726428.24      6821822.79      2726176.41      6821825.56
      2725872.40      6821861.76
#Sta/Elev= 30
  4747.8  367.36  4800.0  366.43  4820.0  365.33  4850.0  364.43  4880.0  362.77
  4890.0  361.43  4922.1  359.89  4930.0  359.68  4940.1  358.73  4960.1  357.65
  4970.1  356.50  5004.2  355.65  5018.2  354.06  5018.4  353.56  5021.9  353.56
  5022.2  354.06  5030.3  355.58  5050.4  356.94  5060.5  358.40  5066.6  358.56
  5086.8  358.79  5100.8  359.56  5131.0  358.82  5151.1  358.84  5174.4  360.40
  5181.3  361.52  5211.5  364.05  5292.1  368.31  5301.5  369.09  5305.8  369.09
#Mann=5,-1,0
  4747.8    0.05       0  4922.1    0.16       0  5018.2    0.07       0
  5022.2    0.16       0  5066.6    0.12       0
Bank Sta=5018.2,5022.2
Exp/Cntr=0.3,0.1

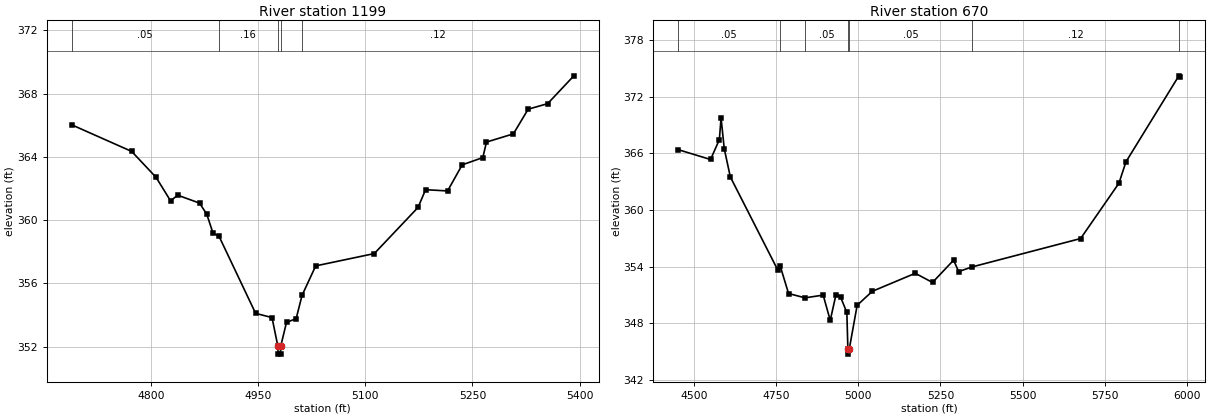
Type RM Length L Ch R = 1,1199,529,529,529
BEGIN DESCRIPTION:
North Twin Creek Trib F1198.57
END DESCRIPTION:
XS GIS Cut Line= 3
      2726432.34      6821690.63      2726122.67      6821636.63
      2725743.63      6821723.88
#Sta/Elev= 30
  4688.7  366.03  4772.6  364.35  4806.8  362.71  4827.0  361.23  4837.2  361.58
  4867.7  361.08  4877.9  360.37  4886.6  359.17  4894.7  359.01  4946.2  354.11
  4969.2  353.84  4977.4  352.03  4977.6  351.53  4981.1  351.53  4981.4  352.03
  4989.5  353.54  5003.0  353.77  5011.3  355.25  5030.4  357.11  5112.5  357.89
  5173.8  360.81  5184.3  361.93  5215.1  361.85  5235.6  363.50  5264.5  363.96
  5269.6  364.94  5307.3  365.46  5328.0  367.02  5355.3  367.37  5392.0  369.13
#Mann=5,-1,0
  4688.7    0.05       0  4894.7    0.16       0  4977.4    0.07       0
  4981.4    0.16       0  5011.3    0.12       0
Bank Sta=4977.4,4981.4
Exp/Cntr=0.3,0.1

Type RM Length L Ch R = 1,670,0,0,0
BEGIN DESCRIPTION:
North Twin Creek Trib F670.031
END DESCRIPTION:
XS GIS Cut Line= 3
      2726486.39      6821735.55      2726332.10      6821208.58
      2725490.08      6821711.74
#Sta/Elev= 30
  4450.9  366.40  4549.4  365.36  4576.2  367.46  4581.4  369.76  4591.1  366.51
  4609.6  363.52  4753.7  353.69  4761.6  354.08  4787.1  351.17  4837.2  350.71
  4892.6  351.00  4914.1  348.32  4931.2  350.99  4945.4  350.81  4964.7  349.16
  4967.9  345.25  4968.1  344.75  4971.9  345.25  4996.1  349.92  5042.1  351.40
  5173.2  353.31  5225.8  352.34  5290.0  354.70  5305.5  353.49  5345.8  353.98
  5677.1  356.99  5793.9  362.85  5815.2  365.11  5976.5  374.22  5980.9  374.05
#Mann=7,-1,0
  4450.9    0.05       0  4761.6    0.16       0  4837.2    0.05       0
  4967.9    0.05       0  4971.9    0.05       0  5345.8    0.12       0
  5976.5    0.05       0
Bank Sta=4967.9,4971.9
Exp/Cntr=0.3,0.1

Chan Stop Cuts=-1