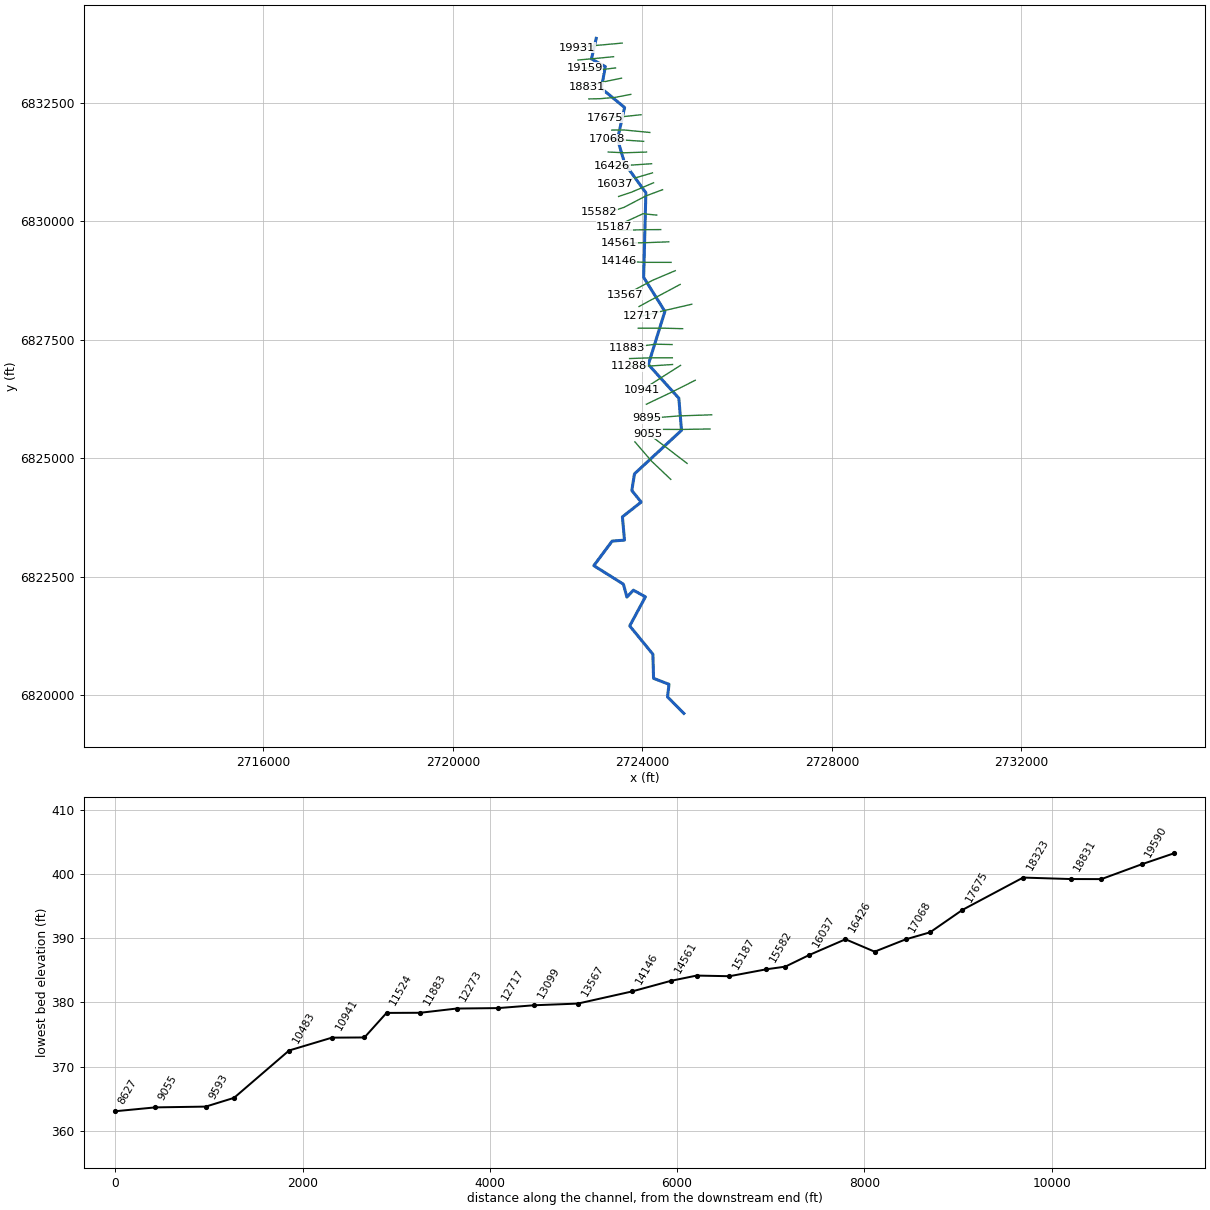
--- North Twin Creek Trib G.prj (project) ---

Proj Title=North Twin Creek Trib G Base Level Engineering
Current Plan=p01
Default Exp/Contr=0.3,0.1
English Units
Geom File=g01
Flow File=f01
Plan File=p01
BEGIN DESCRIPTION:
North Twin Creek Trib G
END DESCRIPTION:

--- North Twin Creek Trib G.p01 (plan) ---

Plan Title=Multiple Run
Short Identifier=Multiple
Geom File=g01
Flow File=f01
Subcritical Flow
K Sum by GR= 0
Std Step Tol= 0.01
Critical Tol= 0.01
Num of Std Step Trials= 20
Max Error Tol= 0.3
Flow Tol Ratio= 0.001
Split Flow NTrial= 30
Split Flow Tol= 0.02
Split Flow Ratio= 0.02
Log Output Level= 0
Friction Slope Method= 1
Unsteady Friction Slope Method= 2
Unsteady Bridges Friction Slope Method= 1
Parabolic Critical Depth
Global Vel Dist=  1 , 1 , 1
Global Log Level= 0
CheckData=True
Encroach Param= -1, 0, 0, 0
BEGIN DESCRIPTION:
Multiple Run
END DESCRIPTION:

--- North Twin Creek Trib G.f01 (steady flow) ---

Flow Title=Multiple
Number of Profiles=7
Profile Names=10-year,25-year,50-year,1pct_min,100-year,1pct_plu,500-year
River Rch & RM= North Twin Creek,Reach-1,19931
     635     850    1022     610    1217    2427    1722
River Rch & RM= North Twin Creek,Reach-1,16737
    1035    1422    1742    1056    2107    4203    3082
River Rch & RM= North Twin Creek,Reach-1,11883
    1132    1556    1905    1154    2302    4593    3363
River Rch & RM= North Twin Creek,Reach-1,5332
    1346    1862    2290    1392    2777    5540    4085
Boundary for River Rch & Prof#=North Twin Creek,Reach-1,1
Up Type=0
Dn Type=3
Dn Slope=0.005
Boundary for River Rch & Prof#=North Twin Creek,Reach-1,2
Up Type=0
Dn Type=3
Dn Slope=0.005
Boundary for River Rch & Prof#=North Twin Creek,Reach-1,3
Up Type=0
Dn Type=3
Dn Slope=0.005
Boundary for River Rch & Prof#=North Twin Creek,Reach-1,4
Up Type=0
Dn Type=3
Dn Slope=0.005
Boundary for River Rch & Prof#=North Twin Creek,Reach-1,5
Up Type=0
Dn Type=3
Dn Slope=0.005
Boundary for River Rch & Prof#=North Twin Creek,Reach-1,6
Up Type=0
Dn Type=3
Dn Slope=0.005
Boundary for River Rch & Prof#=North Twin Creek,Reach-1,7
Up Type=0
Dn Type=3
Dn Slope=0.005

--- North Twin Creek Trib G.g01 (geometry) ---

Geom Title=Existing Conditions

River Reach=North Twin Creek,Reach-1
Reach XY= 30
      2723026.00      6833861.00      2722926.13      6833426.22
      2723218.12      6833264.62      2723135.18      6832804.05
      2723625.37      6832401.38      2723475.44      6831733.80
      2723627.79      6831217.08      2724074.65      6830601.34
      2724027.65      6828816.42      2724475.84      6828096.90
      2724126.74      6826975.74      2724770.64      6826263.70
      2724826.50      6825585.96      2723833.81      6824667.19
      2723777.99      6824316.27      2723974.97      6824071.43
      2723579.53      6823759.53      2723622.94      6823268.62
      2723362.27      6823247.79      2722975.79      6822729.77
      2723600.09      6822338.15      2723674.08      6822065.90
      2723810.86      6822211.81      2724065.02      6822071.37
      2723733.43      6821457.59      2724222.57      6820859.77
      2724236.83      6820350.68      2724562.84      6820224.73
      2724531.40      6819958.54      2724876.00      6819611.00

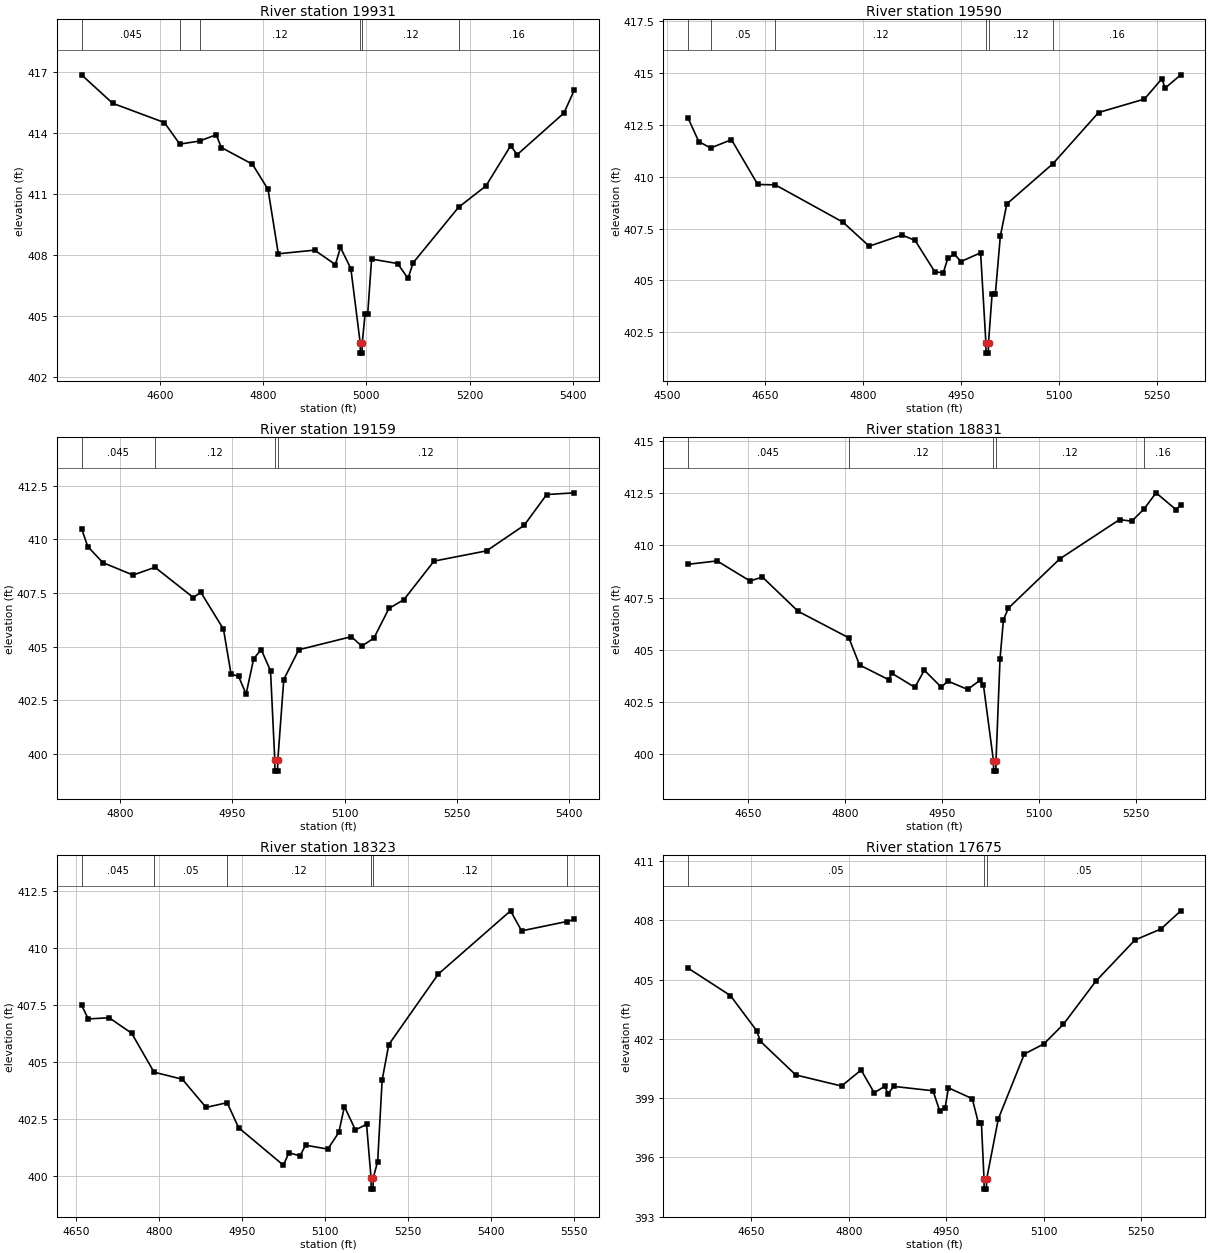
Type RM Length L Ch R = 1,19931,341,341,341
BEGIN DESCRIPTION:
North Twin Creek Trib G19930.681
END DESCRIPTION:
XS GIS Cut Line= 3
      2723575.97      6833761.00      2723026.00      6833711.00
      2722626.05      6833661.01
#Sta/Elev= 30
  4447.8  416.88  4508.0  415.48  4608.4  414.53  4638.2  413.47  4676.5  413.62
  4708.8  413.93  4718.9  413.30  4779.1  412.48  4809.3  411.24  4829.3  408.07
  4899.6  408.25  4939.8  407.54  4949.8  408.38  4969.9  407.34  4988.0  403.68
  4988.2  403.18  4991.7  403.18  4992.0  403.68  4997.5  405.12  5002.6  405.12
  5010.1  407.81  5060.5  407.59  5080.7  406.86  5090.7  407.63  5178.7  410.36
  5231.8  411.41  5279.7  413.39  5292.3  412.95  5383.0  415.00  5403.1  416.13
#Mann=6,-1,0
  4447.8   0.045       0  4638.2    0.05       0  4676.5    0.12       0
  4988.0    0.07       0  4992.0    0.12       0  5178.7    0.16       0
Bank Sta=4988,4992
Exp/Cntr=0.3,0.1

Type RM Length L Ch R = 1,19590,431,431,431
BEGIN DESCRIPTION:
North Twin Creek Trib G19590.09
END DESCRIPTION:
XS GIS Cut Line= 3
      2723392.29      6833473.06      2722926.04      6833428.44
      2722640.50      6833403.64
#Sta/Elev= 30
  4531.5  412.84  4547.9  411.70  4566.1  411.39  4598.1  411.79  4638.3  409.63
  4665.3  409.61  4768.9  407.81  4809.1  406.65  4859.3  407.19  4879.4  406.93
  4909.5  405.42  4922.5  405.36  4929.6  406.07  4939.7  406.26  4949.7  405.91
  4979.8  406.33  4987.9  401.99  4988.1  401.49  4991.6  401.49  4991.9  401.99
  4997.4  404.34  5002.4  404.34  5010.0  407.13  5020.0  408.69  5090.9  410.64
  5160.5  413.10  5230.8  413.75  5257.5  414.73  5262.5  414.28  5286.5  414.92
#Mann=6,-1,0
  4531.5   0.045       0  4566.1    0.05       0  4665.3    0.12       0
  4987.9    0.07       0  4991.9    0.12       0  5090.9    0.16       0
Bank Sta=4987.9,4991.9
Exp/Cntr=0.3,0.1

Type RM Length L Ch R = 1,19159,328,328,328
BEGIN DESCRIPTION:
North Twin Creek Trib G19159.43
END DESCRIPTION:
XS GIS Cut Line= 3
      2723434.23      6833236.09      2723183.68      6833206.88
      2722779.19      6833237.55
#Sta/Elev= 30
  4748.7  410.51  4757.0  409.67  4777.1  408.92  4817.4  408.34  4846.8  408.70
  4897.9  407.29  4908.0  407.53  4938.2  405.81  4948.3  403.71  4958.3  403.61
  4968.4  402.78  4978.5  404.43  4988.5  404.86  5001.0  403.87  5006.7  399.68
  5006.9  399.18  5010.4  399.18  5010.7  399.68  5018.7  403.46  5038.7  404.85
  5108.9  405.46  5122.8  405.02  5139.0  405.39  5159.1  406.78  5179.1  407.19
  5219.3  408.99  5289.5  409.47  5339.6  410.66  5369.7  412.10  5406.6  412.18
#Mann=4,-1,0
  4748.7   0.045       0  4846.8    0.12       0  5006.7    0.07       0
  5010.7    0.12       0
Bank Sta=5006.7,5010.7
Exp/Cntr=0.3,0.1

Type RM Length L Ch R = 1,18831,508,508,508
BEGIN DESCRIPTION:
North Twin Creek Trib G18831.21
END DESCRIPTION:
XS GIS Cut Line= 3
      2723560.10      6833020.18      2723125.01      6832929.94
      2722824.39      6832823.36
#Sta/Elev= 30
  4556.5  409.09  4601.5  409.25  4652.6  408.29  4671.7  408.48  4727.0  406.84
  4805.6  405.57  4822.2  404.27  4867.1  403.57  4872.4  403.87  4907.9  403.20
  4922.5  404.02  4948.8  403.21  4959.0  403.50  4989.6  403.10  5008.9  403.54
  5014.2  403.29  5029.6  399.69  5029.9  399.19  5033.4  399.19  5033.6  399.69
  5039.8  404.56  5045.1  406.44  5052.8  406.99  5132.4  409.35  5225.0  411.23
  5243.8  411.15  5263.0  411.74  5281.5  412.51  5312.3  411.71  5319.8  411.92
#Mann=5,-1,0
  4556.5   0.045       0  4805.6    0.12       0  5029.6    0.07       0
  5033.6    0.12       0  5263.0    0.16       0
Bank Sta=5029.6,5033.6
Exp/Cntr=0.3,0.1

Type RM Length L Ch R = 1,18323,648,648,648
BEGIN DESCRIPTION:
North Twin Creek Trib G18322.58
END DESCRIPTION:
XS GIS Cut Line= 4
      2723755.09      6832677.86      2723420.46      6832613.79
      2723112.50      6832587.13      2722870.59      6832581.50
#Sta/Elev= 30
  4659.4  407.51  4671.5  406.90  4709.4  406.95  4750.1  406.27  4790.6  404.56
  4841.7  404.25  4884.8  403.01  4922.9  403.22  4943.6  402.12  5024.7  400.47
  5034.7  401.02  5054.8  400.88  5064.8  401.35  5105.0  401.18  5125.0  401.91
  5135.1  403.05  5155.1  402.02  5175.2  402.27  5183.3  399.92  5183.5  399.42
  5187.0  399.42  5187.3  399.92  5195.3  400.63  5203.4  404.21  5215.4  405.77
  5305.0  408.87  5435.8  411.65  5455.8  410.77  5537.6  411.18  5551.2  411.27
#Mann=6,-1,0
  4659.4   0.045       0  4790.6    0.05       0  4922.9    0.12       0
  5183.3    0.07       0  5187.3    0.12       0  5537.6    0.16       0
Bank Sta=5183.3,5187.3
Exp/Cntr=0.3,0.1

Type RM Length L Ch R = 1,17675,346,346,346
BEGIN DESCRIPTION:
North Twin Creek Trib G17674.84
END DESCRIPTION:
XS GIS Cut Line= 3
      2723970.87      6832247.79      2723521.92      6832200.52
      2723215.47      6832189.06
#Sta/Elev= 30
  4552.7  405.58  4617.9  404.19  4658.1  402.42  4664.2  401.87  4718.5  400.17
  4788.9  399.61  4819.0  400.42  4839.1  399.27  4855.3  399.59  4860.3  399.22
  4869.3  399.59  4929.6  399.37  4939.7  398.37  4948.3  398.51  4953.3  399.52
  4990.0  398.97  4999.6  397.72  5004.1  397.72  5008.1  394.89  5008.3  394.39
  5011.8  394.39  5012.1  394.89  5030.1  397.95  5070.1  401.23  5100.1  401.74
  5130.1  402.73  5180.2  404.92  5240.2  407.00  5280.2  407.56  5310.8  408.48
#Mann=3,-1,0
  4552.7    0.05       0  5008.1    0.05       0  5012.1    0.05       0
Bank Sta=5008.1,5012.1
Exp/Cntr=0.3,0.1

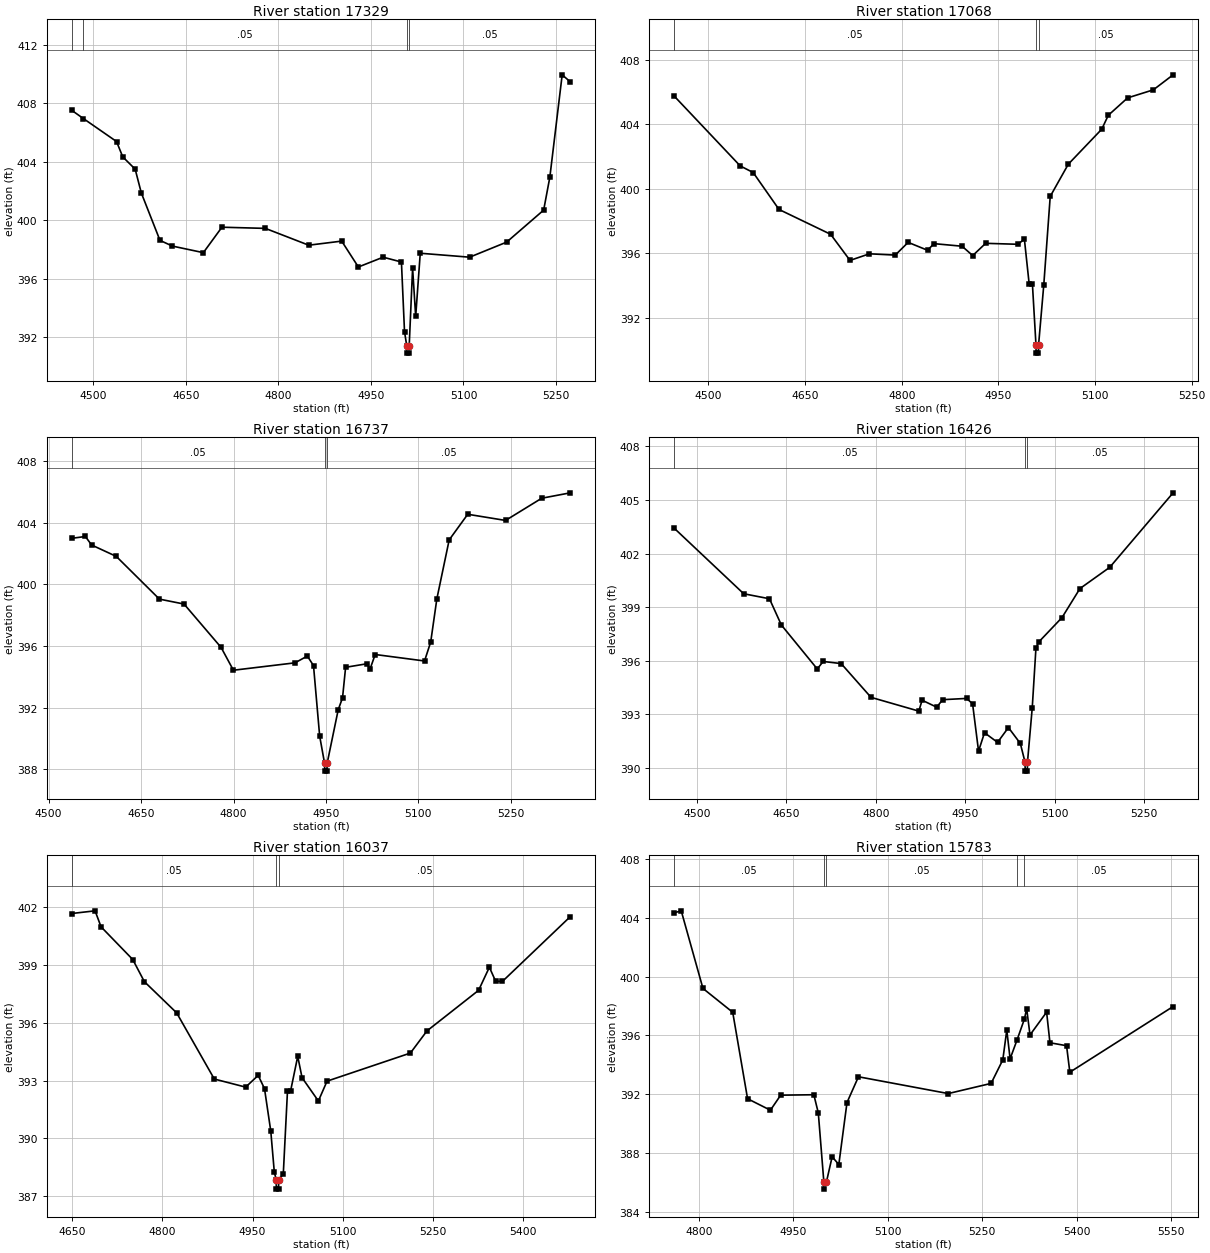
Type RM Length L Ch R = 1,17329,261,261,261
BEGIN DESCRIPTION:
North Twin Creek Trib G17329.1
END DESCRIPTION:
XS GIS Cut Line= 3
      2724158.49      6831873.70      2723620.96      6831926.11
      2723352.85      6831924.19
#Sta/Elev= 30
  4465.0  407.51  4484.1  406.94  4537.8  405.37  4547.9  404.32  4568.0  403.48
  4578.0  401.85  4608.2  398.61  4628.3  398.22  4678.5  397.77  4708.6  399.51
  4779.0  399.43  4849.3  398.28  4902.7  398.56  4929.7  396.79  4969.9  397.46
  4999.5  397.13  5004.5  392.37  5008.1  391.40  5008.3  390.90  5011.8  390.90
  5012.1  391.40  5017.6  396.71  5022.6  393.41  5030.0  397.73  5110.0  397.46
  5170.0  398.49  5230.0  400.68  5240.0  402.93  5260.0  409.93  5273.2  409.45
#Mann=4,-1,0
  4465.0   0.045       0  4484.1    0.05       0  5008.1    0.05       0
  5012.1    0.05       0
Bank Sta=5008.1,5012.1
Exp/Cntr=0.3,0.1

Type RM Length L Ch R = 1,17068,331,331,331
BEGIN DESCRIPTION:
North Twin Creek Trib G17068.2
END DESCRIPTION:
XS GIS Cut Line= 3
      2724028.00      6831686.29      2723476.10      6831723.22
      2723255.46      6831733.23
#Sta/Elev= 30
  4447.1  405.73  4549.3  401.41  4569.4  401.00  4609.5  398.71  4689.6  397.17
  4719.7  395.55  4749.8  395.96  4789.9  395.88  4809.9  396.67  4840.0  396.18
  4850.0  396.59  4893.6  396.43  4910.1  395.85  4930.2  396.61  4980.3  396.55
  4990.3  396.87  4997.8  394.06  5002.8  394.06  5008.3  390.30  5008.6  389.80
  5012.1  389.80  5012.3  390.30  5020.4  394.03  5030.4  399.52  5058.5  401.52
  5110.4  403.69  5120.5  404.55  5150.5  405.63  5190.5  406.13  5221.1  407.06
#Mann=3,-1,0
  4447.1    0.05       0  5008.3    0.05       0  5012.3    0.05       0
Bank Sta=5008.3,5012.3
Exp/Cntr=0.3,0.1

Type RM Length L Ch R = 1,16737,311,311,311
BEGIN DESCRIPTION:
North Twin Creek Trib G16737.38
END DESCRIPTION:
XS GIS Cut Line= 3
      2724088.42      6831460.40      2723624.00      6831445.25
      2723279.63      6831460.95
#Sta/Elev= 30
  4537.2  402.98  4559.6  403.10  4569.6  402.55  4609.7  401.81  4679.7  399.04
  4719.7  398.72  4779.8  395.91  4799.8  394.43  4899.8  394.91  4919.8  395.35
  4929.8  394.73  4939.8  390.16  4947.8  388.39  4948.0  387.89  4951.6  387.89
  4951.9  388.39  4969.9  391.87  4976.9  392.64  4981.9  394.62  5016.6  394.85
  5021.6  394.51  5029.9  395.45  5110.0  395.03  5120.0  396.26  5130.0  399.06
  5150.0  402.88  5180.1  404.54  5241.5  404.14  5300.2  405.58  5346.6  405.93
#Mann=3,-1,0
  4537.2    0.05       0  4947.8    0.05       0  4951.9    0.05       0
Bank Sta=4947.8,4951.9
Exp/Cntr=0.3,0.1

Type RM Length L Ch R = 1,16426,389,389,389
BEGIN DESCRIPTION:
North Twin Creek Trib G16426.01
END DESCRIPTION:
XS GIS Cut Line= 3
      2724195.13      6831213.94      2723654.12      6831177.53
      2723359.73      6831170.67
#Sta/Elev= 30
  4461.9  403.41  4578.2  399.75  4621.4  399.47  4641.4  398.00  4701.6  395.54
  4711.6  395.96  4741.7  395.84  4791.8  393.95  4872.0  393.18  4877.5  393.79
  4902.0  393.40  4912.0  393.82  4952.1  393.89  4962.2  393.59  4972.2  390.94
  4982.2  391.97  5004.1  391.43  5022.3  392.26  5042.3  391.37  5050.2  390.32
  5050.5  389.82  5054.1  389.82  5054.3  390.32  5062.3  393.37  5068.5  396.71
  5073.5  397.06  5112.3  398.42  5142.3  400.04  5192.3  401.23  5298.6  405.40
#Mann=3,-1,0
  4461.9    0.05       0  5050.2    0.05       0  5054.3    0.05       0
Bank Sta=5050.2,5054.3
Exp/Cntr=0.3,0.1

Type RM Length L Ch R = 1,16037,254,254,254
BEGIN DESCRIPTION:
North Twin Creek Trib G16037.01
END DESCRIPTION:
XS GIS Cut Line= 3
      2724213.47      6831021.10      2723867.57      6830919.52
      2723416.42      6830794.72
#Sta/Elev= 30
  4649.4  401.68  4688.4  401.82  4698.3  400.99  4751.0  399.29  4770.3  398.14
  4823.9  396.52  4886.5  393.08  4938.6  392.66  4959.4  393.27  4969.9  392.58
  4980.3  390.38  4986.2  388.24  4989.3  387.86  4989.6  387.36  4993.2  387.36
  4993.5  387.86  5001.1  388.14  5008.1  392.47  5013.3  392.47  5025.1  394.26
  5032.3  393.15  5059.4  391.94  5073.8  392.97  5212.3  394.43  5239.8  395.58
  5325.6  397.69  5343.5  398.89  5353.9  398.16  5365.1  398.15  5478.0  401.52
#Mann=3,-1,0
  4649.4    0.05       0  4989.3    0.05       0  4993.5    0.05       0
Bank Sta=4989.3,4993.5
Exp/Cntr=0.3,0.1

Type RM Length L Ch R = 1,15783,201,201,201
BEGIN DESCRIPTION:
North Twin Creek Trib G15782.75
END DESCRIPTION:
XS GIS Cut Line= 4
      2724236.37      6830812.29      2724010.87      6830716.13
      2723763.51      6830610.79      2723499.23      6830522.95
#Sta/Elev= 30
  4760.9  404.33  4771.8  404.46  4806.3  399.19  4853.6  397.57  4877.2  391.70
  4913.5  390.92  4929.8  391.94  4982.5  391.97  4989.6  390.74  4998.4  386.06
  4998.6  385.56  5002.6  386.06  5011.6  387.76  5022.2  387.23  5035.2  391.44
  5053.4  393.19  5196.1  392.05  5264.2  392.74  5282.8  394.34  5289.1  396.36
  5294.4  394.41  5305.5  395.70  5317.2  397.12  5320.7  397.82  5326.0  396.03
  5352.4  397.58  5357.7  395.50  5384.1  395.30  5389.3  393.50  5553.4  397.96
#Mann=5,-1,0
  4760.9    0.05       0  4998.4    0.05       0  5002.6    0.05       0
  5305.5   0.063       0  5317.2    0.05       0
Bank Sta=4998.4,5002.6
Exp/Cntr=0.3,0.1

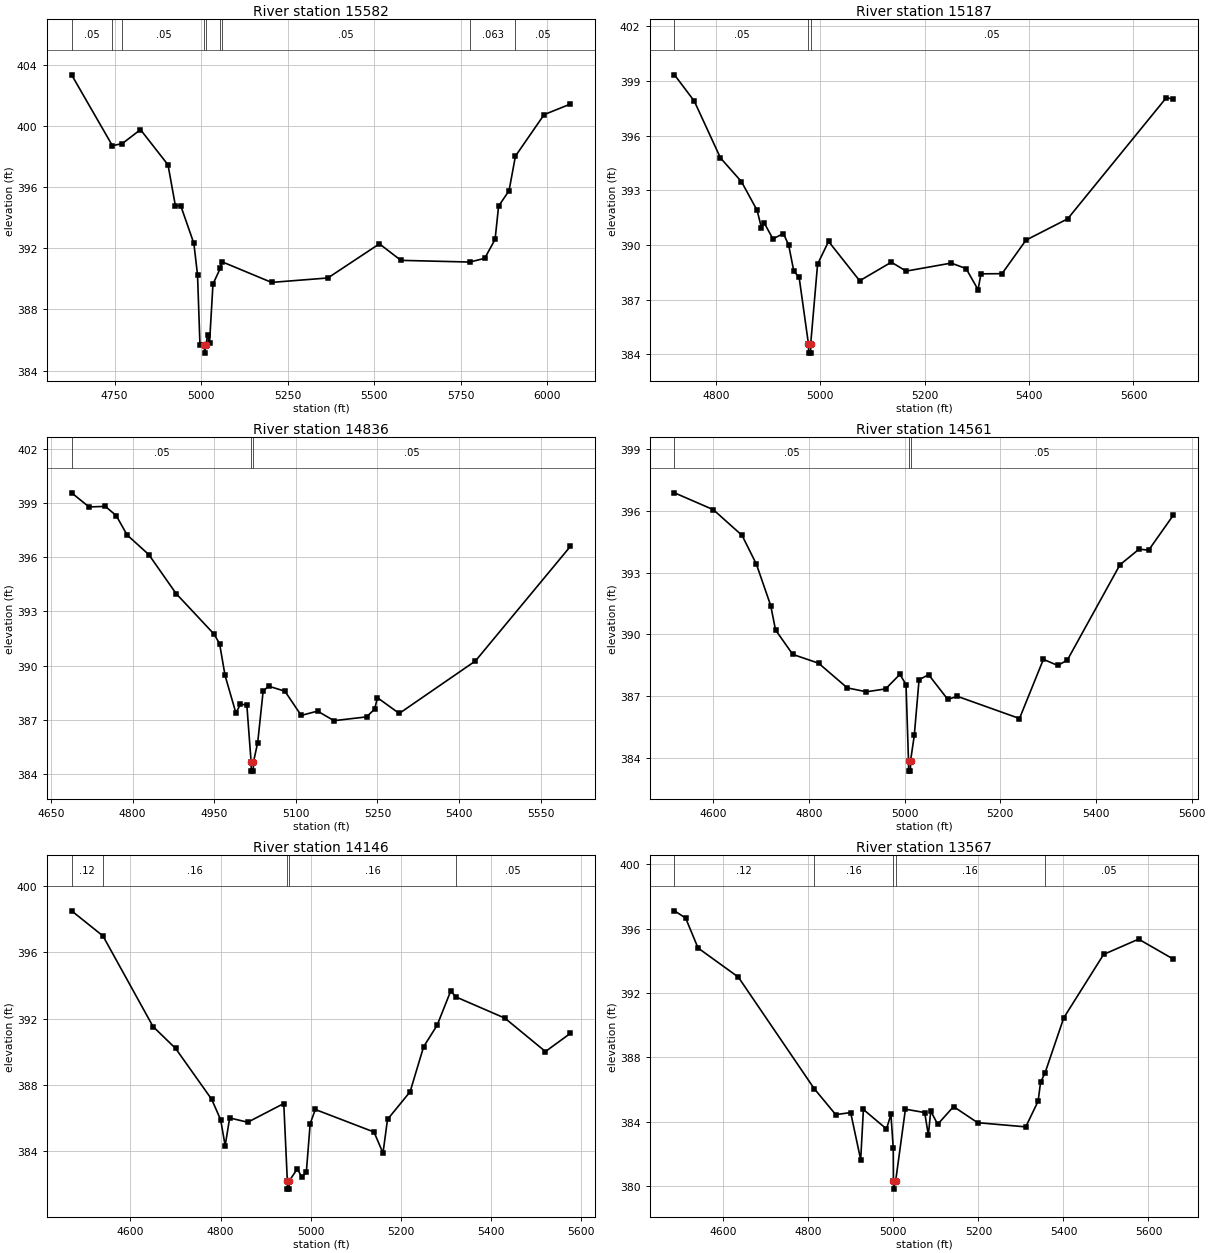
Type RM Length L Ch R = 1,15582,395,395,395
BEGIN DESCRIPTION:
North Twin Creek Trib G15581.69
END DESCRIPTION:
XS GIS Cut Line= 5
      2724427.21      6830665.23      2724077.53      6830535.85
      2723609.31      6830291.15      2723448.86      6830239.79
      2723079.89      6830196.67
#Sta/Elev= 30
  4625.9  403.33  4743.8  398.70  4772.4  398.84  4824.9  399.75  4904.4  397.45
  4925.7  394.78  4941.2  394.78  4979.1  392.32  4989.7  390.26  4996.7  385.71
  5009.6  385.65  5009.9  385.15  5013.9  385.65  5018.7  386.36  5024.3  385.78
  5034.3  389.66  5055.2  390.68  5060.2  391.12  5203.6  389.77  5366.3  390.06
  5515.2  392.29  5577.3  391.21  5776.1  391.10  5819.3  391.34  5849.4  392.58
  5859.5  394.75  5889.7  395.76  5908.2  398.02  5991.0  400.73  6067.0  401.42
#Mann=9,-1,0
  4625.9    0.05       0  4743.8   0.063       0  4772.4    0.05       0
  5009.6    0.05       0  5013.9    0.05       0  5055.2    0.16       0
  5060.2    0.05       0  5776.1   0.063       0  5908.2    0.05       0
Bank Sta=5009.6,5013.9
Exp/Cntr=0.3,0.1

Type RM Length L Ch R = 1,15187,351,351,351
BEGIN DESCRIPTION:
North Twin Creek Trib G15186.74
END DESCRIPTION:
XS GIS Cut Line= 3
      2724303.71      6830129.83      2724012.86      6830157.68
      2723410.28      6829879.90
#Sta/Elev= 30
  4720.6  399.34  4758.5  397.90  4808.7  394.78  4848.9  393.48  4879.0  391.90
  4887.1  390.96  4892.2  391.23  4909.2  390.34  4929.3  390.63  4939.3  390.01
  4949.3  388.56  4959.4  388.24  4977.3  384.57  4977.6  384.07  4981.3  384.07
  4981.6  384.57  4994.8  388.95  5015.8  390.20  5075.4  388.04  5136.1  389.06
  5164.5  388.57  5250.9  389.01  5279.3  388.71  5302.3  387.55  5307.8  388.42
  5348.2  388.43  5394.1  390.27  5474.0  391.44  5663.1  398.09  5676.3  398.00
#Mann=3,-1,0
  4720.6    0.05       0  4977.3    0.05       0  4981.6    0.05       0
Bank Sta=4977.3,4981.6
Exp/Cntr=0.3,0.1

Type RM Length L Ch R = 1,14836,275,275,275
BEGIN DESCRIPTION:
North Twin Creek Trib G14835.82
END DESCRIPTION:
XS GIS Cut Line= 3
      2724388.00      6829823.78      2724075.08      6829821.68
      2723471.47      6829807.62
#Sta/Elev= 30
  4688.0  399.56  4720.0  398.78  4750.0  398.81  4770.0  398.30  4790.0  397.23
  4830.0  396.14  4880.0  393.99  4950.0  391.74  4960.0  391.21  4970.0  389.46
  4990.0  387.38  4998.0  387.86  5010.0  387.84  5017.9  384.67  5018.2  384.17
  5021.9  384.17  5022.2  384.67  5030.0  385.75  5040.0  388.59  5050.0  388.87
  5080.0  388.59  5110.0  387.25  5140.0  387.49  5170.1  386.96  5230.1  387.17
  5244.9  387.60  5250.1  388.23  5290.1  387.36  5430.1  390.26  5604.7  396.60
#Mann=3,-1,0
  4688.0    0.05       0  5017.9    0.05       0  5022.2    0.05       0
Bank Sta=5017.9,5022.2
Exp/Cntr=0.3,0.1

Type RM Length L Ch R = 1,14561,415,415,415
BEGIN DESCRIPTION:
North Twin Creek Trib G14561.35
END DESCRIPTION:
XS GIS Cut Line= 3
      2724557.16      6829565.36      2724075.60      6829547.20
      2723514.48      6829537.60
#Sta/Elev= 30
  4518.5  396.89  4599.7  396.07  4659.8  394.82  4689.8  393.42  4719.8  391.40
  4729.8  390.22  4765.8  389.03  4819.9  388.60  4879.9  387.40  4919.9  387.21
  4960.0  387.35  4990.0  388.06  5002.7  387.56  5007.9  383.85  5008.2  383.35
  5011.9  383.35  5012.2  383.85  5020.0  385.09  5030.0  387.80  5050.0  388.04
  5090.0  386.84  5110.0  386.99  5240.0  385.91  5290.0  388.79  5320.0  388.49
  5340.0  388.75  5450.1  393.39  5490.1  394.15  5510.1  394.10  5561.6  395.80
#Mann=3,-1,0
  4518.5    0.05       0  5007.9    0.05       0  5012.2    0.05       0
Bank Sta=5007.9,5012.2
Exp/Cntr=0.3,0.1

Type RM Length L Ch R = 1,14146,579,579,579
BEGIN DESCRIPTION:
North Twin Creek Trib G14146.39
END DESCRIPTION:
XS GIS Cut Line= 3
      2724606.61      6829131.70      2724073.88      6829132.27
      2723500.60      6829153.53
#Sta/Elev= 30
  4469.5  398.51  4539.1  396.99  4650.1  391.52  4700.1  390.20  4780.1  387.13
  4800.1  385.89  4810.1  384.32  4820.1  386.00  4860.1  385.74  4940.1  386.87
  4948.0  382.20  4948.3  381.70  4952.0  381.70  4952.3  382.20  4970.1  382.92
  4980.1  382.43  4990.1  382.71  4998.7  385.66  5010.1  386.51  5140.2  385.15
  5160.2  383.88  5170.2  385.91  5220.3  387.58  5250.3  390.30  5280.3  391.60
  5310.3  393.66  5321.9  393.31  5430.4  392.03  5520.5  390.01  5575.9  391.11
#Mann=5,-1,0
  4469.5    0.12       0  4539.1    0.16       0  4948.0    0.07       0
  4952.3    0.16       0  5321.9    0.05       0
Bank Sta=4948,4952.3
Exp/Cntr=0.3,0.1

Type RM Length L Ch R = 1,13567,468,468,468
BEGIN DESCRIPTION:
North Twin Creek Trib G13567.32
END DESCRIPTION:
XS GIS Cut Line= 3
      2724695.20      6828956.26      2724218.62      6828754.65
      2723639.49      6828447.54
#Sta/Elev= 30
  4485.3  397.11  4511.6  396.66  4540.7  394.80  4635.5  392.99  4813.8  386.06
  4864.5  384.44  4899.6  384.57  4923.2  381.64  4929.6  384.76  4983.9  383.55
  4994.3  384.45  4999.8  382.36  5000.2  380.31  5000.6  379.81  5005.4  380.31
  5028.4  384.78  5073.7  384.57  5082.3  383.17  5088.0  384.66  5104.3  383.84
  5141.6  384.94  5198.2  383.94  5311.4  383.68  5340.5  385.28  5346.2  386.45
  5356.8  387.04  5400.8  390.46  5494.5  394.40  5576.8  395.35  5658.3  394.11
#Mann=5,-1,0
  4485.3    0.12       0  4813.8    0.16       0  5000.2    0.07       0
  5005.4    0.16       0  5356.8    0.05       0
Bank Sta=5000.2,5005.4
Exp/Cntr=0.3,0.1

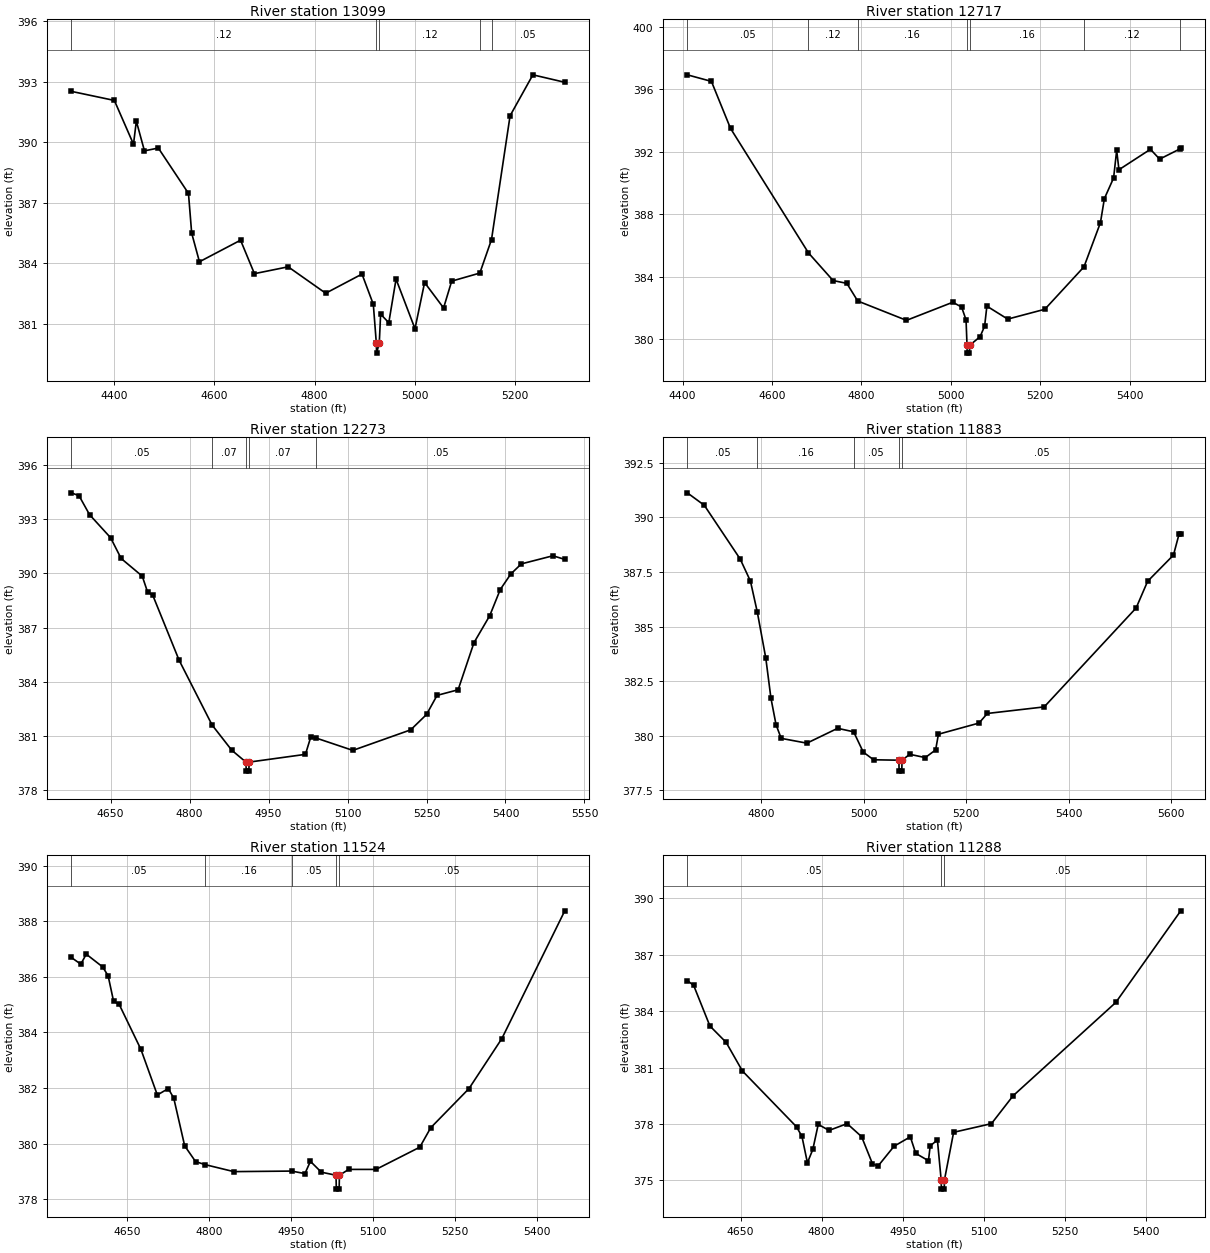
Type RM Length L Ch R = 1,13099,382,382,382
BEGIN DESCRIPTION:
North Twin Creek Trib G13098.61
END DESCRIPTION:
XS GIS Cut Line= 3
      2724797.94      6828665.80      2724192.65      6828342.57
      2723930.12      6828199.23
#Sta/Elev= 30
  4314.3  392.53  4400.2  392.08  4438.4  389.91  4444.1  391.05  4460.3  389.58
  4488.0  389.72  4548.2  387.47  4554.6  385.50  4570.1  384.08  4652.2  385.15
  4679.9  383.49  4747.3  383.83  4822.2  382.52  4894.7  383.47  4917.3  381.97
  4923.3  380.05  4923.8  379.55  4929.2  380.05  4931.9  381.48  4948.2  381.06
  4962.7  383.22  5000.5  380.76  5019.7  383.05  5057.6  381.79  5073.8  383.12
  5130.0  383.52  5153.3  385.18  5190.4  391.32  5235.9  393.35  5299.6  392.98
#Mann=5,-1,0
  4314.3    0.12       0  4923.3    0.07       0  4929.2    0.12       0
  5130.0    0.16       0  5153.3    0.05       0
Bank Sta=4923.3,4929.2
Exp/Cntr=0.3,0.1

Type RM Length L Ch R = 1,12717,444,444,444
BEGIN DESCRIPTION:
North Twin Creek Trib G12717.24
END DESCRIPTION:
XS GIS Cut Line= 3
      2725043.60      6828248.13      2724469.10      6828115.23
      2723970.15      6827992.07
#Sta/Elev= 30
  4410.6  396.94  4464.5  396.52  4507.2  393.51  4681.6  385.53  4736.6  383.76
  4767.4  383.58  4791.7  382.45  4900.8  381.21  5004.4  382.37  5024.1  382.06
  5034.0  381.24  5036.2  379.61  5036.7  379.11  5041.6  379.11  5042.1  379.61
  5065.3  380.16  5075.5  380.83  5080.6  382.12  5127.2  381.29  5210.2  381.92
  5297.8  384.64  5334.6  387.47  5343.4  389.01  5364.0  390.33  5370.9  392.10
  5376.0  390.86  5446.4  392.17  5467.0  391.54  5511.5  392.18  5514.2  392.27
#Mann=7,-1,0
  4410.6    0.05       0  4681.6    0.12       0  4791.7    0.16       0
  5036.2    0.07       0  5042.1    0.16       0  5297.8    0.12       0
  5511.5    0.05       0
Bank Sta=5036.2,5042.1
Exp/Cntr=0.3,0.1

Type RM Length L Ch R = 1,12273,390,390,390
BEGIN DESCRIPTION:
North Twin Creek Trib G12273.23
END DESCRIPTION:
XS GIS Cut Line= 3
      2724850.61      6827731.88      2724424.87      6827742.73
      2723913.45      6827741.20
#Sta/Elev= 30
  4575.3  394.47  4589.9  394.31  4609.9  393.26  4649.9  391.98  4669.9  390.83
  4710.0  389.85  4720.0  388.98  4730.0  388.79  4780.0  385.19  4842.6  381.60
  4880.0  380.20  4907.0  379.54  4907.5  379.04  4912.5  379.04  4913.0  379.54
  5020.0  379.97  5030.0  380.92  5040.7  380.87  5110.0  380.19  5220.0  381.33
  5250.0  382.18  5270.0  383.24  5310.0  383.55  5340.1  386.16  5370.1  387.66
  5390.1  389.11  5410.1  389.97  5430.1  390.53  5490.1  390.98  5512.6  390.78
#Mann=5,-1,0
  4575.3    0.05       0  4842.6    0.07       0  4907.0    0.07       0
  4913.0    0.07       0  5040.7    0.05       0
Bank Sta=4907,4913
Exp/Cntr=0.3,0.1

Type RM Length L Ch R = 1,11883,359,359,359
BEGIN DESCRIPTION:
North Twin Creek Trib G11883.44
END DESCRIPTION:
XS GIS Cut Line= 3
      2724629.10      6827396.81      2724280.66      6827404.27
      2723671.90      6827325.15
#Sta/Elev= 30
  4656.3  391.12  4689.4  390.55  4759.4  388.09  4779.4  387.08  4792.9  385.65
  4809.4  383.55  4819.4  381.72  4829.4  380.50  4839.4  379.88  4889.5  379.66
  4949.5  380.34  4980.7  380.18  4999.5  379.25  5019.6  378.90  5068.9  378.88
  5069.4  378.38  5074.6  378.38  5075.1  378.88  5090.2  379.15  5120.4  379.00
  5140.6  379.35  5146.1  380.07  5225.2  380.58  5241.5  381.02  5352.4  381.32
  5531.7  385.85  5554.1  387.07  5604.5  388.27  5615.4  389.23  5618.7  389.23
#Mann=5,-1,0
  4656.3    0.05       0  4792.9    0.16       0  4980.7    0.05       0
  5068.9    0.05       0  5075.1    0.05       0
Bank Sta=5068.9,5075.1
Exp/Cntr=0.3,0.1

Type RM Length L Ch R = 1,11524,236,236,236
BEGIN DESCRIPTION:
North Twin Creek Trib G11524.43
END DESCRIPTION:
XS GIS Cut Line= 3
      2724633.27      6827117.01      2724181.32      6827116.86
      2723730.94      6827101.17
#Sta/Elev= 30
  4548.3  386.70  4565.6  386.46  4575.6  386.82  4605.6  386.36  4615.6  386.04
  4625.6  385.12  4635.6  385.02  4675.6  383.39  4705.6  381.75  4725.6  381.98
  4735.6  381.64  4755.6  379.92  4775.6  379.35  4793.4  379.24  4845.6  378.99
  4951.1  379.01  4975.6  378.92  4985.6  379.36  5005.6  378.97  5032.5  378.86
  5033.0  378.36  5038.2  378.36  5038.7  378.86  5055.6  379.07  5105.6  379.07
  5185.7  379.87  5205.7  380.57  5275.7  381.98  5335.8  383.78  5450.9  388.38
#Mann=5,-1,0
  4548.3    0.05       0  4793.4    0.16       0  4951.1    0.05       0
  5032.5    0.05       0  5038.7    0.05       0
Bank Sta=5032.5,5038.7
Exp/Cntr=0.3,0.1

Type RM Length L Ch R = 1,11288,347,347,347
BEGIN DESCRIPTION:
North Twin Creek Trib G11287.88
END DESCRIPTION:
XS GIS Cut Line= 3
      2724637.67      6826975.54      2724187.51      6826945.56
      2723725.80      6826940.00
#Sta/Elev= 30
  4551.5  385.62  4563.2  385.37  4593.3  383.21  4623.3  382.34  4653.4  380.82
  4753.6  377.85  4763.6  377.34  4773.7  375.94  4783.7  376.65  4793.7  377.98
  4813.7  377.66  4847.2  378.02  4873.9  377.33  4893.9  375.90  4903.9  375.75
  4934.0  376.82  4964.1  377.32  4974.1  376.44  4997.6  376.05  5000.9  376.84
  5014.2  377.15  5021.1  375.04  5021.6  374.54  5026.8  374.54  5027.3  375.04
  5044.2  377.56  5114.2  378.02  5154.2  379.50  5344.2  384.46  5464.4  389.33
#Mann=3,-1,0
  4551.5    0.05       0  5021.1    0.05       0  5027.3    0.05       0
Bank Sta=5021.1,5027.3
Exp/Cntr=0.3,0.1

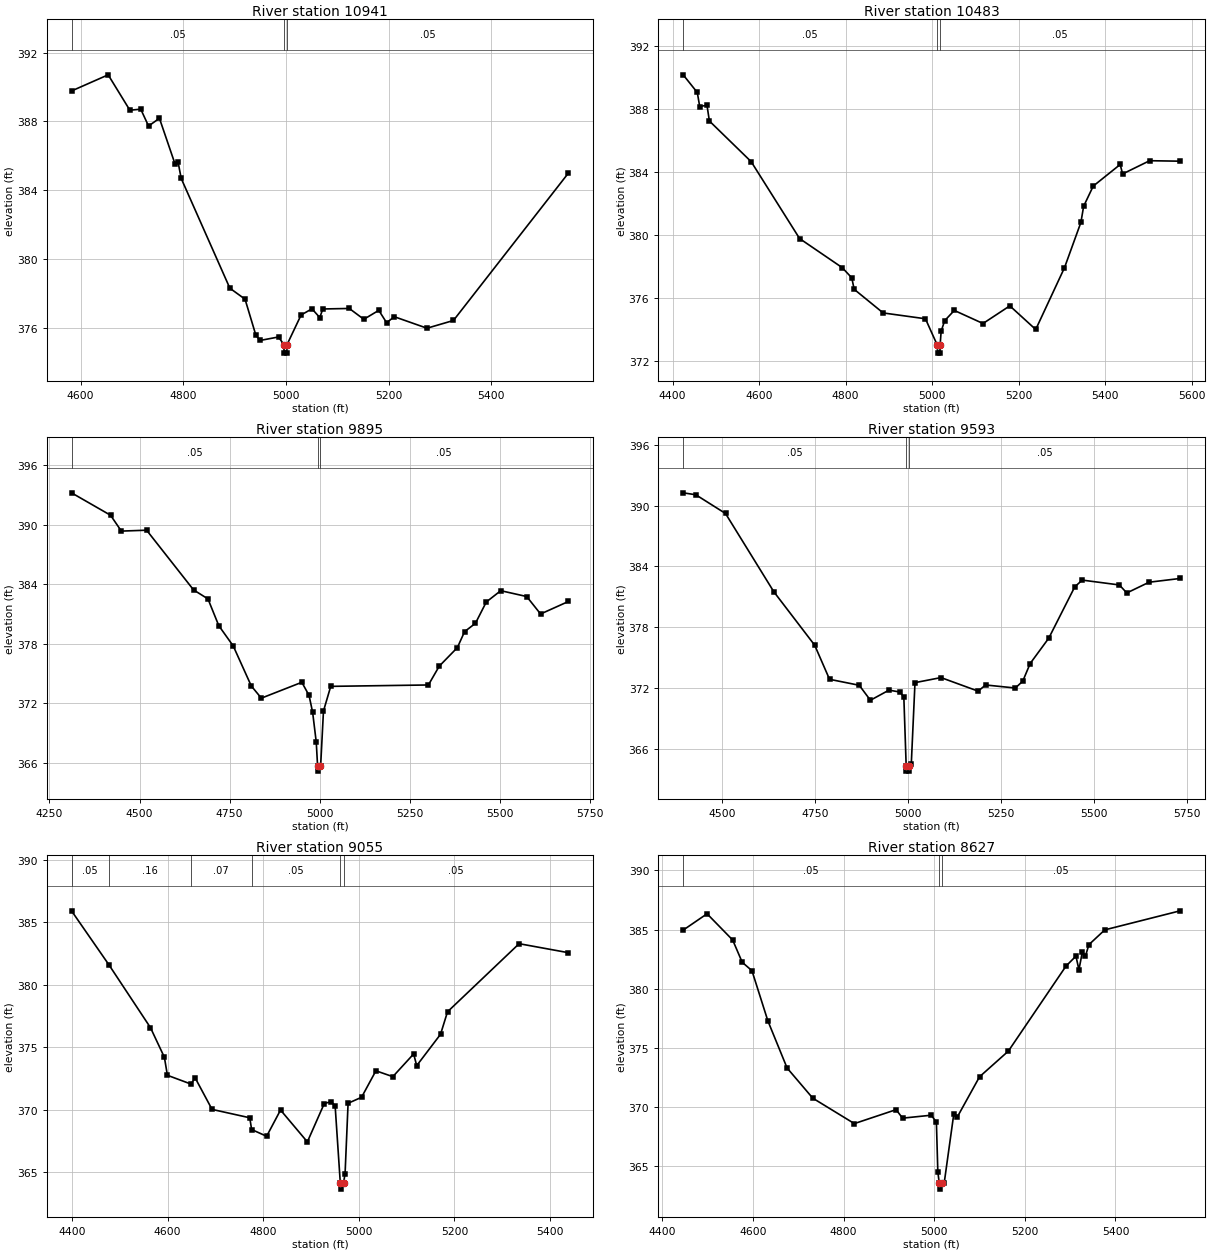
Type RM Length L Ch R = 1,10941,458,458,458
BEGIN DESCRIPTION:
North Twin Creek Trib G10941.48
END DESCRIPTION:
XS GIS Cut Line= 3
      2724806.36      6826957.40      2724450.08      6826730.88
      2723990.29      6826436.58
#Sta/Elev= 30
  4582.2  389.77  4653.6  390.71  4695.9  388.65  4717.1  388.71  4732.3  387.73
  4753.5  388.18  4784.0  385.51  4789.9  385.62  4795.9  384.68  4890.7  378.29
  4920.3  377.65  4941.5  375.54  4950.0  375.25  4985.5  375.45  4995.9  375.01
  4996.4  374.51  5001.7  374.51  5002.2  375.01  5029.5  376.73  5050.7  377.09
  5065.9  376.58  5071.8  377.08  5123.4  377.11  5151.7  376.48  5180.9  377.00
  5196.1  376.28  5211.1  376.63  5274.8  375.96  5326.3  376.41  5550.3  384.99
#Mann=3,-1,0
  4582.2    0.05       0  4995.9    0.05       0  5002.2    0.05       0
Bank Sta=4995.9,5002.2
Exp/Cntr=0.3,0.1

Type RM Length L Ch R = 1,10483,588,588,588
BEGIN DESCRIPTION:
North Twin Creek Trib G10483.33
END DESCRIPTION:
XS GIS Cut Line= 3
      2725116.46      6826642.52      2724596.39      6826381.01
      2724084.71      6826137.01
#Sta/Elev= 30
  4424.3  390.17  4456.9  389.05  4462.5  388.16  4479.3  388.24  4484.9  387.24
  4581.5  384.66  4693.5  379.78  4791.8  377.94  4814.1  377.29  4819.7  376.56
  4886.7  375.06  4984.5  374.69  5012.0  373.01  5012.5  372.51  5017.9  372.51
  5018.4  373.01  5020.8  373.90  5029.0  374.57  5051.2  375.22  5117.6  374.39
  5179.6  375.51  5239.5  374.01  5306.0  377.93  5344.0  380.81  5350.3  381.83
  5372.5  383.11  5434.8  384.48  5440.4  383.88  5502.9  384.72  5573.3  384.69
#Mann=3,-1,0
  4424.3    0.05       0  5012.0    0.05       0  5018.4    0.05       0
Bank Sta=5012,5018.4
Exp/Cntr=0.3,0.1

Type RM Length L Ch R = 1,9895,302,302,302
BEGIN DESCRIPTION:
North Twin Creek Trib G9895.06
END DESCRIPTION:
XS GIS Cut Line= 3
      2725464.11      6825913.67      2724776.77      6825890.70
      2724089.11      6825836.68
#Sta/Elev= 30
  4311.5  393.21  4419.7  390.95  4449.7  389.35  4519.7  389.44  4649.8  383.42
  4689.8  382.51  4719.8  379.81  4759.9  377.76  4809.9  373.73  4837.8  372.50
  4950.0  374.10  4970.0  372.78  4980.0  371.06  4990.0  368.06  4993.7  365.64
  4994.2  365.14  5000.5  365.64  5002.1  365.64  5010.0  371.20  5030.1  373.69
  5300.9  373.83  5331.0  375.73  5381.2  377.60  5401.2  379.21  5431.3  380.05
  5461.4  382.20  5501.5  383.34  5573.4  382.75  5611.9  380.99  5689.0  382.25
#Mann=3,-1,0
  4311.5    0.05       0  4993.7    0.05       0  5000.5    0.05       0
Bank Sta=4993.7,5000.5
Exp/Cntr=0.3,0.1

Type RM Length L Ch R = 1,9593,538,538,538
BEGIN DESCRIPTION:
North Twin Creek Trib G9592.56
END DESCRIPTION:
XS GIS Cut Line= 3
      2725429.85      6825615.00      2724821.67      6825604.28
      2724092.55      6825608.06
#Sta/Elev= 30
  4394.4  391.27  4428.3  391.08  4508.3  389.23  4638.3  381.50  4748.3  376.22
  4788.3  372.85  4868.3  372.26  4898.3  370.78  4948.3  371.78  4978.3  371.59
  4988.3  371.08  4994.6  364.28  4995.1  363.78  5000.9  363.78  5001.4  364.28
  5008.3  364.45  5018.3  372.52  5088.3  373.02  5188.3  371.68  5208.3  372.29
  5288.3  371.99  5308.3  372.66  5328.3  374.41  5378.3  376.91  5448.3  381.98
  5468.4  382.65  5568.4  382.17  5588.4  381.38  5648.4  382.44  5731.8  382.81
#Mann=3,-1,0
  4394.4    0.05       0  4994.6    0.05       0  5001.4    0.05       0
Bank Sta=4994.6,5001.4
Exp/Cntr=0.3,0.1

Type RM Length L Ch R = 1,9055,428,428,428
BEGIN DESCRIPTION:
North Twin Creek Trib G9055.07
END DESCRIPTION:
XS GIS Cut Line= 3
      2724945.08      6824887.73      2724462.44      6825257.49
      2724118.36      6825517.87
#Sta/Elev= 30
  4399.0  385.93  4477.1  381.62  4564.2  376.58  4593.3  374.21  4599.6  372.77
  4648.8  372.07  4657.7  372.56  4693.0  370.04  4771.9  369.37  4775.8  368.43
  4807.2  367.89  4836.3  369.99  4892.4  367.44  4927.8  370.51  4942.3  370.66
  4950.5  370.33  4961.3  364.16  4961.8  363.66  4968.1  364.16  4971.3  364.90
  4977.6  370.53  5005.8  371.01  5035.8  373.13  5071.2  372.66  5114.8  374.48
  5121.1  373.54  5171.0  376.05  5185.6  377.85  5335.4  383.30  5438.5  382.58
#Mann=6,-1,0
  4399.0    0.05       0  4477.1    0.16       0  4648.8    0.07       0
  4775.8    0.05       0  4961.3    0.05       0  4968.1    0.05       0
Bank Sta=4961.3,4968.1
Exp/Cntr=0.3,0.1

Type RM Length L Ch R = 1,8627,468,468,468
BEGIN DESCRIPTION:
North Twin Creek Trib G8626.86
END DESCRIPTION:
XS GIS Cut Line= 3
      2724600.17      6824550.68      2724194.37      6824935.19
      2723843.13      6825342.67
#Sta/Elev= 30
  4445.7  384.96  4498.4  386.34  4555.0  384.12  4576.0  382.24  4597.5  381.53
  4632.7  377.28  4675.1  373.30  4731.8  370.75  4823.6  368.60  4915.8  369.78
  4930.0  369.06  4993.5  369.31  5004.7  368.72  5007.9  364.51  5011.1  363.56
  5011.6  363.06  5017.9  363.56  5022.1  363.62  5043.0  369.38  5050.6  369.14
  5100.0  372.56  5163.6  374.73  5290.9  381.92  5312.8  382.76  5319.4  381.61
  5327.1  383.14  5333.7  382.75  5341.4  383.73  5376.5  384.98  5542.7  386.59
#Mann=3,-1,0
  4445.7    0.05       0  5011.1    0.05       0  5017.9    0.05       0
Bank Sta=5011.1,5017.9
Exp/Cntr=0.3,0.1