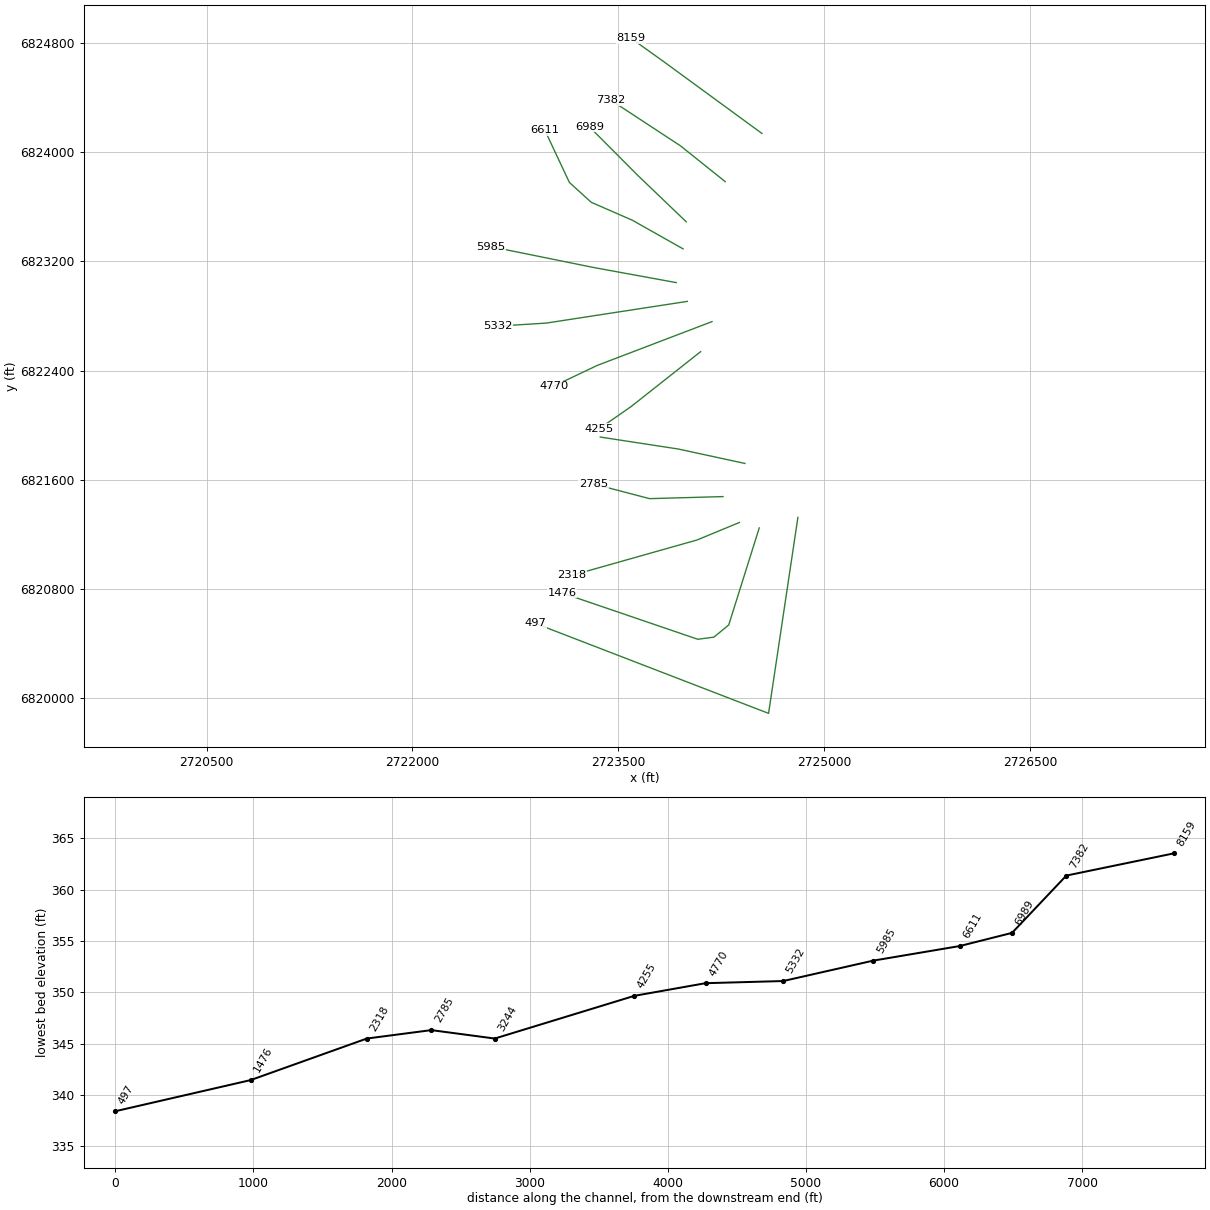
HEC-RAS study North Twin Creek Trib G.prj: North Twin Creek Trib G Base Level Engineering

--- North Twin Creek Trib G.g01 (geometry) --- (continued)

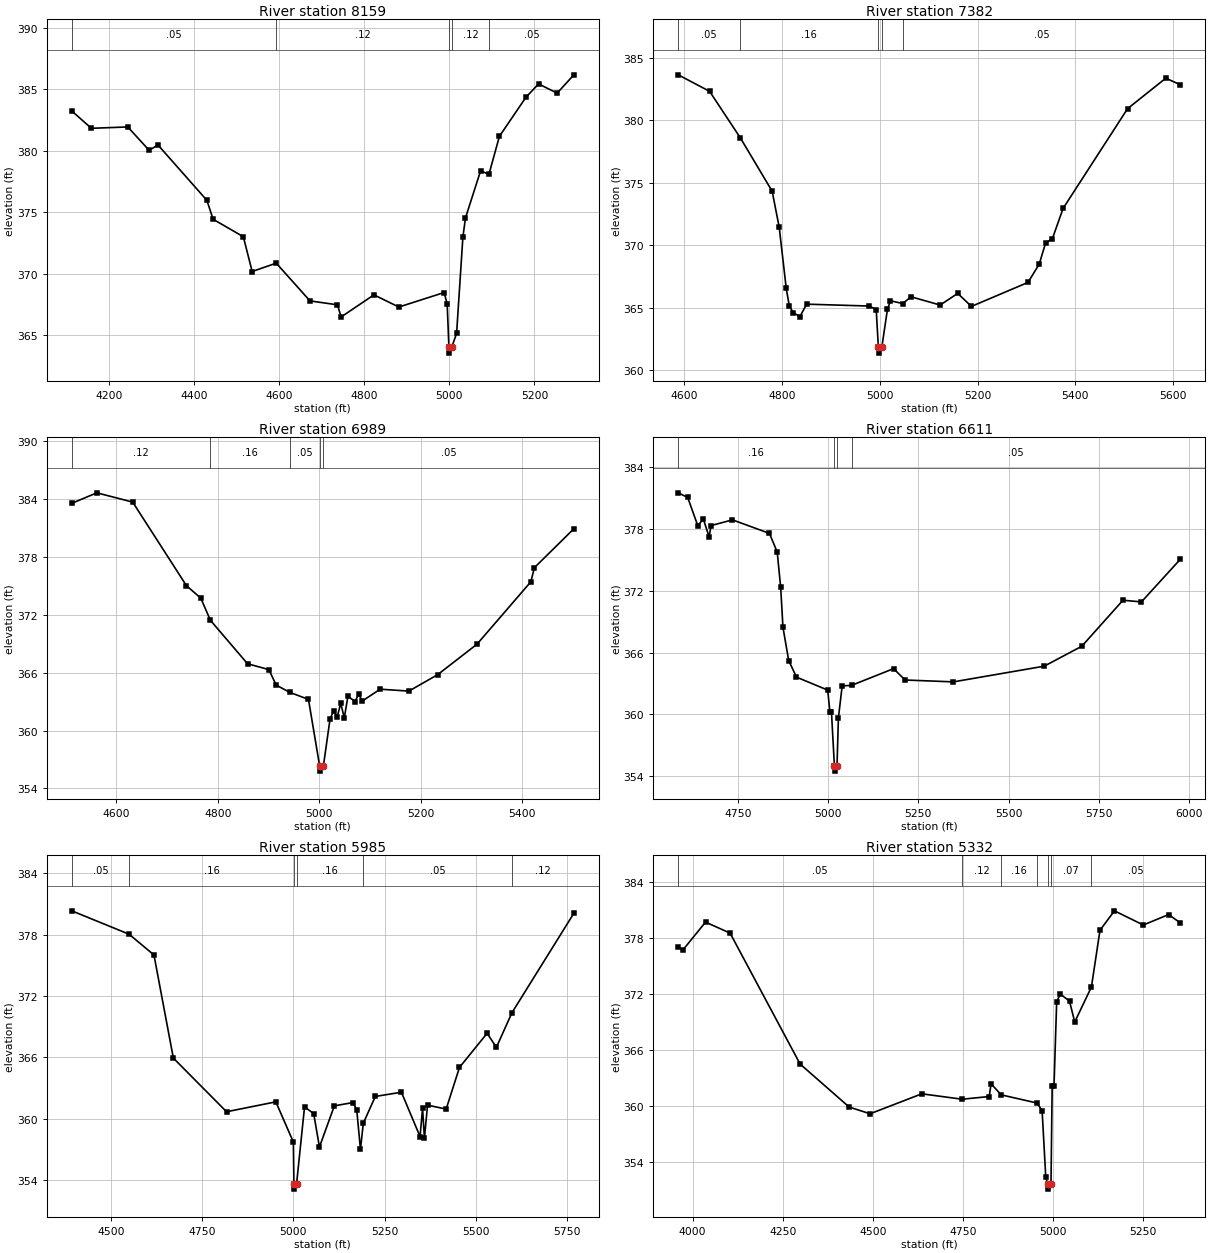
Type RM Length L Ch R = 1,8159,777,777,777
BEGIN DESCRIPTION:
North Twin Creek Trib G8158.85
END DESCRIPTION:
XS GIS Cut Line= 3
      2724547.35      6824138.12      2723822.05      6824671.08
      2723594.11      6824834.62
#Sta/Elev= 30
  4112.0  383.23  4158.1  381.82  4243.7  381.93  4293.9  380.03  4314.8  380.46
  4429.7  375.96  4444.3  374.42  4515.4  373.00  4536.2  370.17  4592.8  370.85
  4672.1  367.78  4736.8  367.46  4745.3  366.47  4822.5  368.27  4881.1  367.28
  4987.6  368.46  4994.8  367.52  4998.8  364.03  4999.3  363.53  5005.7  364.03
  5016.9  365.14  5031.7  372.97  5037.8  374.53  5073.4  378.37  5092.9  378.07
  5117.6  381.17  5180.3  384.36  5209.7  385.43  5253.3  384.68  5292.6  386.17
#Mann=5,-1,0
  4112.0    0.05       0  4592.8    0.12       0  4998.8    0.07       0
  5005.7    0.12       0  5092.9    0.05       0
Bank Sta=4998.8,5005.7
Exp/Cntr=0.3,0.1

Type RM Length L Ch R = 1,7382,393,393,393
BEGIN DESCRIPTION:
North Twin Creek Trib G7382.38
END DESCRIPTION:
XS GIS Cut Line= 3
      2724279.97      6823785.01      2723953.42      6824047.57
      2723445.88      6824382.12
#Sta/Elev= 30
  4587.8  383.65  4651.9  382.33  4714.9  378.60  4779.9  374.33  4794.3  371.45
  4808.7  366.55  4815.1  365.12  4823.1  364.61  4836.7  364.29  4850.3  365.29
  4978.3  365.14  4992.7  364.86  4997.1  361.87  4997.6  361.37  5004.3  361.87
  5015.7  364.88  5021.9  365.56  5047.0  365.34  5064.0  365.88  5123.5  365.22
  5159.4  366.15  5187.5  365.11  5303.1  367.03  5326.1  368.49  5339.1  370.18
  5353.1  370.54  5375.0  372.96  5506.8  380.94  5585.0  383.38  5614.7  382.86
#Mann=5,-1,0
  4587.8    0.05       0  4714.9    0.16       0  4997.1    0.07       0
  5004.3    0.16       0  5047.0    0.05       0
Bank Sta=4997.1,5004.3
Exp/Cntr=0.3,0.1

Type RM Length L Ch R = 1,6989,378,378,378
BEGIN DESCRIPTION:
North Twin Creek Trib G6989.3
END DESCRIPTION:
XS GIS Cut Line= 3
      2723995.76      6823490.95      2723640.95      6823832.48
      2723290.84      6824185.83
#Sta/Elev= 30
  4512.0  383.57  4561.4  384.66  4632.1  383.70  4738.1  375.03  4766.4  373.73
  4785.3  371.44  4858.5  366.93  4900.7  366.32  4914.9  364.72  4941.9  363.96
  4978.7  363.23  5000.8  356.29  5001.3  355.79  5008.0  356.29  5021.1  361.15
  5028.2  362.07  5035.2  361.40  5042.3  362.81  5049.3  361.32  5056.5  363.55
  5070.6  363.01  5077.6  363.79  5084.7  363.06  5120.1  364.29  5176.6  364.09
  5233.2  365.79  5311.0  368.96  5417.1  375.43  5424.2  376.90  5501.9  380.93
#Mann=5,-1,0
  4512.0    0.12       0  4785.3    0.16       0  4941.9    0.05       0
  5000.8    0.05       0  5008.0    0.05       0
Bank Sta=5000.8,5008
Exp/Cntr=0.3,0.1

Type RM Length L Ch R = 1,6611,626,626,626
BEGIN DESCRIPTION:
North Twin Creek Trib G6611.02
END DESCRIPTION:
XS GIS Cut Line= 5
      2723972.93      6823292.49      2723603.54      6823502.09
      2723303.57      6823633.65      2723144.39      6823778.87
      2722964.95      6824162.66
#Sta/Elev= 30
  4584.7  381.48  4611.0  381.03  4638.7  378.31  4654.3  378.93  4670.1  377.23
  4675.9  378.31  4735.0  378.86  4837.4  377.55  4859.0  375.74  4868.6  372.32
  4874.9  368.45  4890.8  365.23  4912.4  363.62  4999.0  362.36  5005.1  360.20
  5009.4  360.20  5017.5  355.01  5018.0  354.51  5024.7  355.01  5028.6  359.67
  5039.0  362.77  5064.9  362.82  5181.4  364.44  5213.5  363.34  5347.2  363.16
  5598.9  364.68  5703.0  366.61  5817.2  371.07  5868.4  370.91  5976.1  375.04
#Mann=4,-1,0
  4584.7    0.16       0  5017.5    0.07       0  5024.7    0.16       0
  5064.9    0.05       0
Bank Sta=5017.5,5024.7
Exp/Cntr=0.3,0.1

Type RM Length L Ch R = 1,5985,653,653,653
BEGIN DESCRIPTION:
North Twin Creek Trib G5985.26
END DESCRIPTION:
XS GIS Cut Line= 3
      2723922.88      6823045.40      2723320.57      6823156.07
      2722573.33      6823308.39
#Sta/Elev= 30
  4393.4  380.32  4550.4  378.03  4618.5  376.00  4671.6  365.91  4817.3  360.66
  4952.3  361.63  5000.3  357.69  5001.7  353.59  5002.2  353.09  5009.0  353.59
  5030.9  361.14  5055.9  360.48  5071.7  357.21  5112.5  361.24  5163.5  361.56
  5173.8  360.86  5184.0  356.98  5191.8  359.54  5224.8  362.16  5296.2  362.57
  5347.2  358.23  5354.1  360.99  5359.2  358.06  5367.7  361.31  5418.7  360.92
  5455.2  365.00  5530.9  368.34  5556.3  366.96  5598.7  370.34  5768.4  380.08
#Mann=6,-1,0
  4393.4    0.05       0  4550.4    0.16       0  5001.7    0.07       0
  5009.0    0.16       0  5191.8    0.05       0  5598.7    0.12       0
Bank Sta=5001.7,5009
Exp/Cntr=0.3,0.1

Type RM Length L Ch R = 1,5332,562,562,562
BEGIN DESCRIPTION:
North Twin Creek Trib G5331.74
END DESCRIPTION:
XS GIS Cut Line= 3
      2724003.94      6822907.89      2722975.81      6822748.88
      2722623.55      6822726.83
#Sta/Elev= 30
  3960.1  377.10  3972.8  376.73  4035.9  379.73  4104.0  378.55  4298.3  364.51
  4434.5  359.90  4492.6  359.18  4636.0  361.32  4748.0  360.74  4823.1  361.03
  4828.2  362.40  4856.3  361.21  4956.0  360.33  4969.9  359.51  4980.0  352.38
  4985.8  351.60  4986.3  351.10  4994.5  351.60  4997.8  362.16  5002.9  362.16
  5010.3  371.20  5020.3  372.02  5045.9  371.26  5060.4  369.02  5106.7  372.77
  5130.5  378.86  5170.6  380.94  5250.8  379.42  5320.9  380.54  5353.4  379.65
#Mann=7,-1,0
  3960.1    0.05       0  4748.0    0.12       0  4856.3    0.16       0
  4956.0    0.07       0  4985.8    0.07       0  4994.5    0.07       0
  5106.7    0.05       0
Bank Sta=4985.8,4994.5
Exp/Cntr=0.3,0.1

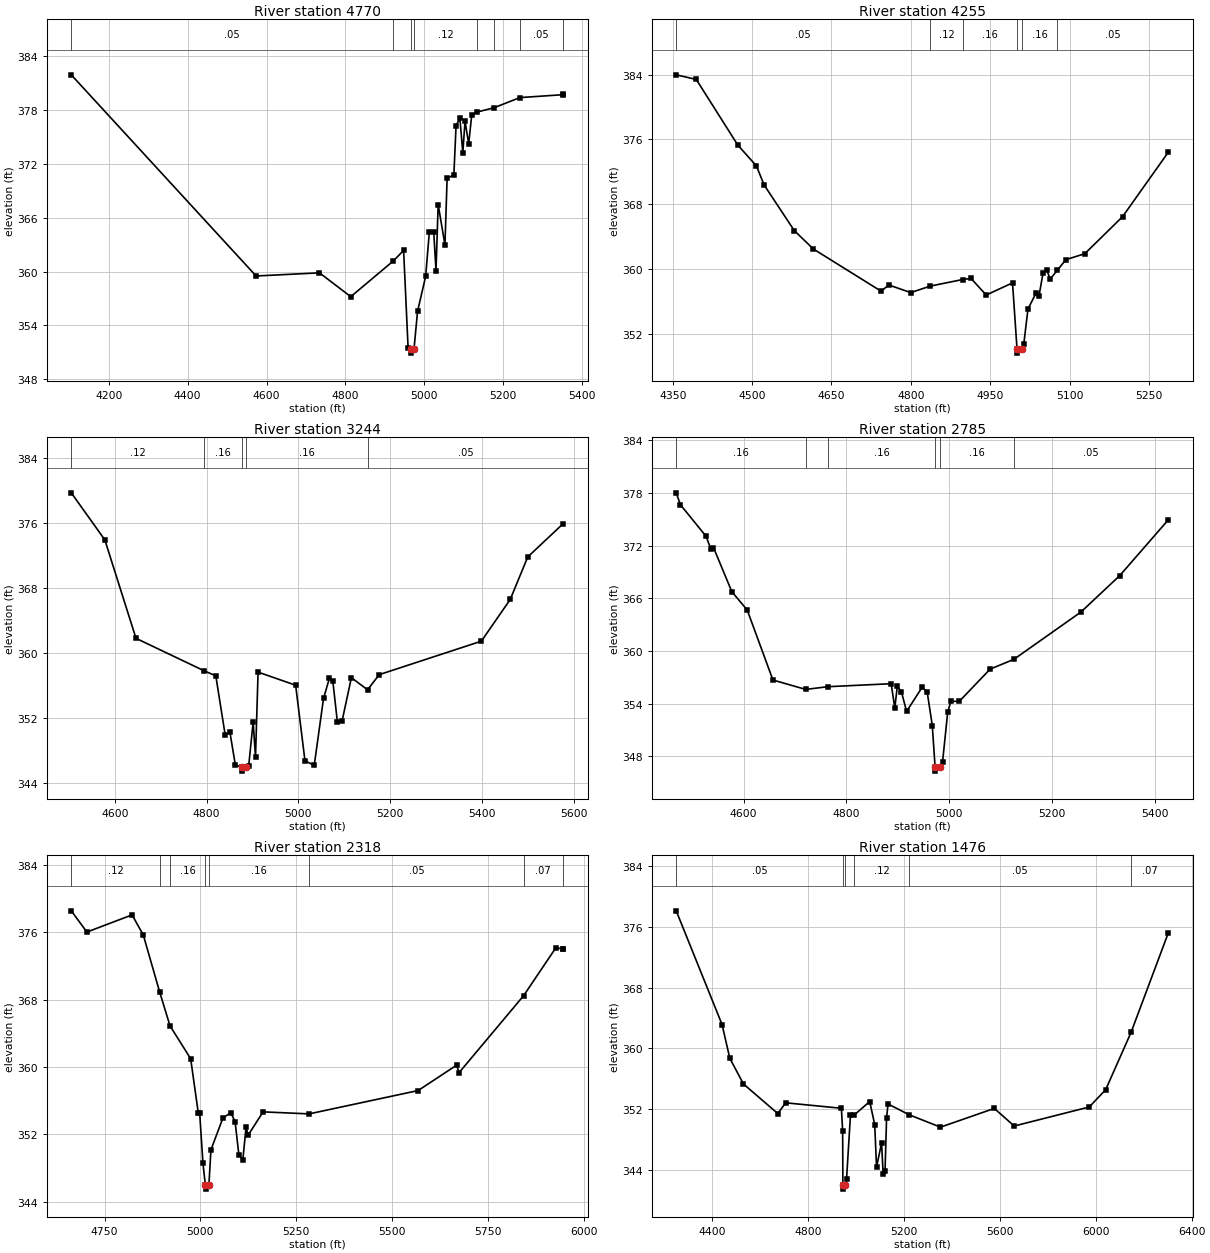
Type RM Length L Ch R = 1,4770,515,515,515
BEGIN DESCRIPTION:
North Twin Creek Trib G4769.71
END DESCRIPTION:
XS GIS Cut Line= 3
      2724183.77      6822759.68      2723347.55      6822438.88
      2723029.39      6822286.76
#Sta/Elev= 30
  4104.7  381.95  4573.6  359.50  4734.4  359.85  4813.8  357.19  4921.8  361.18
  4947.8  362.35  4959.2  351.49  4965.4  351.39  4965.9  350.89  4974.3  351.39
  4983.2  355.55  5003.7  359.45  5013.1  364.40  5024.2  364.44  5030.0  360.09
  5035.5  367.47  5052.7  362.96  5058.2  370.42  5075.3  370.76  5080.9  376.29
  5090.7  377.09  5098.0  373.23  5103.6  376.80  5112.9  374.24  5120.7  377.50
  5134.4  377.80  5176.8  378.27  5242.9  379.41  5351.4  379.73  5353.0  379.80
#Mann=8,-1,0
  4104.7    0.05       0  4921.8    0.12       0  4965.4    0.07       0
  4974.3    0.12       0  5134.4    0.16       0  5176.8    0.07       0
  5242.9    0.05       0  5351.4    0.07       0
Bank Sta=4965.4,4974.3
Exp/Cntr=0.3,0.1

Type RM Length L Ch R = 1,4255,1011,1011,1011
BEGIN DESCRIPTION:
North Twin Creek Trib G4255.25
END DESCRIPTION:
XS GIS Cut Line= 3
      2724100.69      6822539.52      2723592.72      6822136.33
      2723361.94      6821975.54
#Sta/Elev= 30
  4356.6  383.96  4394.5  383.39  4473.0  375.30  4508.2  372.73  4522.6  370.40
  4579.6  364.77  4615.6  362.50  4743.8  357.29  4758.2  358.06  4799.8  357.12
  4836.5  357.92  4897.8  358.73  4913.6  358.87  4942.4  356.82  4992.1  358.32
  5000.6  350.16  5001.1  349.66  5009.6  350.16  5013.3  350.75  5021.3  355.10
  5036.2  357.02  5042.2  356.75  5049.9  359.58  5057.1  359.87  5063.2  358.78
  5076.9  359.88  5092.9  361.18  5128.6  361.91  5200.2  366.49  5286.4  374.42
#Mann=6,-1,0
  4356.6    0.05       0  4836.5    0.12       0  4897.8    0.16       0
  5000.6    0.07       0  5009.6    0.16       0  5076.9    0.05       0
Bank Sta=5000.6,5009.6
Exp/Cntr=0.3,0.1

Type RM Length L Ch R = 1,3244,459,459,459
BEGIN DESCRIPTION:
North Twin Creek Trib G3243.75
END DESCRIPTION:
XS GIS Cut Line= 3
      2724423.88      6821720.73      2723938.55      6821826.32
      2723369.36      6821914.07
#Sta/Elev= 30
  4505.1  379.68  4578.3  373.90  4646.2  361.81  4795.2  357.81  4820.2  357.20
  4840.6  349.94  4850.9  350.30  4862.7  346.26  4877.0  346.00  4877.5  345.50
  4886.1  346.00  4891.8  346.12  4901.6  351.54  4906.7  347.18  4912.3  357.66
  4994.2  356.05  5014.5  346.78  5034.7  346.20  5055.0  354.44  5067.7  356.88
  5075.2  356.57  5085.3  351.49  5095.4  351.65  5115.7  356.98  5150.9  355.49
  5176.4  357.35  5399.0  361.46  5461.9  366.58  5500.2  371.81  5577.7  375.91
#Mann=5,-1,0
  4505.1    0.12       0  4795.2    0.16       0  4877.0    0.07       0
  4886.1    0.16       0  5150.9    0.05       0
Bank Sta=4877,4886.1
Exp/Cntr=0.3,0.1

Type RM Length L Ch R = 1,2785,467,467,467
BEGIN DESCRIPTION:
North Twin Creek Trib G2784.66
END DESCRIPTION:
XS GIS Cut Line= 3
      2724264.14      6821478.02      2723728.73      6821462.95
      2723320.73      6821570.29
#Sta/Elev= 30
  4468.9  378.03  4477.0  376.68  4527.1  373.07  4536.4  371.59  4541.4  371.80
  4577.1  366.77  4607.1  364.67  4657.1  356.70  4720.9  355.63  4764.1  355.94
  4887.2  356.28  4894.2  353.52  4899.2  356.01  4907.2  355.34  4917.2  353.13
  4947.2  355.85  4957.2  355.37  4967.2  351.51  4972.6  346.82  4973.1  346.32
  4981.8  346.82  4987.2  347.38  4997.2  353.04  5003.4  354.28  5019.7  354.27
  5079.7  357.94  5126.0  359.06  5256.5  364.45  5332.0  368.60  5426.4  374.95
#Mann=6,-1,0
  4468.9    0.16       0  4720.9    0.05       0  4764.1    0.16       0
  4972.6    0.07       0  4981.8    0.16       0  5126.0    0.05       0
Bank Sta=4972.6,4981.8
Exp/Cntr=0.3,0.1

Type RM Length L Ch R = 1,2318,842,842,842
BEGIN DESCRIPTION:
North Twin Creek Trib G2317.65
END DESCRIPTION:
XS GIS Cut Line= 3
      2724383.70      6821288.47      2724074.31      6821160.03
      2723161.64      6820900.66
#Sta/Elev= 30
  4663.1  378.53  4703.9  376.01  4821.8  378.05  4851.1  375.65  4893.5  368.93
  4920.7  364.88  4974.6  360.98  4994.5  354.53  4998.1  354.53  5006.7  348.56
  5012.9  346.00  5013.4  345.50  5022.2  346.00  5027.5  350.16  5058.7  353.94
  5079.5  354.58  5090.6  353.48  5100.3  349.60  5110.7  348.97  5119.2  352.88
  5124.4  351.89  5163.5  354.67  5283.6  354.43  5568.1  357.20  5669.1  360.23
  5674.3  359.29  5843.3  368.46  5927.1  374.12  5945.5  374.03  5946.9  374.03
#Mann=8,-1,0
  4663.1    0.12       0  4893.5    0.05       0  4920.7    0.16       0
  5012.9    0.07       0  5022.2    0.16       0  5283.6    0.05       0
  5843.3    0.07       0  5945.5    0.05       0
Bank Sta=5012.9,5022.2
Exp/Cntr=0.3,0.1

Type RM Length L Ch R = 1,1476,979,979,979
BEGIN DESCRIPTION:
North Twin Creek Trib G1476.11
END DESCRIPTION:
XS GIS Cut Line= 5
      2724527.92      6821248.51      2724305.63      6820537.66
      2724197.46      6820448.55      2724080.23      6820432.83
      2723089.24      6820772.76
#Sta/Elev= 30
  4251.6  378.14  4442.6  363.15  4475.0  358.70  4531.9  355.31  4675.1  351.41
  4707.6  352.83  4940.1  352.11  4945.3  349.12  4946.3  341.95  4946.8  341.45
  4955.6  341.95  4961.5  342.75  4977.8  351.17  4991.6  351.17  5058.1  353.00
  5078.9  349.96  5086.6  344.36  5107.6  347.55  5114.1  343.39  5121.9  343.80
  5128.4  350.81  5134.3  352.68  5222.7  351.25  5353.1  349.62  5577.3  352.09
  5660.5  349.77  5973.2  352.28  6041.6  354.56  6147.6  362.13  6302.5  375.22
#Mann=6,-1,0
  4251.6    0.05       0  4946.3    0.07       0  4955.6    0.05       0
  4991.6    0.12       0  5222.7    0.05       0  6147.6    0.07       0
Bank Sta=4946.3,4955.6
Exp/Cntr=0.3,0.1

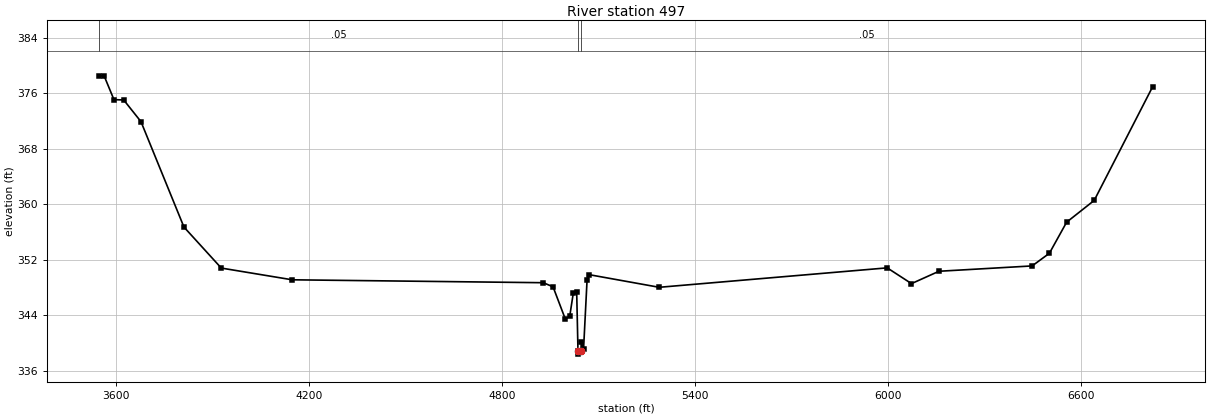
Type RM Length L Ch R = 1,497,0,0,0
BEGIN DESCRIPTION:
North Twin Creek Trib G497.092
END DESCRIPTION:
XS GIS Cut Line= 3
      2724809.79      6821325.93      2724595.92      6819890.07
      2722896.41      6820548.78
#Sta/Elev= 30
  3548.3  378.52  3563.4  378.49  3593.7  375.09  3624.1  375.04  3677.7  371.92
  3811.3  356.73  3927.4  350.82  4147.9  349.13  4928.3  348.71  4958.6  348.12
  4997.0  343.44  5010.6  343.93  5021.6  347.23  5032.1  347.38  5036.1  338.92
  5036.6  338.42  5045.5  338.92  5046.1  340.14  5053.5  339.20  5064.3  349.05
  5070.7  349.87  5288.6  348.05  5997.3  350.85  6072.8  348.58  6158.2  350.36
  6447.8  351.13  6501.4  352.95  6555.0  357.43  6640.8  360.57  6822.7  376.98
#Mann=3,-1,0
  3548.3    0.05       0  5036.1    0.05       0  5045.5    0.05       0
Bank Sta=5036.1,5045.5
Exp/Cntr=0.3,0.1

Chan Stop Cuts=-1