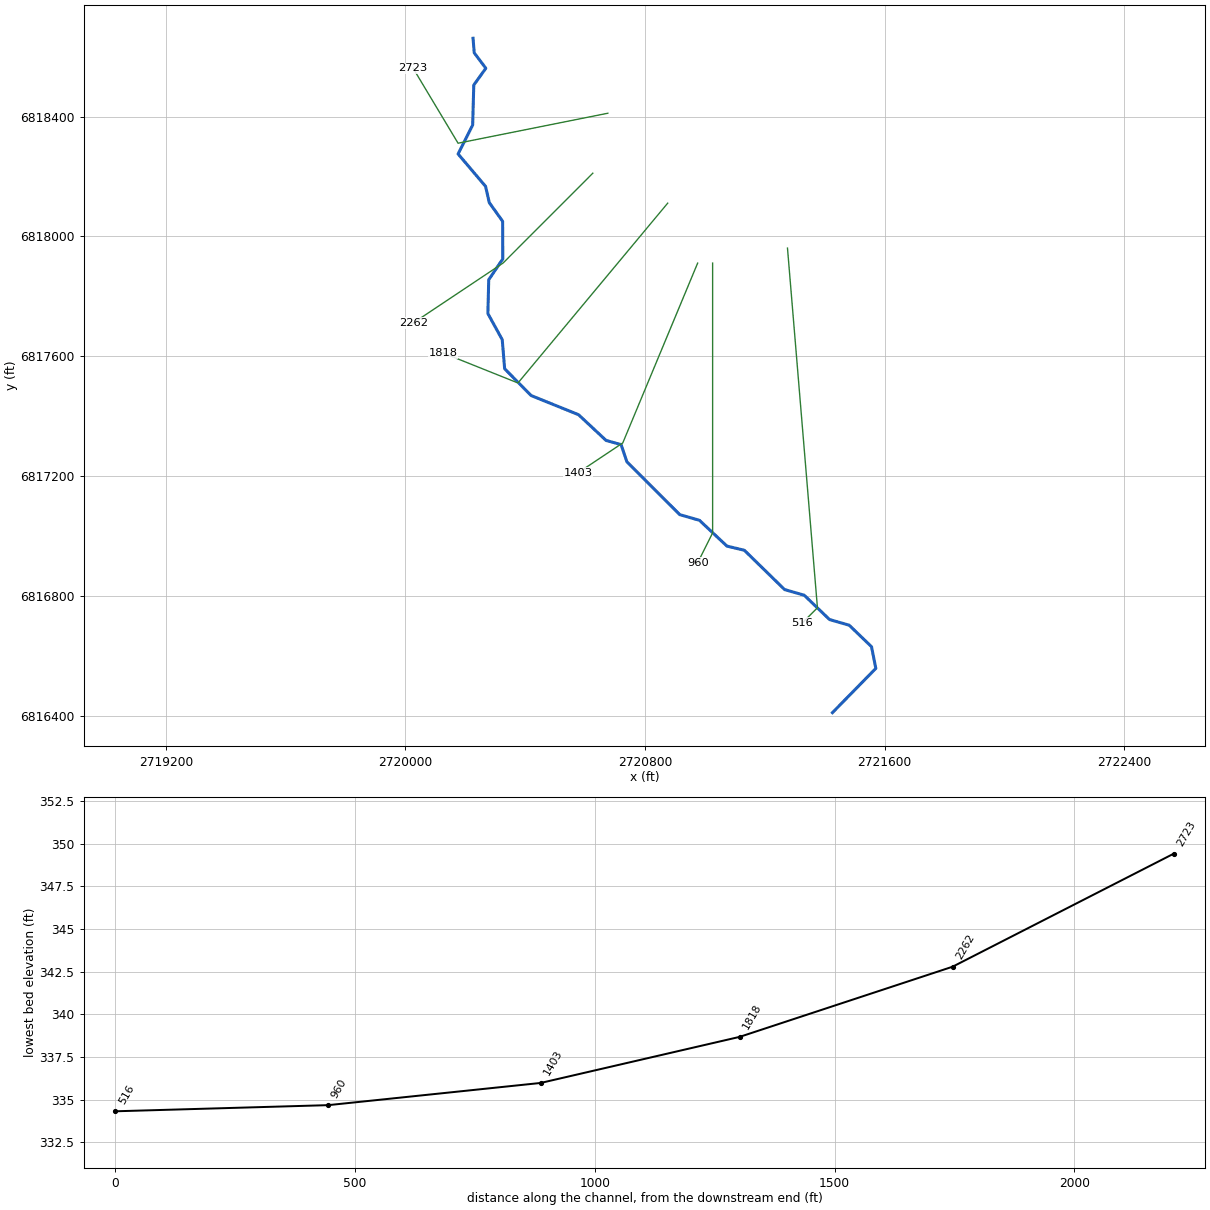
--- North Twin Creek Trib H.prj (project) ---

Proj Title=North Twin Creek Trib H Base Level Engineering
Current Plan=p01
Default Exp/Contr=0.3,0.1
English Units
Geom File=g01
Flow File=f01
Plan File=p01
BEGIN DESCRIPTION:
North Twin Creek Trib H
END DESCRIPTION:

--- North Twin Creek Trib H.p01 (plan) ---

Plan Title=Multiple Run
Short Identifier=Multiple
Geom File=g01
Flow File=f01
Subcritical Flow
K Sum by GR= 0
Std Step Tol= 0.01
Critical Tol= 0.01
Num of Std Step Trials= 20
Max Error Tol= 0.3
Flow Tol Ratio= 0.001
Split Flow NTrial= 30
Split Flow Tol= 0.02
Split Flow Ratio= 0.02
Log Output Level= 0
Friction Slope Method= 1
Unsteady Friction Slope Method= 2
Unsteady Bridges Friction Slope Method= 1
Parabolic Critical Depth
Global Vel Dist=  1 , 1 , 1
Global Log Level= 0
CheckData=True
Encroach Param= -1, 0, 0, 0
BEGIN DESCRIPTION:
Multiple Run
END DESCRIPTION:

--- North Twin Creek Trib H.f01 (steady flow) ---

Flow Title=Multiple
Number of Profiles=7
Profile Names=10-year,25-year,50-year,1pct_min,100-year,1pct_plu,500-year
River Rch & RM= North Twin Creek,Reach-1,2723
     242     298     340     192     383     764     486
Boundary for River Rch & Prof#=North Twin Creek,Reach-1,1
Up Type=0
Dn Type=3
Dn Slope=0.005
Boundary for River Rch & Prof#=North Twin Creek,Reach-1,2
Up Type=0
Dn Type=3
Dn Slope=0.005
Boundary for River Rch & Prof#=North Twin Creek,Reach-1,3
Up Type=0
Dn Type=3
Dn Slope=0.005
Boundary for River Rch & Prof#=North Twin Creek,Reach-1,4
Up Type=0
Dn Type=3
Dn Slope=0.005
Boundary for River Rch & Prof#=North Twin Creek,Reach-1,5
Up Type=0
Dn Type=3
Dn Slope=0.005
Boundary for River Rch & Prof#=North Twin Creek,Reach-1,6
Up Type=0
Dn Type=3
Dn Slope=0.005
Boundary for River Rch & Prof#=North Twin Creek,Reach-1,7
Up Type=0
Dn Type=3
Dn Slope=0.005

--- North Twin Creek Trib H.g01 (geometry) ---

Geom Title=Existing Conditions

River Reach=North Twin Creek,Reach-1
Reach XY= 30
      2720226.00      6818661.00      2720230.00      6818612.36
      2720268.69      6818561.04      2720228.46      6818505.14
      2720224.75      6818371.50      2720176.10      6818275.04
      2720267.84      6818167.05      2720280.22      6818112.75
      2720324.81      6818050.50      2720325.33      6817924.93
      2720278.37      6817855.47      2720275.57      6817742.67
      2720323.53      6817655.43      2720331.52      6817558.56
      2720419.93      6817469.13      2720578.29      6817405.15
      2720670.26      6817319.30      2720720.38      6817305.38
      2720739.73      6817248.02      2720916.32      6817071.78
      2720982.04      6817052.82      2721073.72      6816966.87
      2721132.05      6816952.84      2721266.32      6816821.78
      2721332.04      6816802.82      2721416.33      6816721.80
      2721482.07      6816702.85      2721556.60      6816631.13
      2721570.94      6816558.71      2721426.00      6816411.00

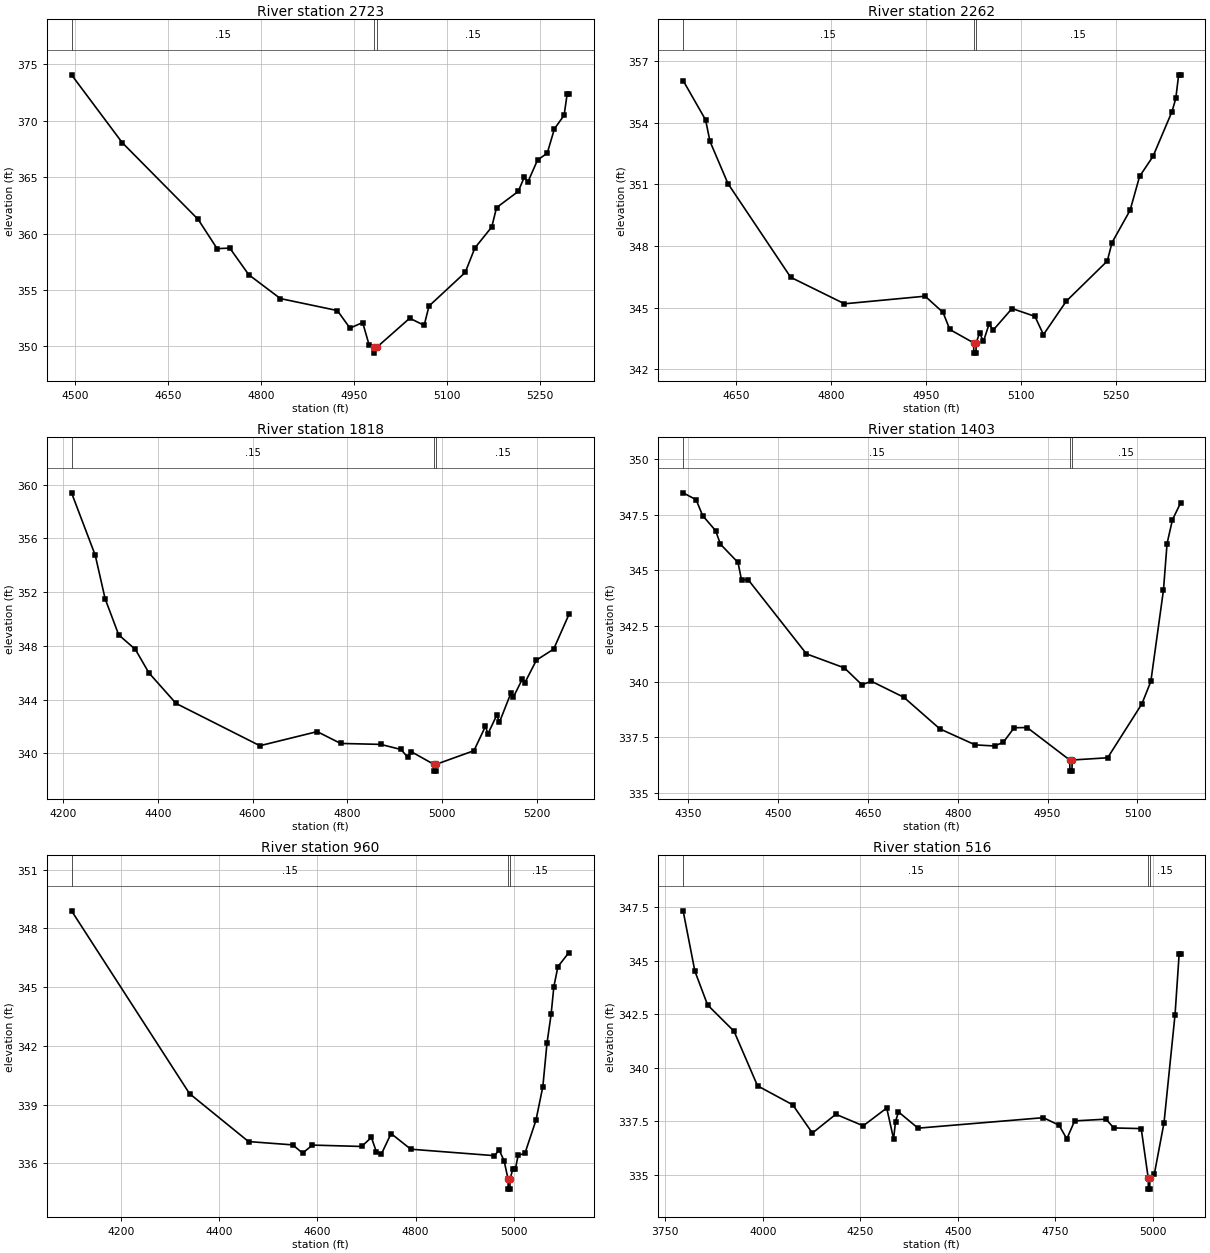
Type RM Length L Ch R = 1,2723,461,461,461
BEGIN DESCRIPTION:
North Twin Creek Trib H 6.0
END DESCRIPTION:
XS GIS Cut Line= 3
      2720676.01      6818411.00      2720176.00      6818311.00
      2720025.98      6818561.03
#Sta/Elev= 30
  4494.9  374.05  4576.5  368.05  4698.9  361.25  4729.5  358.66  4749.9  358.71
  4780.5  356.35  4831.4  354.24  4923.2  353.18  4943.6  351.62  4964.0  352.12
  4974.2  350.17  4982.4  349.91  4982.7  349.41  4986.4  349.91  5039.8  352.50
  5063.1  351.87  5070.9  353.58  5129.2  356.55  5144.8  358.72  5172.0  360.58
  5179.7  362.29  5214.7  363.73  5224.4  364.99  5230.3  364.57  5245.8  366.51
  5261.4  367.11  5273.0  369.27  5288.6  370.47  5293.4  372.32  5296.4  372.32
#Mann=3,-1,0
  4494.9    0.15       0  4982.4    0.05       0  4986.4    0.15       0
Bank Sta=4982.4,4986.4
Exp/Cntr=0.3,0.1

Type RM Length L Ch R = 1,2262,444,444,444
BEGIN DESCRIPTION:
North Twin Creek Trib H 5.0
END DESCRIPTION:
XS GIS Cut Line= 3
      2720626.01      6818211.01      2720326.00      6817911.00
      2720026.02      6817711.02
#Sta/Elev= 30
  4566.8  356.05  4602.2  354.14  4609.2  353.09  4637.5  351.04  4736.5  346.48
  4821.4  345.19  4948.6  345.56  4976.9  344.77  4987.5  343.94  5025.1  343.29
  5025.4  342.79  5028.9  342.79  5029.1  343.29  5034.6  343.77  5040.6  343.36
  5049.7  344.22  5055.7  343.90  5085.7  344.96  5121.8  344.58  5135.3  343.69
  5171.4  345.32  5236.0  347.27  5243.5  348.17  5272.0  349.74  5287.0  351.39
  5308.1  352.36  5338.1  354.54  5344.1  355.18  5348.6  356.33  5351.6  356.33
#Mann=3,-1,0
  4566.8    0.15       0  5025.1    0.05       0  5029.1    0.15       0
Bank Sta=5025.1,5029.1
Exp/Cntr=0.3,0.1

Type RM Length L Ch R = 1,1818,415,415,415
BEGIN DESCRIPTION:
North Twin Creek Trib H 4.0
END DESCRIPTION:
XS GIS Cut Line= 3
      2720875.99      6818110.99      2720376.00      6817511.00
      2720125.97      6817611.01
#Sta/Elev= 30
  4217.7  359.39  4267.8  354.74  4288.6  351.51  4317.3  348.82  4352.4  347.74
  4381.1  345.99  4438.3  343.72  4615.4  340.57  4736.4  341.62  4785.9  340.74
  4870.5  340.67  4913.4  340.29  4927.8  339.70  4934.3  340.14  4983.0  339.18
  4983.3  338.68  4986.8  338.68  4987.0  339.18  5067.4  340.20  5091.6  342.01
  5097.0  341.46  5115.8  342.86  5121.2  342.32  5145.5  344.49  5150.8  344.20
  5169.7  345.54  5175.1  345.27  5199.3  346.94  5235.7  347.76  5268.0  350.34
#Mann=3,-1,0
  4217.7    0.15       0  4983.0    0.05       0  4987.0    0.15       0
Bank Sta=4983,4987
Exp/Cntr=0.3,0.1

Type RM Length L Ch R = 1,1403,443,443,443
BEGIN DESCRIPTION:
North Twin Creek Trib H 3.0
END DESCRIPTION:
XS GIS Cut Line= 3
      2720976.01      6817911.02      2720726.00      6817311.00
      2720576.00      6817211.00
#Sta/Elev= 30
  4341.6  348.49  4363.3  348.18  4374.1  347.47  4395.8  346.79  4403.9  346.18
  4433.2  345.36  4439.1  344.57  4450.0  344.59  4547.5  341.25  4610.8  340.62
  4640.1  339.86  4655.8  340.02  4710.0  339.30  4770.1  337.88  4829.1  337.16
  4861.6  337.11  4876.2  337.28  4894.1  337.93  4915.8  337.94  4986.9  336.48
  4987.2  335.98  4990.7  335.98  4990.9  336.48  5050.2  336.58  5107.3  339.00
  5122.3  340.01  5143.4  344.12  5149.4  346.21  5158.4  347.28  5171.9  348.03
#Mann=3,-1,0
  4341.6    0.15       0  4986.9    0.05       0  4990.9    0.15       0
Bank Sta=4986.9,4990.9
Exp/Cntr=0.3,0.1

Type RM Length L Ch R = 1,960,444,444,444
BEGIN DESCRIPTION:
North Twin Creek Trib H 2.0
END DESCRIPTION:
XS GIS Cut Line= 3
      2721026.00      6817911.00      2721026.00      6817011.00
      2720976.00      6816911.00
#Sta/Elev= 30
  4100.0  348.90  4340.0  339.56  4460.0  337.11  4550.0  336.94  4570.0  336.52
  4590.0  336.93  4690.0  336.86  4710.0  337.32  4720.0  336.59  4730.0  336.46
  4750.0  337.52  4790.0  336.72  4960.0  336.39  4970.0  336.67  4980.0  336.12
  4988.0  335.18  4988.2  334.68  4991.7  334.68  4992.0  335.18  4997.5  335.71
  5002.8  335.71  5008.4  336.40  5022.4  336.52  5044.7  338.20  5058.7  339.92
  5067.1  342.13  5075.5  343.61  5081.1  345.03  5089.4  346.05  5111.8  346.77
#Mann=3,-1,0
  4100.0    0.15       0  4988.0    0.05       0  4992.0    0.15       0
Bank Sta=4988,4992
Exp/Cntr=0.3,0.1

Type RM Length L Ch R = 1,516,0,0,0
BEGIN DESCRIPTION:
North Twin Creek Trib H 1.0
END DESCRIPTION:
XS GIS Cut Line= 3
      2721276.00      6817961.03      2721376.00      6816761.00
      2721326.00      6816711.00
#Sta/Elev= 30
  3795.8  347.33  3825.9  344.51  3858.5  342.93  3926.3  341.70  3986.5  339.15
  4076.8  338.26  4127.0  336.94  4187.2  337.82  4257.4  337.28  4317.6  338.11
  4335.2  336.67  4340.2  337.48  4347.7  337.93  4397.9  337.17  4719.0  337.66
  4759.2  337.31  4779.2  336.67  4799.3  337.51  4879.6  337.59  4899.6  337.18
  4969.9  337.15  4988.0  334.82  4988.2  334.32  4991.7  334.32  4992.0  334.82
  5003.5  335.02  5028.3  337.42  5056.6  342.48  5067.2  345.33  5070.7  345.33
#Mann=3,-1,0
  3795.8    0.15       0  4988.0    0.05       0  4992.0    0.15       0
Bank Sta=4988,4992
Exp/Cntr=0.3,0.1

Chan Stop Cuts=-1