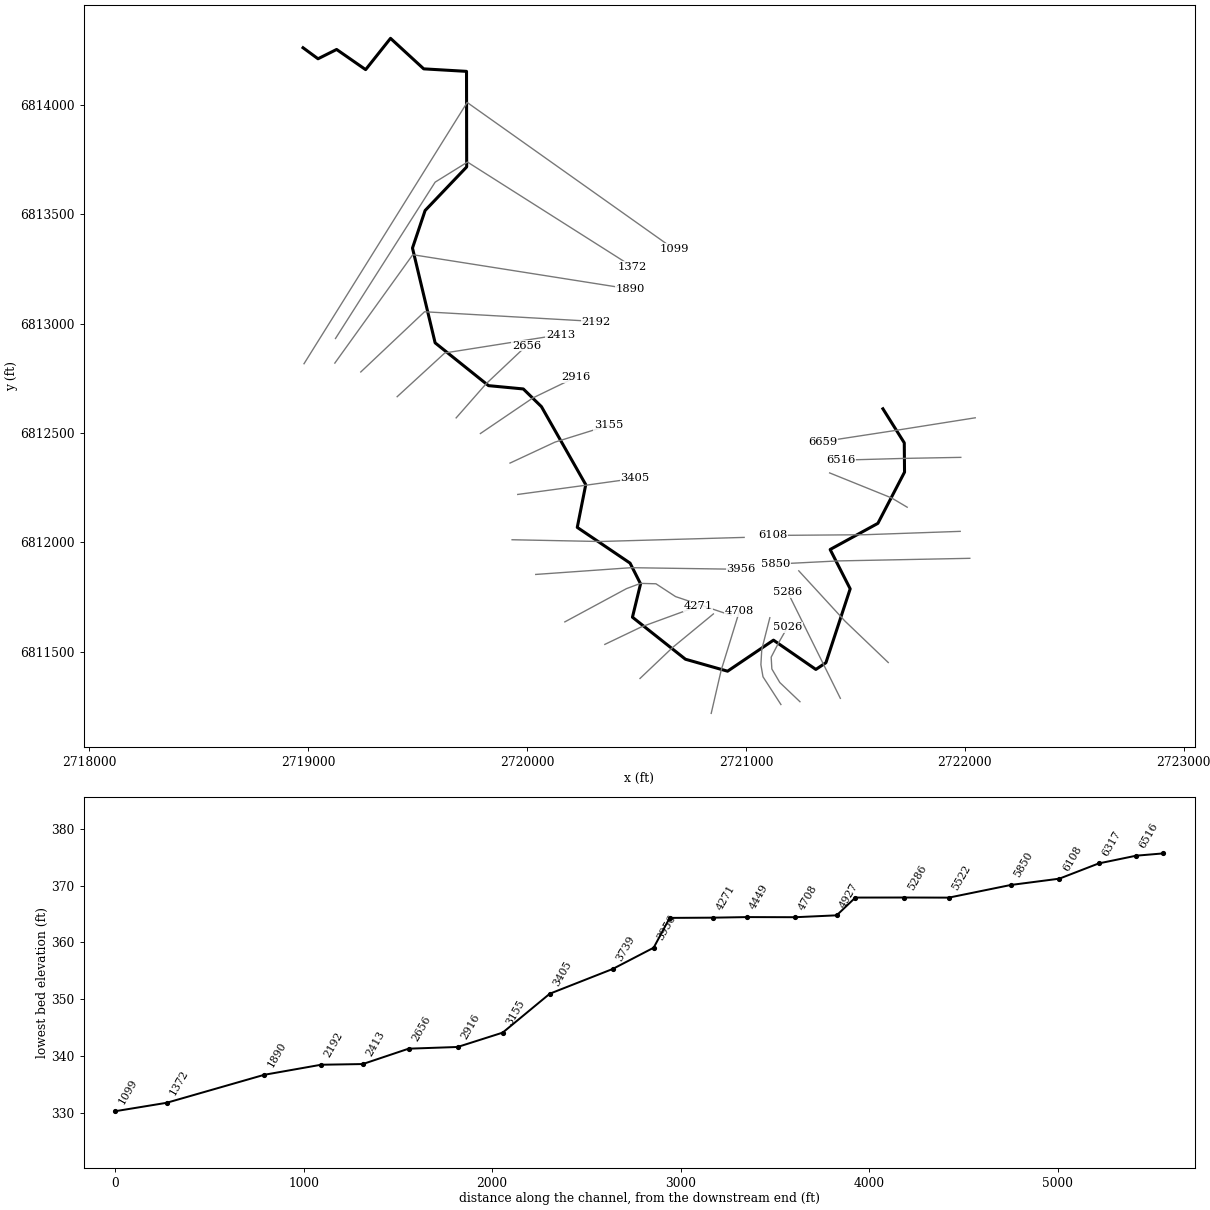
--- North Twin Creek Trib I.prj (project) ---

Proj Title=North Twin Creek Trib I Base Level Engineering
Current Plan=p01
Default Exp/Contr=0.3,0.1
English Units
Geom File=g01
Flow File=f01
Plan File=p01
BEGIN DESCRIPTION:
North Twin Creek Trib I
END DESCRIPTION:

--- North Twin Creek Trib I.p01 (plan) ---

Plan Title=Multiple Run
Short Identifier=Multiple
Geom File=g01
Flow File=f01
Subcritical Flow
K Sum by GR= 0
Std Step Tol= 0.01
Critical Tol= 0.01
Num of Std Step Trials= 20
Max Error Tol= 0.3
Flow Tol Ratio= 0.001
Split Flow NTrial= 30
Split Flow Tol= 0.02
Split Flow Ratio= 0.02
Log Output Level= 0
Friction Slope Method= 1
Unsteady Friction Slope Method= 2
Unsteady Bridges Friction Slope Method= 1
Parabolic Critical Depth
Global Vel Dist=  1 , 1 , 1
Global Log Level= 0
CheckData=True
Encroach Param= -1, 0, 0, 0
BEGIN DESCRIPTION:
Multiple Run
END DESCRIPTION:

--- North Twin Creek Trib I.f01 (steady flow) ---

Flow Title=Multiple
Number of Profiles=7
Profile Names=10-year,25-year,50-year,1pct_min,100-year,1pct_plu,500-year
River Rch & RM= North Twin Creek,Reach-1,6659
     337     433     507     295     589    1175     793
Boundary for River Rch & Prof#=North Twin Creek,Reach-1,1
Up Type=0
Dn Type=3
Dn Slope=0.005
Boundary for River Rch & Prof#=North Twin Creek,Reach-1,2
Up Type=0
Dn Type=3
Dn Slope=0.005
Boundary for River Rch & Prof#=North Twin Creek,Reach-1,3
Up Type=0
Dn Type=3
Dn Slope=0.005
Boundary for River Rch & Prof#=North Twin Creek,Reach-1,4
Up Type=0
Dn Type=3
Dn Slope=0.005
Boundary for River Rch & Prof#=North Twin Creek,Reach-1,5
Up Type=0
Dn Type=3
Dn Slope=0.005
Boundary for River Rch & Prof#=North Twin Creek,Reach-1,6
Up Type=0
Dn Type=3
Dn Slope=0.005
Boundary for River Rch & Prof#=North Twin Creek,Reach-1,7
Up Type=0
Dn Type=3
Dn Slope=0.005

--- North Twin Creek Trib I.g01 (geometry) ---

Geom Title=Existing Conditions

River Reach=North Twin Creek,Reach-1
Reach XY= 30
      2721626.00      6812611.00      2721723.64      6812455.47
      2721724.81      6812321.50      2721603.01      6812087.48
      2721384.83      6811968.00      2721476.43      6811788.21
      2721365.48      6811450.46      2721319.51      6811419.90
      2721125.92      6811553.70      2720916.16      6811411.91
      2720723.58      6811466.54      2720481.39      6811658.56
      2720518.48      6811811.04      2720470.52      6811905.71
      2720229.22      6812069.01      2720267.96      6812264.32
      2720065.48      6812620.83      2719982.69      6812701.71
      2719823.72      6812716.82      2719579.61      6812912.48
      2719476.15      6813345.58      2719533.86      6813517.17
      2719723.83      6813716.44      2719723.09      6814153.09
      2719527.47      6814164.54      2719375.79      6814304.02
      2719262.07      6814160.99      2719129.40      6814253.18
      2719044.49      6814210.62      2718976.00      6814261.00

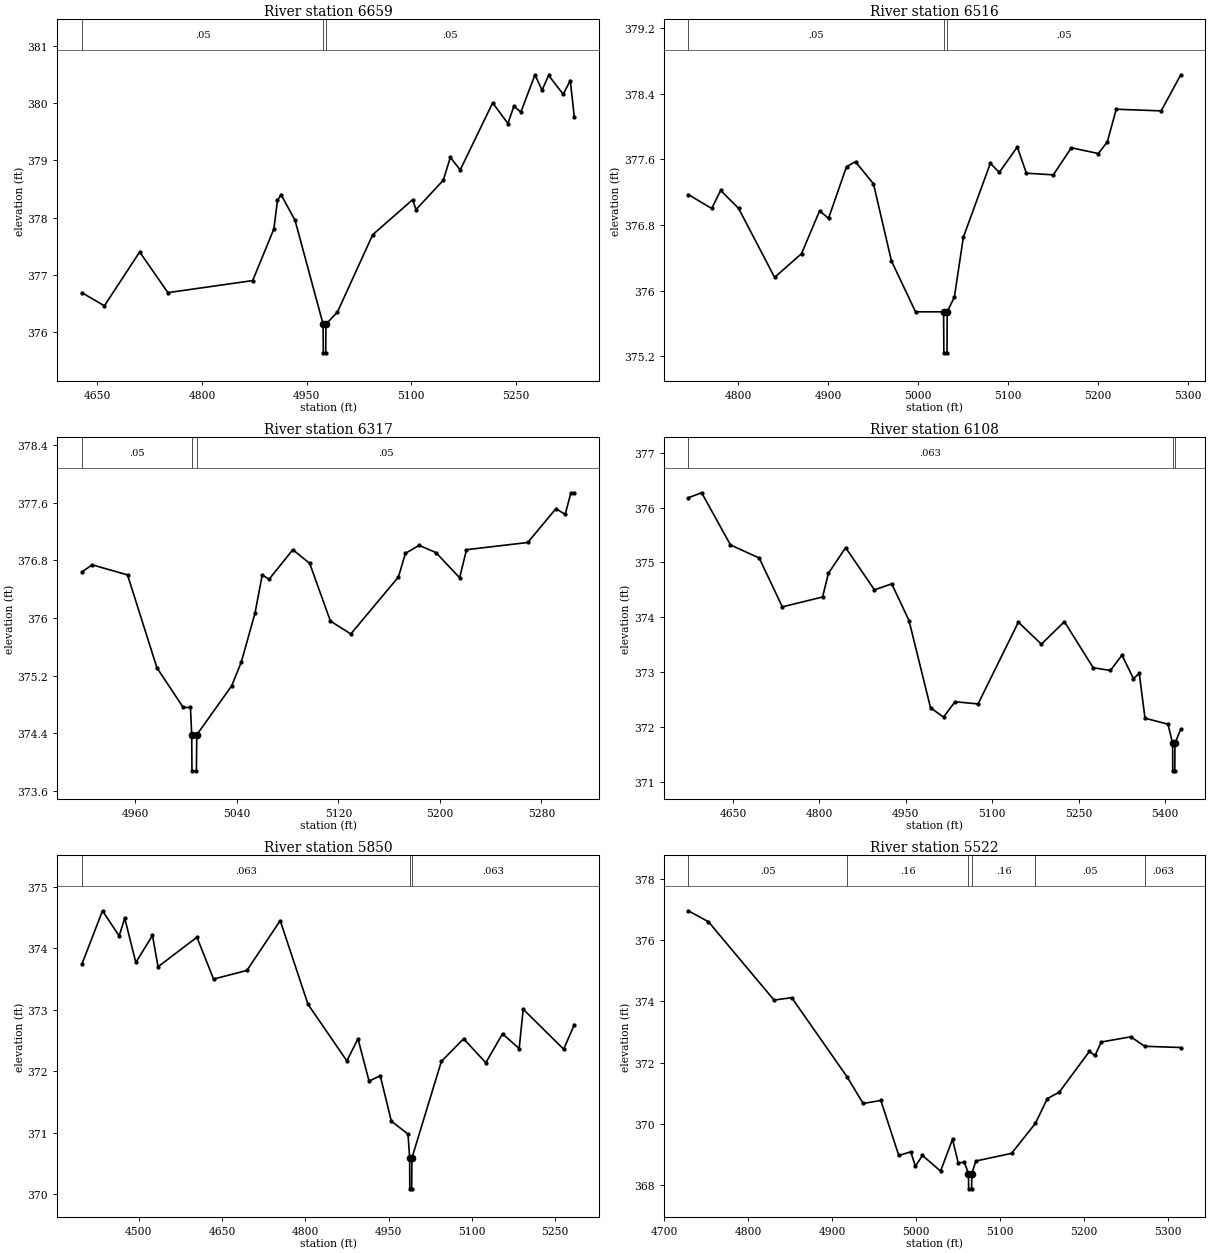
Type RM Length L Ch R = 1,6659,143,143,143
BEGIN DESCRIPTION:
North Twin Creek Trib I6659.366
END DESCRIPTION:
XS GIS Cut Line= 3
      2722047.92      6812569.90      2721676.00      6812511.00
      2721350.26      6812461.06
#Sta/Elev= 30
  4627.8  376.69  4660.1  376.46  4710.7  377.40  4751.2  376.69  4872.7  376.90
  4903.1  377.80  4908.3  378.30  4913.4  378.40  4933.5  377.95  4973.7  376.14
  4974.0  375.64  4977.5  375.64  4977.7  376.14  4994.2  376.35  5044.8  377.70
  5101.9  378.31  5107.0  378.14  5146.0  378.65  5156.1  379.05  5170.3  378.83
  5216.8  380.00  5238.7  379.64  5247.2  379.94  5257.3  379.84  5277.5  380.49
  5287.6  380.22  5297.0  380.48  5318.0  380.15  5328.1  380.39  5333.9  379.75
#Mann=3,-1,0
  4627.8    0.05       0  4973.7    0.05       0  4977.7    0.05       0
Bank Sta=4973.7,4977.7
Exp/Cntr=0.3,0.1

Type RM Length L Ch R = 1,6516,199,199,199
BEGIN DESCRIPTION:
North Twin Creek Trib I6516.39
END DESCRIPTION:
XS GIS Cut Line= 3
      2721981.96      6812389.06      2721727.38      6812384.43
      2721434.22      6812376.34
#Sta/Elev= 30
  4744.4  377.17  4770.4  377.00  4780.4  377.22  4800.4  377.00  4840.4  376.16
  4870.4  376.45  4890.4  376.97  4900.4  376.88  4920.4  377.51  4930.4  377.57
  4950.4  377.30  4970.4  376.36  4997.2  375.74  5028.4  375.74  5028.7  375.24
  5032.2  375.24  5032.4  375.74  5040.4  375.92  5050.4  376.65  5080.4  377.55
  5090.4  377.44  5110.4  377.75  5120.5  377.43  5150.5  377.41  5170.5  377.74
  5200.5  377.67  5210.5  377.81  5220.5  378.21  5270.5  378.19  5292.3  378.63
#Mann=3,-1,0
  4744.4    0.05       0  5028.4    0.05       0  5032.4    0.05       0
Bank Sta=5028.4,5032.4
Exp/Cntr=0.3,0.1

Type RM Length L Ch R = 1,6317,209,209,209
BEGIN DESCRIPTION:
North Twin Creek Trib I6317.54
END DESCRIPTION:
XS GIS Cut Line= 3
      2721736.93      6812161.28      2721665.41      6812203.75
      2721382.59      6812318.01
#Sta/Elev= 30
  4917.8  376.64  4925.9  376.74  4953.8  376.60  4977.0  375.31  4997.7  374.76
  5003.4  374.76  5004.4  374.38  5004.6  373.88  5008.1  373.88  5008.4  374.38
  5035.9  375.06  5043.5  375.39  5054.3  376.07  5060.0  376.60  5065.4  376.54
  5084.1  376.95  5097.4  376.76  5113.7  375.96  5129.8  375.78  5167.3  376.57
  5172.9  376.90  5183.7  377.01  5196.9  376.91  5215.6  376.56  5221.0  376.95
  5269.3  377.05  5291.5  377.52  5298.8  377.44  5303.3  377.74  5306.0  377.74
#Mann=3,-1,0
  4917.8    0.05       0  5004.4    0.05       0  5008.4    0.05       0
Bank Sta=5004.4,5008.4
Exp/Cntr=0.3,0.1

Type RM Length L Ch R = 1,6108,258,258,258
BEGIN DESCRIPTION:
North Twin Creek Trib I6107.86
END DESCRIPTION:
XS GIS Cut Line= 3
      2721979.16      6812050.91      2721542.90      6812035.53
      2721123.84      6812032.35
#Sta/Elev= 30
  4572.1  376.18  4595.3  376.27  4645.3  375.32  4695.3  375.08  4735.4  374.19
  4805.4  374.37  4815.4  374.80  4845.4  375.27  4895.5  374.50  4925.5  374.61
  4955.5  373.94  4992.9  372.35  5015.5  372.18  5035.5  372.46  5075.5  372.42
  5145.5  373.91  5185.5  373.51  5225.5  373.92  5275.5  373.08  5305.5  373.03
  5325.5  373.31  5345.5  372.88  5355.5  372.98  5365.5  372.16  5405.5  372.05
  5413.5  371.70  5413.8  371.20  5417.3  371.20  5417.5  371.70  5427.7  371.96
#Mann=3,-1,0
  4572.1   0.063       0  5413.5   0.063       0  5417.5   0.063       0
Bank Sta=5413.5,5417.5
Exp/Cntr=0.3,0.1

Type RM Length L Ch R = 1,5850,328,328,328
BEGIN DESCRIPTION:
North Twin Creek Trib I5849.78
END DESCRIPTION:
XS GIS Cut Line= 3
      2722023.15      6811927.70      2721420.70      6811915.80
      2721136.83      6811901.47
#Sta/Elev= 30
  4397.6  373.74  4434.8  374.61  4464.8  374.20  4474.8  374.49  4494.8  373.77
  4524.8  374.21  4534.8  373.70  4604.8  374.18  4634.8  373.50  4694.8  373.64
  4754.8  374.45  4804.8  373.09  4874.8  372.17  4894.8  372.53  4914.8  371.84
  4934.9  371.93  4954.9  371.19  4984.9  370.98  4987.9  370.59  4988.1  370.09
  4991.6  370.09  4991.9  370.59  5044.9  372.16  5085.0  372.53  5125.0  372.14
  5155.1  372.61  5185.1  372.37  5192.3  373.01  5265.2  372.36  5284.4  372.76
#Mann=3,-1,0
  4397.6   0.063       0  4987.9   0.063       0  4991.9   0.063       0
Bank Sta=4987.9,4991.9
Exp/Cntr=0.3,0.1

Type RM Length L Ch R = 1,5522,236,236,236
BEGIN DESCRIPTION:
North Twin Creek Trib I5520.71
END DESCRIPTION:
XS GIS Cut Line= 3
      2721650.44      6811451.46      2721452.95      6811640.45
      2721241.48      6811870.60
#Sta/Elev= 30
  4728.9  376.96  4752.9  376.60  4830.9  374.04  4851.9  374.12  4917.8  371.53
  4936.9  370.66  4957.9  370.76  4979.3  368.96  4993.5  369.08  4999.0  368.61
  5007.5  368.96  5029.0  368.45  5043.2  369.49  5050.0  368.72  5057.3  368.74
  5062.2  368.37  5062.4  367.87  5065.9  367.87  5066.2  368.37  5071.0  368.78
  5113.5  369.03  5141.8  370.01  5156.1  370.82  5170.2  371.03  5206.0  372.36
  5212.8  372.23  5220.2  372.67  5255.3  372.84  5271.9  372.53  5314.8  372.49
#Mann=6,-1,0
  4728.9    0.05       0  4917.8    0.16       0  5062.2    0.07       0
  5066.2    0.16       0  5141.8    0.05       0  5271.9   0.063       0
Bank Sta=5062.2,5066.2
Exp/Cntr=0.3,0.1

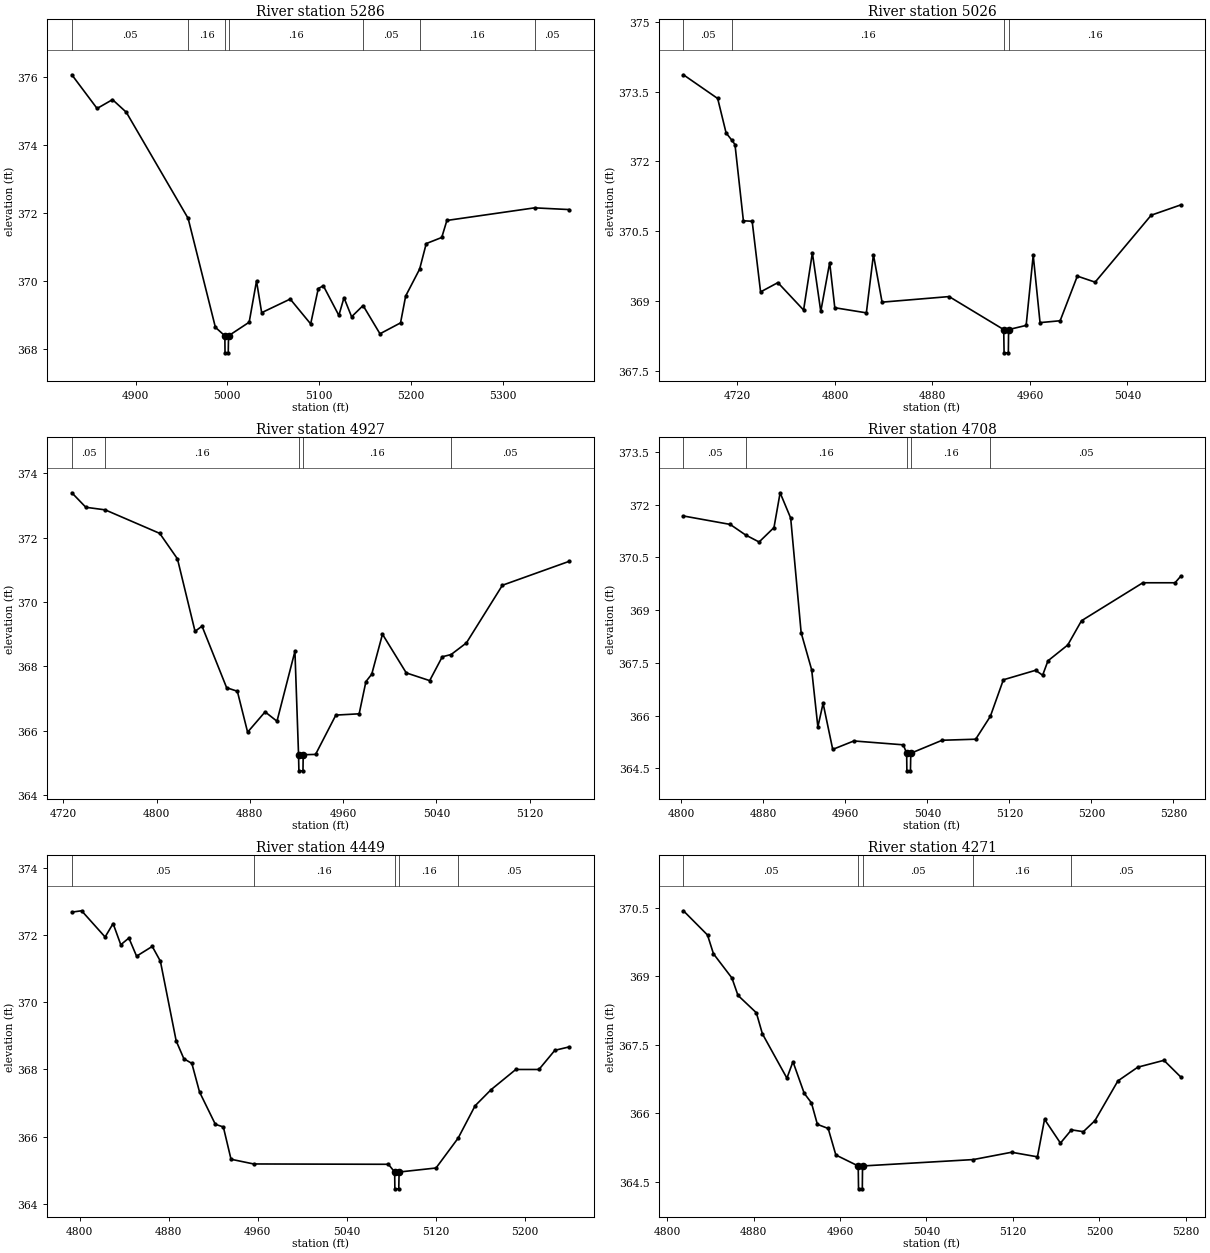
Type RM Length L Ch R = 1,5286,260,260,260
BEGIN DESCRIPTION:
North Twin Creek Trib I5285.57
END DESCRIPTION:
XS GIS Cut Line= 3
      2721431.47      6811287.91      2721355.00      6811442.06
      2721190.90      6811773.15
#Sta/Elev= 30
  4830.6  376.06  4858.1  375.07  4874.9  375.33  4889.9  374.96  4957.3  371.84
  4987.0  368.64  4997.3  368.39  4997.5  367.89  5001.0  367.89  5001.3  368.39
  5023.8  368.79  5031.8  370.00  5037.4  369.07  5068.5  369.47  5090.8  368.74
  5099.1  369.78  5104.6  369.86  5121.5  368.99  5127.1  369.51  5135.4  368.95
  5147.9  369.28  5166.3  368.45  5188.7  368.77  5194.3  369.56  5209.5  370.35
  5216.7  371.10  5233.6  371.28  5239.2  371.78  5334.7  372.15  5372.2  372.10
#Mann=7,-1,0
  4830.6    0.05       0  4957.3    0.16       0  4997.3    0.07       0
  5001.3    0.16       0  5147.9    0.05       0  5209.5    0.16       0
  5334.7    0.05       0
Bank Sta=4997.3,5001.3
Exp/Cntr=0.3,0.1

Type RM Length L Ch R = 1,5026,99,99,99
BEGIN DESCRIPTION:
North Twin Creek Trib I5025.86
END DESCRIPTION:
XS GIS Cut Line= 6
      2721246.93      6811272.37      2721154.84      6811360.06
      2721118.48      6811421.99      2721115.39      6811476.04
      2721148.81      6811540.67      2721189.41      6811611.94
#Sta/Elev= 30
  4675.7  373.86  4703.8  373.35  4710.7  372.61  4715.5  372.45  4718.0  372.36
  4724.9  370.72  4732.1  370.71  4739.0  369.19  4753.2  369.39  4774.3  368.80
  4781.5  370.03  4788.4  368.77  4795.7  369.82  4799.9  368.85  4825.8  368.74
  4831.6  369.99  4838.7  368.97  4893.7  369.09  4938.5  368.38  4938.8  367.88
  4942.3  367.88  4942.5  368.38  4956.9  368.47  4962.7  369.98  4968.3  368.53
  4984.8  368.57  4998.9  369.53  5013.5  369.40  5059.5  370.84  5083.6  371.06
#Mann=4,-1,0
  4675.7    0.05       0  4715.5    0.16       0  4938.5    0.07       0
  4942.5    0.16       0
Bank Sta=4938.5,4942.5
Exp/Cntr=0.3,0.1

Type RM Length L Ch R = 1,4927,219,219,219
BEGIN DESCRIPTION:
North Twin Creek Trib I4926.81
END DESCRIPTION:
XS GIS Cut Line= 5
      2721159.90      6811259.56      2721077.95      6811386.42
      2721068.40      6811441.40      2721072.31      6811510.76
      2721109.28      6811656.33
#Sta/Elev= 30
  4727.3  373.39  4739.3  372.94  4755.9  372.86  4802.7  372.13  4817.9  371.34
  4833.0  369.09  4839.0  369.25  4860.1  367.34  4869.3  367.23  4878.1  365.96
  4893.1  366.59  4903.3  366.30  4918.7  368.47  4921.8  365.26  4922.1  364.76
  4925.6  364.76  4925.8  365.26  4936.4  365.27  4953.8  366.49  4973.8  366.53
  4979.6  367.53  4984.6  367.76  4993.8  369.00  5014.2  367.80  5034.3  367.56
  5045.1  368.30  5052.7  368.37  5065.8  368.73  5096.7  370.52  5153.8  371.26
#Mann=5,-1,0
  4727.3    0.05       0  4755.9    0.16       0  4921.8    0.07       0
  4925.8    0.16       0  5052.7    0.05       0
Bank Sta=4921.8,4925.8
Exp/Cntr=0.3,0.1

Type RM Length L Ch R = 1,4708,259,259,259
BEGIN DESCRIPTION:
North Twin Creek Trib I4707.68
END DESCRIPTION:
XS GIS Cut Line= 3
      2720841.33      6811219.10      2720886.76      6811415.84
      2720970.16      6811686.14
#Sta/Elev= 30
  4802.1  371.68  4847.7  371.44  4862.7  371.14  4875.9  370.94  4890.4  371.35
  4896.4  372.34  4906.7  371.62  4916.9  368.36  4927.2  367.30  4933.2  365.68
  4938.3  366.35  4947.7  365.04  4968.3  365.28  5016.5  365.17  5019.8  364.93
  5020.0  364.43  5023.5  364.43  5023.8  364.93  5054.4  365.30  5087.1  365.33
  5101.4  365.98  5114.1  367.02  5145.5  367.29  5152.4  367.15  5157.6  367.56
  5176.9  368.01  5190.3  368.70  5250.1  369.78  5281.5  369.78  5286.9  369.96
#Mann=5,-1,0
  4802.1    0.05       0  4862.7    0.16       0  5019.8    0.07       0
  5023.8    0.16       0  5101.4    0.05       0
Bank Sta=5019.8,5023.8
Exp/Cntr=0.3,0.1

Type RM Length L Ch R = 1,4449,178,178,178
BEGIN DESCRIPTION:
North Twin Creek Trib I4448.91
END DESCRIPTION:
XS GIS Cut Line= 3
      2720515.92      6811378.68      2720665.53      6811520.68
      2720851.30      6811673.63
#Sta/Elev= 30
  4793.0  372.68  4801.8  372.72  4822.9  371.94  4830.1  372.34  4837.0  371.71
  4844.3  371.91  4851.2  371.37  4865.3  371.66  4872.6  371.22  4886.8  368.85
  4893.7  368.32  4900.9  368.18  4907.8  367.33  4922.0  366.37  4929.2  366.29
  4936.1  365.33  4956.4  365.19  5077.6  365.18  5083.2  364.95  5083.4  364.45
  5086.9  364.45  5087.2  364.95  5120.4  365.07  5140.3  365.96  5155.5  366.92
  5169.9  367.40  5192.1  368.00  5212.9  368.00  5227.2  368.57  5239.9  368.67
#Mann=5,-1,0
  4793.0    0.05       0  4956.4    0.16       0  5083.2    0.07       0
  5087.2    0.16       0  5140.3    0.05       0
Bank Sta=5083.2,5087.2
Exp/Cntr=0.3,0.1

Type RM Length L Ch R = 1,4271,230,230,230
BEGIN DESCRIPTION:
Mapping XS 5d37c4b0
END DESCRIPTION:
XS GIS Cut Line= 3
      2720355.16      6811534.35      2720522.44      6811614.44
      2720780.49      6811708.74
#Sta/Elev= 30
  4815.0  370.43  4837.3  369.90  4842.8  369.49  4859.9  368.96  4865.5  368.58
  4882.5  368.20  4888.1  367.74  4910.8  366.77  4916.4  367.13  4926.8  366.44
  4933.5  366.23  4939.0  365.76  4949.0  365.67  4956.1  365.09  4976.8  364.85
  4977.1  364.35  4980.6  364.35  4980.8  364.85  5083.4  364.99  5118.8  365.15
  5142.7  365.05  5149.3  365.87  5164.0  365.35  5174.2  365.64  5185.2  365.60
  5195.9  365.84  5217.2  366.71  5235.6  367.01  5259.8  367.16  5275.2  366.80
#Mann=5,-1,0
  4815.0    0.05       0  4976.8    0.05       0  4980.8    0.05       0
  5083.4    0.16       0  5174.2    0.05       0
Bank Sta=4976.8,4980.8
Exp/Cntr=0.3,0.1

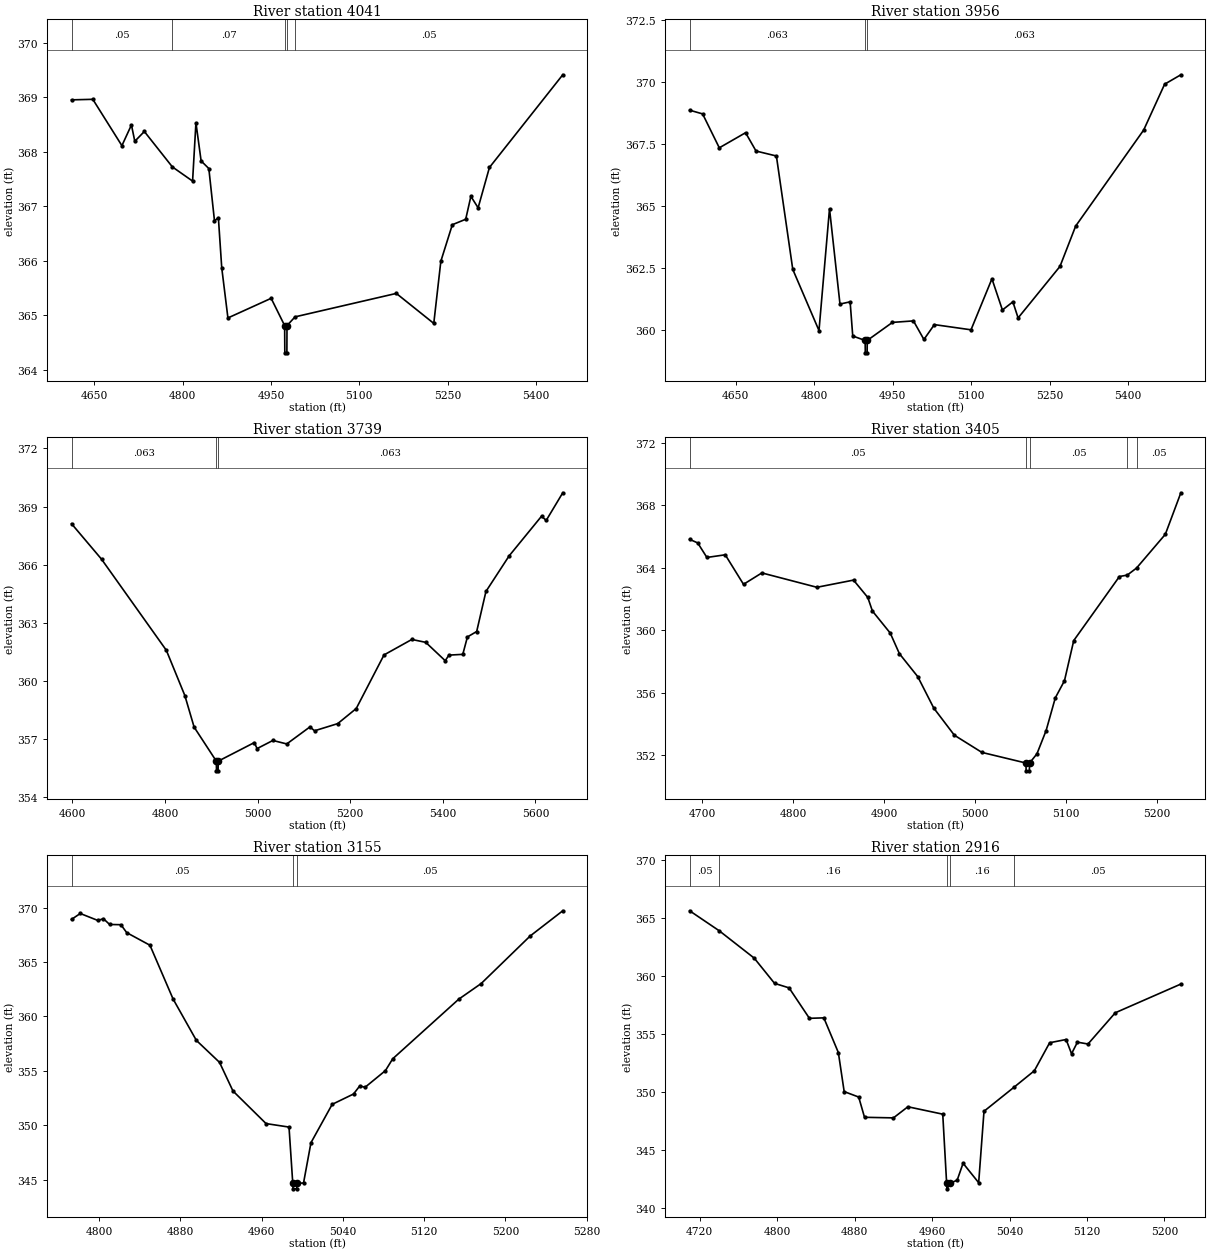
Type RM Length L Ch R = 1,4041,85,85,85
BEGIN DESCRIPTION:
North Twin Creek Trib I4041.49
END DESCRIPTION:
XS GIS Cut Line= 6
      2720172.38      6811637.19      2720454.07      6811789.16
      2720518.21      6811813.16      2720588.83      6811811.34
      2720678.40      6811752.80      2720932.19      6811667.30
#Sta/Elev= 30
  4611.5  368.95  4647.6  368.96  4697.0  368.11  4713.2  368.49  4718.9  368.19
  4735.1  368.37  4782.7  367.72  4817.0  367.46  4822.7  368.53  4831.5  367.83
  4844.6  367.69  4854.2  366.73  4860.8  366.79  4866.5  365.87  4877.0  364.95
  4950.4  365.31  4973.3  364.81  4973.6  364.31  4977.1  364.31  4977.3  364.81
  4991.0  364.97  5162.9  365.40  5226.5  364.85  5238.5  365.99  5258.0  366.66
  5280.7  366.76  5289.5  367.18  5301.8  366.97  5321.0  367.71  5445.5  369.41
#Mann=5,-1,0
  4611.5    0.05       0  4782.7    0.07       0  4973.3    0.05       0
  4977.3    0.07       0  4991.0    0.05       0
Bank Sta=4973.3,4977.3
Exp/Cntr=0.3,0.1

Type RM Length L Ch R = 1,3956,217,217,217
BEGIN DESCRIPTION:
North Twin Creek Trib I3956.21
END DESCRIPTION:
XS GIS Cut Line= 3
      2720039.41      6811854.02      2720475.37      6811884.90
      2720976.96      6811877.48
#Sta/Elev= 30
  4561.9  368.87  4586.7  368.72  4618.6  367.35  4668.8  367.96  4688.8  367.22
  4727.7  367.02  4759.0  362.44  4809.1  359.97  4829.2  364.89  4849.2  361.04
  4868.6  361.13  4873.6  359.75  4897.3  359.57  4897.6  359.07  4901.1  359.07
  4901.3  359.57  4949.5  360.30  4989.6  360.36  5009.6  359.61  5029.6  360.21
  5099.6  360.00  5139.6  362.06  5159.6  360.80  5179.6  361.13  5189.6  360.48
  5269.6  362.56  5299.6  364.19  5429.6  368.07  5469.6  369.92  5500.6  370.30
#Mann=3,-1,0
  4561.9   0.063       0  4897.3   0.063       0  4901.3   0.063       0
Bank Sta=4897.3,4901.3
Exp/Cntr=0.3,0.1

Type RM Length L Ch R = 1,3739,334,334,334
BEGIN DESCRIPTION:
North Twin Creek Trib I3738.56
END DESCRIPTION:
XS GIS Cut Line= 3
      2719931.34      6812012.57      2720332.92      6812004.56
      2720991.79      6812023.29
#Sta/Elev= 30
  4598.3  368.11  4663.0  366.28  4803.0  361.57  4843.0  359.23  4863.0  357.60
  4911.0  355.84  4911.3  355.34  4914.8  355.34  4915.0  355.84  4993.0  356.80
  4999.0  356.49  5033.1  356.91  5063.1  356.73  5113.1  357.61  5123.1  357.41
  5173.1  357.78  5213.1  358.56  5273.1  361.33  5333.2  362.13  5363.2  361.98
  5405.3  361.03  5413.2  361.32  5443.2  361.36  5453.2  362.26  5473.2  362.54
  5493.2  364.61  5543.3  366.45  5613.3  368.50  5623.3  368.28  5659.1  369.71
#Mann=3,-1,0
  4598.3   0.063       0  4911.0   0.063       0  4915.0   0.063       0
Bank Sta=4911,4915
Exp/Cntr=0.3,0.1

Type RM Length L Ch R = 1,3405,250,250,250
BEGIN DESCRIPTION:
North Twin Creek Trib I3404.52
END DESCRIPTION:
XS GIS Cut Line= 3
      2719957.20      6812219.59      2720269.44      6812261.90
      2720492.91      6812292.84
#Sta/Elev= 30
  4686.0  365.81  4694.9  365.58  4705.0  364.65  4725.2  364.82  4745.3  362.93
  4765.5  363.66  4826.1  362.74  4866.4  363.20  4882.1  362.09  4887.2  361.22
  4906.8  359.81  4916.9  358.49  4937.1  357.02  4954.7  355.01  4977.4  353.27
  5007.7  352.17  5056.2  351.49  5056.4  350.99  5059.9  350.99  5060.2  351.49
  5068.3  352.08  5078.4  353.57  5088.5  355.66  5098.6  356.76  5108.8  359.33
  5159.1  363.43  5167.7  363.52  5177.9  363.97  5209.6  366.13  5226.7  368.79
#Mann=5,-1,0
  4686.0    0.05       0  5056.2    0.05       0  5060.2    0.05       0
  5167.7    0.07       0  5177.9    0.05       0
Bank Sta=5056.2,5060.2
Exp/Cntr=0.3,0.1

Type RM Length L Ch R = 1,3155,239,239,239
BEGIN DESCRIPTION:
North Twin Creek Trib I3155.26
END DESCRIPTION:
XS GIS Cut Line= 3
      2719921.97      6812362.97      2720127.04      6812458.62
      2720372.69      6812535.23
#Sta/Elev= 30
  4772.9  368.93  4781.5  369.47  4798.8  368.83  4804.3  368.99  4810.4  368.46
  4821.5  368.44  4827.2  367.71  4850.1  366.55  4872.9  361.60  4895.8  357.80
  4918.6  355.78  4931.8  353.15  4964.4  350.15  4987.0  349.83  4990.7  344.65
  4991.0  344.15  4994.5  344.15  4994.7  344.65  5001.3  344.69  5008.6  348.39
  5029.5  351.92  5050.5  352.87  5056.6  353.61  5061.9  353.49  5081.9  355.02
  5089.1  356.11  5154.1  361.59  5176.2  363.03  5224.4  367.40  5256.5  369.72
#Mann=3,-1,0
  4772.9    0.05       0  4990.7    0.05       0  4994.7    0.05       0
Bank Sta=4990.7,4994.7
Exp/Cntr=0.3,0.1

Type RM Length L Ch R = 1,2916,260,260,260
BEGIN DESCRIPTION:
North Twin Creek Trib I2916.01
END DESCRIPTION:
XS GIS Cut Line= 3
      2719786.55      6812498.01      2720026.51      6812660.75
      2720222.18      6812755.41
#Sta/Elev= 30
  4709.6  365.65  4740.2  363.92  4776.3  361.56  4797.3  359.38  4812.3  358.99
  4833.3  356.36  4848.2  356.40  4863.2  353.40  4869.2  350.03  4884.2  349.56
  4890.2  347.81  4920.1  347.76  4935.0  348.72  4971.0  348.08  4975.0  342.13
  4975.3  341.63  4979.0  342.13  4985.9  342.38  4992.0  343.84  5008.1  342.16
  5013.6  348.33  5044.5  350.40  5065.6  351.83  5081.4  354.25  5098.4  354.53
  5104.0  353.30  5110.1  354.30  5121.0  354.14  5149.2  356.84  5216.9  359.32
#Mann=5,-1,0
  4709.6    0.05       0  4740.2    0.16       0  4975.0    0.07       0
  4979.0    0.16       0  5044.5    0.05       0
Bank Sta=4975,4979
Exp/Cntr=0.3,0.1

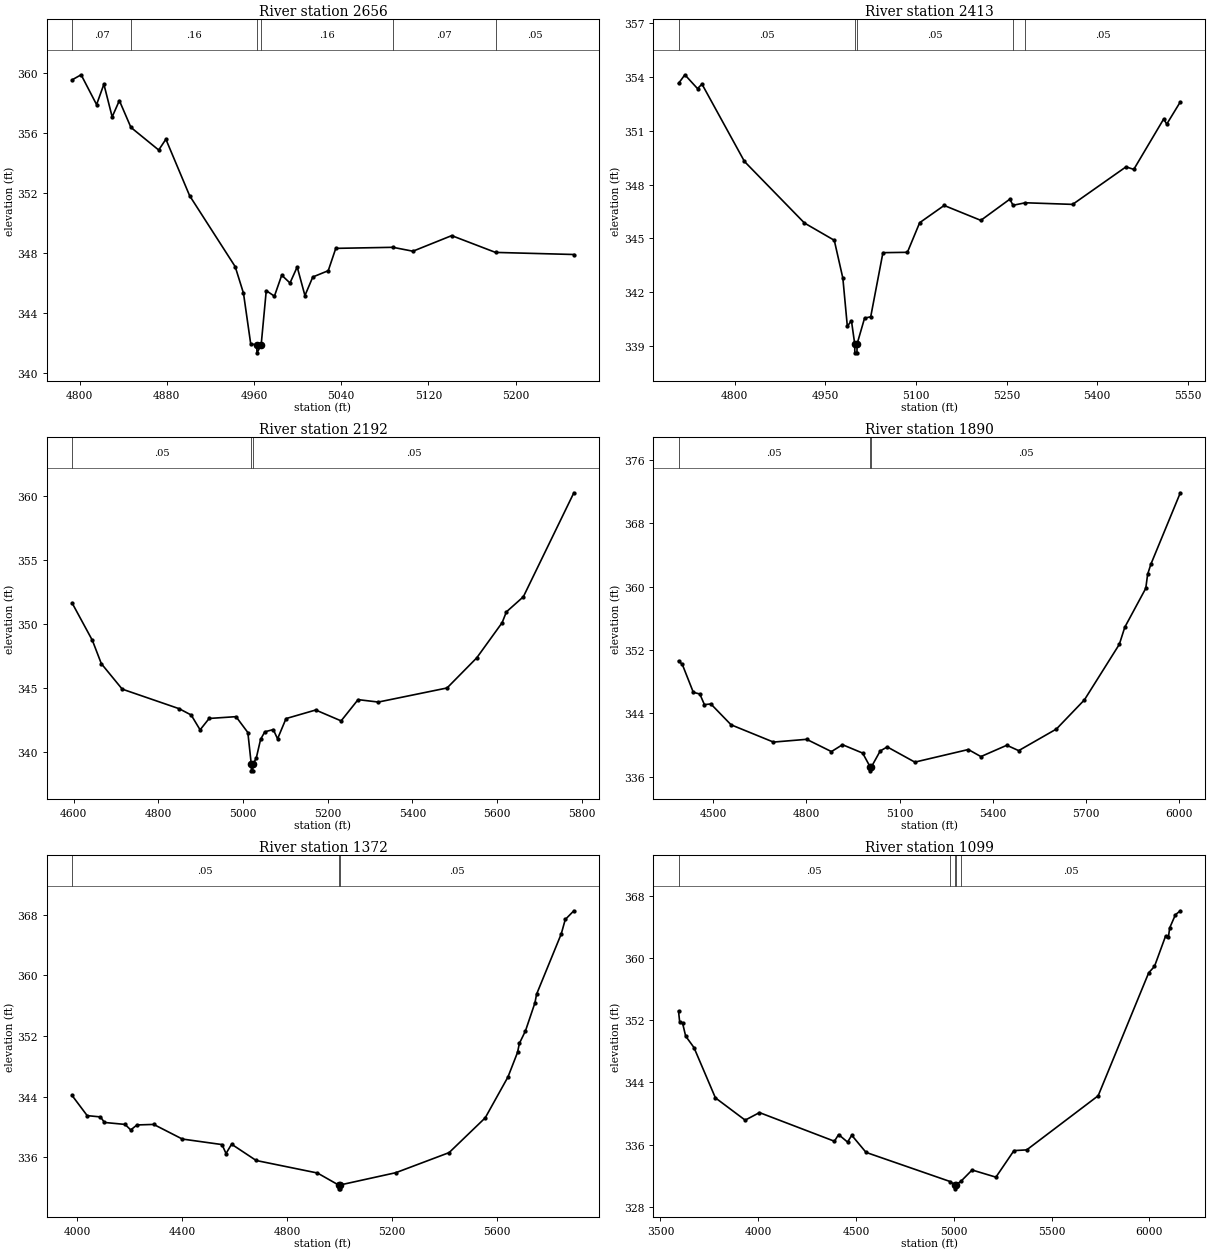
Type RM Length L Ch R = 1,2656,243,243,243
BEGIN DESCRIPTION:
North Twin Creek Trib I2656.07
END DESCRIPTION:
XS GIS Cut Line= 3
      2719675.75      6812569.50      2719813.28      6812725.95
      2719996.71      6812899.02
#Sta/Elev= 30
  4793.0  359.54  4801.3  359.88  4815.5  357.89  4822.2  359.25  4829.8  357.07
  4836.4  358.16  4847.0  356.37  4872.5  354.86  4879.1  355.58  4900.9  351.81
  4942.7  347.08  4950.3  345.31  4956.9  341.95  4962.5  341.83  4962.7  341.33
  4966.5  341.83  4971.2  345.48  4978.7  345.11  4985.4  346.51  4993.0  345.99
  4999.6  347.06  5006.7  345.15  5013.9  346.39  5028.1  346.81  5035.0  348.30
  5087.4  348.37  5105.8  348.11  5141.4  349.15  5181.6  348.03  5253.5  347.89
#Mann=6,-1,0
  4793.0    0.07       0  4847.0    0.16       0  4962.5    0.07       0
  4966.5    0.16       0  5087.4    0.07       0  5181.6    0.05       0
Bank Sta=4962.5,4966.5
Exp/Cntr=0.3,0.1

Type RM Length L Ch R = 1,2413,221,221,221
BEGIN DESCRIPTION:
North Twin Creek Trib I2412.91
END DESCRIPTION:
XS GIS Cut Line= 3
      2719406.11      6812666.32      2719623.84      6812866.16
      2720152.04      6812949.70
#Sta/Elev= 30
  4707.1  353.64  4717.6  354.12  4738.5  353.35  4745.9  353.60  4816.2  349.29
  4915.5  345.86  4964.8  344.90  4979.0  342.79  4986.4  340.11  4993.2  340.42
  4998.6  339.13  4998.8  338.63  5002.3  338.63  5002.6  339.13  5014.9  340.56
  5025.1  340.64  5045.3  344.21  5085.8  344.23  5106.1  345.88  5146.6  346.84
  5207.3  346.01  5255.3  347.19  5260.6  346.85  5280.9  346.99  5359.2  346.90
  5447.5  348.99  5460.4  348.85  5509.9  351.66  5514.9  351.37  5537.4  352.61
#Mann=5,-1,0
  4707.1    0.05       0  4998.6    0.05       0  5002.6    0.05       0
  5260.6    0.07       0  5280.9    0.05       0
Bank Sta=4998.6,5002.6
Exp/Cntr=0.3,0.1

Type RM Length L Ch R = 1,2192,302,302,302
BEGIN DESCRIPTION:
North Twin Creek Trib I2192.07
END DESCRIPTION:
XS GIS Cut Line= 3
      2719239.88      6812779.33      2719531.26      6813054.51
      2720315.21      6813009.90
#Sta/Elev= 30
  4595.8  351.62  4643.9  348.69  4664.9  346.88  4714.3  344.89  4849.0  343.36
  4877.3  342.87  4898.4  341.71  4919.8  342.60  4983.3  342.74  5011.3  341.50
  5019.4  339.01  5019.6  338.51  5023.1  338.51  5023.4  339.01  5031.4  339.54
  5041.4  340.97  5051.4  341.56  5071.4  341.73  5081.5  341.01  5101.5  342.59
  5171.6  343.26  5231.7  342.41  5271.8  344.07  5319.6  343.88  5482.1  344.98
  5552.2  347.33  5612.3  350.08  5622.3  350.92  5662.4  352.10  5781.8  360.22
#Mann=3,-1,0
  4595.8    0.05       0  5019.4    0.05       0  5023.4    0.05       0
Bank Sta=5019.4,5023.4
Exp/Cntr=0.3,0.1

Type RM Length L Ch R = 1,1890,518,518,518
BEGIN DESCRIPTION:
North Twin Creek Trib I1890.23
END DESCRIPTION:
XS GIS Cut Line= 3
      2719121.36      6812819.94      2719477.44      6813315.20
      2720469.87      6813158.51
#Sta/Elev= 30
  4388.7  350.61  4400.7  350.19  4436.3  346.65  4457.2  346.44  4471.9  345.10
  4492.8  345.18  4557.8  342.55  4694.1  340.37  4800.9  340.72  4880.7  339.17
  4916.3  340.04  4981.2  338.98  5005.3  337.24  5005.6  336.74  5009.3  337.24
  5037.7  339.25  5060.3  339.76  5149.1  337.84  5321.2  339.43  5361.7  338.54
  5445.1  339.97  5483.2  339.29  5604.7  342.02  5694.8  345.70  5807.1  352.71
  5824.7  354.87  5892.2  359.78  5898.2  361.55  5908.4  362.80  6003.4  371.84
#Mann=3,-1,0
  4388.7    0.05       0  5005.3    0.05       0  5009.3    0.05       0
Bank Sta=5005.3,5009.3
Exp/Cntr=0.3,0.1

Type RM Length L Ch R = 1,1372,273,273,273
BEGIN DESCRIPTION:
Mapping XS 8a388d1d
END DESCRIPTION:
XS GIS Cut Line= 4
      2719124.29      6812932.32      2719579.71      6813646.83
      2719727.56      6813738.57      2720481.46      6813260.16
#Sta/Elev= 30
  3980.1  344.14  4037.8  341.48  4088.4  341.31  4103.6  340.58  4182.4  340.32
  4203.9  339.59  4227.6  340.25  4291.5  340.32  4400.7  338.39  4552.2  337.66
  4567.4  336.48  4588.6  337.71  4682.5  335.56  4916.0  333.91  4997.0  332.32
  4997.2  331.82  5000.7  331.82  5001.0  332.32  5215.1  333.95  5418.4  336.60
  5556.2  341.19  5642.9  346.58  5679.3  349.81  5686.5  351.01  5709.8  352.67
  5745.7  356.35  5752.2  357.51  5846.2  365.46  5861.5  367.36  5894.3  368.51
#Mann=3,-1,0
  3980.1    0.05       0  4997.0    0.05       0  5001.0    0.05       0
Bank Sta=4997,5001
Exp/Cntr=0.3,0.1

Type RM Length L Ch R = 1,1099,0,0,0
BEGIN DESCRIPTION:
North Twin Creek Trib I1099.023
END DESCRIPTION:
XS GIS Cut Line= 3
      2718980.50      6812817.05      2719726.01      6814011.01
      2720670.96      6813341.13
#Sta/Elev= 30
  3592.4  353.14  3598.1  351.80  3613.5  351.57  3628.8  349.95  3671.3  348.48
  3781.0  342.02  3933.1  339.16  4006.3  340.13  4389.6  336.45  4410.8  337.31
  4456.8  336.34  4478.1  337.22  4551.2  335.02  4980.9  331.28  5005.4  330.84
  5005.6  330.34  5009.4  330.84  5037.2  331.33  5093.5  332.76  5215.3  331.84
  5307.6  335.25  5372.8  335.34  5738.2  342.29  5996.6  358.08  6026.2  358.90
  6082.8  362.79  6097.5  362.65  6103.7  363.83  6133.2  365.53  6158.3  366.04
#Mann=5,-1,0
  3592.4    0.05       0  4980.9    0.07       0  5005.4    0.07       0
  5009.4    0.07       0  5037.2    0.05       0
Bank Sta=5005.4,5009.4
Exp/Cntr=0.3,0.1

Chan Stop Cuts=-1