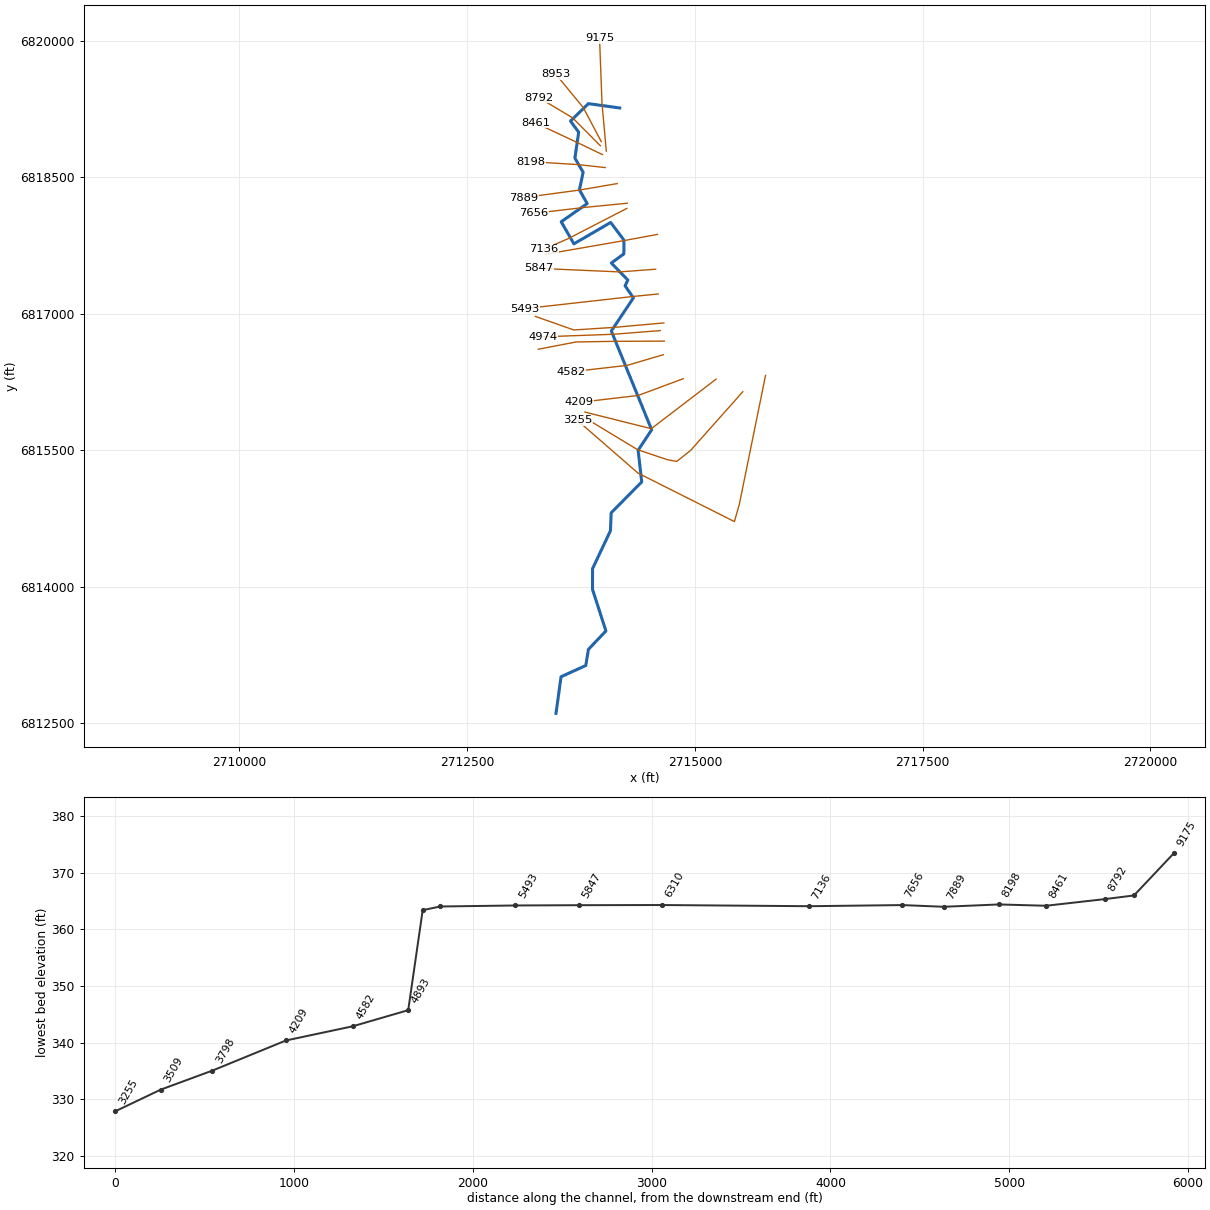
--- North Twin Creek Trib J.prj (project) ---

Proj Title=North Twin Creek Trib J Base Level Engineering
Current Plan=p01
Default Exp/Contr=0.3,0.1
English Units
Geom File=g01
Flow File=f01
Plan File=p01
BEGIN DESCRIPTION:
North Twin Creek Trib J
END DESCRIPTION:

--- North Twin Creek Trib J.p01 (plan) ---

Plan Title=Multiple Run
Short Identifier=Multiple
Geom File=g01
Flow File=f01
Subcritical Flow
K Sum by GR= 0
Std Step Tol= 0.01
Critical Tol= 0.01
Num of Std Step Trials= 20
Max Error Tol= 0.3
Flow Tol Ratio= 0.001
Split Flow NTrial= 30
Split Flow Tol= 0.02
Split Flow Ratio= 0.02
Log Output Level= 0
Friction Slope Method= 1
Unsteady Friction Slope Method= 2
Unsteady Bridges Friction Slope Method= 1
Parabolic Critical Depth
Global Vel Dist=  1 , 1 , 1
Global Log Level= 0
CheckData=True
Encroach Param= -1, 0, 0, 0
BEGIN DESCRIPTION:
Multiple Run
END DESCRIPTION:

--- North Twin Creek Trib J.f01 (steady flow) ---

Flow Title=Multiple
Number of Profiles=7
Profile Names=10-year,25-year,50-year,1pct_min,100-year,1pct_plu,500-year
River Rch & RM= North Twin Creek,Reach-1,9175
     367     476     560     328     654    1304     889
Boundary for River Rch & Prof#=North Twin Creek,Reach-1,1
Up Type=0
Dn Type=3
Dn Slope=0.005
Boundary for River Rch & Prof#=North Twin Creek,Reach-1,2
Up Type=0
Dn Type=3
Dn Slope=0.005
Boundary for River Rch & Prof#=North Twin Creek,Reach-1,3
Up Type=0
Dn Type=3
Dn Slope=0.005
Boundary for River Rch & Prof#=North Twin Creek,Reach-1,4
Up Type=0
Dn Type=3
Dn Slope=0.005
Boundary for River Rch & Prof#=North Twin Creek,Reach-1,5
Up Type=0
Dn Type=3
Dn Slope=0.005
Boundary for River Rch & Prof#=North Twin Creek,Reach-1,6
Up Type=0
Dn Type=3
Dn Slope=0.005
Boundary for River Rch & Prof#=North Twin Creek,Reach-1,7
Up Type=0
Dn Type=3
Dn Slope=0.005

--- North Twin Creek Trib J.g01 (geometry) ---

Geom Title=Existing Conditions

River Reach=North Twin Creek,Reach-1
Reach XY= 30
      2714176.00      6819261.00      2713831.85      6819308.94
      2713635.10      6819117.71      2713725.08      6818995.06
      2713683.53      6818710.99      2713773.77      6818555.07
      2713733.53      6818360.99      2713818.72      6818210.90
      2713533.22      6818011.31      2713672.58      6817768.76
      2714076.10      6818003.72      2714222.26      6817809.44
      2714220.65      6817658.30      2714083.51      6817557.85
      2714264.76      6817371.00      2714234.02      6817307.67
      2714325.96      6817175.06      2714083.33      6816811.10
      2714526.04      6815726.34      2714377.36      6815501.35
      2714416.99      6815153.98      2714081.45      6814813.47
      2714073.76      6814616.93      2713877.21      6814200.50
      2713877.02      6813971.86      2714023.92      6813516.48
      2713831.47      6813313.45      2713803.35      6813136.97
      2713531.46      6813013.47      2713476.00      6812611.00

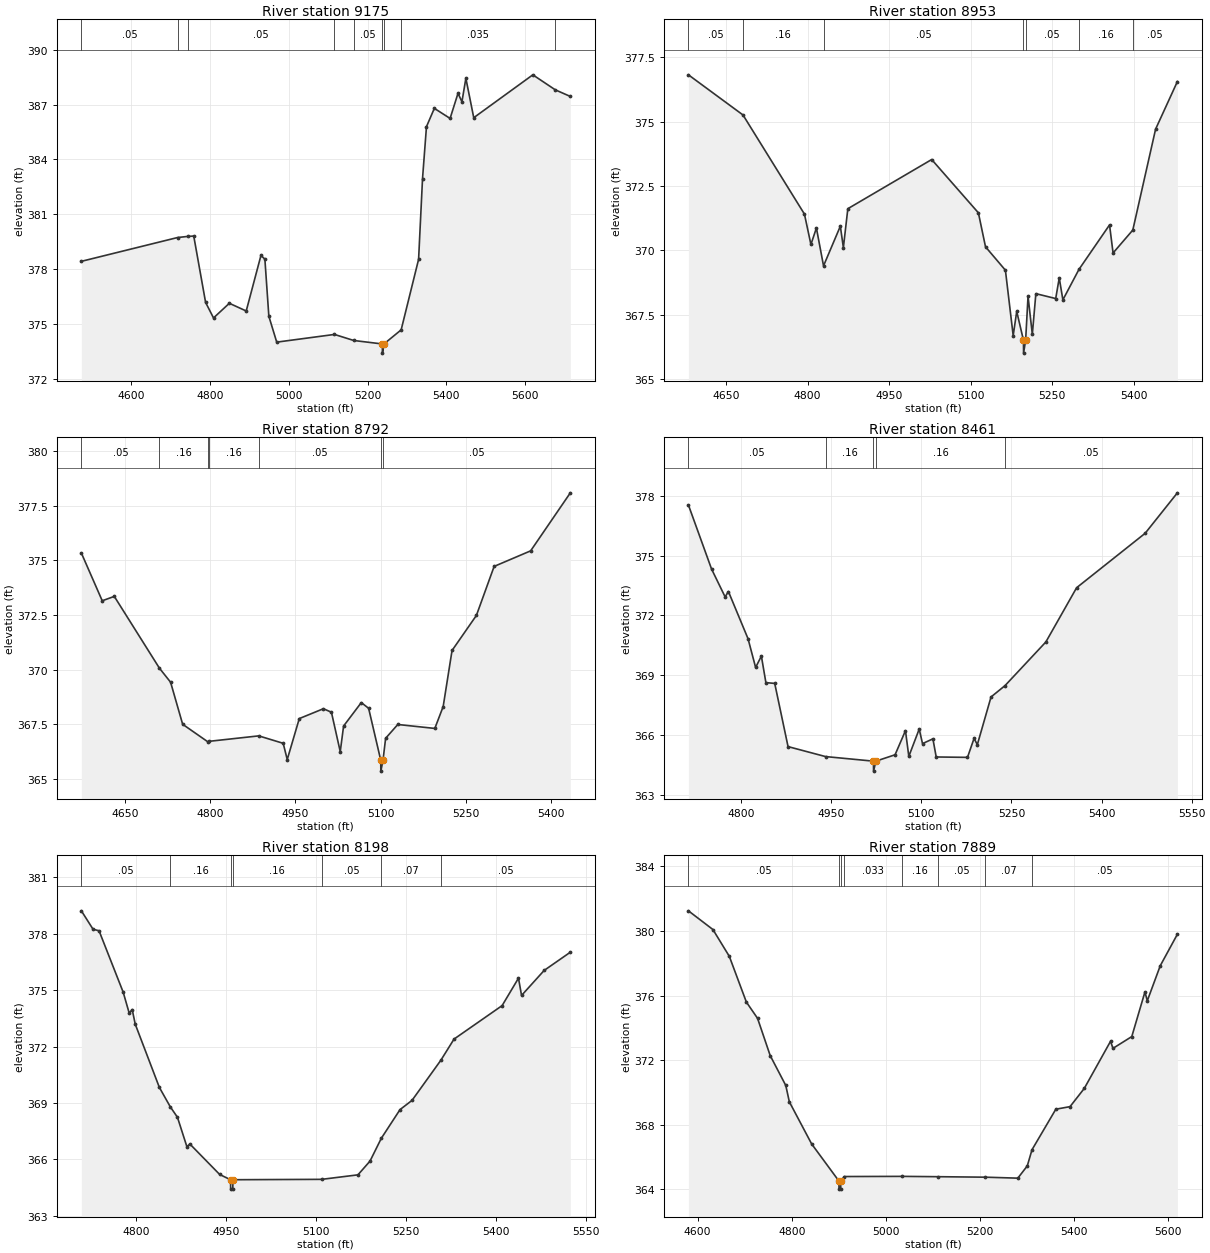
Type RM Length L Ch R = 1,9175,222,222,222
BEGIN DESCRIPTION:
North Twin Creek Trib J9175.356
END DESCRIPTION:
XS GIS Cut Line= 3
      2714028.05      6818786.64      2713981.18      6819311.45
      2713954.00      6820026.23
#Sta/Elev= 30
  4473.1  378.44  4717.6  379.74  4743.4  379.80  4758.6  379.82  4788.7  376.20
  4808.8  375.35  4849.0  376.15  4891.9  375.73  4929.3  378.76  4939.3  378.56
  4949.4  375.44  4969.4  374.03  5116.1  374.45  5165.0  374.12  5237.7  373.93
  5238.0  373.43  5241.7  373.93  5285.5  374.70  5329.8  378.55  5339.8  382.96
  5349.8  385.79  5369.8  386.79  5409.8  386.24  5429.9  387.61  5439.9  387.15
  5449.9  388.43  5469.9  386.28  5620.0  388.62  5677.1  387.80  5715.3  387.44
#Mann=9,-1,0
  4473.1    0.05       0  4717.6    0.16       0  4743.4    0.05       0
  5116.1   0.035       0  5165.0    0.05       0  5237.7    0.05       0
  5241.7    0.05       0  5285.5   0.035       0  5677.1    0.16       0
Bank Sta=5237.7,5241.7
Exp/Cntr=0.3,0.1

Type RM Length L Ch R = 1,8953,161,161,161
BEGIN DESCRIPTION:
North Twin Creek Trib J8953.41
END DESCRIPTION:
XS GIS Cut Line= 3
      2713973.08      6818891.84      2713775.22      6819266.10
      2713472.80      6819633.62
#Sta/Elev= 30
  4580.7  376.82  4681.1  375.26  4794.1  371.41  4806.0  370.23  4816.1  370.87
  4829.2  369.40  4860.1  370.94  4865.7  370.11  4873.9  371.62  5028.1  373.53
  5114.0  371.46  5127.1  370.14  5163.7  369.23  5178.0  366.69  5184.5  367.63
  5196.9  366.51  5197.1  366.01  5200.9  366.51  5205.3  368.22  5213.2  366.74
  5219.7  368.32  5256.2  368.13  5262.7  368.93  5269.4  368.08  5298.9  369.26
  5355.2  370.99  5361.7  369.90  5398.0  370.79  5439.9  374.71  5480.0  376.56
#Mann=7,-1,0
  4580.7    0.05       0  4681.1    0.16       0  4829.2    0.05       0
  5196.9    0.05       0  5200.9    0.05       0  5298.9    0.16       0
  5398.0    0.05       0
Bank Sta=5196.9,5200.9
Exp/Cntr=0.3,0.1

Type RM Length L Ch R = 1,8792,331,331,331
BEGIN DESCRIPTION:
North Twin Creek Trib J8791.99
END DESCRIPTION:
XS GIS Cut Line= 3
      2713963.09      6818846.16      2713658.38      6819153.02
      2713291.34      6819371.90
#Sta/Elev= 30
  4573.8  375.33  4610.5  373.15  4631.7  373.35  4711.1  370.07  4730.7  369.43
  4751.9  367.51  4797.2  366.69  4798.0  366.73  4885.7  366.98  4928.7  366.64
  4935.8  365.90  4957.0  367.77  4999.4  368.22  5013.5  368.06  5029.0  366.26
  5034.9  367.43  5066.0  368.50  5078.9  368.24  5100.2  365.87  5100.4  365.37
  5104.2  365.87  5108.8  366.87  5130.2  367.50  5195.3  367.32  5210.0  368.32
  5225.6  370.88  5268.4  372.48  5299.6  374.72  5363.8  375.43  5433.6  378.08
#Mann=7,-1,0
  4573.8    0.05       0  4711.1    0.16       0  4797.2    0.05       0
  4798.0    0.16       0  4885.7    0.05       0  5100.2    0.05       0
  5104.2    0.05       0
Bank Sta=5100.2,5104.2
Exp/Cntr=0.3,0.1

Type RM Length L Ch R = 1,8461,263,263,263
BEGIN DESCRIPTION:
North Twin Creek Trib J8460.89
END DESCRIPTION:
XS GIS Cut Line= 3
      2713985.52      6818749.26      2713723.56      6818875.27
      2713249.53      6819097.43
#Sta/Elev= 30
  4712.1  377.54  4750.6  374.33  4773.2  372.93  4778.7  373.20  4811.4  370.83
  4824.0  369.39  4833.6  369.96  4841.1  368.63  4855.8  368.59  4878.0  365.42
  4940.4  364.92  5020.2  364.69  5020.4  364.19  5024.2  364.69  5056.2  365.01
  5073.5  366.22  5079.1  364.93  5096.4  366.30  5101.9  365.57  5119.2  365.81
  5124.7  364.90  5176.8  364.88  5187.7  365.83  5193.2  365.52  5216.0  367.91
  5239.3  368.48  5307.3  370.67  5358.5  373.39  5472.6  376.12  5526.3  378.15
#Mann=5,-1,0
  4712.1    0.05       0  4940.4    0.16       0  5020.2    0.07       0
  5024.2    0.16       0  5239.3    0.05       0
Bank Sta=5020.2,5024.2
Exp/Cntr=0.3,0.1

Type RM Length L Ch R = 1,8198,309,309,309
BEGIN DESCRIPTION:
North Twin Creek Trib J8197.53
END DESCRIPTION:
XS GIS Cut Line= 3
      2714015.35      6818606.77      2713721.33      6818638.98
      2713202.41      6818671.22
#Sta/Elev= 30
  4708.6  379.22  4728.1  378.24  4738.1  378.16  4778.4  374.89  4788.4  373.78
  4793.4  373.97  4798.5  373.19  4838.7  369.83  4856.9  368.80  4868.9  368.24
  4884.6  366.68  4889.6  366.82  4939.3  365.20  4957.4  364.92  4957.7  364.42
  4961.2  364.42  4961.4  364.92  5109.6  364.94  5170.0  365.18  5190.1  365.91
  5208.9  367.12  5240.2  368.65  5260.2  369.14  5308.2  371.27  5330.3  372.40
  5410.5  374.18  5437.8  375.64  5442.9  374.72  5480.6  376.05  5524.3  377.02
#Mann=7,-1,0
  4708.6    0.05       0  4856.9    0.16       0  4957.4    0.07       0
  4961.4    0.16       0  5109.6    0.05       0  5208.9    0.07       0
  5308.2    0.05       0
Bank Sta=4957.4,4961.4
Exp/Cntr=0.3,0.1

Type RM Length L Ch R = 1,7889,233,233,233
BEGIN DESCRIPTION:
North Twin Creek Trib J7888.65
END DESCRIPTION:
XS GIS Cut Line= 3
      2714147.30      6818430.57      2713727.78      6818358.58
      2713119.96      6818277.20
#Sta/Elev= 30
  4580.4  381.25  4632.5  380.09  4667.3  378.43  4703.5  375.60  4727.3  374.59
  4754.2  372.28  4787.3  370.43  4794.8  369.42  4842.2  366.81  4900.2  364.51
  4900.4  364.01  4903.9  364.01  4904.2  364.51  4911.8  364.79  5035.1  364.80
  5111.3  364.78  5210.8  364.75  5280.3  364.69  5300.4  365.45  5310.4  366.45
  5361.0  368.96  5391.2  369.12  5421.5  370.25  5477.3  373.17  5482.4  372.73
  5522.4  373.46  5550.3  376.22  5555.4  375.68  5582.9  377.85  5619.3  379.80
#Mann=8,-1,0
  4580.4    0.05       0  4900.2   0.033       0  4904.2    0.05       0
  4911.8   0.033       0  5035.1    0.16       0  5111.3    0.05       0
  5210.8    0.07       0  5310.4    0.05       0
Bank Sta=4900.2,4904.2
Exp/Cntr=0.3,0.1

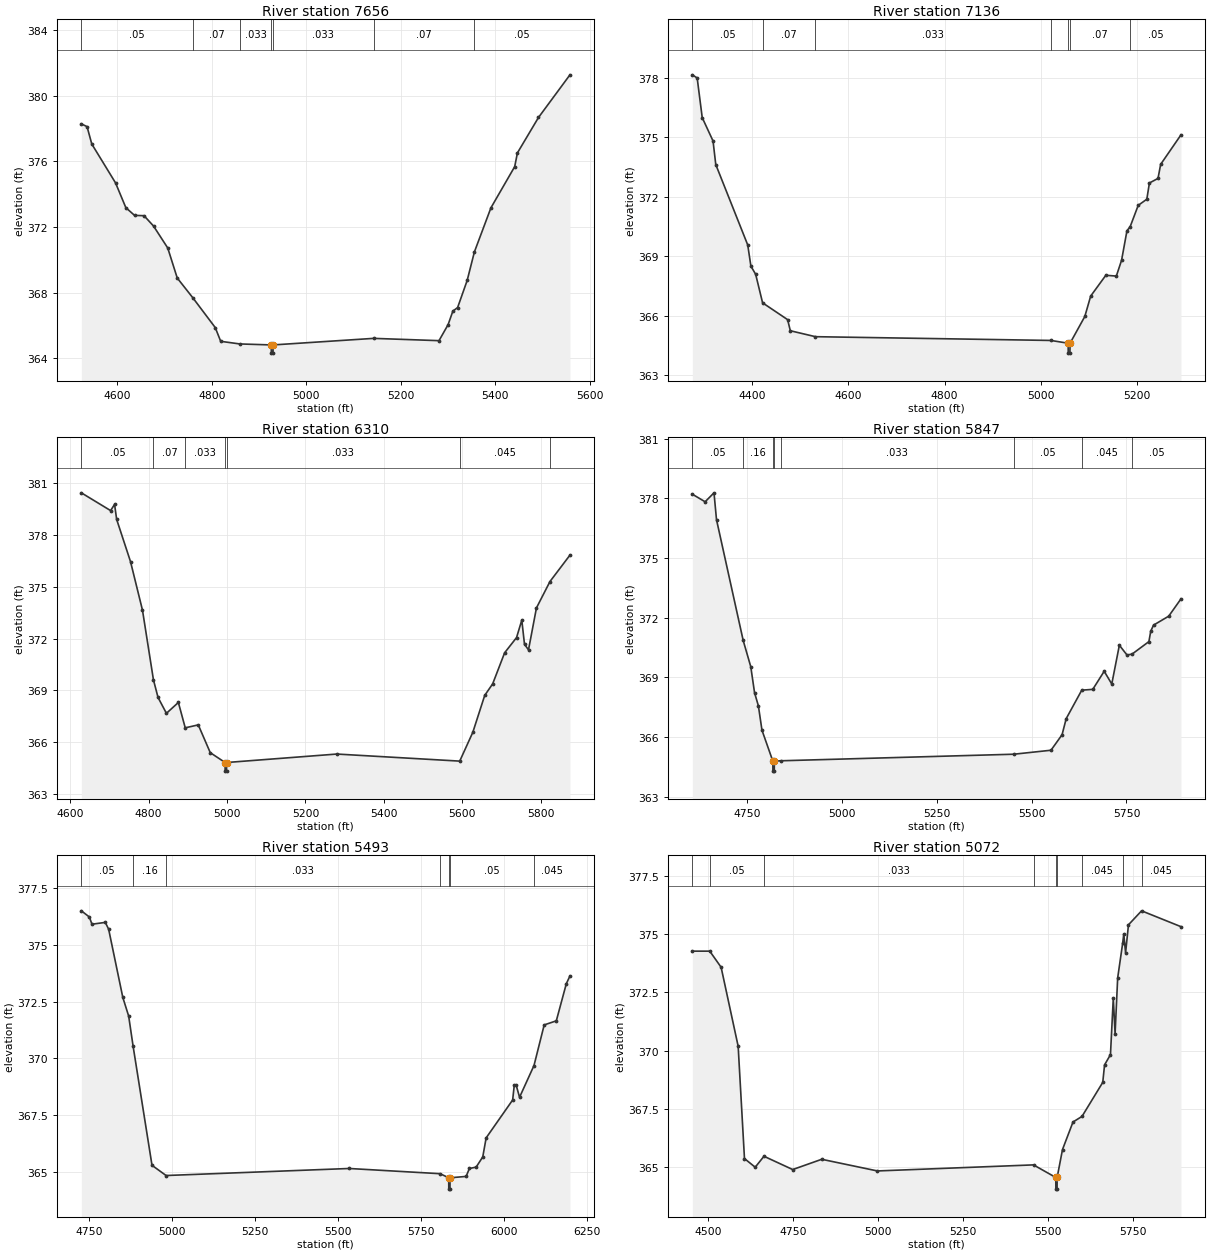
Type RM Length L Ch R = 1,7656,520,520,520
BEGIN DESCRIPTION:
North Twin Creek Trib J7656.49
END DESCRIPTION:
XS GIS Cut Line= 3
      2714258.04      6818214.91      2713776.27      6818167.47
      2713229.85      6818103.08
#Sta/Elev= 30
  4523.8  378.29  4535.9  378.12  4545.9  377.06  4596.2  374.69  4618.0  373.18
  4636.4  372.71  4656.5  372.69  4676.6  372.06  4706.7  370.72  4726.8  368.89
  4759.9  367.68  4807.2  365.87  4818.8  365.03  4859.2  364.87  4925.8  364.81
  4926.0  364.31  4929.5  364.31  4929.8  364.81  5142.5  365.21  5280.9  365.07
  5300.2  366.05  5310.2  366.87  5320.3  367.09  5340.5  368.74  5355.8  370.48
  5390.8  373.17  5441.1  375.68  5446.9  376.52  5491.5  378.68  5558.1  381.28
#Mann=7,-1,0
  4523.8    0.05       0  4759.9    0.07       0  4859.2   0.033       0
  4925.8   0.033       0  4929.8   0.033       0  5142.5    0.07       0
  5355.8    0.05       0
Bank Sta=4925.8,4929.8
Exp/Cntr=0.3,0.1

Type RM Length L Ch R = 1,7136,826,826,826
BEGIN DESCRIPTION:
North Twin Creek Trib J7136.29
END DESCRIPTION:
XS GIS Cut Line= 3
      2714254.26      6818158.33      2713611.37      6817826.64
      2713342.81      6817708.76
#Sta/Elev= 30
  4275.2  378.16  4285.2  378.00  4295.7  376.00  4318.2  374.82  4323.9  373.63
  4390.4  369.57  4397.0  368.50  4406.9  368.09  4421.3  366.65  4473.4  365.80
  4479.0  365.24  4531.3  364.94  5021.2  364.75  5057.1  364.61  5057.3  364.11
  5060.8  364.11  5061.1  364.61  5091.8  365.96  5104.0  366.99  5135.5  368.04
  5157.4  368.00  5168.3  368.80  5179.5  370.29  5186.1  370.49  5202.9  371.57
  5220.8  371.88  5226.2  372.70  5244.1  372.93  5249.6  373.64  5291.9  375.13
#Mann=7,-1,0
  4275.2    0.05       0  4421.3    0.07       0  4531.3   0.033       0
  5021.2    0.07       0  5057.1   0.033       0  5061.1    0.07       0
  5186.1    0.05       0
Bank Sta=5057.1,5061.1
Exp/Cntr=0.3,0.1

Type RM Length L Ch R = 1,6310,463,463,463
BEGIN DESCRIPTION:
North Twin Creek Trib J6310.41
END DESCRIPTION:
XS GIS Cut Line= 3
      2714589.42      6817872.50      2714222.69      6817804.32
      2713361.72      6817654.65
#Sta/Elev= 30
  4628.2  380.45  4702.9  379.42  4713.0  379.78  4718.3  378.91  4753.7  376.46
  4784.2  373.65  4812.2  369.61  4823.9  368.59  4845.3  367.67  4875.8  368.30
  4893.3  366.83  4926.6  367.00  4957.2  365.39  4995.0  364.82  4995.2  364.32
  4998.7  364.32  4999.0  364.82  5280.2  365.31  5593.8  364.90  5627.2  366.57
  5657.6  368.71  5677.9  369.38  5708.4  371.18  5738.8  372.06  5752.2  373.07
  5759.1  371.67  5769.3  371.35  5789.6  373.78  5824.1  375.31  5875.1  376.84
#Mann=7,-1,0
  4628.2    0.05       0  4812.2    0.07       0  4893.3   0.033       0
  4995.0   0.033       0  4999.0   0.033       0  5593.8   0.045       0
  5824.1    0.05       0
Bank Sta=4995,4999
Exp/Cntr=0.3,0.1

Type RM Length L Ch R = 1,5847,354,354,354
BEGIN DESCRIPTION:
North Twin Creek Trib J5847.01
END DESCRIPTION:
XS GIS Cut Line= 3
      2714569.46      6817490.18      2714175.47      6817460.34
      2713283.75      6817499.60
#Sta/Elev= 30
  4606.0  378.21  4639.6  377.83  4663.0  378.28  4669.6  376.93  4739.9  370.86
  4759.9  369.54  4769.9  368.23  4780.0  367.57  4789.4  366.35  4818.1  364.79
  4818.3  364.29  4821.8  364.29  4822.1  364.79  4839.0  364.81  5453.1  365.14
  5551.1  365.34  5580.3  366.12  5591.2  366.93  5632.2  368.36  5661.2  368.40
  5691.3  369.31  5711.3  368.67  5731.3  370.62  5751.3  370.13  5764.6  370.17
  5809.1  370.80  5814.1  371.33  5821.4  371.63  5861.4  372.08  5893.7  372.95
#Mann=8,-1,0
  4606.0    0.05       0  4739.9    0.16       0  4818.1   0.033       0
  4822.1    0.16       0  4839.0   0.033       0  5453.1    0.05       0
  5632.2   0.045       0  5764.6    0.05       0
Bank Sta=4818.1,4822.1
Exp/Cntr=0.3,0.1

Type RM Length L Ch R = 1,5493,421,421,421
BEGIN DESCRIPTION:
North Twin Creek Trib J5493.27
END DESCRIPTION:
XS GIS Cut Line= 3
      2714597.80      6817218.08      2714325.00      6817191.03
      2713135.14      6817057.19
#Sta/Elev= 30
  4727.3  376.51  4751.3  376.24  4759.3  375.92  4799.4  376.00  4809.5  375.70
  4852.2  372.69  4869.8  371.87  4883.3  370.53  4940.1  365.29  4982.5  364.84
  5533.8  365.15  5807.8  364.92  5833.7  364.74  5833.9  364.24  5837.4  364.24
  5837.7  364.74  5886.0  364.80  5896.0  365.15  5916.2  365.21  5936.2  365.66
  5946.4  366.50  6026.2  368.17  6031.2  368.83  6036.9  368.82  6047.0  368.29
  6090.5  369.69  6121.2  371.48  6157.7  371.66  6187.9  373.30  6198.8  373.64
#Mann=7,-1,0
  4727.3    0.05       0  4883.3    0.16       0  4982.5   0.033       0
  5807.8    0.05       0  5833.7   0.033       0  5837.7    0.05       0
  6090.5   0.045       0
Bank Sta=5833.7,5837.7
Exp/Cntr=0.3,0.1

Type RM Length L Ch R = 1,5072,98,98,98
BEGIN DESCRIPTION:
North Twin Creek Trib J5072.2
END DESCRIPTION:
XS GIS Cut Line= 4
      2714660.24      6816900.01      2714114.50      6816851.09
      2713671.92      6816822.74      2713250.22      6816971.25
#Sta/Elev= 30
  4453.3  374.27  4504.5  374.27  4537.9  373.58  4588.1  370.19  4606.7  365.37
  4638.3  365.00  4664.1  365.47  4748.7  364.90  4834.1  365.34  4998.0  364.84
  5457.6  365.10  5523.2  364.56  5523.5  364.06  5527.0  364.06  5527.2  364.56
  5543.0  365.76  5573.9  366.94  5600.4  367.18  5661.5  368.64  5666.8  369.39
  5684.2  369.83  5692.5  372.25  5697.8  370.73  5705.4  373.12  5720.4  374.64
  5723.4  375.01  5728.7  374.20  5737.2  375.40  5775.8  376.00  5891.8  375.32
#Mann=9,-1,0
  4453.3   0.045       0  4504.5    0.05       0  4664.1   0.033       0
  5457.6    0.05       0  5523.2   0.033       0  5527.2    0.05       0
  5600.4   0.045       0  5720.4    0.05       0  5775.8   0.045       0
Bank Sta=5523.2,5527.2
Exp/Cntr=0.3,0.1

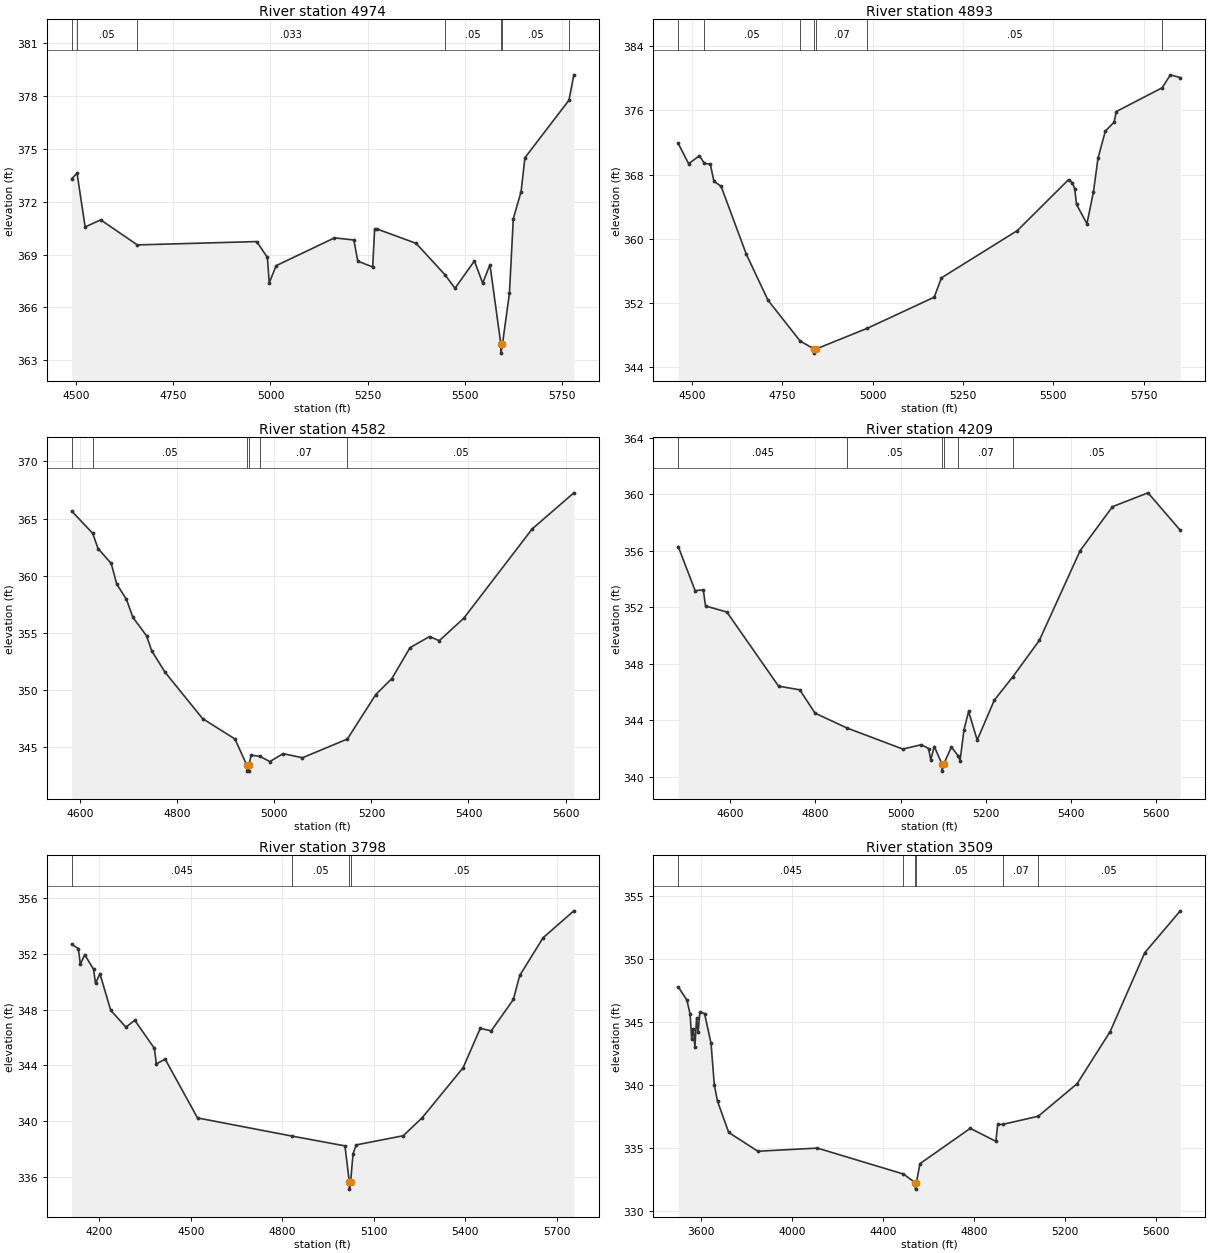
Type RM Length L Ch R = 1,4974,81,81,81
BEGIN DESCRIPTION:
North Twin Creek Trib J4974.41
END DESCRIPTION:
XS GIS Cut Line= 3
      2714620.27      6816815.96      2714111.83      6816775.70
      2713330.28      6816747.36
#Sta/Elev= 30
  4488.7  373.31  4502.3  373.62  4523.1  370.57  4563.2  370.97  4657.4  369.55
  4964.5  369.74  4992.2  368.84  4996.8  367.39  5014.6  368.37  5164.7  369.95
  5214.7  369.83  5224.7  368.63  5263.1  368.30  5268.1  370.44  5274.7  370.45
  5374.8  369.64  5449.5  367.85  5474.9  367.09  5524.9  368.64  5546.2  367.38
  5564.9  368.43  5593.0  363.91  5593.2  363.41  5597.0  363.91  5615.0  366.80
  5625.0  371.04  5645.0  372.57  5655.0  374.50  5768.2  377.76  5780.8  379.20
#Mann=7,-1,0
  4488.7   0.045       0  4502.3    0.05       0  4657.4   0.033       0
  5449.5    0.05       0  5593.0   0.033       0  5597.0    0.05       0
  5768.2   0.045       0
Bank Sta=5593,5597
Exp/Cntr=0.3,0.1

Type RM Length L Ch R = 1,4893,311,311,311
BEGIN DESCRIPTION:
North Twin Creek Trib J4892.64
END DESCRIPTION:
XS GIS Cut Line= 4
      2714664.84      6816700.10      2714124.64      6816698.06
      2713697.00      6816690.83      2713282.08      6816611.17
#Sta/Elev= 30
  4461.3  371.88  4490.1  369.36  4520.1  370.35  4533.8  369.39  4550.1  369.30
  4560.1  367.19  4580.1  366.53  4650.1  358.05  4710.1  352.34  4798.8  347.27
  4838.1  346.26  4838.4  345.76  4842.1  346.26  4984.1  348.84  5170.2  352.73
  5190.2  355.14  5400.2  361.02  5542.2  367.37  5552.4  367.01  5559.2  366.25
  5564.3  364.28  5593.1  361.88  5611.2  365.86  5623.7  370.03  5644.1  373.42
  5668.3  374.53  5674.6  375.86  5801.5  378.82  5824.2  380.43  5851.7  380.08
#Mann=7,-1,0
  4461.3   0.045       0  4533.8    0.05       0  4798.8    0.07       0
  4838.1    0.05       0  4842.1    0.07       0  4984.1    0.05       0
  5801.5   0.045       0
Bank Sta=4838.1,4842.1
Exp/Cntr=0.3,0.1

Type RM Length L Ch R = 1,4582,373,373,373
BEGIN DESCRIPTION:
North Twin Creek Trib J4582.02
END DESCRIPTION:
XS GIS Cut Line= 3
      2714653.98      6816550.96      2714256.05      6816433.57
      2713640.64      6816363.19
#Sta/Elev= 30
  4582.8  365.65  4626.0  363.70  4636.9  362.38  4664.1  361.07  4675.4  359.27
  4695.4  357.94  4708.7  356.36  4736.8  354.75  4747.5  353.43  4775.3  351.54
  4852.4  347.50  4919.0  345.72  4943.6  343.41  4943.9  342.91  4947.4  342.91
  4947.6  343.41  4952.3  344.31  4970.7  344.20  4990.8  343.74  5017.9  344.44
  5058.1  344.08  5150.6  345.72  5209.1  349.61  5242.3  351.01  5279.6  353.71
  5319.8  354.68  5339.9  354.32  5390.3  356.28  5531.2  364.09  5617.1  367.25
#Mann=6,-1,0
  4582.8   0.045       0  4626.0    0.05       0  4943.6    0.07       0
  4947.6    0.05       0  4970.7    0.07       0  5150.6    0.05       0
Bank Sta=4943.6,4947.6
Exp/Cntr=0.3,0.1

Type RM Length L Ch R = 1,4209,411,411,411
BEGIN DESCRIPTION:
North Twin Creek Trib J4208.8
END DESCRIPTION:
XS GIS Cut Line= 3
      2714873.23      6816287.59      2714377.58      6816103.00
      2713732.48      6816027.56
#Sta/Elev= 30
  4478.2  356.29  4517.9  353.17  4537.0  353.23  4542.3  352.09  4592.3  351.66
  4713.7  346.42  4763.4  346.16  4799.3  344.51  4873.6  343.47  5005.3  341.97
  5049.0  342.28  5065.7  342.01  5070.8  341.22  5079.2  342.15  5097.3  340.91
  5097.6  340.41  5101.3  340.91  5119.4  342.12  5135.7  341.47  5139.6  341.15
  5149.0  343.35  5159.7  344.63  5179.9  342.61  5220.1  345.43  5263.7  347.09
  5325.8  349.66  5421.5  356.00  5497.4  359.11  5580.8  360.09  5656.6  357.44
#Mann=6,-1,0
  4478.2   0.045       0  4873.6    0.05       0  5097.3    0.05       0
  5101.3    0.05       0  5135.7    0.07       0  5263.7    0.05       0
Bank Sta=5097.3,5101.3
Exp/Cntr=0.3,0.1

Type RM Length L Ch R = 1,3798,289,289,289
BEGIN DESCRIPTION:
North Twin Creek Trib J3798.4
END DESCRIPTION:
XS GIS Cut Line= 3
      2715233.45      6816282.86      2714521.96      6815738.32
      2713793.71      6815920.73
#Sta/Elev= 30
  4109.5  352.70  4131.2  352.40  4137.5  351.27  4152.0  351.96  4181.1  350.90
  4187.4  349.89  4201.9  350.59  4237.2  347.96  4287.1  346.75  4316.1  347.24
  4380.5  345.22  4386.8  344.11  4415.9  344.44  4521.9  340.22  4832.7  338.91
  5005.5  338.21  5019.9  335.60  5020.2  335.10  5023.9  335.60  5032.1  337.66
  5042.5  338.28  5196.8  338.94  5259.0  340.24  5393.0  343.83  5449.2  346.66
  5485.2  346.48  5558.0  348.74  5578.6  350.46  5655.2  353.17  5756.2  355.11
#Mann=4,-1,0
  4109.5   0.045       0  4832.7    0.05       0  5019.9    0.05       0
  5023.9    0.05       0
Bank Sta=5019.9,5023.9
Exp/Cntr=0.3,0.1

Type RM Length L Ch R = 1,3509,254,254,254
BEGIN DESCRIPTION:
Mapping XS de6bd9f5
END DESCRIPTION:
XS GIS Cut Line= 6
      2715526.39      6816144.29      2714953.18      6815499.00
      2714801.58      6815378.62      2714698.23      6815397.88
      2714372.27      6815507.28      2713772.21      6815870.14
#Sta/Elev= 30
  3500.7  347.81  3538.7  346.76  3553.0  345.63  3559.6  343.69  3567.2  344.50
  3573.9  343.07  3581.4  345.33  3588.1  344.22  3595.6  345.78  3616.5  345.69
  3644.9  343.32  3659.2  340.04  3673.4  338.72  3722.7  336.24  3850.7  334.75
  4112.4  335.00  4490.4  332.94  4543.4  332.24  4543.7  331.74  4547.4  332.24
  4563.1  333.76  4784.3  336.57  4896.9  335.54  4905.1  336.89  4926.1  336.88
  5083.1  337.53  5254.2  340.12  5399.3  344.26  5551.2  350.52  5707.6  353.85
#Mann=6,-1,0
  3500.7   0.045       0  4490.4    0.05       0  4543.4    0.07       0
  4547.4    0.05       0  4926.1    0.07       0  5083.1    0.05       0
Bank Sta=4543.4,4547.4
Exp/Cntr=0.3,0.1

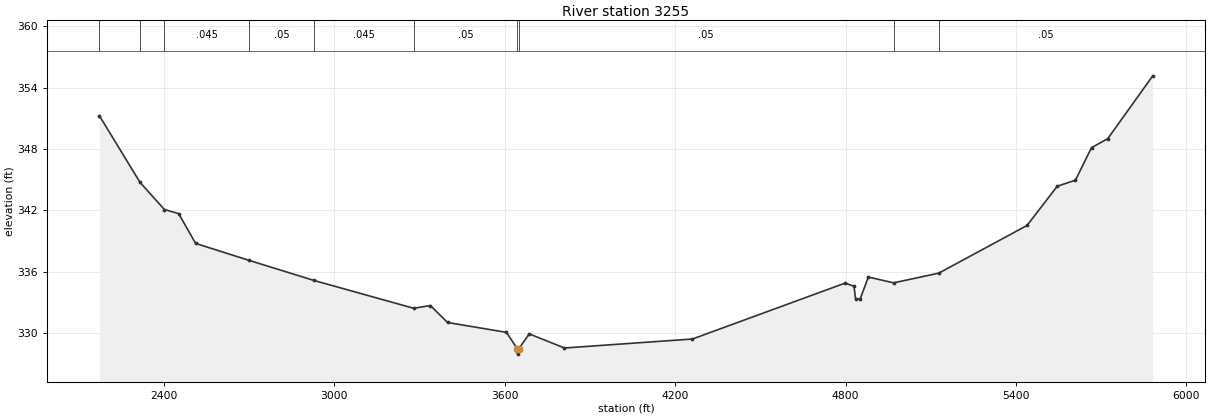
Type RM Length L Ch R = 1,3255,0,0,0
BEGIN DESCRIPTION:
North Twin Creek Trib J3216.219
END DESCRIPTION:
XS GIS Cut Line= 5
      2715775.86      6816323.17      2715488.67      6814909.54
      2715434.28      6814717.79      2714375.60      6815250.79
      2713710.79      6815829.64
#Sta/Elev= 30
  2172.9  351.27  2316.1  344.74  2401.9  342.08  2452.1  341.68  2511.9  338.76
  2701.4  337.09  2929.0  335.13  3279.4  332.41  3338.4  332.68  3398.7  331.02
  3606.3  330.05  3644.9  328.42  3645.1  327.92  3648.9  328.42  3686.6  329.90
  3810.5  328.52  4260.9  329.40  4798.0  334.87  4829.8  334.57  4835.4  333.30
  4852.2  333.36  4880.1  335.47  4969.2  334.90  5128.2  335.85  5439.0  340.52
  5545.3  344.36  5609.4  344.95  5665.9  348.14  5722.9  349.01  5881.5  355.17
#Mann=10,-1,0
  2172.9   0.045       0  2316.1    0.05       0  2401.9   0.045       0
  2701.4    0.05       0  2929.0   0.045       0  3279.4    0.05       0
  3644.9    0.07       0  3648.9    0.05       0  4969.2    0.07       0
  5128.2    0.05       0
Bank Sta=3644.9,3648.9
Exp/Cntr=0.3,0.1

Chan Stop Cuts=-1