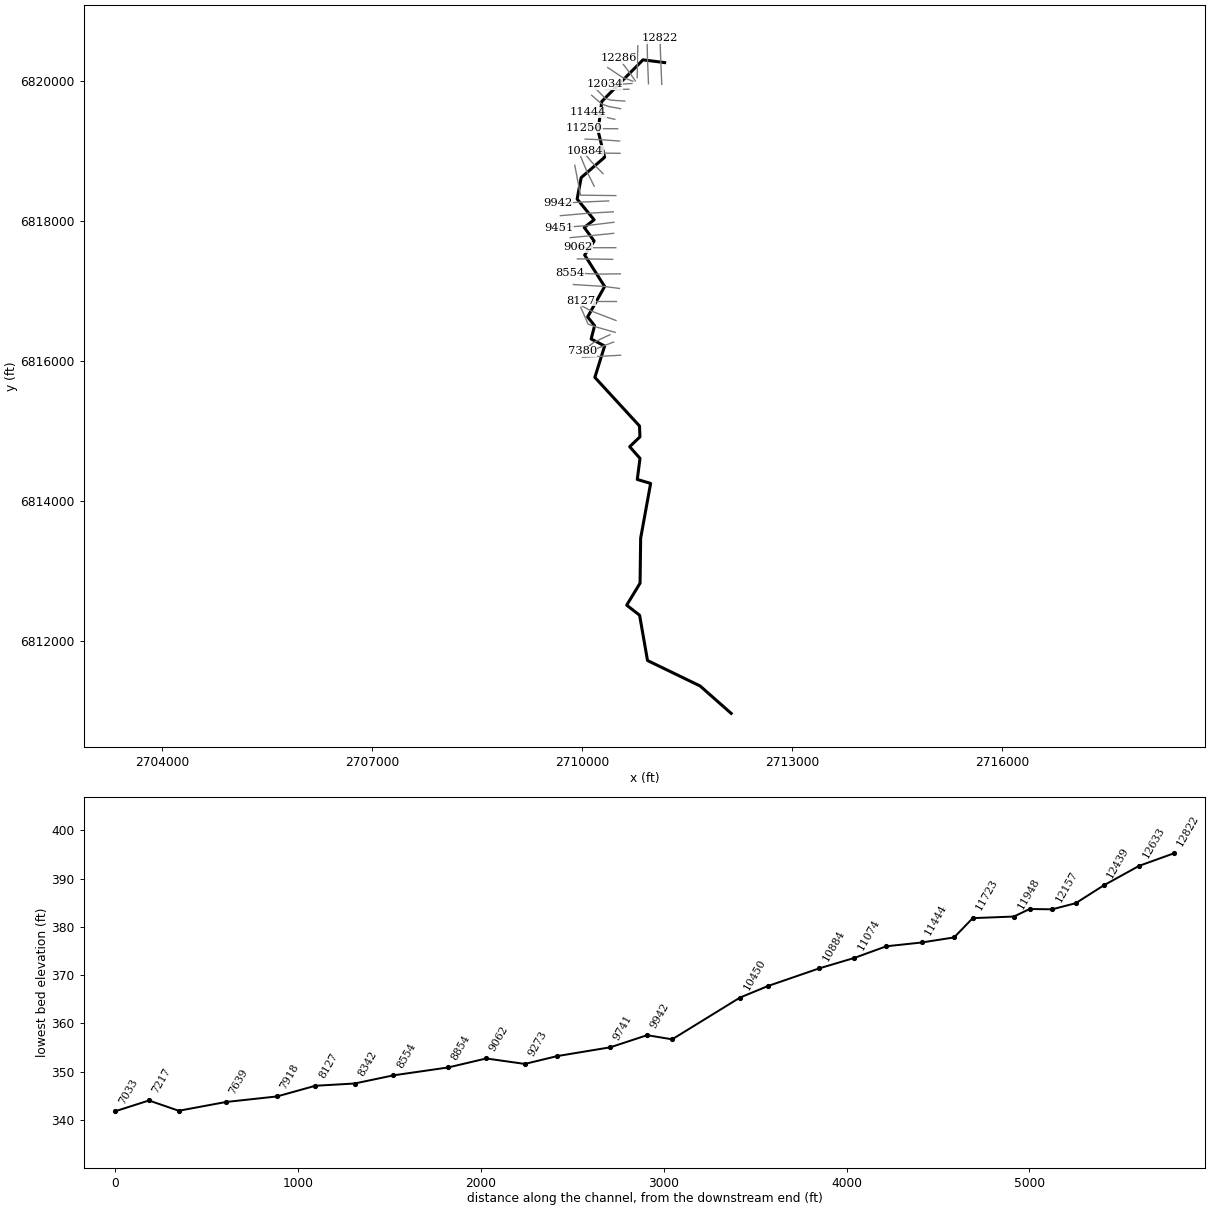
--- North Twin Creek Trib K.prj (project) ---

Proj Title=North Twin Creek Trib K Base Level Engineering
Current Plan=p01
Default Exp/Contr=0.3,0.1
English Units
Geom File=g01
Flow File=f01
Plan File=p01
BEGIN DESCRIPTION:
North Twin Creek Trib K
END DESCRIPTION:

--- North Twin Creek Trib K.p01 (plan) ---

Plan Title=Multiple Run
Short Identifier=Multiple
Geom File=g01
Flow File=f01
Subcritical Flow
K Sum by GR= 0
Std Step Tol= 0.01
Critical Tol= 0.01
Num of Std Step Trials= 20
Max Error Tol= 0.3
Flow Tol Ratio= 0.001
Split Flow NTrial= 30
Split Flow Tol= 0.02
Split Flow Ratio= 0.02
Log Output Level= 0
Friction Slope Method= 1
Unsteady Friction Slope Method= 2
Unsteady Bridges Friction Slope Method= 1
Parabolic Critical Depth
Global Vel Dist=  1 , 1 , 1
Global Log Level= 0
CheckData=True
Encroach Param= -1, 0, 0, 0
BEGIN DESCRIPTION:
Multiple Run
END DESCRIPTION:

--- North Twin Creek Trib K.f01 (steady flow) ---

Flow Title=Multiple
Number of Profiles=7
Profile Names=10-year,25-year,50-year,1pct_min,100-year,1pct_plu,500-year
River Rch & RM= North Twin Creek,Reach-1,12822
     159     194     221     125     250     499     318
River Rch & RM= North Twin Creek,Reach-1,9942
     447     590     704     418     833    1663    1165
River Rch & RM= North Twin Creek,Reach-1,7380
     753    1026    1250     755    1507    3007    2190
River Rch & RM= North Twin Creek,Reach-1,3421
     862    1176    1434     866    1728    3448    2510
Boundary for River Rch & Prof#=North Twin Creek,Reach-1,1
Up Type=0
Dn Type=3
Dn Slope=0.005
Boundary for River Rch & Prof#=North Twin Creek,Reach-1,2
Up Type=0
Dn Type=3
Dn Slope=0.005
Boundary for River Rch & Prof#=North Twin Creek,Reach-1,3
Up Type=0
Dn Type=3
Dn Slope=0.005
Boundary for River Rch & Prof#=North Twin Creek,Reach-1,4
Up Type=0
Dn Type=3
Dn Slope=0.005
Boundary for River Rch & Prof#=North Twin Creek,Reach-1,5
Up Type=0
Dn Type=3
Dn Slope=0.005
Boundary for River Rch & Prof#=North Twin Creek,Reach-1,6
Up Type=0
Dn Type=3
Dn Slope=0.005
Boundary for River Rch & Prof#=North Twin Creek,Reach-1,7
Up Type=0
Dn Type=3
Dn Slope=0.005

--- North Twin Creek Trib K.g01 (geometry) ---

Geom Title=Existing Conditions

River Reach=North Twin Creek,Reach-1
Reach XY= 30
      2711176.00      6820261.00      2710865.94      6820299.90
      2710278.09      6819705.74      2710225.72      6819283.77
      2710318.32      6818907.30      2709983.81      6818617.19
      2709926.00      6818311.00      2710168.47      6818014.15
      2710027.50      6817905.13      2710168.71      6817711.09
      2710033.30      6817511.08      2710318.67      6817061.10
      2710075.90      6816626.36      2710175.25      6816501.22
      2710126.00      6816311.00      2710318.82      6816211.33
      2710179.12      6815762.62      2710816.77      6815067.93
      2710822.93      6814912.43      2710676.53      6814771.69
      2710823.94      6814605.15      2710785.01      6814303.88
      2710975.64      6814247.26      2710833.23      6813464.45
      2710824.80      6812821.50      2710633.67      6812507.34
      2710818.00      6812364.35      2710931.17      6811716.41
      2711682.06      6811352.86      2712126.00      6810961.00

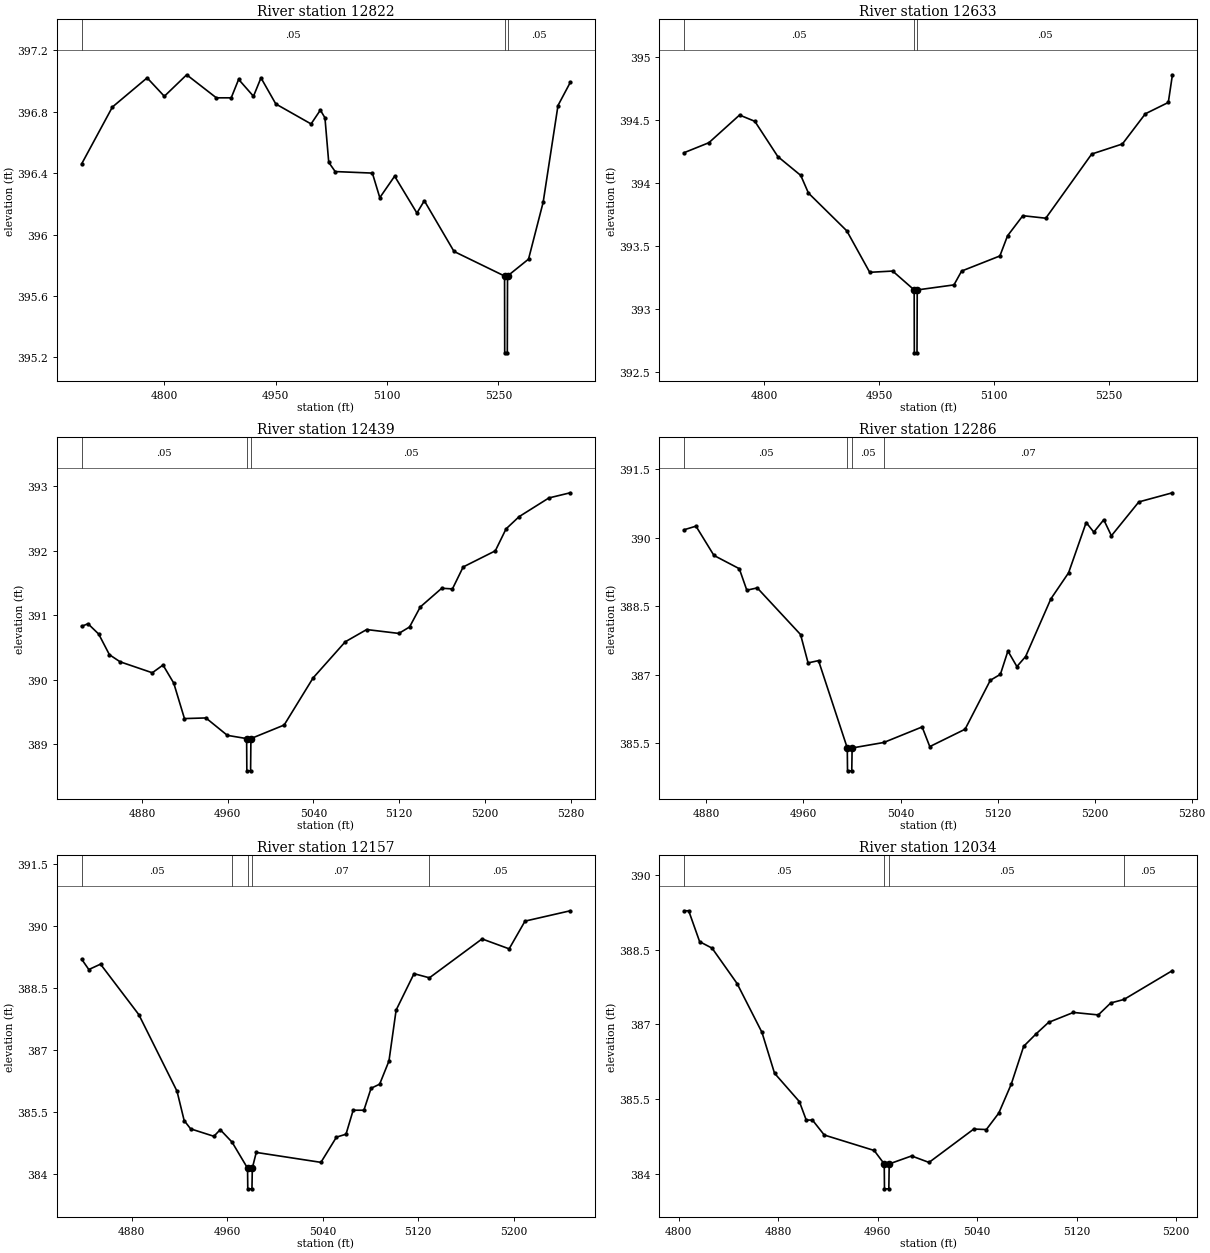
Type RM Length L Ch R = 1,12822,189,189,189
BEGIN DESCRIPTION:
North Twin Creek Trib K12821.965
END DESCRIPTION:
XS GIS Cut Line= 3
      2711134.79      6819949.66      2711121.65      6820260.98
      2711108.73      6820607.44
#Sta/Elev= 30
  4688.4  396.46  4729.8  396.83  4776.6  397.02  4799.8  396.90  4829.9  397.04
  4869.9  396.89  4889.9  396.89  4899.9  397.01  4919.9  396.90  4930.0  397.02
  4950.0  396.85  4997.5  396.72  5010.0  396.81  5016.2  396.76  5021.3  396.47
  5030.0  396.41  5080.1  396.40  5090.1  396.24  5110.1  396.38  5140.1  396.14
  5150.1  396.22  5190.1  395.89  5258.2  395.73  5258.4  395.23  5261.9  395.23
  5262.2  395.73  5290.5  395.84  5310.2  396.21  5330.2  396.84  5346.7  396.99
#Mann=3,-1,0
  4688.4    0.05       0  5258.2    0.05       0  5262.2    0.05       0
Bank Sta=5258.2,5262.2
Exp/Cntr=0.3,0.1

Type RM Length L Ch R = 1,12633,194,194,194
BEGIN DESCRIPTION:
North Twin Creek Trib K12632.74
END DESCRIPTION:
XS GIS Cut Line= 3
      2710944.97      6819958.28      2710932.62      6820268.53
      2710923.75      6820596.42
#Sta/Elev= 25
  4694.8  394.24  4727.5  394.32  4767.6  394.54  4787.6  394.49  4817.6  394.21
  4847.6  394.06  4857.6  393.92  4907.7  393.62  4937.7  393.29  4967.7  393.30
  4995.8  393.15  4996.0  392.65  4999.5  392.65  4999.8  393.15  5047.8  393.19
  5057.8  393.30  5107.8  393.42  5117.8  393.58  5137.8  393.74  5167.8  393.72
  5227.8  394.23  5267.9  394.31  5297.9  394.55  5327.9  394.64  5333.3  394.86
#Mann=3,-1,0
  4694.8    0.05       0  4995.8    0.05       0  4999.8    0.05       0
Bank Sta=4995.8,4999.8
Exp/Cntr=0.3,0.1

Type RM Length L Ch R = 1,12439,153,153,153
BEGIN DESCRIPTION:
North Twin Creek Trib K12439.26
END DESCRIPTION:
XS GIS Cut Line= 3
      2710783.39      6820045.14      2710786.42      6820234.02
      2710792.07      6820500.85
#Sta/Elev= 30
  4823.8  390.83  4829.7  390.87  4839.7  390.71  4849.7  390.39  4859.7  390.28
  4889.7  390.11  4899.7  390.23  4909.7  389.95  4919.7  389.40  4939.7  389.41
  4959.7  389.14  4977.7  389.09  4977.9  388.59  4981.4  388.59  4981.7  389.09
  5012.7  389.30  5039.7  390.03  5069.7  390.59  5089.7  390.78  5119.7  390.72
  5129.7  390.82  5139.7  391.13  5159.7  391.42  5169.7  391.41  5179.7  391.75
  5209.7  392.00  5219.7  392.34  5231.9  392.53  5259.7  392.82  5279.6  392.90
#Mann=3,-1,0
  4823.8    0.05       0  4977.7    0.05       0  4981.7    0.05       0
Bank Sta=4977.7,4981.7
Exp/Cntr=0.3,0.1

Type RM Length L Ch R = 1,12286,129,129,129
BEGIN DESCRIPTION:
North Twin Creek Trib K12286.11
END DESCRIPTION:
XS GIS Cut Line= 3
      2710758.00      6819999.54      2710677.45      6820113.76
      2710518.34      6820323.09
#Sta/Elev= 30
  4861.4  390.17  4871.4  390.25  4886.2  389.61  4907.1  389.32  4913.3  388.85
  4921.9  388.90  4957.6  387.88  4963.8  387.26  4972.4  387.31  4996.1  385.40
  4996.3  384.90  4999.8  384.90  5000.1  385.40  5026.2  385.52  5057.8  385.86
  5064.1  385.43  5093.2  385.81  5114.0  386.88  5122.3  387.01  5128.5  387.52
  5135.9  387.18  5143.1  387.40  5163.9  388.66  5178.5  389.23  5193.0  390.33
  5199.3  390.12  5207.5  390.39  5213.8  390.04  5236.4  390.78  5264.1  390.98
#Mann=4,-1,0
  4861.4    0.05       0  4996.1    0.05       0  5000.1    0.05       0
  5026.2    0.07       0
Bank Sta=4996.1,5000.1
Exp/Cntr=0.3,0.1

Type RM Length L Ch R = 1,12157,123,123,123
BEGIN DESCRIPTION:
North Twin Creek Trib K12156.68
END DESCRIPTION:
XS GIS Cut Line= 3
      2710720.77      6819995.41      2710565.05      6820054.21
      2710363.50      6820189.87
#Sta/Elev= 30
  4838.0  389.19  4844.0  388.94  4853.8  389.07  4885.9  387.85  4917.9  386.00
  4923.9  385.29  4929.3  385.09  4948.8  384.91  4954.1  385.07  4964.0  384.77
  4977.0  384.14  4977.2  383.64  4980.7  383.64  4981.0  384.14  4984.3  384.52
  5038.5  384.28  5051.5  384.89  5059.5  384.96  5065.5  385.54  5074.5  385.54
  5080.5  386.07  5087.7  386.17  5095.5  386.73  5101.5  387.96  5116.5  388.84
  5129.4  388.74  5173.5  389.68  5196.2  389.44  5209.5  390.11  5247.4  390.36
#Mann=5,-1,0
  4838.0    0.05       0  4964.0    0.07       0  4977.0    0.07       0
  4981.0    0.07       0  5129.4    0.05       0
Bank Sta=4977,4981
Exp/Cntr=0.3,0.1

Type RM Length L Ch R = 1,12034,86,86,86
BEGIN DESCRIPTION:
North Twin Creek Trib K12034.31
END DESCRIPTION:
XS GIS Cut Line= 3
      2710708.69      6819962.60      2710512.02      6819949.44
      2710316.42      6819955.36
#Sta/Elev= 30
  4804.1  389.28  4808.0  389.28  4816.8  388.66  4826.8  388.53  4846.9  387.82
  4866.9  386.84  4877.0  386.02  4897.0  385.45  4902.5  385.08  4907.5  385.08
  4917.0  384.78  4957.1  384.47  4965.2  384.20  4965.4  383.70  4968.9  383.70
  4969.2  384.20  4987.2  384.36  5001.2  384.23  5037.2  384.90  5047.3  384.89
  5057.3  385.22  5067.3  385.80  5077.3  386.56  5087.3  386.81  5097.3  387.04
  5117.3  387.24  5137.3  387.19  5147.3  387.43  5157.9  387.50  5196.9  388.08
#Mann=4,-1,0
  4804.1    0.05       0  4965.2    0.07       0  4969.2    0.05       0
  5157.9    0.05       0
Bank Sta=4965.2,4969.2
Exp/Cntr=0.3,0.1

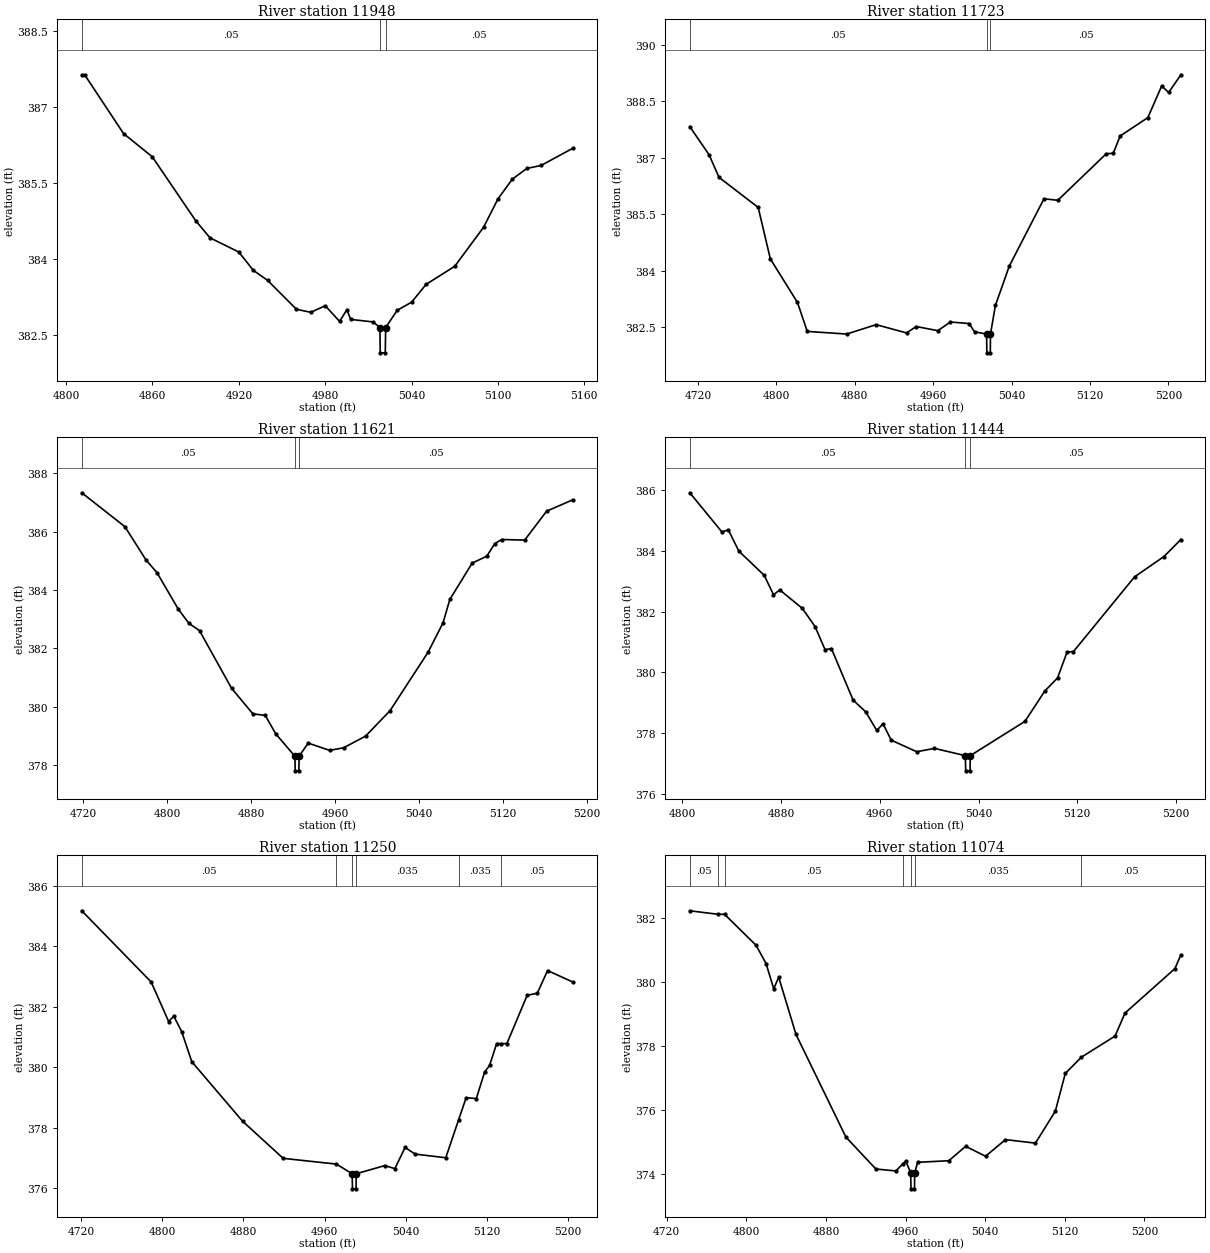
Type RM Length L Ch R = 1,11948,225,225,225
BEGIN DESCRIPTION:
North Twin Creek Trib K11947.98
END DESCRIPTION:
XS GIS Cut Line= 3
      2710665.03      6819880.21      2710475.48      6819875.87
      2710323.99      6819877.60
#Sta/Elev= 30
  4810.9  387.63  4812.9  387.63  4839.9  386.47  4859.9  386.01  4890.0  384.75
  4900.0  384.41  4920.0  384.13  4930.0  383.77  4940.0  383.57  4960.0  383.00
  4970.0  382.94  4980.0  383.07  4990.0  382.76  4995.0  382.99  4997.7  382.80
  5013.3  382.75  5018.0  382.64  5018.2  382.14  5021.7  382.14  5022.0  382.64
  5030.0  382.98  5040.0  383.14  5050.0  383.49  5070.0  383.85  5090.0  384.62
  5100.0  385.18  5110.0  385.57  5120.0  385.78  5130.0  385.84  5152.0  386.18
#Mann=3,-1,0
  4810.9    0.05       0  5018.0    0.05       0  5022.0    0.05       0
Bank Sta=5018,5022
Exp/Cntr=0.3,0.1

Type RM Length L Ch R = 1,11723,102,102,102
BEGIN DESCRIPTION:
North Twin Creek Trib K11722.69
END DESCRIPTION:
XS GIS Cut Line= 6
      2710605.70      6819710.87      2710467.29      6819719.83
      2710402.49      6819725.27      2710343.21      6819746.43
      2710320.93      6819756.31      2710173.95      6819906.53
#Sta/Elev= 30
  4711.6  387.83  4731.3  387.08  4741.4  386.48  4781.4  385.68  4793.8  384.31
  4821.5  383.15  4831.5  382.38  4871.7  382.31  4901.8  382.56  4932.8  382.34
  4942.7  382.51  4964.7  382.40  4977.6  382.63  4996.7  382.59  5002.2  382.37
  5014.5  382.31  5014.8  381.81  5018.3  381.81  5018.5  382.31  5023.5  383.07
  5037.7  384.12  5073.1  385.91  5087.2  385.87  5136.7  387.11  5143.8  387.12
  5150.8  387.58  5179.1  388.07  5193.2  388.91  5200.4  388.74  5212.8  389.21
#Mann=3,-1,0
  4711.6    0.05       0  5014.5    0.05       0  5018.5    0.05       0
Bank Sta=5014.5,5018.5
Exp/Cntr=0.3,0.1

Type RM Length L Ch R = 1,11621,177,177,177
BEGIN DESCRIPTION:
North Twin Creek Trib K11621.38
END DESCRIPTION:
XS GIS Cut Line= 5
      2710546.41      6819602.15      2710378.14      6819632.93
      2710304.05      6819658.95      2710269.86      6819675.48
      2710133.43      6819793.55
#Sta/Elev= 30
  4718.7  387.33  4759.8  386.17  4780.1  385.02  4790.3  384.60  4810.6  383.35
  4820.8  382.86  4830.9  382.61  4861.4  380.64  4881.8  379.76  4893.5  379.71
  4903.5  379.08  4921.8  378.31  4922.1  377.81  4925.6  377.81  4925.8  378.31
  4934.5  378.76  4954.9  378.51  4968.3  378.60  4989.2  379.00  5012.5  379.87
  5048.7  381.87  5062.9  382.87  5069.5  383.68  5090.7  384.92  5104.7  385.16
  5112.3  385.59  5118.9  385.73  5140.8  385.71  5161.7  386.70  5186.7  387.09
#Mann=3,-1,0
  4718.7    0.05       0  4921.8    0.05       0  4925.8    0.05       0
Bank Sta=4921.8,4925.8
Exp/Cntr=0.3,0.1

Type RM Length L Ch R = 1,11444,194,194,194
BEGIN DESCRIPTION:
North Twin Creek Trib K11443.79
END DESCRIPTION:
XS GIS Cut Line= 3
      2710464.61      6819449.46      2710275.39      6819495.36
      2710079.86      6819550.26
#Sta/Elev= 30
  4806.1  385.92  4832.1  384.63  4837.3  384.70  4845.8  384.00  4866.4  383.20
  4873.9  382.56  4879.0  382.72  4897.3  382.11  4907.6  381.51  4915.7  380.75
  4920.8  380.79  4938.4  379.09  4948.7  378.70  4957.5  378.09  4962.6  378.31
  4969.3  377.77  4989.9  377.39  5004.3  377.50  5029.3  377.26  5029.6  376.76
  5033.1  376.76  5033.3  377.26  5077.6  378.39  5093.7  379.39  5104.0  379.82
  5111.7  380.67  5116.9  380.69  5166.4  383.15  5190.2  383.82  5203.9  384.38
#Mann=3,-1,0
  4806.1    0.05       0  5029.3    0.05       0  5033.3    0.05       0
Bank Sta=5029.3,5033.3
Exp/Cntr=0.3,0.1

Type RM Length L Ch R = 1,11250,176,176,176
BEGIN DESCRIPTION:
North Twin Creek Trib K11249.95
END DESCRIPTION:
XS GIS Cut Line= 3
      2710504.41      6819315.30      2710223.60      6819317.54
      2710021.13      6819331.96
#Sta/Elev= 30
  4720.8  385.18  4789.2  382.82  4806.4  381.51  4811.4  381.69  4819.2  381.18
  4829.2  380.18  4879.2  378.21  4919.2  376.98  4971.6  376.79  4987.2  376.47
  4987.5  375.97  4991.0  375.97  4991.2  376.47  5019.3  376.74  5029.3  376.64
  5039.3  377.34  5049.3  377.12  5079.4  377.00  5092.1  378.26  5099.5  378.99
  5109.5  378.96  5117.6  379.83  5122.6  380.06  5129.5  380.78  5133.6  380.78
  5139.6  380.78  5159.6  382.38  5169.6  382.45  5179.7  383.20  5204.6  382.82
#Mann=6,-1,0
  4720.8    0.05       0  4971.6   0.035       0  4987.2    0.05       0
  4991.2   0.035       0  5092.1   0.035       0  5133.6    0.05       0
Bank Sta=4987.2,4991.2
Exp/Cntr=0.3,0.1

Type RM Length L Ch R = 1,11074,190,190,190
BEGIN DESCRIPTION:
North Twin Creek Trib K11074.45
END DESCRIPTION:
XS GIS Cut Line= 3
      2710532.41      6819139.73      2710272.88      6819158.48
      2710039.96      6819167.37
#Sta/Elev= 30
  4743.3  382.24  4771.7  382.13  4778.2  382.13  4809.9  381.16  4819.9  380.59
  4827.6  379.80  4832.6  380.16  4850.0  378.37  4900.1  375.16  4930.2  374.16
  4950.3  374.10  4957.6  374.33  4960.3  374.41  4965.2  374.04  4965.5  373.54
  4969.0  373.54  4969.2  374.04  4972.2  374.37  5003.5  374.42  5020.4  374.87
  5040.4  374.56  5060.4  375.08  5090.5  374.97  5110.5  375.97  5120.5  377.15
  5136.7  377.66  5170.5  378.32  5180.5  379.04  5230.6  380.43  5236.6  380.86
#Mann=7,-1,0
  4743.3    0.05       0  4771.7   0.035       0  4778.2    0.05       0
  4957.6   0.035       0  4965.2   0.035       0  4969.2   0.035       0
  5136.7    0.05       0
Bank Sta=4965.2,4969.2
Exp/Cntr=0.3,0.1

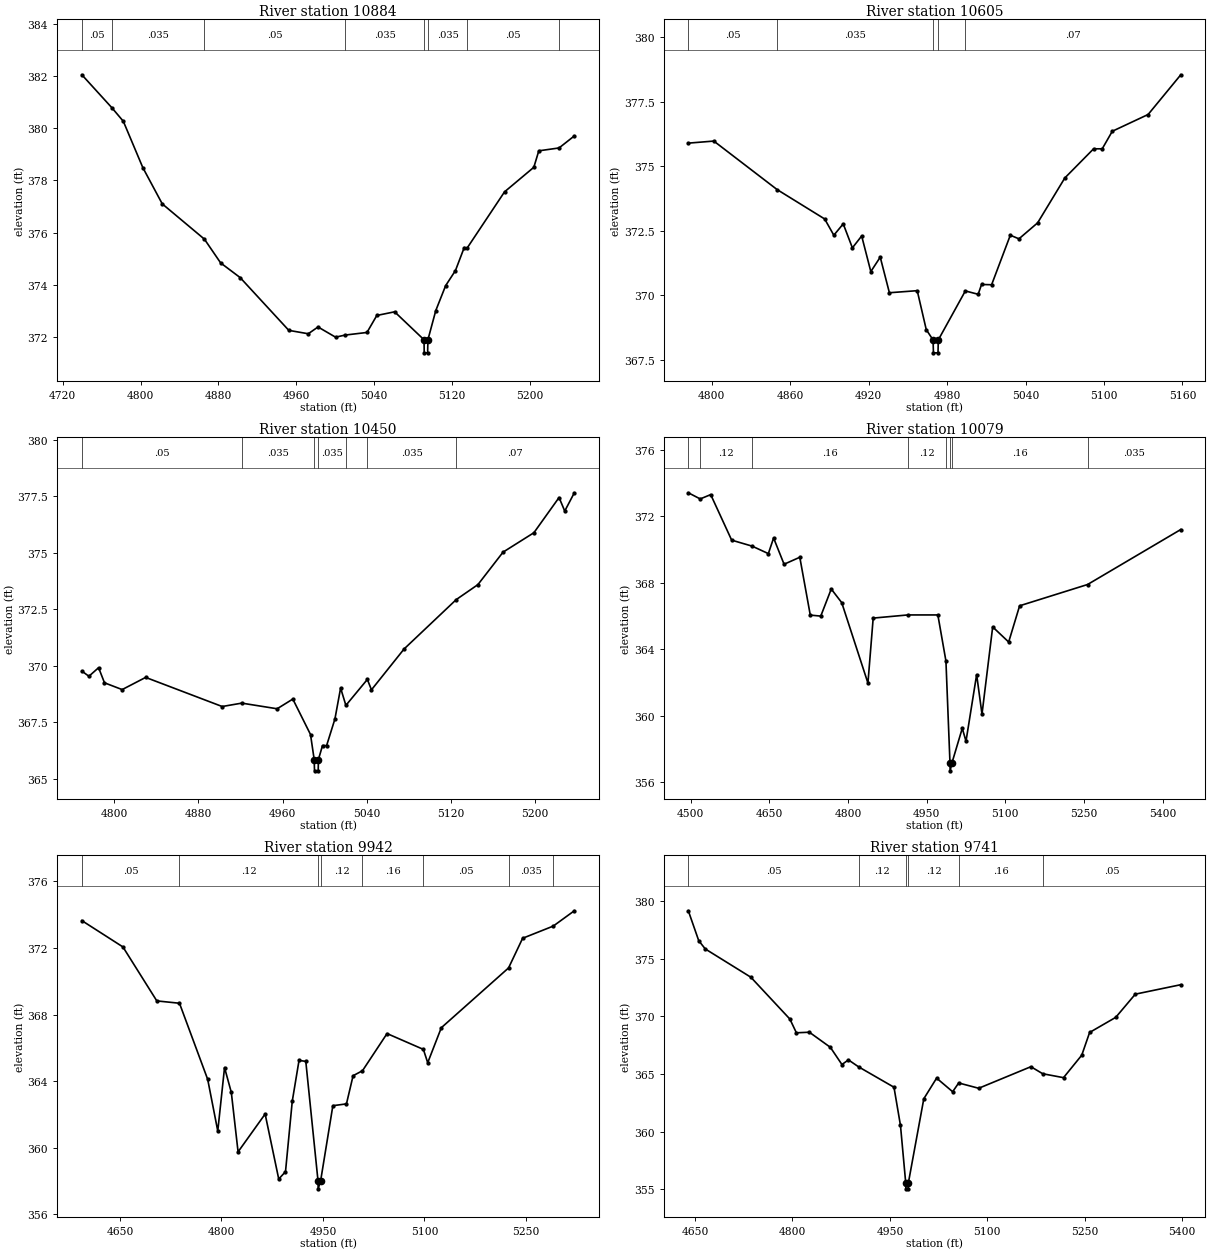
Type RM Length L Ch R = 1,10884,279,279,279
BEGIN DESCRIPTION:
North Twin Creek Trib K10883.59
END DESCRIPTION:
XS GIS Cut Line= 3
      2710538.58      6818964.54      2710275.04      6818967.60
      2710035.03      6819001.08
#Sta/Elev= 30
  4739.7  382.04  4770.5  380.78  4782.3  380.26  4802.3  378.49  4822.3  377.10
  4865.6  375.75  4882.3  374.84  4902.3  374.28  4952.3  372.26  4972.3  372.13
  4982.3  372.39  5000.3  372.00  5010.2  372.08  5032.6  372.18  5042.7  372.83
  5061.0  372.97  5091.2  371.90  5091.4  371.40  5094.9  371.40  5095.2  371.90
  5103.3  373.02  5113.4  373.97  5123.5  374.55  5132.5  375.43  5135.5  375.41
  5173.9  377.56  5204.0  378.50  5209.1  379.13  5229.9  379.24  5245.6  379.70
#Mann=8,-1,0
  4739.7    0.05       0  4770.5   0.035       0  4865.6    0.05       0
  5010.2   0.035       0  5091.2    0.05       0  5095.2   0.035       0
  5135.5    0.05       0  5229.9    0.07       0
Bank Sta=5091.2,5095.2
Exp/Cntr=0.3,0.1

Type RM Length L Ch R = 1,10605,155,155,155
BEGIN DESCRIPTION:
North Twin Creek Trib K10604.93
END DESCRIPTION:
XS GIS Cut Line= 3
      2710295.75      6818673.26      2710141.10      6818832.06
      2710040.62      6818950.13
#Sta/Elev= 30
  4782.0  375.89  4801.5  375.97  4849.9  374.09  4886.3  372.95  4893.3  372.32
  4900.5  372.76  4907.5  371.83  4914.6  372.29  4921.6  370.91  4928.8  371.47
  4935.8  370.09  4957.1  370.17  4964.0  368.66  4969.2  368.26  4969.5  367.76
  4973.0  367.76  4973.2  368.26  4993.9  370.16  5003.7  370.03  5006.3  370.41
  5014.0  370.40  5028.3  372.32  5034.9  372.18  5049.2  372.80  5070.0  374.54
  5092.0  375.67  5098.6  375.67  5106.3  376.35  5133.7  377.00  5158.7  378.54
#Mann=5,-1,0
  4782.0    0.05       0  4849.9   0.035       0  4969.2    0.07       0
  4973.2   0.035       0  4993.9    0.07       0
Bank Sta=4969.2,4973.2
Exp/Cntr=0.3,0.1

Type RM Length L Ch R = 1,10450,371,371,371
BEGIN DESCRIPTION:
North Twin Creek Trib K10449.93
END DESCRIPTION:
XS GIS Cut Line= 3
      2710169.74      6818495.05      2710065.77      6818703.05
      2709975.91      6818920.48
#Sta/Elev= 30
  4769.3  369.76  4776.0  369.53  4785.2  369.91  4790.8  369.24  4807.6  368.94
  4829.9  369.48  4902.6  368.19  4921.2  368.34  4954.8  368.09  4969.7  368.52
  4986.5  366.95  4990.0  365.84  4990.3  365.34  4993.8  365.34  4994.0  365.84
  4997.9  366.46  5001.8  366.46  5009.7  367.64  5015.1  369.01  5020.1  368.24
  5040.5  369.39  5044.4  368.93  5075.4  370.74  5125.0  372.93  5145.5  373.59
  5169.4  375.03  5198.7  375.89  5222.6  377.45  5228.0  376.85  5237.1  377.66
#Mann=7,-1,0
  4769.3    0.05       0  4921.2   0.035       0  4990.0   0.035       0
  4994.0   0.035       0  5020.1    0.07       0  5040.5   0.035       0
  5125.0    0.07       0
Bank Sta=4990,4994
Exp/Cntr=0.3,0.1

Type RM Length L Ch R = 1,10079,137,137,137
BEGIN DESCRIPTION:
North Twin Creek Trib K10079.223
END DESCRIPTION:
XS GIS Cut Line= 3
      2710478.66      6818360.14      2709974.00      6818366.37
      2709892.53      6818793.57
#Sta/Elev= 30
  4495.3  373.41  4518.0  373.04  4538.0  373.30  4578.0  370.56  4617.0  370.20
  4648.0  369.75  4658.0  370.69  4678.0  369.11  4708.0  369.53  4728.0  366.05
  4748.0  365.99  4768.0  367.62  4788.0  366.80  4838.0  361.96  4848.0  365.87
  4914.1  366.06  4971.4  366.06  4986.8  363.29  4994.5  357.18  4994.8  356.68
  4998.5  357.18  5018.0  359.24  5025.1  358.46  5045.4  362.47  5055.6  360.09
  5076.0  365.34  5106.5  364.43  5127.4  366.61  5257.0  367.89  5434.9  371.20
#Mann=8,-1,0
  4495.3    0.05       0  4518.0    0.12       0  4617.0    0.16       0
  4914.1    0.12       0  4986.8    0.16       0  4994.5    0.07       0
  4998.5    0.16       0  5257.0   0.035       0
Bank Sta=4994.5,4998.5
Exp/Cntr=0.3,0.1

Type RM Length L Ch R = 1,9942,201,201,201
BEGIN DESCRIPTION:
North Twin Creek Trib K9941.87
END DESCRIPTION:
XS GIS Cut Line= 3
      2710376.68      6818284.23      2709971.39      6818266.30
      2709649.67      6818248.60
#Sta/Elev= 30
  4593.7  373.64  4654.4  372.06  4704.5  368.82  4738.0  368.68  4779.7  364.11
  4794.6  361.01  4804.6  364.82  4814.6  363.33  4824.6  359.76  4864.6  362.03
  4884.7  358.13  4894.7  358.57  4904.7  362.80  4914.7  365.25  4924.7  365.19
  4942.7  358.04  4943.0  357.54  4946.7  358.04  4964.7  362.53  4984.8  362.64
  4994.6  364.33  5008.5  364.63  5044.8  366.86  5098.5  365.91  5104.9  365.11
  5125.0  367.21  5224.4  370.80  5245.2  372.58  5290.4  373.31  5321.6  374.23
#Mann=8,-1,0
  4593.7    0.05       0  4738.0    0.12       0  4942.7    0.07       0
  4946.7    0.12       0  5008.5    0.16       0  5098.5    0.05       0
  5224.4   0.035       0  5290.4    0.05       0
Bank Sta=4942.7,4946.7
Exp/Cntr=0.3,0.1

Type RM Length L Ch R = 1,9741,290,290,290
BEGIN DESCRIPTION:
North Twin Creek Trib K9741.32
END DESCRIPTION:
XS GIS Cut Line= 3
      2710442.02      6818128.13      2710079.39      6818107.72
      2709686.25      6818072.76
#Sta/Elev= 30
  4639.8  379.14  4655.8  376.55  4665.9  375.83  4736.0  373.38  4796.1  369.75
  4806.1  368.56  4826.1  368.61  4858.4  367.30  4876.2  365.81  4886.2  366.21
  4901.8  365.61  4956.3  363.84  4966.3  360.53  4974.4  355.53  4974.6  355.03
  4978.1  355.03  4978.4  355.53  5002.2  362.84  5021.9  364.63  5046.6  363.45
  5055.9  364.21  5086.7  363.75  5167.0  365.62  5185.2  365.01  5217.2  364.67
  5245.3  366.62  5257.4  368.59  5297.6  369.90  5327.7  371.91  5397.7  372.73
#Mann=6,-1,0
  4639.8    0.05       0  4901.8    0.12       0  4974.4    0.07       0
  4978.4    0.12       0  5055.9    0.16       0  5185.2    0.05       0
Bank Sta=4974.4,4978.4
Exp/Cntr=0.3,0.1

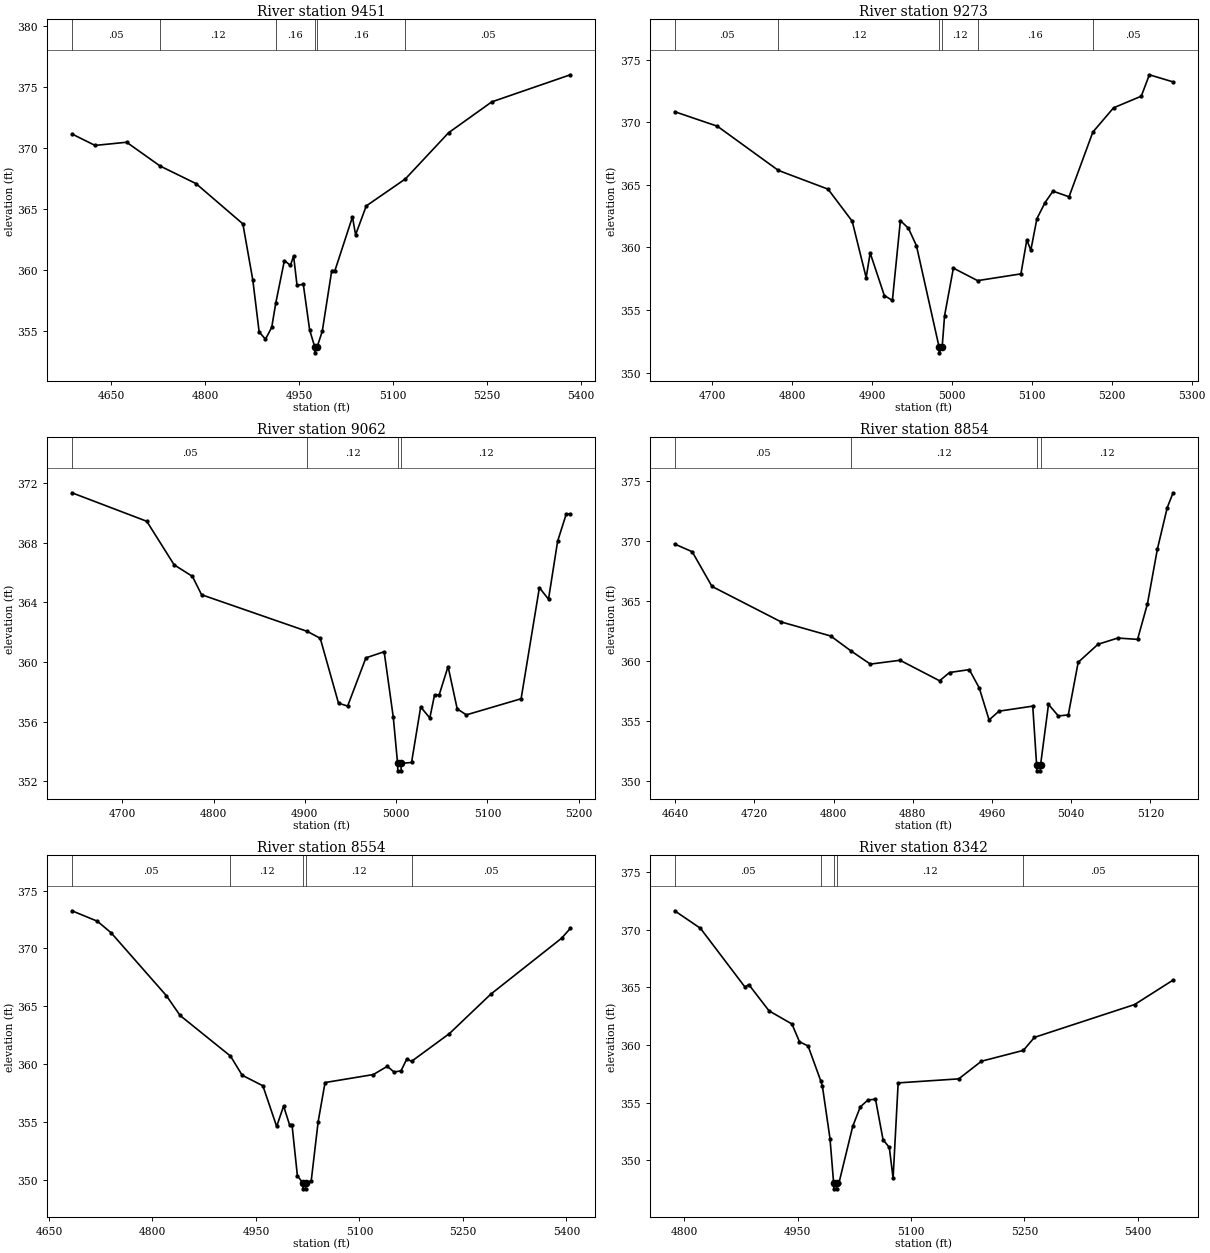
Type RM Length L Ch R = 1,9451,178,178,178
BEGIN DESCRIPTION:
North Twin Creek Trib K9451.37
END DESCRIPTION:
XS GIS Cut Line= 3
      2710452.73      6817979.44      2710040.85      6817928.46
      2709660.86      6817902.47
#Sta/Elev= 30
  4586.8  371.15  4623.8  370.21  4674.2  370.47  4727.7  368.52  4785.0  367.08
  4859.8  363.78  4875.7  359.17  4885.8  354.92  4895.9  354.33  4905.9  355.30
  4912.3  357.28  4926.1  360.77  4935.8  360.38  4940.8  361.15  4946.3  358.74
  4956.3  358.83  4966.4  355.09  4974.5  353.71  4974.7  353.21  4978.5  353.71
  4986.6  354.98  5001.7  359.95  5006.8  359.95  5034.8  364.35  5039.8  362.88
  5056.8  365.25  5119.2  367.46  5188.3  371.25  5257.3  373.78  5382.7  376.00
#Mann=6,-1,0
  4586.8    0.05       0  4727.7    0.12       0  4912.3    0.16       0
  4974.5    0.07       0  4978.5    0.16       0  5119.2    0.05       0
Bank Sta=4974.5,4978.5
Exp/Cntr=0.3,0.1

Type RM Length L Ch R = 1,9273,211,211,211
BEGIN DESCRIPTION:
North Twin Creek Trib K9273.19
END DESCRIPTION:
XS GIS Cut Line= 3
      2710446.88      6817821.29      2710099.26      6817784.76
      2709826.40      6817759.04
#Sta/Elev= 30
  4653.2  370.85  4706.6  369.69  4782.9  366.16  4845.1  364.66  4875.3  362.10
  4892.8  357.59  4897.8  359.56  4915.5  356.16  4925.6  355.77  4935.6  362.15
  4945.7  361.53  4955.7  360.14  4983.9  352.08  4984.1  351.58  4987.9  352.08
  4990.9  354.55  5001.9  358.35  5032.2  357.35  5086.4  357.89  5093.8  360.60
  5098.8  359.78  5106.4  362.30  5116.5  363.58  5126.5  364.50  5146.6  364.05
  5176.4  369.22  5202.3  371.16  5237.0  372.09  5247.1  373.80  5276.8  373.23
#Mann=6,-1,0
  4653.2    0.05       0  4782.9    0.12       0  4983.9    0.07       0
  4987.9    0.12       0  5032.2    0.16       0  5176.4    0.05       0
Bank Sta=4983.9,4987.9
Exp/Cntr=0.3,0.1

Type RM Length L Ch R = 1,9062,208,208,208
BEGIN DESCRIPTION:
North Twin Creek Trib K9062.34
END DESCRIPTION:
XS GIS Cut Line= 3
      2710477.97      6817615.49      2710117.48      6817615.04
      2709932.14      6817619.89
#Sta/Elev= 30
  4644.9  371.34  4726.9  369.43  4756.9  366.51  4776.9  365.74  4786.9  364.51
  4902.8  362.05  4916.9  361.59  4936.9  357.24  4946.9  357.05  4966.9  360.28
  4986.9  360.69  4996.9  356.30  5001.6  353.21  5001.9  352.71  5005.4  352.71
  5005.6  353.21  5016.9  353.27  5026.9  356.99  5036.9  356.25  5042.1  357.80
  5047.1  357.79  5056.9  359.70  5066.9  356.86  5076.9  356.46  5136.9  357.54
  5156.9  364.98  5166.9  364.21  5176.9  368.10  5186.4  369.93  5190.8  369.93
#Mann=4,-1,0
  4644.9    0.05       0  4902.8    0.12       0  5001.6    0.07       0
  5005.6    0.12       0
Bank Sta=5001.6,5005.6
Exp/Cntr=0.3,0.1

Type RM Length L Ch R = 1,8854,300,300,300
BEGIN DESCRIPTION:
North Twin Creek Trib K8853.58
END DESCRIPTION:
XS GIS Cut Line= 3
      2710433.66      6817449.09      2710071.90      6817454.67
      2709930.10      6817454.87
#Sta/Elev= 30
  4639.4  369.74  4657.1  369.10  4677.1  366.21  4747.1  363.25  4797.1  362.08
  4817.3  360.85  4837.1  359.74  4867.1  360.06  4907.1  358.35  4917.1  359.04
  4937.1  359.28  4947.1  357.76  4957.1  355.09  4967.1  355.82  5001.2  356.24
  5005.1  351.35  5005.3  350.85  5008.8  350.85  5009.1  351.35  5017.1  356.38
  5027.1  355.42  5037.1  355.51  5047.1  359.89  5067.1  361.39  5087.1  361.91
  5107.1  361.80  5117.1  364.77  5127.1  369.31  5137.1  372.78  5143.0  374.01
#Mann=4,-1,0
  4639.4    0.05       0  4817.3    0.12       0  5005.1    0.07       0
  5009.1    0.12       0
Bank Sta=5005.1,5009.1
Exp/Cntr=0.3,0.1

Type RM Length L Ch R = 1,8554,212,212,212
BEGIN DESCRIPTION:
North Twin Creek Trib K8554.2
END DESCRIPTION:
XS GIS Cut Line= 3
      2710542.80      6817242.04      2710223.86      6817238.21
      2709820.85      6817256.69
#Sta/Elev= 30
  4683.2  373.25  4720.0  372.35  4740.0  371.35  4820.0  365.92  4840.0  364.20
  4913.0  360.69  4930.0  359.03  4960.0  358.12  4980.0  354.60  4990.0  356.37
  4998.6  354.76  5002.2  354.76  5010.0  350.35  5018.0  349.71  5018.3  349.21
  5021.8  349.21  5022.0  349.71  5030.1  349.92  5040.1  355.01  5050.1  358.40
  5120.1  359.09  5140.2  359.80  5150.2  359.31  5160.2  359.41  5168.7  360.45
  5175.4  360.23  5230.3  362.63  5290.3  366.04  5393.0  370.88  5405.6  371.73
#Mann=5,-1,0
  4683.2    0.05       0  4913.0    0.12       0  5018.0    0.07       0
  5022.0    0.12       0  5175.4    0.05       0
Bank Sta=5018,5022
Exp/Cntr=0.3,0.1

Type RM Length L Ch R = 1,8342,215,215,215
BEGIN DESCRIPTION:
North Twin Creek Trib K8341.9
END DESCRIPTION:
XS GIS Cut Line= 3
      2710529.82      6817033.36      2710317.48      6817061.41
      2709872.84      6817089.34
#Sta/Elev= 30
  4787.0  371.64  4821.1  370.12  4880.1  365.02  4885.1  365.24  4911.9  362.96
  4942.2  361.82  4952.2  360.28  4963.6  359.91  4980.6  356.84  4982.5  356.44
  4992.6  351.87  4997.4  348.02  4997.7  347.52  5001.2  347.52  5001.4  348.02
  5004.4  348.02  5022.7  352.95  5032.7  354.63  5042.7  355.22  5052.8  355.30
  5062.8  351.78  5071.1  351.11  5076.1  348.44  5082.8  356.71  5163.0  357.06
  5193.0  358.59  5248.5  359.53  5263.2  360.66  5395.9  363.51  5446.7  365.63
#Mann=5,-1,0
  4787.0    0.05       0  4980.6    0.12       0  4997.4    0.07       0
  5001.4    0.12       0  5248.5    0.05       0
Bank Sta=4997.4,5001.4
Exp/Cntr=0.3,0.1

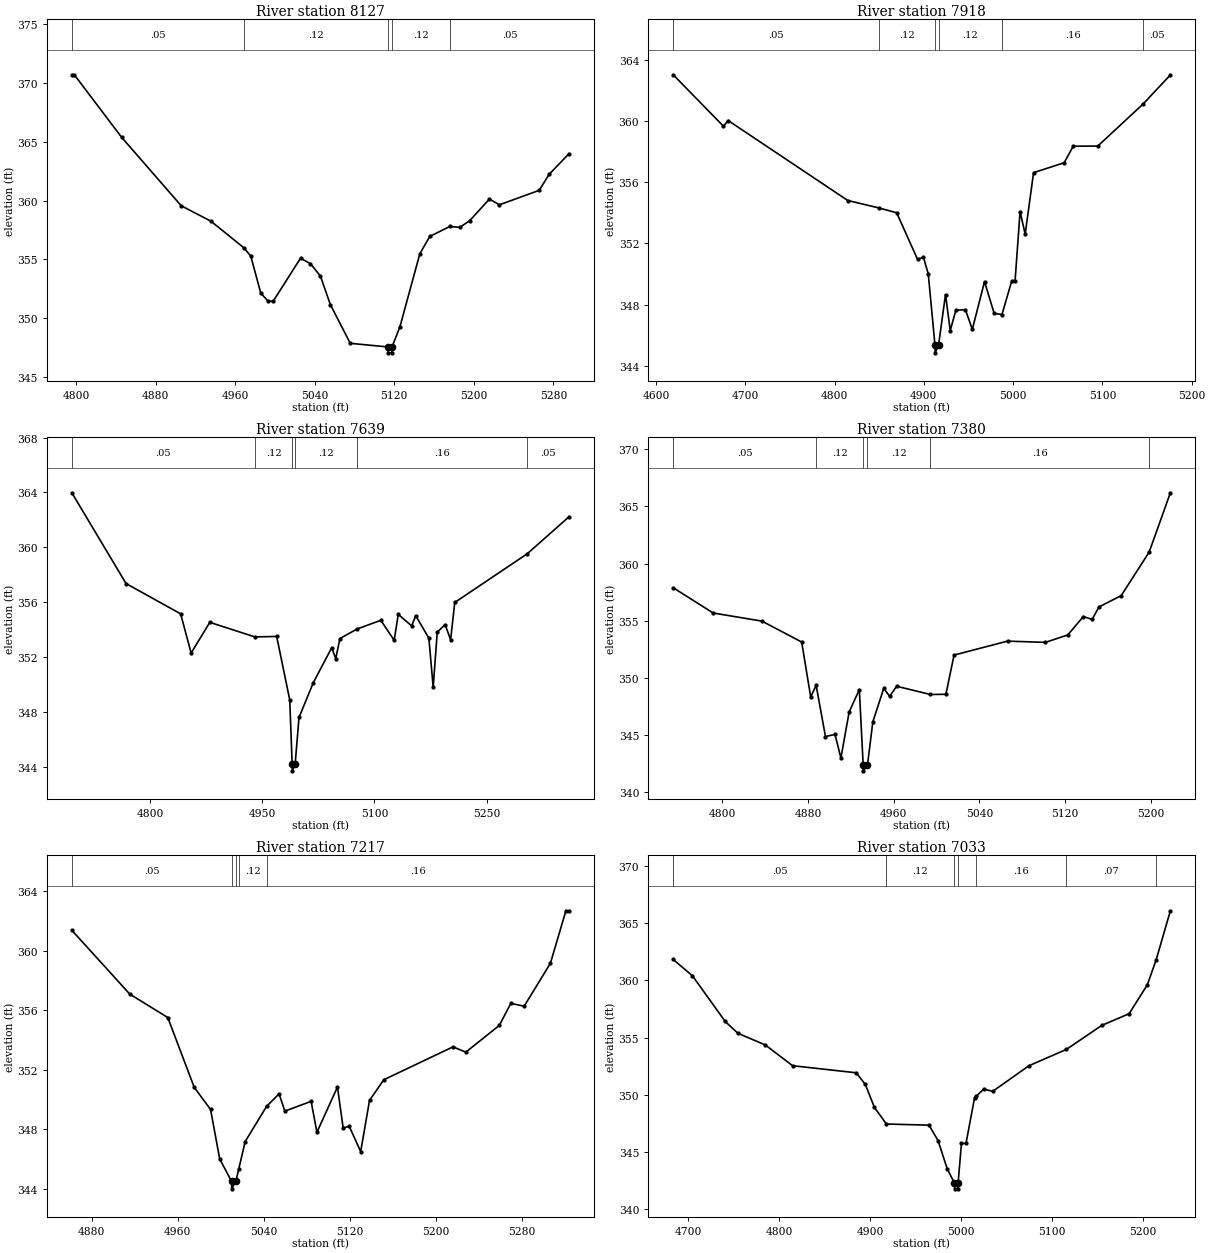
Type RM Length L Ch R = 1,8127,209,209,209
BEGIN DESCRIPTION:
North Twin Creek Trib K8126.928
END DESCRIPTION:
XS GIS Cut Line= 3
      2710476.04      6816861.00      2710276.00      6816861.00
      2709976.04      6816861.00
#Sta/Elev= 30
  4795.7  370.70  4798.2  370.70  4845.7  365.39  4905.7  359.56  4935.7  358.24
  4968.9  355.97  4975.7  355.27  4985.7  352.13  4993.2  351.44  4998.2  351.44
  5025.7  355.10  5035.7  354.63  5045.7  353.58  5055.7  351.15  5075.7  347.86
  5113.7  347.55  5114.0  347.05  5117.5  347.05  5117.7  347.55  5125.7  349.28
  5145.7  355.48  5155.7  356.95  5175.9  357.80  5185.7  357.72  5195.7  358.28
  5215.7  360.13  5225.7  359.64  5265.7  360.87  5275.7  362.23  5295.7  363.99
#Mann=5,-1,0
  4795.7    0.05       0  4968.9    0.12       0  5113.7    0.07       0
  5117.7    0.12       0  5175.9    0.05       0
Bank Sta=5113.7,5117.7
Exp/Cntr=0.3,0.1

Type RM Length L Ch R = 1,7918,279,279,279
BEGIN DESCRIPTION:
North Twin Creek Trib K7917.97
END DESCRIPTION:
XS GIS Cut Line= 3
      2710481.45      6816575.09      2710124.05      6816712.36
      2709971.92      6816796.50
#Sta/Elev= 30
  4619.4  363.02  4675.6  359.66  4680.9  360.03  4814.9  354.80  4849.3  354.32
  4869.6  354.00  4893.0  350.95  4899.6  351.09  4905.0  350.00  4912.5  345.34
  4912.7  344.84  4916.5  345.34  4924.3  348.65  4929.6  346.30  4935.9  347.63
  4946.6  347.66  4954.3  346.37  4968.0  349.50  4978.7  347.43  4987.5  347.34
  4998.5  349.55  5002.2  349.55  5007.8  354.08  5013.5  352.60  5022.9  356.62
  5057.2  357.27  5067.3  358.35  5094.8  358.36  5145.4  361.10  5176.1  363.01
#Mann=6,-1,0
  4619.4    0.05       0  4849.3    0.12       0  4912.5    0.07       0
  4916.5    0.12       0  4987.5    0.16       0  5145.4    0.05       0
Bank Sta=4912.5,4916.5
Exp/Cntr=0.3,0.1

Type RM Length L Ch R = 1,7639,259,259,259
BEGIN DESCRIPTION:
North Twin Creek Trib K7638.99
END DESCRIPTION:
XS GIS Cut Line= 4
      2710469.44      6816405.80      2710173.49      6816489.95
      2710082.65      6816524.67      2709977.99      6816762.54
#Sta/Elev= 30
  4695.4  363.97  4767.9  357.35  4840.9  355.14  4854.9  352.28  4879.9  354.52
  4940.0  353.46  4969.3  353.49  4986.8  348.86  4990.0  344.19  4990.2  343.69
  4994.0  344.19  4999.2  347.59  5018.2  350.11  5042.9  352.67  5048.3  351.88
  5053.9  353.34  5077.0  354.04  5108.6  354.67  5126.4  353.21  5131.9  355.10
  5149.8  354.26  5155.2  355.01  5172.8  353.37  5178.6  349.79  5184.0  353.80
  5194.6  354.36  5201.9  353.24  5207.4  355.97  5304.3  359.52  5360.2  362.22
#Mann=6,-1,0
  4695.4    0.05       0  4940.0    0.12       0  4990.0    0.07       0
  4994.0    0.12       0  5077.0    0.16       0  5304.3    0.05       0
Bank Sta=4990,4994
Exp/Cntr=0.3,0.1

Type RM Length L Ch R = 1,7380,163,163,163
BEGIN DESCRIPTION:
North Twin Creek Trib K7380.22
END DESCRIPTION:
XS GIS Cut Line= 3
      2710394.36      6816372.17      2710168.96      6816265.28
      2709998.22      6816135.37
#Sta/Elev= 30
  4754.3  357.89  4791.6  355.68  4837.1  354.97  4874.2  353.14  4882.6  348.34
  4887.7  349.35  4896.4  344.87  4905.3  345.06  4910.8  342.99  4918.5  347.02
  4928.0  348.98  4931.6  342.37  4931.8  341.87  4935.6  342.37  4940.6  346.16
  4950.8  349.09  4956.3  348.39  4962.8  349.27  4994.4  348.55  5008.8  348.57
  5016.4  352.00  5066.3  353.22  5101.7  353.11  5122.5  353.76  5137.1  355.37
  5145.3  355.12  5151.6  356.21  5172.4  357.20  5198.5  361.01  5218.3  366.20
#Mann=6,-1,0
  4754.3    0.05       0  4887.7    0.12       0  4931.6    0.07       0
  4935.6    0.12       0  4994.4    0.16       0  5198.5    0.05       0
Bank Sta=4931.6,4935.6
Exp/Cntr=0.3,0.1

Type RM Length L Ch R = 1,7217,184,184,184
BEGIN DESCRIPTION:
North Twin Creek Trib K7217.33
END DESCRIPTION:
XS GIS Cut Line= 3
      2710446.38      6816267.29      2710315.25      6816216.68
      2710015.64      6816099.43
#Sta/Elev= 30
  4861.6  361.37  4915.5  357.08  4950.8  355.51  4975.4  350.82  4990.6  349.33
  4999.1  346.01  5010.1  344.50  5010.3  344.00  5014.1  344.50  5016.7  345.30
  5022.8  347.18  5042.7  349.54  5054.3  350.38  5059.7  349.22  5084.1  349.88
  5089.5  347.80  5108.6  350.84  5113.9  348.08  5119.5  348.21  5130.2  346.50
  5138.4  349.94  5151.7  351.33  5216.1  353.54  5227.9  353.18  5259.1  354.98
  5269.8  356.46  5282.2  356.27  5306.6  359.15  5321.0  362.68  5323.9  362.68
#Mann=5,-1,0
  4861.6    0.05       0  5010.1    0.05       0  5014.1    0.05       0
  5016.7    0.12       0  5042.7    0.16       0
Bank Sta=5010.1,5014.1
Exp/Cntr=0.3,0.1

Type RM Length L Ch R = 1,7033,121,121,121
BEGIN DESCRIPTION:
North Twin Creek Trib K7032.64
END DESCRIPTION:
XS GIS Cut Line= 3
      2710547.20      6816079.11      2710229.65      6816062.11
      2710000.65      6816050.39
#Sta/Elev= 30
  4683.2  361.83  4704.4  360.40  4740.4  356.41  4754.5  355.37  4784.5  354.36
  4814.6  352.54  4884.7  351.92  4894.7  350.90  4904.7  348.89  4917.9  347.44
  4964.8  347.34  4974.8  345.98  4984.8  343.53  4992.8  342.27  4993.1  341.77
  4996.6  341.77  4996.8  342.27  5000.5  345.74  5005.5  345.74  5014.9  349.72
  5016.9  349.87  5024.9  350.49  5034.9  350.30  5074.9  352.54  5115.9  353.96
  5155.1  356.07  5185.1  357.09  5205.1  359.61  5214.8  361.79  5230.5  366.09
#Mann=7,-1,0
  4683.2    0.05       0  4917.9    0.12       0  4992.8    0.07       0
  4996.8    0.12       0  5016.9    0.16       0  5115.9    0.07       0
  5214.8    0.05       0
Bank Sta=4992.8,4996.8
Exp/Cntr=0.3,0.1