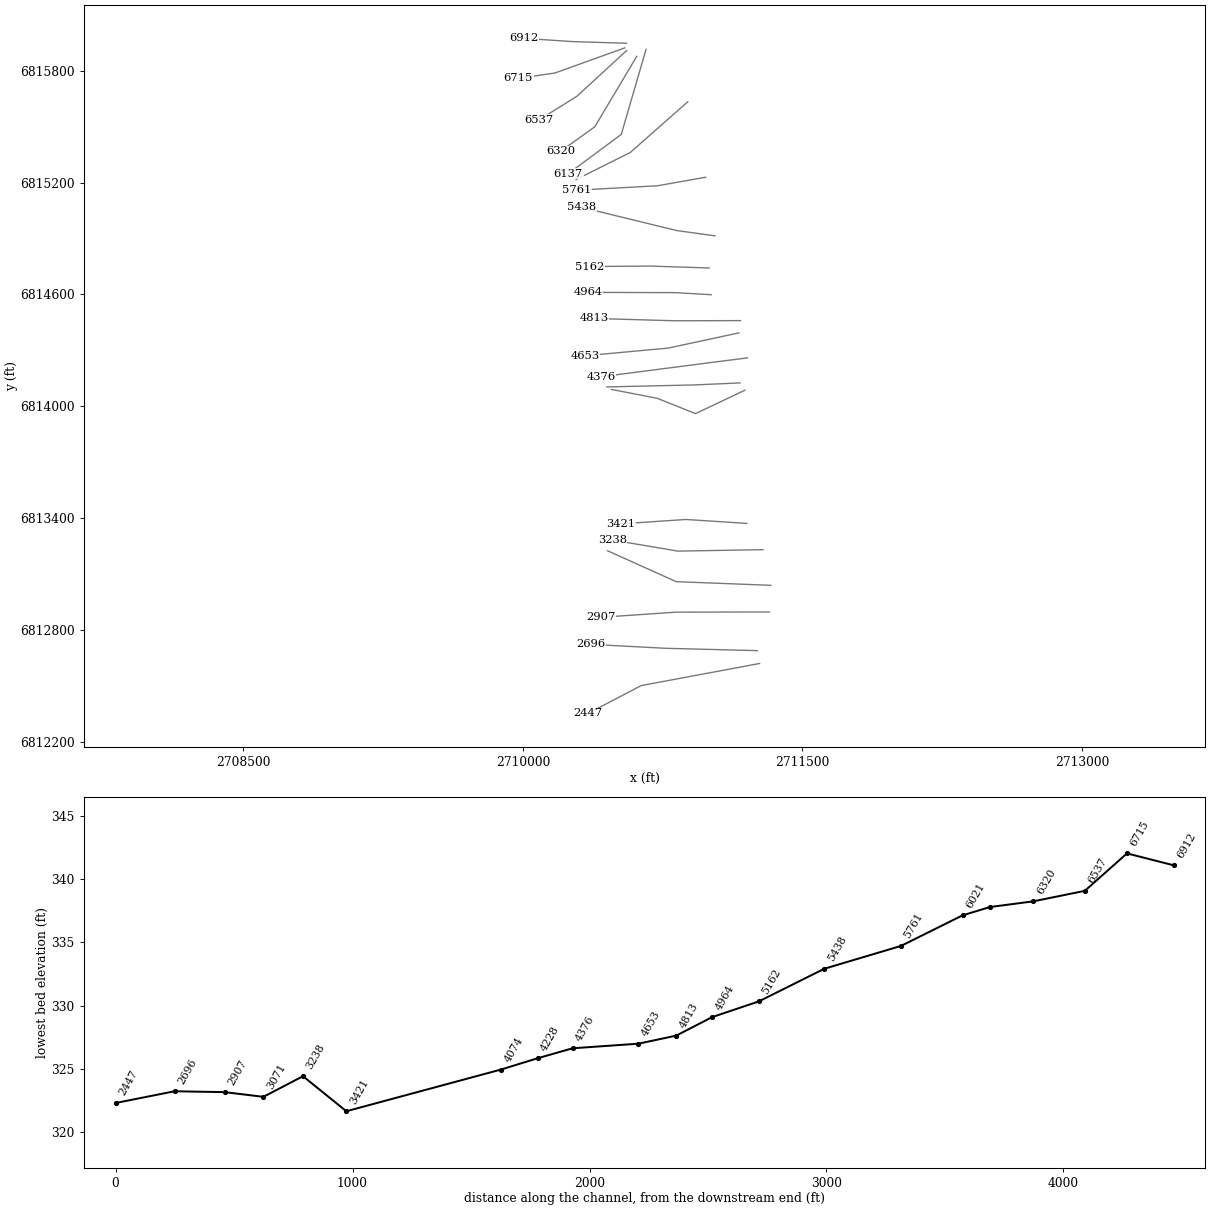
HEC-RAS study North Twin Creek Trib K.prj: North Twin Creek Trib K Base Level Engineering

--- North Twin Creek Trib K.g01 (geometry) --- (continued)

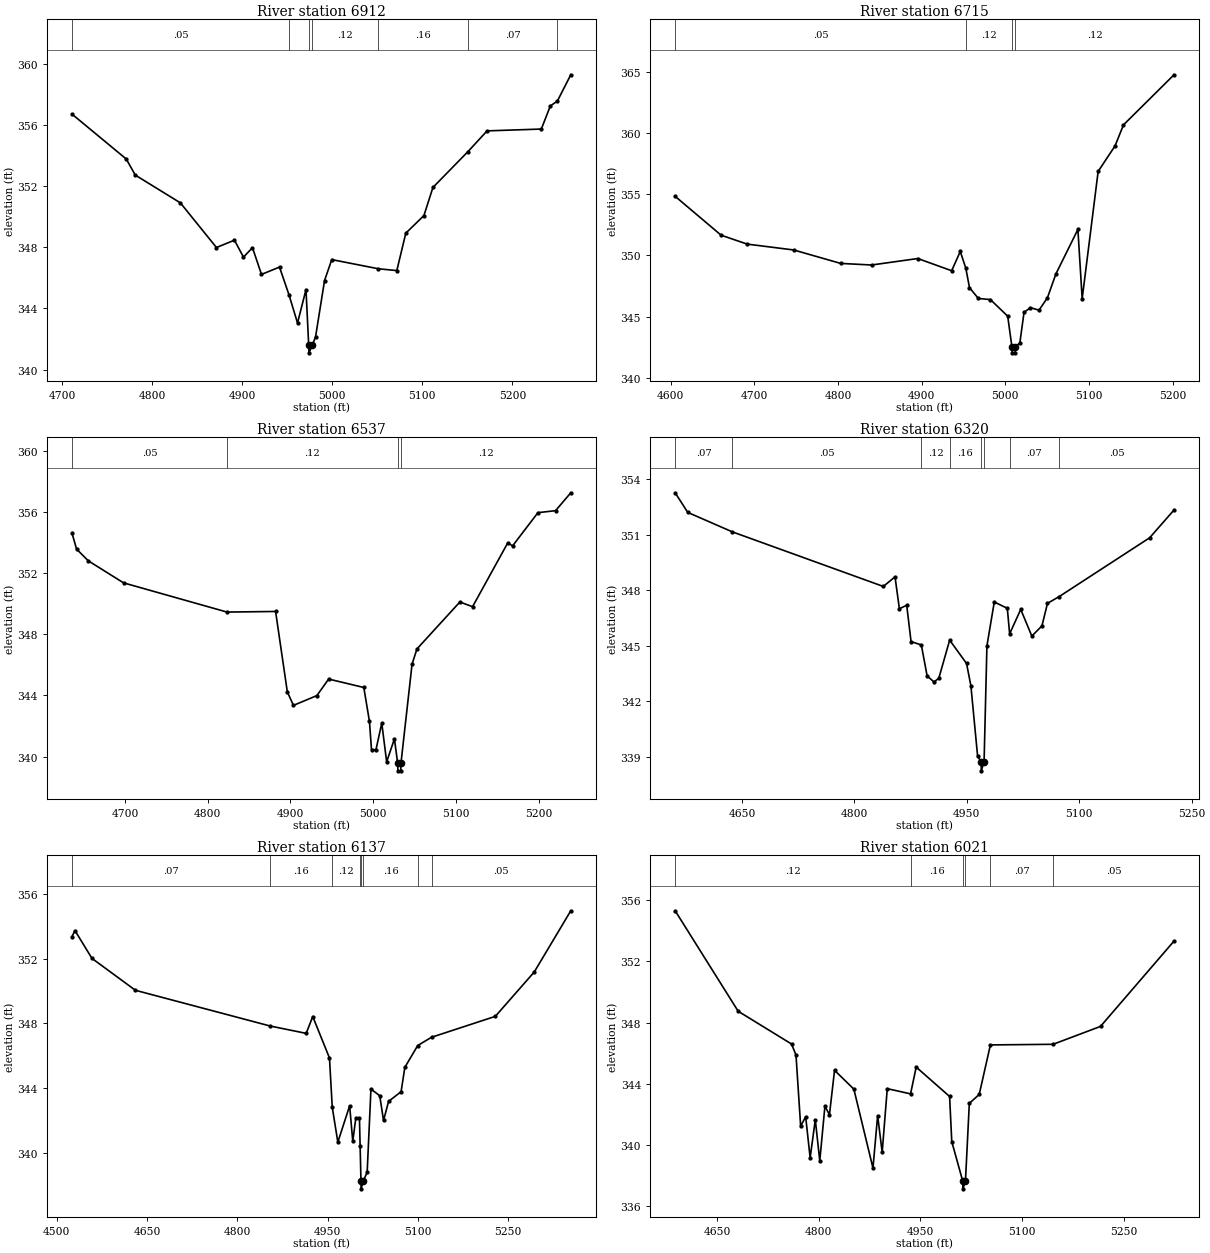
Type RM Length L Ch R = 1,6912,197,197,197
BEGIN DESCRIPTION:
North Twin Creek Trib K6912.09
END DESCRIPTION:
XS GIS Cut Line= 3
      2710556.31      6815947.91      2710265.05      6815956.83
      2710003.32      6815974.23
#Sta/Elev= 30
  4711.1  356.71  4771.4  353.77  4781.4  352.72  4831.5  350.90  4871.5  347.98
  4891.5  348.46  4901.5  347.35  4911.5  347.97  4921.5  346.22  4941.5  346.70
  4952.0  344.89  4961.5  343.04  4970.9  345.23  4973.9  341.59  4974.2  341.09
  4977.9  341.59  4981.5  342.13  4991.5  345.82  4999.5  347.19  5051.2  346.59
  5071.7  346.47  5081.7  348.92  5101.8  350.07  5111.8  351.91  5150.6  354.25
  5171.9  355.61  5232.1  355.73  5242.1  357.24  5249.9  357.56  5264.8  359.28
#Mann=7,-1,0
  4711.1    0.05       0  4952.0    0.12       0  4973.9    0.07       0
  4977.9    0.12       0  5051.2    0.16       0  5150.6    0.07       0
  5249.9    0.05       0
Bank Sta=4973.9,4977.9
Exp/Cntr=0.3,0.1

Type RM Length L Ch R = 1,6715,178,178,178
BEGIN DESCRIPTION:
North Twin Creek Trib K6714.99
END DESCRIPTION:
XS GIS Cut Line= 3
      2710546.99      6815923.01      2710172.98      6815788.48
      2709976.30      6815759.31
#Sta/Elev= 30
  4605.3  354.84  4660.2  351.66  4691.4  350.93  4747.0  350.45  4803.1  349.35
  4840.1  349.22  4895.3  349.75  4935.8  348.75  4946.1  350.33  4952.7  348.96
  4957.1  347.37  4967.7  346.48  4982.1  346.39  5002.8  345.03  5007.8  342.53
  5008.1  342.03  5011.6  342.03  5011.8  342.53  5017.3  342.84  5022.3  345.34
  5030.0  345.73  5040.2  345.52  5050.3  346.54  5060.4  348.49  5086.7  352.13
  5091.8  346.46  5110.9  356.88  5131.1  358.97  5141.2  360.69  5201.6  364.79
#Mann=4,-1,0
  4605.3    0.05       0  4952.7    0.12       0  5007.8    0.07       0
  5011.8    0.12       0
Bank Sta=5007.8,5011.8
Exp/Cntr=0.3,0.1

Type RM Length L Ch R = 1,6537,217,217,217
BEGIN DESCRIPTION:
North Twin Creek Trib K6537.11
END DESCRIPTION:
XS GIS Cut Line= 3
      2710556.54      6815908.54      2710290.14      6815663.44
      2710085.89      6815535.89
#Sta/Elev= 30
  4635.9  354.63  4641.5  353.57  4655.7  352.80  4698.3  351.36  4823.3  349.45
  4882.0  349.49  4896.2  344.23  4903.6  343.35  4931.9  343.99  4946.1  345.07
  4988.6  344.52  4995.4  342.31  4997.9  340.45  5003.3  340.45  5010.3  342.19
  5016.2  339.66  5025.6  341.16  5029.5  339.57  5029.8  339.07  5033.3  339.07
  5033.5  339.57  5046.9  346.04  5052.8  347.04  5104.7  350.11  5120.0  349.80
  5162.5  353.97  5168.4  353.78  5199.0  355.95  5220.3  356.08  5238.7  357.25
#Mann=4,-1,0
  4635.9    0.05       0  4823.3    0.12       0  5029.5    0.07       0
  5033.5    0.12       0
Bank Sta=5029.5,5033.5
Exp/Cntr=0.3,0.1

Type RM Length L Ch R = 1,6320,183,183,183
BEGIN DESCRIPTION:
North Twin Creek Trib K6320.02
END DESCRIPTION:
XS GIS Cut Line= 3
      2710611.28      6815877.69      2710386.15      6815499.76
      2710202.82      6815368.29
#Sta/Elev= 30
  4560.9  353.26  4577.7  352.20  4637.1  351.15  4838.6  348.20  4854.2  348.72
  4860.0  347.00  4869.8  347.18  4875.6  345.22  4889.3  345.04  4897.0  343.37
  4906.2  343.04  4912.6  343.24  4927.1  345.30  4949.6  344.04  4955.4  342.84
  4964.4  339.02  4969.0  338.74  4969.3  338.24  4973.0  338.74  4976.8  344.99
  4986.6  347.36  5004.0  347.02  5007.1  345.64  5021.9  346.96  5036.7  345.52
  5050.2  346.07  5057.6  347.29  5073.1  347.65  5193.9  350.83  5226.4  352.33
#Mann=8,-1,0
  4560.9    0.07       0  4637.1    0.05       0  4889.3    0.12       0
  4927.1    0.16       0  4969.0    0.07       0  4973.0    0.16       0
  5007.1    0.07       0  5073.1    0.05       0
Bank Sta=4969,4973
Exp/Cntr=0.3,0.1

Type RM Length L Ch R = 1,6137,116,116,116
BEGIN DESCRIPTION:
North Twin Creek Trib K6136.7
END DESCRIPTION:
XS GIS Cut Line= 3
      2710661.13      6815915.18      2710528.23      6815458.85
      2710244.16      6815248.44
#Sta/Elev= 30
  4525.3  353.35  4530.3  353.74  4558.6  352.02  4630.8  350.05  4855.1  347.84
  4914.5  347.39  4925.4  348.43  4953.2  345.87  4957.8  342.83  4967.1  340.67
  4986.7  342.92  4991.9  340.73  4996.9  342.14  5003.0  342.14  5004.1  340.45
  5005.5  338.29  5005.7  337.79  5009.5  338.29  5015.8  338.81  5022.1  343.95
  5036.7  343.54  5043.0  342.01  5051.4  343.19  5072.2  343.79  5078.4  345.29
  5099.8  346.64  5122.8  347.15  5228.7  348.44  5293.4  351.18  5354.1  354.96
#Mann=8,-1,0
  4525.3    0.07       0  4855.1    0.16       0  4957.8    0.12       0
  5004.1    0.16       0  5005.5    0.07       0  5009.5    0.16       0
  5099.8    0.07       0  5122.8    0.05       0
Bank Sta=5005.5,5009.5
Exp/Cntr=0.3,0.1

Type RM Length L Ch R = 1,6021,260,260,260
BEGIN DESCRIPTION:
North Twin Creek Trib K6021.47
END DESCRIPTION:
XS GIS Cut Line= 3
      2710884.89      6815633.82      2710576.48      6815361.79
      2710285.77      6815216.59
#Sta/Elev= 30
  4588.2  355.31  4681.2  348.74  4759.9  346.60  4766.5  345.88  4773.4  341.23
  4780.8  341.84  4787.4  339.16  4795.0  341.65  4801.6  338.96  4809.2  342.53
  4815.9  341.98  4823.4  344.88  4851.9  343.65  4880.1  338.49  4887.0  341.92
  4893.7  339.52  4901.2  343.68  4935.6  343.34  4943.9  345.09  4993.2  343.17
  4996.4  340.22  5012.6  337.63  5012.8  337.13  5016.6  337.63  5022.3  342.72
  5036.9  343.30  5053.4  346.54  5145.9  346.58  5215.9  347.75  5324.4  353.33
#Mann=6,-1,0
  4588.2    0.12       0  4935.6    0.16       0  5012.6    0.07       0
  5016.6    0.16       0  5053.4    0.07       0  5145.9    0.05       0
Bank Sta=5012.6,5016.6
Exp/Cntr=0.3,0.1

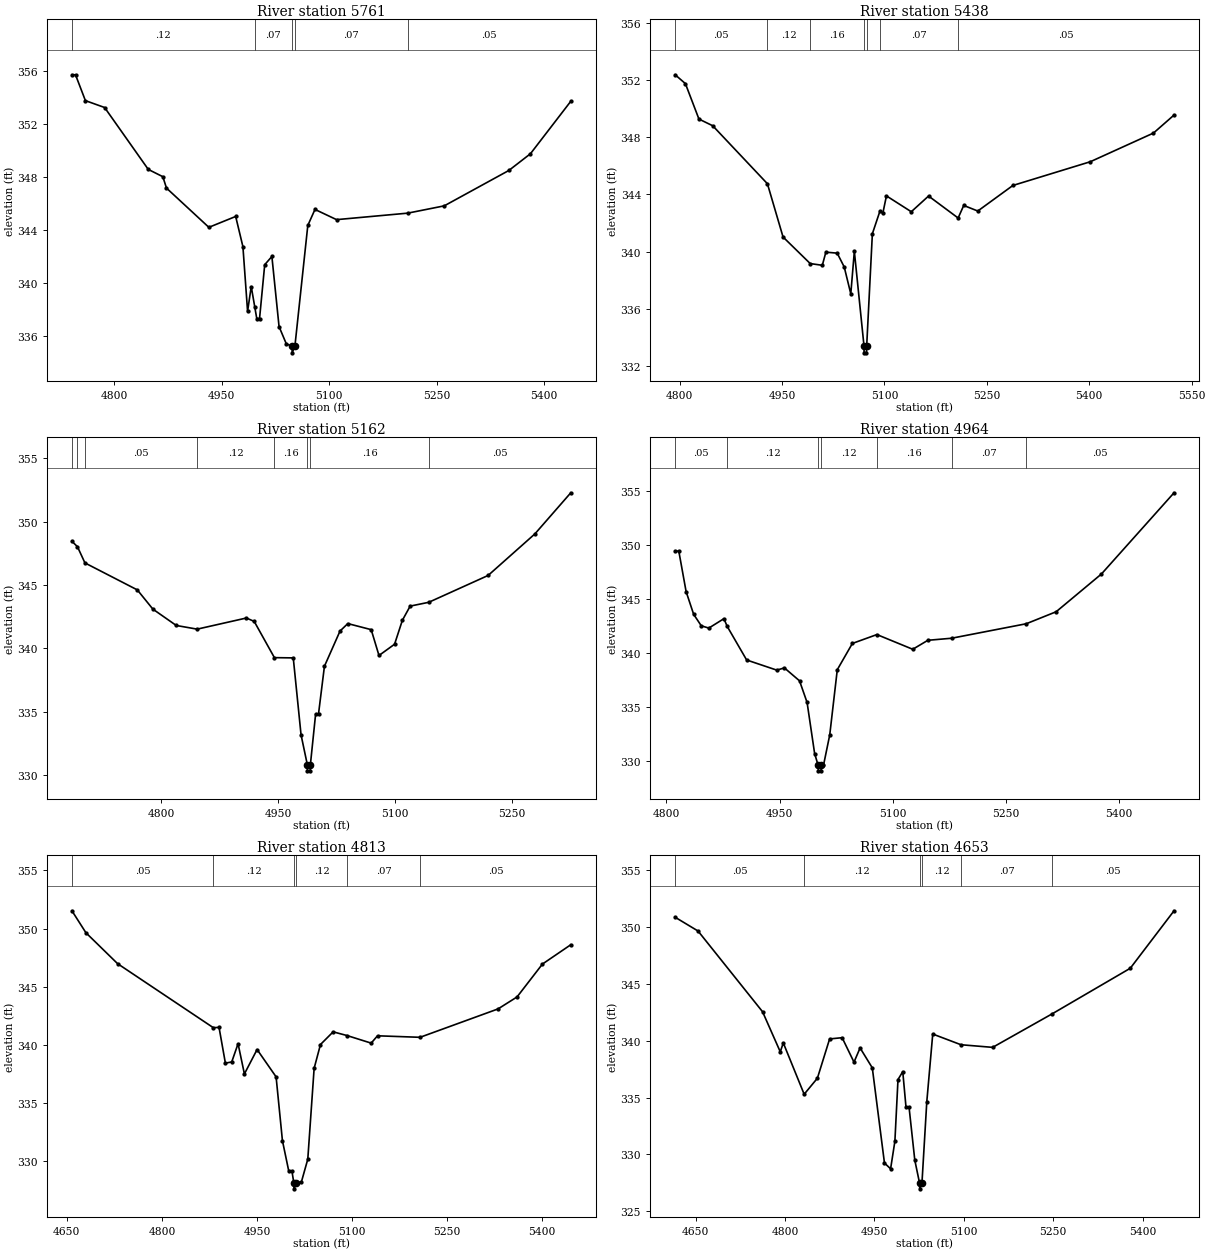
Type RM Length L Ch R = 1,5761,323,323,323
BEGIN DESCRIPTION:
North Twin Creek Trib K5760.9
END DESCRIPTION:
XS GIS Cut Line= 3
      2710980.88      6815229.04      2710723.17      6815183.31
      2710289.75      6815159.58
#Sta/Elev= 30
  4741.2  355.69  4746.2  355.69  4760.0  353.74  4786.8  353.22  4847.7  348.55
  4868.0  348.00  4873.1  347.14  4932.2  344.18  4969.6  345.00  4979.7  342.72
  4986.2  337.84  4991.3  339.71  4996.2  338.18  4999.0  337.30  5002.9  337.30
  5010.1  341.36  5020.1  341.98  5030.1  336.69  5040.2  335.39  5048.2  335.21
  5048.4  334.71  5052.2  335.21  5070.2  344.32  5080.2  345.53  5110.3  344.76
  5209.6  345.25  5260.5  345.80  5350.6  348.47  5380.7  349.73  5437.0  353.69
#Mann=5,-1,0
  4741.2    0.12       0  4996.2    0.07       0  5048.2    0.07       0
  5052.2    0.07       0  5209.6    0.05       0
Bank Sta=5048.2,5052.2
Exp/Cntr=0.3,0.1

Type RM Length L Ch R = 1,5438,276,276,276
BEGIN DESCRIPTION:
North Twin Creek Trib K5438.45
END DESCRIPTION:
XS GIS Cut Line= 3
      2711030.50      6814914.56      2710824.04      6814943.39
      2710316.76      6815067.07
#Sta/Elev= 30
  4793.6  352.38  4808.6  351.76  4828.4  349.28  4848.6  348.81  4928.7  344.75
  4951.6  341.02  4991.4  339.16  5009.1  339.04  5014.3  339.96  5030.9  339.89
  5041.2  338.92  5050.8  337.04  5056.0  340.02  5070.1  333.41  5070.3  332.91
  5073.8  332.91  5074.1  333.41  5082.4  341.25  5093.6  342.85  5097.7  342.68
  5103.0  343.90  5139.4  342.79  5164.7  343.89  5208.0  342.35  5216.2  343.23
  5236.8  342.84  5288.2  344.63  5401.5  346.29  5494.1  348.30  5524.2  349.56
#Mann=7,-1,0
  4793.6    0.05       0  4928.7    0.12       0  4991.4    0.16       0
  5070.1    0.07       0  5074.1    0.16       0  5093.6    0.07       0
  5208.0    0.05       0
Bank Sta=5070.1,5074.1
Exp/Cntr=0.3,0.1

Type RM Length L Ch R = 1,5162,198,198,198
BEGIN DESCRIPTION:
North Twin Creek Trib K5161.84
END DESCRIPTION:
XS GIS Cut Line= 3
      2710999.83      6814742.23      2710683.55      6814752.31
      2710359.89      6814750.08
#Sta/Elev= 30
  4685.5  348.46  4692.6  348.03  4702.2  346.75  4769.4  344.62  4789.4  343.10
  4819.4  341.81  4846.2  341.52  4909.4  342.40  4919.4  342.13  4945.3  339.27
  4969.5  339.25  4979.5  333.17  4987.5  330.83  4987.7  330.33  4991.2  330.33
  4991.5  330.83  4998.2  334.82  5001.9  334.82  5009.5  338.59  5029.5  341.37
  5039.5  341.96  5069.5  341.48  5079.5  339.44  5099.5  340.33  5109.5  342.22
  5119.5  343.34  5143.3  343.64  5219.5  345.76  5279.5  349.04  5325.6  352.29
#Mann=8,-1,0
  4685.5    0.05       0  4692.6    0.12       0  4702.2    0.05       0
  4846.2    0.12       0  4945.3    0.16       0  4987.5    0.07       0
  4991.5    0.16       0  5143.3    0.05       0
Bank Sta=4987.5,4991.5
Exp/Cntr=0.3,0.1

Type RM Length L Ch R = 1,4964,151,151,151
BEGIN DESCRIPTION:
North Twin Creek Trib K4963.7
END DESCRIPTION:
XS GIS Cut Line= 3
      2711010.50      6814598.74      2710817.66      6814609.91
      2710349.82      6814611.30
#Sta/Elev= 30
  4811.6  349.40  4816.4  349.40  4826.1  345.65  4836.1  343.55  4846.2  342.49
  4856.2  342.28  4876.2  343.15  4880.5  342.44  4906.3  339.33  4946.3  338.39
  4956.3  338.60  4976.4  337.40  4986.4  335.40  4996.4  330.67  5001.1  329.58
  5001.3  329.08  5004.8  329.08  5005.1  329.58  5008.1  329.58  5016.4  332.40
  5026.4  338.43  5046.4  340.86  5078.9  341.68  5126.4  340.32  5146.4  341.15
  5177.8  341.34  5276.8  342.68  5316.4  343.79  5376.4  347.28  5472.6  354.79
#Mann=7,-1,0
  4811.6    0.05       0  4880.5    0.12       0  5001.1    0.07       0
  5005.1    0.12       0  5078.9    0.16       0  5177.8    0.07       0
  5276.8    0.05       0
Bank Sta=5001.1,5005.1
Exp/Cntr=0.3,0.1

Type RM Length L Ch R = 1,4813,160,160,160
BEGIN DESCRIPTION:
North Twin Creek Trib K4812.52
END DESCRIPTION:
XS GIS Cut Line= 3
      2711168.09      6814459.90      2710821.13      6814458.88
      2710381.27      6814471.33
#Sta/Elev= 30
  4658.0  351.53  4680.1  349.64  4730.1  346.98  4881.0  341.48  4890.1  341.50
  4900.1  338.43  4910.1  338.53  4920.1  340.10  4930.1  337.50  4950.1  339.60
  4980.1  337.25  4990.1  331.76  5000.0  329.17  5005.0  329.17  5008.1  328.12
  5008.3  327.62  5012.1  328.12  5020.1  328.23  5030.1  330.17  5040.1  337.98
  5050.1  340.03  5070.1  341.12  5092.1  340.80  5130.1  340.15  5140.1  340.78
  5207.2  340.65  5330.2  343.09  5360.2  344.12  5400.3  346.95  5445.0  348.61
#Mann=6,-1,0
  4658.0    0.05       0  4881.0    0.12       0  5008.1    0.07       0
  5012.1    0.12       0  5092.1    0.07       0  5207.2    0.05       0
Bank Sta=5008.1,5012.1
Exp/Cntr=0.3,0.1

Type RM Length L Ch R = 1,4653,277,277,277
BEGIN DESCRIPTION:
North Twin Creek Trib K4652.71
END DESCRIPTION:
XS GIS Cut Line= 3
      2711159.29      6814393.89      2710780.37      6814312.48
      2710332.95      6814271.08
#Sta/Elev= 30
  4615.8  350.84  4654.2  349.63  4762.4  342.54  4792.1  339.02  4797.2  339.80
  4832.2  335.29  4854.4  336.70  4874.9  340.15  4895.9  340.26  4915.8  338.11
  4926.0  339.36  4946.5  337.61  4966.9  329.25  4977.2  328.74  4984.4  331.16
  4989.6  336.58  4997.6  337.28  5003.0  334.18  5008.1  334.18  5017.8  329.50
  5025.8  327.48  5026.1  326.98  5029.8  327.48  5037.9  334.62  5047.9  340.58
  5095.3  339.64  5148.4  339.41  5248.4  342.36  5379.3  346.36  5452.7  351.41
#Mann=6,-1,0
  4615.8    0.05       0  4832.2    0.12       0  5025.8    0.07       0
  5029.8    0.12       0  5095.3    0.07       0  5248.4    0.05       0
Bank Sta=5025.8,5029.8
Exp/Cntr=0.3,0.1

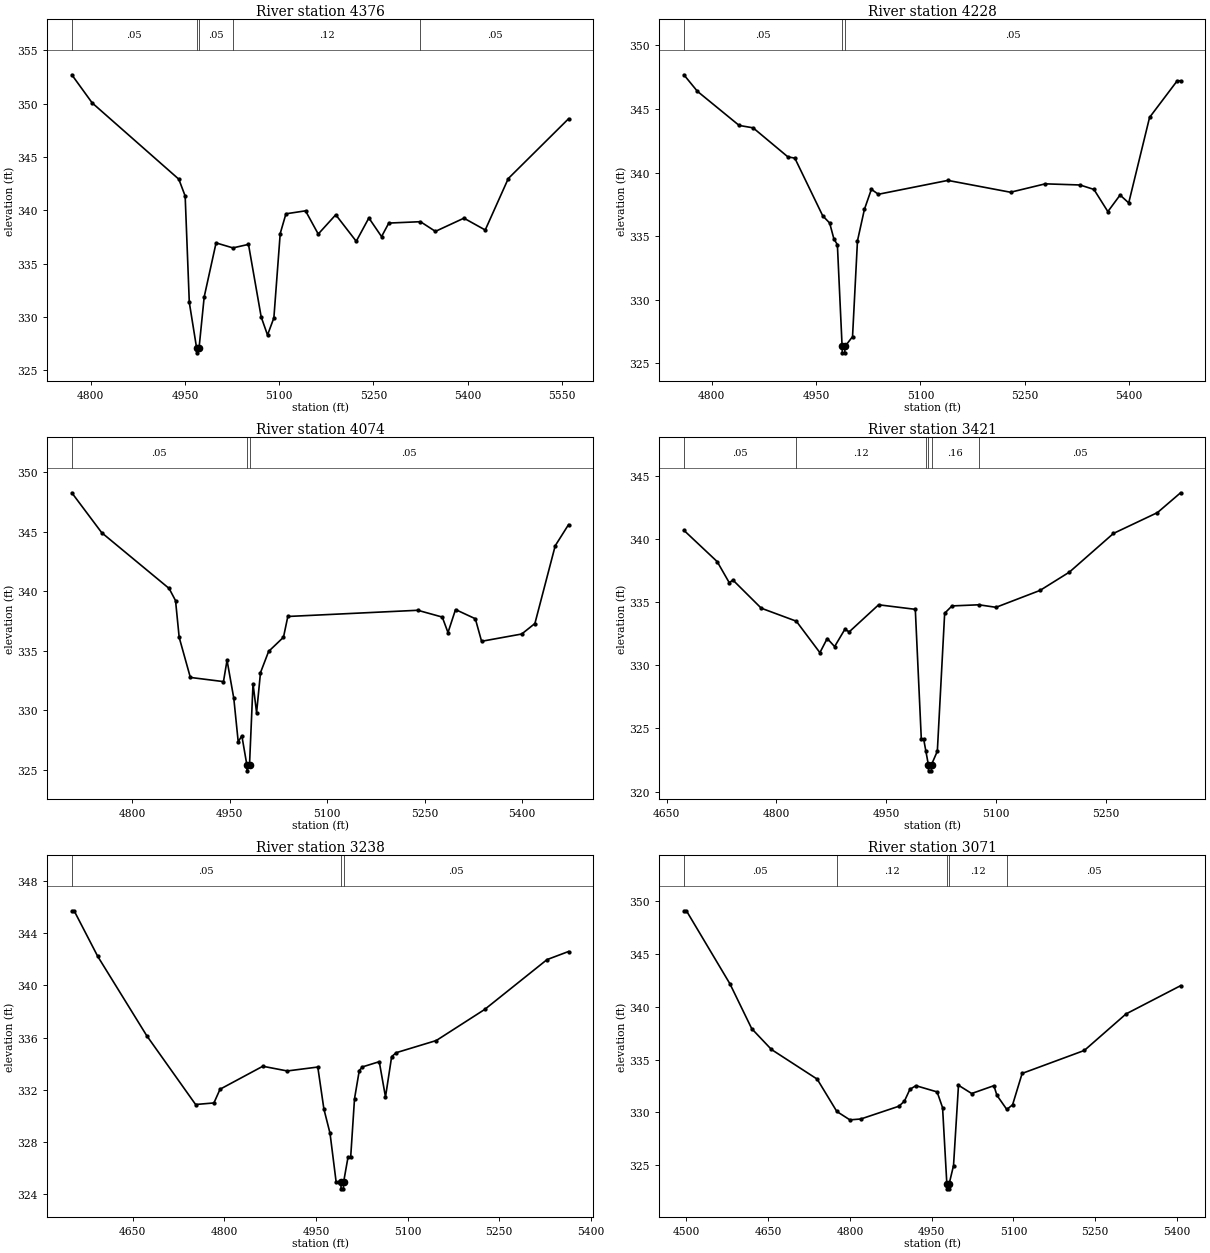
Type RM Length L Ch R = 1,4376,148,148,148
BEGIN DESCRIPTION:
North Twin Creek Trib K4375.59
END DESCRIPTION:
XS GIS Cut Line= 3
      2711204.98      6814259.85      2710973.38      6814230.31
      2710420.86      6814158.80
#Sta/Elev= 30
  4769.9  352.72  4802.3  350.08  4940.2  342.92  4950.3  341.34  4956.9  331.35
  4968.4  327.12  4968.7  326.62  4972.5  327.12  4980.6  331.87  4999.5  336.94
  5026.3  336.47  5051.1  336.80  5071.3  329.99  5081.4  328.29  5091.5  329.90
  5101.6  337.82  5110.7  339.67  5141.9  339.95  5162.1  337.77  5190.0  339.58
  5222.6  337.09  5242.7  339.28  5262.9  337.53  5274.4  338.80  5324.8  338.93
  5348.6  338.02  5394.0  339.26  5427.9  338.15  5464.6  342.98  5560.5  348.59
#Mann=5,-1,0
  4769.9    0.05       0  4968.4    0.05       0  4972.5    0.05       0
  5026.3    0.12       0  5324.8    0.05       0
Bank Sta=4968.4,4972.5
Exp/Cntr=0.3,0.1

Type RM Length L Ch R = 1,4228,154,154,154
BEGIN DESCRIPTION:
North Twin Creek Trib K4227.57
END DESCRIPTION:
XS GIS Cut Line= 3
      2711165.47      6814125.61      2710923.09      6814114.86
      2710451.43      6814104.07
#Sta/Elev= 30
  4759.8  347.68  4779.3  346.38  4839.3  343.70  4859.4  343.51  4909.4  341.23
  4919.4  341.13  4959.5  336.60  4969.5  336.03  4975.6  334.78  4980.6  334.33
  4987.4  326.33  4987.7  325.83  4991.2  325.83  4991.5  326.33  5002.4  327.10
  5009.5  334.63  5019.5  337.11  5029.5  338.68  5039.5  338.29  5139.5  339.38
  5229.6  338.45  5279.6  339.11  5329.6  339.02  5349.6  338.67  5369.6  336.93
  5387.2  338.23  5399.6  337.61  5429.6  344.33  5469.4  347.21  5474.2  347.21
#Mann=3,-1,0
  4759.8    0.05       0  4987.4    0.05       0  4991.5    0.05       0
Bank Sta=4987.4,4991.5
Exp/Cntr=0.3,0.1

Type RM Length L Ch R = 1,4074,653,653,653
BEGIN DESCRIPTION:
North Twin Creek Trib K4073.5
END DESCRIPTION:
XS GIS Cut Line= 4
      2711191.32      6814086.36      2710926.62      6813960.82
      2710721.85      6814042.72      2710475.19      6814090.77
#Sta/Elev= 30
  4706.8  348.25  4752.9  344.90  4856.6  340.23  4866.5  339.21  4872.1  336.13
  4889.3  332.77  4940.3  332.42  4945.8  334.21  4956.2  331.02  4963.0  327.37
  4968.6  327.88  4976.3  325.44  4976.6  324.94  4980.4  325.44  4985.8  332.24
  4991.3  329.82  4997.3  333.17  5009.8  334.95  5032.7  336.14  5039.4  337.88
  5239.5  338.40  5277.2  337.83  5286.0  336.53  5297.6  338.46  5328.1  337.69
  5337.7  335.80  5399.5  336.41  5419.8  337.29  5451.1  343.81  5471.6  345.58
#Mann=3,-1,0
  4706.8    0.05       0  4976.3    0.05       0  4980.4    0.05       0
Bank Sta=4976.3,4980.4
Exp/Cntr=0.3,0.1

Type RM Length L Ch R = 1,3421,183,183,183
BEGIN DESCRIPTION:
North Twin Creek Trib K3420.86
END DESCRIPTION:
XS GIS Cut Line= 3
      2711201.44      6813371.92      2710874.59      6813393.01
      2710524.51      6813369.41
#Sta/Elev= 30
  4673.6  340.69  4719.1  338.21  4735.6  336.54  4740.6  336.75  4779.3  334.52
  4827.2  333.49  4859.4  331.00  4869.4  332.12  4879.5  331.48  4893.4  332.84
  4899.5  332.65  4939.6  334.79  4989.7  334.43  4997.9  324.16  5001.1  324.16
  5004.1  323.21  5007.5  322.14  5007.8  321.64  5011.6  321.64  5011.9  322.14
  5019.8  323.20  5029.8  334.12  5039.8  334.70  5076.5  334.79  5099.9  334.59
  5160.1  335.93  5200.2  337.38  5260.3  340.44  5320.4  342.09  5352.0  343.66
#Mann=6,-1,0
  4673.6    0.05       0  4827.2    0.12       0  5004.1    0.16       0
  5007.5    0.07       0  5011.9    0.16       0  5076.5    0.05       0
Bank Sta=5007.5,5011.9
Exp/Cntr=0.3,0.1

Type RM Length L Ch R = 1,3238,167,167,167
BEGIN DESCRIPTION:
North Twin Creek Trib K3238.42
END DESCRIPTION:
XS GIS Cut Line= 3
      2711288.53      6813231.04      2710832.16      6813223.19
      2710480.58      6813282.60
#Sta/Elev= 30
  4550.5  345.71  4554.3  345.71  4593.0  342.21  4673.0  336.15  4753.1  330.87
  4783.1  330.99  4793.1  332.04  4863.1  333.80  4903.1  333.44  4953.1  333.74
  4963.1  330.52  4973.1  328.67  4983.1  324.94  4990.9  324.91  4991.2  324.41
  4995.0  324.41  4995.3  324.91  5002.5  326.82  5006.9  326.82  5013.2  331.31
  5021.0  333.47  5026.1  333.75  5053.7  334.15  5063.9  331.45  5074.0  334.54
  5081.5  334.84  5147.0  335.77  5226.2  338.15  5328.3  341.97  5363.5  342.59
#Mann=3,-1,0
  4550.5    0.05       0  4990.9    0.05       0  4995.3    0.05       0
Bank Sta=4990.9,4995.3
Exp/Cntr=0.3,0.1

Type RM Length L Ch R = 1,3071,164,164,164
BEGIN DESCRIPTION:
North Twin Creek Trib K3070.95
END DESCRIPTION:
XS GIS Cut Line= 3
      2711330.39      6813039.77      2710822.68      6813059.32
      2710454.96      6813224.97
#Sta/Elev= 30
  4495.2  349.06  4499.9  349.06  4579.7  342.16  4619.7  337.92  4655.9  335.95
  4739.8  333.15  4775.9  330.09  4799.8  329.30  4819.8  329.38  4889.9  330.59
  4899.9  331.07  4909.9  332.18  4920.9  332.53  4959.9  331.94  4969.9  330.45
  4977.7  323.28  4978.0  322.78  4981.8  322.78  4982.1  323.28  4990.0  324.98
  4999.1  332.57  5023.3  331.79  5064.1  332.53  5069.6  331.62  5087.8  330.28
  5098.4  330.73  5115.9  333.69  5230.0  335.86  5306.5  339.31  5406.6  341.98
#Mann=5,-1,0
  4495.2    0.05       0  4775.9    0.12       0  4977.7    0.07       0
  4982.1    0.12       0  5087.8    0.05       0
Bank Sta=4977.7,4982.1
Exp/Cntr=0.3,0.1

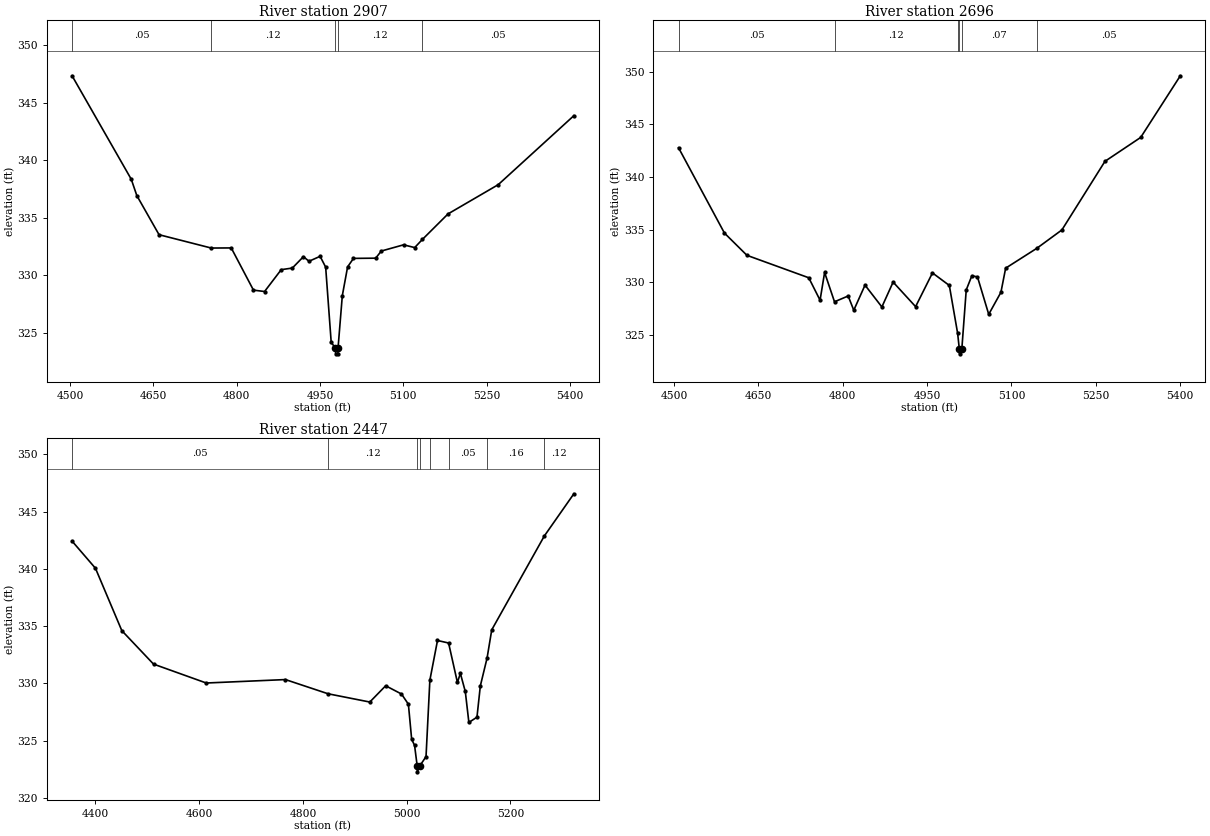
Type RM Length L Ch R = 1,2907,211,211,211
BEGIN DESCRIPTION:
North Twin Creek Trib K2907.42
END DESCRIPTION:
XS GIS Cut Line= 3
      2711322.64      6812896.72      2710822.01      6812895.66
      2710420.07      6812868.32
#Sta/Elev= 30
  4503.5  347.33  4610.1  338.33  4620.1  336.91  4660.1  333.51  4754.1  332.35
  4790.1  332.36  4830.1  328.69  4850.1  328.57  4880.1  330.47  4900.1  330.61
  4920.1  331.60  4930.1  331.20  4950.1  331.63  4960.1  330.69  4970.1  324.14
  4977.8  323.65  4978.2  323.15  4982.1  323.15  4982.4  323.65  4990.1  328.21
  4999.6  330.71  5010.2  331.45  5050.2  331.47  5060.3  332.09  5100.4  332.63
  5120.4  332.39  5134.3  333.10  5180.5  335.32  5270.8  337.86  5407.0  343.86
#Mann=5,-1,0
  4503.5    0.05       0  4754.1    0.12       0  4977.8    0.07       0
  4982.4    0.12       0  5134.3    0.05       0
Bank Sta=4977.8,4982.4
Exp/Cntr=0.3,0.1

Type RM Length L Ch R = 1,2696,249,249,249
BEGIN DESCRIPTION:
North Twin Creek Trib K2695.58
END DESCRIPTION:
XS GIS Cut Line= 3
      2711257.67      6812689.27      2710766.72      6812701.84
      2710365.59      6812722.97
#Sta/Elev= 30
  4507.8  342.78  4589.5  334.68  4629.5  332.57  4739.5  330.44  4759.6  328.31
  4767.7  330.94  4785.3  328.16  4809.6  328.71  4819.6  327.36  4839.6  329.74
  4869.6  327.67  4889.6  330.03  4929.6  327.70  4959.6  330.90  4989.6  329.71
  5004.4  325.16  5007.3  323.72  5007.7  323.22  5011.9  323.72  5019.7  329.29
  5029.7  330.63  5039.7  330.52  5059.7  326.97  5081.4  329.06  5089.8  331.35
  5145.1  333.23  5189.9  334.98  5266.5  341.49  5330.1  343.76  5400.6  349.61
#Mann=6,-1,0
  4507.8    0.05       0  4785.3    0.12       0  5004.4    0.07       0
  5007.3    0.07       0  5011.9    0.07       0  5145.1    0.05       0
Bank Sta=5007.3,5011.9
Exp/Cntr=0.3,0.1

Type RM Length L Ch R = 1,2447,210,210,210
BEGIN DESCRIPTION:
North Twin Creek Trib K2446.78
END DESCRIPTION:
XS GIS Cut Line= 3
      2711270.31      6812620.28      2710635.29      6812501.85
      2710350.57      6812352.67
#Sta/Elev= 30
  4354.9  342.42  4400.0  340.05  4450.8  334.61  4511.9  331.69  4613.6  330.04
  4766.2  330.34  4848.5  329.10  4928.9  328.38  4959.5  329.80  4990.0  329.08
  5003.3  328.19  5009.6  325.13  5015.2  324.60  5020.3  322.79  5020.6  322.29
  5025.0  322.79  5037.3  323.62  5044.7  330.29  5059.4  333.75  5080.8  333.53
  5097.8  330.09  5103.5  330.88  5113.0  329.30  5119.9  326.60  5135.5  327.06
  5142.0  329.79  5155.0  332.22  5164.0  334.68  5265.4  342.87  5322.3  346.55
#Mann=8,-1,0
  4354.9    0.05       0  4848.5    0.12       0  5020.3    0.07       0
  5025.0    0.12       0  5044.7    0.07       0  5080.8    0.05       0
  5155.0    0.16       0  5265.4    0.12       0
Bank Sta=5020.3,5025
Exp/Cntr=0.3,0.1