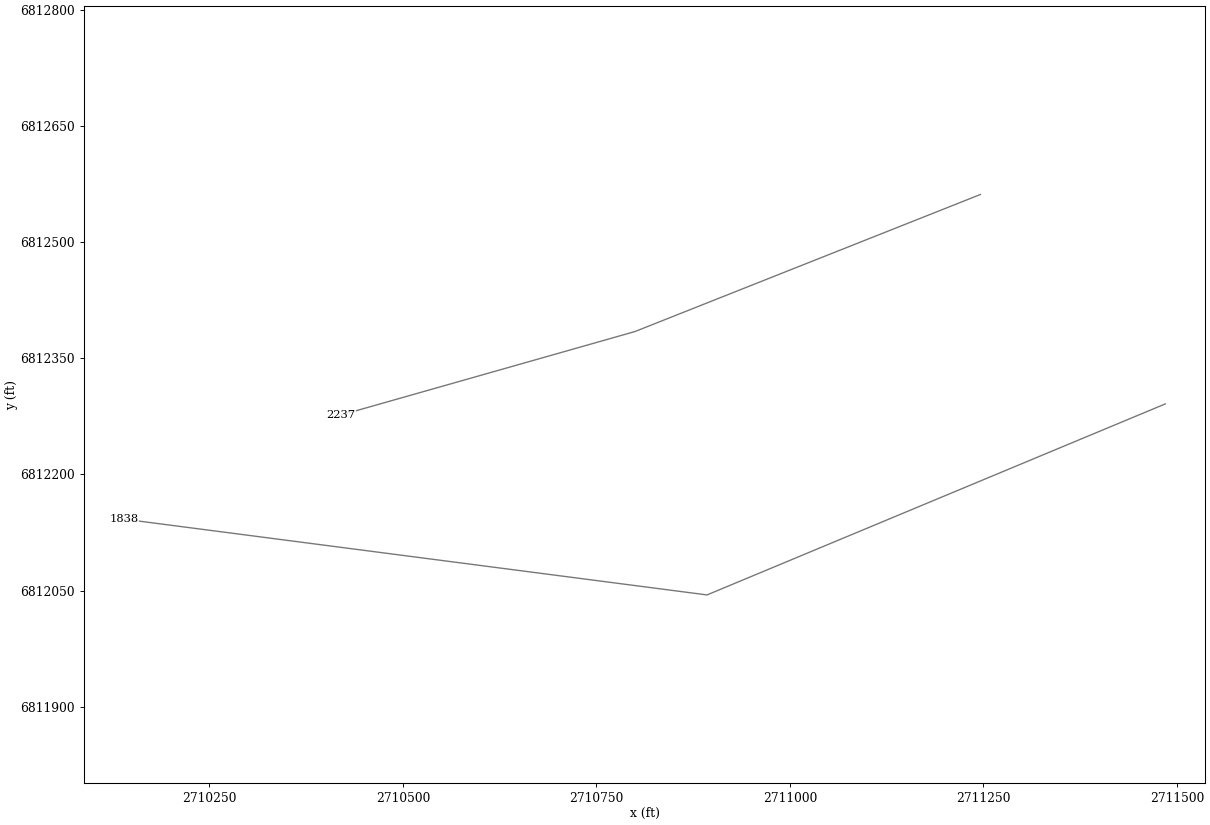
HEC-RAS study North Twin Creek Trib K.prj: North Twin Creek Trib K Base Level Engineering

--- North Twin Creek Trib K.g01 (geometry) --- (continued)

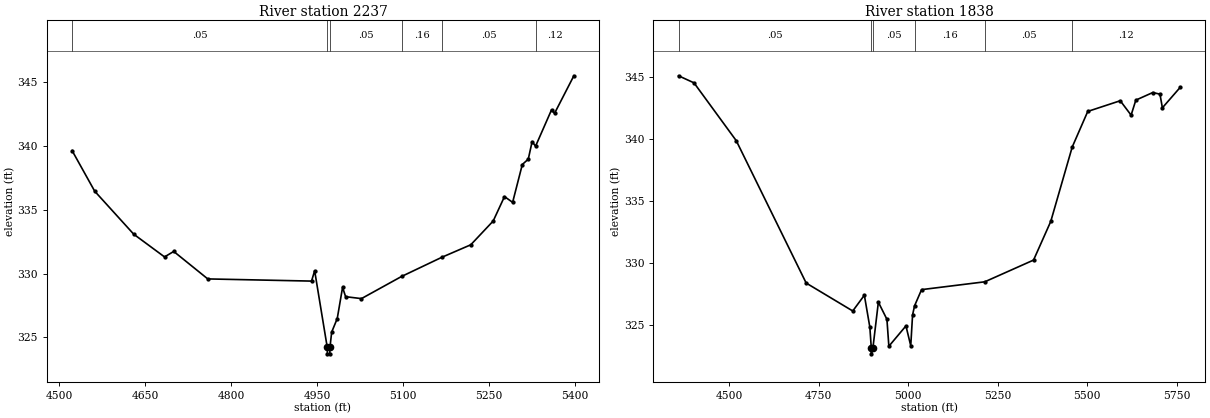
Type RM Length L Ch R = 1,2237,399,399,399
BEGIN DESCRIPTION:
North Twin Creek Trib K2236.62
END DESCRIPTION:
XS GIS Cut Line= 3
      2711245.96      6812561.29      2710799.71      6812384.38
      2710419.56      6812276.50
#Sta/Elev= 30
  4522.9  339.62  4562.4  336.44  4630.4  333.08  4684.2  331.30  4700.2  331.73
  4759.6  329.58  4940.6  329.41  4946.0  330.22  4968.0  324.22  4968.3  323.72
  4972.4  323.72  4972.7  324.22  4975.7  325.42  4985.4  326.48  4994.7  328.92
  5000.0  328.19  5027.6  328.04  5097.5  329.77  5168.2  331.28  5218.3  332.25
  5257.4  334.11  5277.1  336.02  5291.3  335.57  5308.2  338.53  5318.6  338.95
  5325.3  340.32  5331.3  339.96  5359.2  342.81  5364.4  342.53  5398.1  345.47
#Mann=6,-1,0
  4522.9    0.05       0  4968.0    0.05       0  4972.7    0.05       0
  5097.5    0.16       0  5168.2    0.05       0  5331.3    0.12       0
Bank Sta=4968,4972.7
Exp/Cntr=0.3,0.1

Type RM Length L Ch R = 1,1838,0,0,0
BEGIN DESCRIPTION:
North Twin Creek Trib K1962.91
END DESCRIPTION:
XS GIS Cut Line= 3
      2711484.80      6812290.97      2710892.90      6812044.43
      2710139.72      6812142.24
#Sta/Elev= 30
  4358.8  345.06  4402.0  344.49  4520.0  339.83  4715.1  328.37  4845.1  326.12
  4877.5  327.39  4892.8  324.82  4896.8  323.17  4897.1  322.67  4901.5  323.17
  4916.6  326.83  4940.5  325.45  4945.9  323.28  4993.6  324.92  5007.0  323.32
  5012.1  325.81  5017.7  326.54  5037.2  327.84  5213.6  328.47  5349.8  330.22
  5397.8  333.33  5457.7  339.32  5501.1  342.19  5591.8  343.05  5622.1  341.89
  5635.3  343.10  5682.6  343.71  5702.7  343.58  5709.4  342.48  5759.5  344.14
#Mann=6,-1,0
  4358.8    0.05       0  4896.8    0.05       0  4901.5    0.05       0
  5017.7    0.16       0  5213.6    0.05       0  5457.7    0.12       0
Bank Sta=4896.8,4901.5
Exp/Cntr=0.3,0.1

Chan Stop Cuts=-1