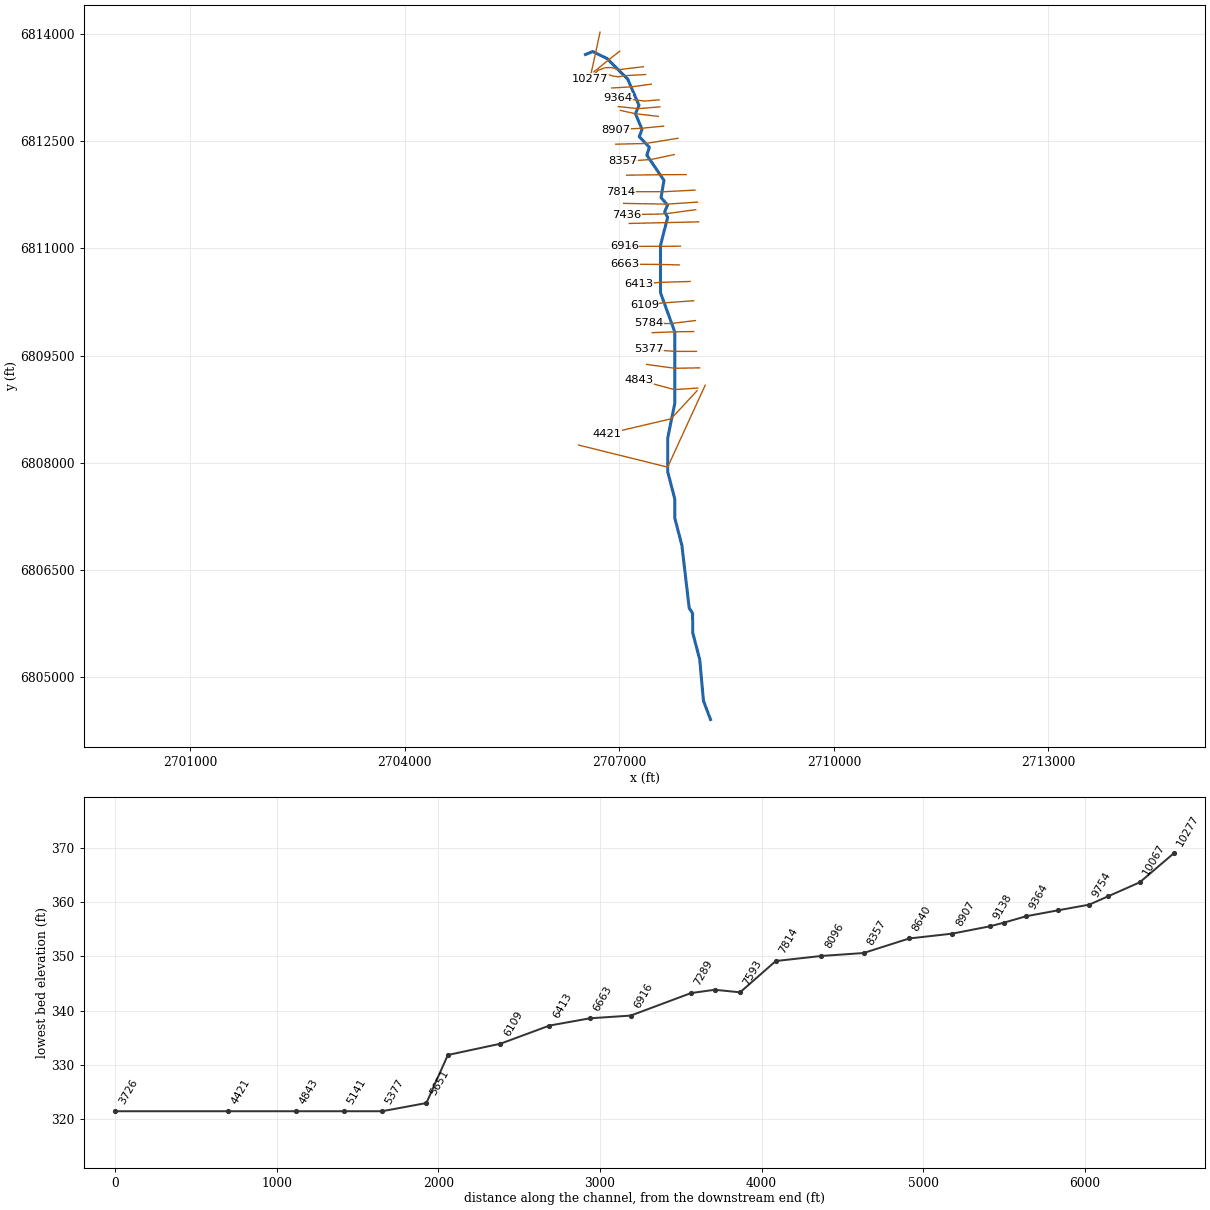
--- North Twin Creek Trib L.prj (project) ---

Proj Title=North Twin Creek Trib L Base Level Engineering
Current Plan=p01
Default Exp/Contr=0.3,0.1
English Units
Geom File=g01
Flow File=f01
Plan File=p01
BEGIN DESCRIPTION:
North Twin Creek Trib L
END DESCRIPTION:

--- North Twin Creek Trib L.p01 (plan) ---

Plan Title=Multiple Run
Short Identifier=Multiple
Geom File=g01
Flow File=f01
Subcritical Flow
K Sum by GR= 0
Std Step Tol= 0.01
Critical Tol= 0.01
Num of Std Step Trials= 20
Max Error Tol= 0.3
Flow Tol Ratio= 0.001
Split Flow NTrial= 30
Split Flow Tol= 0.02
Split Flow Ratio= 0.02
Log Output Level= 0
Friction Slope Method= 1
Unsteady Friction Slope Method= 2
Unsteady Bridges Friction Slope Method= 1
Parabolic Critical Depth
Global Vel Dist=  1 , 1 , 1
Global Log Level= 0
CheckData=True
Encroach Param= -1, 0, 0, 0
BEGIN DESCRIPTION:
Multiple Run
END DESCRIPTION:

--- North Twin Creek Trib L.f01 (steady flow) ---

Flow Title=Multiple
Number of Profiles=7
Profile Names=10-year,25-year,50-year,1pct_min,100-year,1pct_plu,500-year
River Rch & RM= North Twin Creek,Reach-1,10277
     433     570     679     402     802    1600    1117
River Rch & RM= North Twin Creek,Reach-1,3726
     724     982    1192     718    1433    2860    2070
Boundary for River Rch & Prof#=North Twin Creek,Reach-1,1
Up Type=0
Dn Type=3
Dn Slope=0.005
Boundary for River Rch & Prof#=North Twin Creek,Reach-1,2
Up Type=0
Dn Type=3
Dn Slope=0.005
Boundary for River Rch & Prof#=North Twin Creek,Reach-1,3
Up Type=0
Dn Type=3
Dn Slope=0.005
Boundary for River Rch & Prof#=North Twin Creek,Reach-1,4
Up Type=0
Dn Type=3
Dn Slope=0.005
Boundary for River Rch & Prof#=North Twin Creek,Reach-1,5
Up Type=0
Dn Type=3
Dn Slope=0.005
Boundary for River Rch & Prof#=North Twin Creek,Reach-1,6
Up Type=0
Dn Type=3
Dn Slope=0.005
Boundary for River Rch & Prof#=North Twin Creek,Reach-1,7
Up Type=0
Dn Type=3
Dn Slope=0.005

--- North Twin Creek Trib L.g01 (geometry) ---

Geom Title=Existing Conditions

River Reach=North Twin Creek,Reach-1
Reach XY= 30
      2706526.00      6813711.00      2706629.28      6813753.15
      2706828.30      6813655.17      2707117.86      6813367.06
      2707275.23      6813000.31      2707225.63      6812883.81
      2707317.90      6812664.29      2707279.16      6812562.65
      2707420.88      6812413.29      2707385.17      6812304.28
      2707625.05      6811951.14      2707583.36      6811710.92
      2707674.33      6811604.95      2707633.62      6811511.00
      2707676.20      6811433.80      2707576.21      6811042.73
      2707576.07      6810381.03      2707776.39      6809829.34
      2707776.20      6808835.92      2707676.21      6808342.73
      2707676.21      6807879.27      2707775.32      6807497.08
      2707776.52      6807226.22      2707874.78      6806850.50
      2707977.38      6805970.66      2708025.32      6805897.08
      2708026.68      6805624.92      2708124.78      6805250.50
      2708177.22      6804671.50      2708276.00      6804411.00

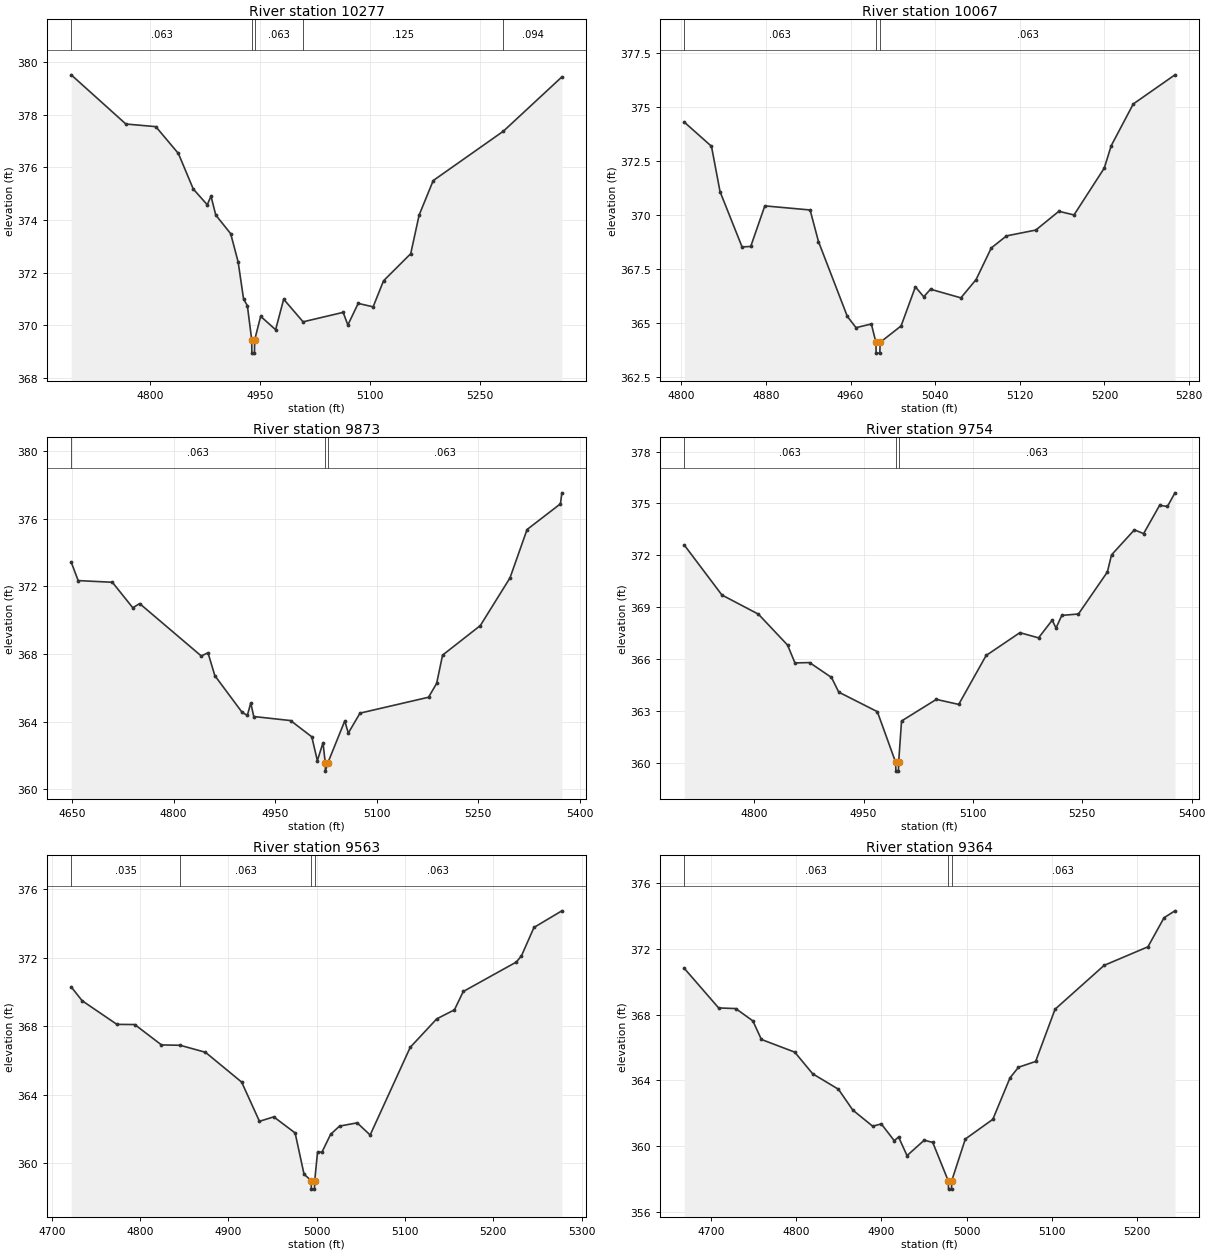
Type RM Length L Ch R = 1,10277,210,210,210
BEGIN DESCRIPTION:
North Twin Creek Trib L10276.93
END DESCRIPTION:
XS GIS Cut Line= 3
      2706730.37      6814023.95      2706666.32      6813722.48
      2706587.95      6813369.57
#Sta/Elev= 30
  4691.8  379.52  4766.4  377.65  4807.3  377.55  4838.1  376.53  4858.4  375.18
  4877.5  374.58  4882.6  374.91  4889.1  374.19  4909.5  373.48  4919.7  372.40
  4927.1  370.99  4932.2  370.75  4938.2  369.44  4938.4  368.94  4941.9  368.94
  4942.2  369.44  4950.4  370.34  4970.8  369.83  4981.8  370.99  5008.3  370.13
  5063.0  370.49  5069.4  370.01  5083.5  370.83  5103.9  370.70  5118.1  371.69
  5155.2  372.72  5166.7  374.19  5185.9  375.50  5281.8  377.38  5361.5  379.44
#Mann=5,-1,0
  4691.8   0.063       0  4938.2   0.063       0  4942.2   0.063       0
  5008.3   0.125       0  5281.8   0.094       0
Bank Sta=4938.2,4942.2
Exp/Cntr=0.3,0.1

Type RM Length L Ch R = 1,10067,194,194,194
BEGIN DESCRIPTION:
North Twin Creek Trib L10067.16
END DESCRIPTION:
XS GIS Cut Line= 3
      2707006.06      6813758.01      2706847.85      6813634.90
      2706644.35      6813467.93
#Sta/Elev= 30
  4802.9  374.32  4828.6  373.20  4836.7  371.10  4857.5  368.54  4865.7  368.56
  4879.0  370.44  4921.8  370.25  4929.7  368.79  4957.0  365.32  4965.2  364.80
  4979.7  364.97  4984.0  364.12  4984.2  363.62  4987.7  363.62  4988.0  364.12
  5007.8  364.88  5021.3  366.69  5029.2  366.23  5035.6  366.58  5064.3  366.18
  5078.7  367.03  5093.0  368.49  5107.4  369.05  5135.1  369.32  5156.9  370.19
  5171.2  370.02  5199.8  372.19  5206.4  373.23  5227.2  375.16  5266.6  376.51
#Mann=3,-1,0
  4802.9   0.063       0  4984.0   0.063       0  4988.0   0.063       0
Bank Sta=4984,4988
Exp/Cntr=0.3,0.1

Type RM Length L Ch R = 1,9873,119,119,119
BEGIN DESCRIPTION:
North Twin Creek Trib L9872.73
END DESCRIPTION:
XS GIS Cut Line= 6
      2707336.23      6813540.81      2706986.57      6813499.09
      2706892.15      6813529.41      2706806.18      6813527.45
      2706704.46      6813491.37      2706650.27      6813433.74
#Sta/Elev= 30
  4648.8  373.43  4659.1  372.34  4709.6  372.24  4739.8  370.73  4749.9  370.98
  4840.9  367.88  4850.8  368.07  4860.9  366.72  4901.3  364.54  4908.9  364.37
  4914.0  365.10  4918.4  364.30  4972.8  364.06  5004.1  363.10  5012.3  361.69
  5020.7  362.75  5023.9  361.57  5024.2  361.07  5027.9  361.57  5052.8  364.04
  5058.0  363.32  5075.3  364.50  5176.5  365.44  5188.5  366.26  5197.2  367.93
  5253.0  369.68  5296.8  372.50  5322.0  375.36  5371.3  376.88  5373.4  377.53
#Mann=3,-1,0
  4648.8   0.063       0  5023.9   0.063       0  5027.9   0.063       0
Bank Sta=5023.9,5027.9
Exp/Cntr=0.3,0.1

Type RM Length L Ch R = 1,9754,191,191,191
BEGIN DESCRIPTION:
North Twin Creek Trib L9753.66
END DESCRIPTION:
XS GIS Cut Line= 6
      2707367.47      6813431.13      2707068.97      6813415.24
      2706993.25      6813399.23      2706909.19      6813410.30
      2706824.70      6813440.85      2706716.87      6813383.87
#Sta/Elev= 30
  4704.1  372.59  4755.7  369.70  4805.8  368.59  4845.8  366.80  4855.9  365.77
  4875.9  365.79  4906.0  364.93  4916.0  364.08  4968.9  362.95  4994.1  360.01
  4994.3  359.51  4997.8  359.51  4998.1  360.01  5002.1  362.41  5049.8  363.66
  5080.5  363.37  5118.1  366.20  5164.4  367.52  5190.0  367.22  5208.7  368.24
  5214.0  367.79  5221.9  368.52  5244.7  368.60  5284.4  371.03  5290.1  372.02
  5321.5  373.47  5334.1  373.25  5356.1  374.89  5366.8  374.82  5377.1  375.61
#Mann=3,-1,0
  4704.1   0.063       0  4994.1   0.063       0  4998.1   0.063       0
Bank Sta=4994.1,4998.1
Exp/Cntr=0.3,0.1

Type RM Length L Ch R = 1,9563,199,199,199
BEGIN DESCRIPTION:
North Twin Creek Trib L9563.06
END DESCRIPTION:
XS GIS Cut Line= 3
      2707447.36      6813297.11      2707170.72      6813259.43
      2706894.48      6813243.40
#Sta/Elev= 30
  4721.8  370.29  4734.2  369.48  4773.6  368.10  4793.8  368.09  4824.1  366.90
  4845.2  366.88  4873.9  366.47  4914.9  364.73  4935.1  362.44  4951.3  362.70
  4975.5  361.76  4985.6  359.35  4993.7  358.98  4993.9  358.48  4997.4  358.48
  4997.7  358.98  5000.9  360.64  5005.9  360.64  5015.7  361.68  5025.8  362.16
  5045.8  362.35  5060.5  361.64  5105.9  366.76  5135.9  368.42  5156.0  368.95
  5166.0  370.02  5226.1  371.74  5231.9  372.10  5246.1  373.76  5277.7  374.73
#Mann=4,-1,0
  4721.8   0.035       0  4845.2   0.063       0  4993.7   0.063       0
  4997.7   0.063       0
Bank Sta=4993.7,4997.7
Exp/Cntr=0.3,0.1

Type RM Length L Ch R = 1,9364,140,140,140
BEGIN DESCRIPTION:
North Twin Creek Trib L9363.7
END DESCRIPTION:
XS GIS Cut Line= 4
      2707556.17      6813077.71      2707357.20      6813060.19
      2707225.42      6813076.67      2706983.22      6813099.30
#Sta/Elev= 30
  4668.7  370.82  4709.0  368.41  4729.1  368.37  4749.2  367.62  4759.2  366.49
  4798.3  365.72  4819.4  364.40  4849.6  363.46  4866.5  362.19  4889.8  361.21
  4899.9  361.35  4915.1  360.33  4920.2  360.55  4930.1  359.42  4950.3  360.36
  4960.3  360.22  4978.5  357.88  4978.8  357.38  4982.3  357.38  4982.5  357.88
  4998.5  360.43  5030.8  361.63  5050.9  364.15  5060.9  364.80  5081.0  365.15
  5103.8  368.33  5161.4  371.00  5212.8  372.13  5231.7  373.90  5244.5  374.32
#Mann=3,-1,0
  4668.7   0.063       0  4978.5   0.063       0  4982.5   0.063       0
Bank Sta=4978.5,4982.5
Exp/Cntr=0.3,0.1

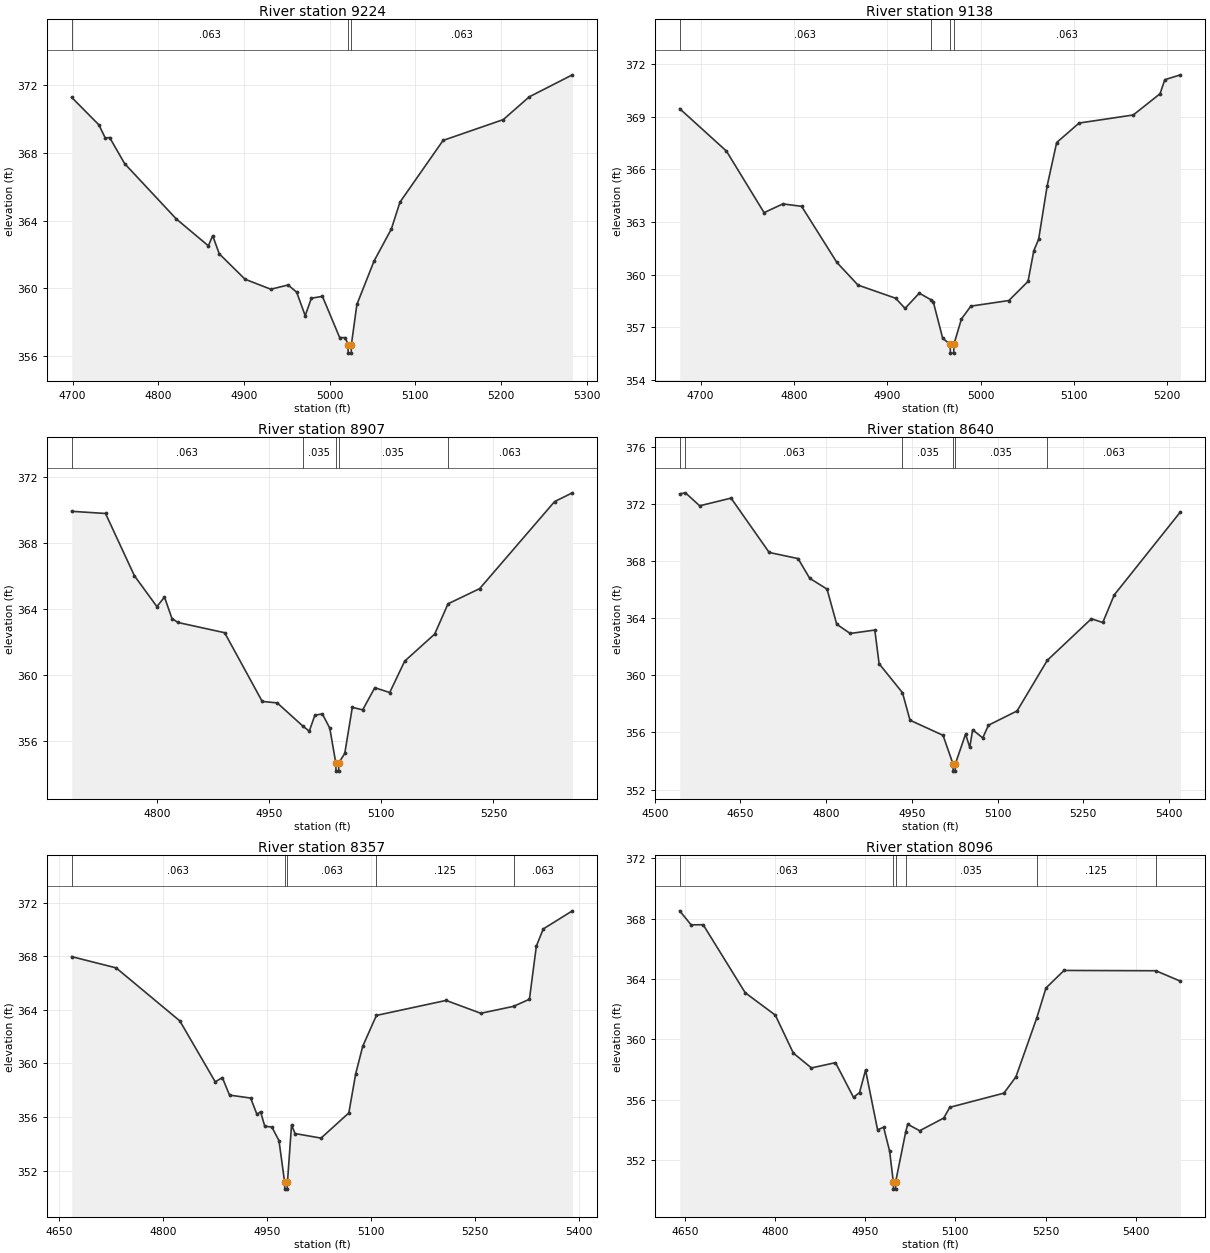
Type RM Length L Ch R = 1,9224,86,86,86
BEGIN DESCRIPTION:
North Twin Creek Trib L9223.52
END DESCRIPTION:
XS GIS Cut Line= 3
      2707567.60      6812979.48      2707264.97      6812954.19
      2706985.89      6812983.55
#Sta/Elev= 30
  4699.0  371.27  4730.7  369.65  4738.2  368.87  4743.3  368.90  4760.8  367.36
  4821.0  364.10  4858.5  362.51  4863.5  363.11  4871.2  362.04  4901.3  360.54
  4931.4  359.95  4951.5  360.20  4961.5  359.78  4971.5  358.39  4978.7  359.42
  4991.6  359.53  5011.7  357.10  5018.4  357.09  5021.4  356.68  5021.7  356.18
  5025.2  356.18  5025.4  356.68  5031.8  359.05  5051.9  361.62  5072.0  363.50
  5082.1  365.09  5132.4  368.73  5202.7  369.96  5232.9  371.30  5283.3  372.60
#Mann=3,-1,0
  4699.0   0.063       0  5021.4   0.063       0  5025.4   0.063       0
Bank Sta=5021.4,5025.4
Exp/Cntr=0.3,0.1

Type RM Length L Ch R = 1,9138,231,231,231
BEGIN DESCRIPTION:
North Twin Creek Trib L9138.08
END DESCRIPTION:
XS GIS Cut Line= 3
      2707545.73      6812846.04      2707221.78      6812884.12
      2707016.76      6812930.10
#Sta/Elev= 30
  4677.7  369.46  4727.8  367.04  4768.1  363.53  4788.2  364.03  4808.3  363.89
  4846.1  360.69  4868.7  359.40  4909.0  358.65  4919.1  358.07  4934.3  358.94
  4946.6  358.57  4949.3  358.45  4959.4  356.37  4967.4  356.02  4967.7  355.52
  4971.2  355.52  4971.4  356.02  4979.5  357.47  4989.6  358.20  5030.3  358.52
  5050.8  359.61  5057.0  361.36  5062.2  362.02  5071.3  365.06  5081.5  367.53
  5105.5  368.64  5163.5  369.10  5192.2  370.31  5197.3  371.11  5214.0  371.39
#Mann=4,-1,0
  4677.7   0.063       0  4946.6   0.035       0  4967.4   0.063       0
  4971.4   0.063       0
Bank Sta=4967.4,4971.4
Exp/Cntr=0.3,0.1

Type RM Length L Ch R = 1,8907,267,267,267
BEGIN DESCRIPTION:
North Twin Creek Trib L8907.35
END DESCRIPTION:
XS GIS Cut Line= 3
      2707619.41      6812710.04      2707305.84      6812679.52
      2706952.21      6812662.38
#Sta/Elev= 30
  4686.4  369.91  4731.6  369.78  4770.2  366.01  4800.3  364.14  4810.4  364.72
  4820.4  363.42  4828.4  363.18  4890.8  362.56  4941.0  358.40  4961.1  358.31
  4995.5  356.90  5003.9  356.60  5011.3  357.56  5021.3  357.65  5031.3  356.78
  5039.3  354.68  5039.6  354.18  5043.1  354.18  5043.3  354.68  5051.3  355.25
  5061.4  358.04  5075.3  357.89  5091.4  359.23  5111.4  358.94  5131.4  360.84
  5171.5  362.48  5189.3  364.31  5231.6  365.23  5331.7  370.50  5355.5  371.03
#Mann=5,-1,0
  4686.4   0.063       0  4995.5   0.035       0  5039.3   0.035       0
  5043.3   0.035       0  5189.3   0.063       0
Bank Sta=5039.3,5043.3
Exp/Cntr=0.3,0.1

Type RM Length L Ch R = 1,8640,283,283,283
BEGIN DESCRIPTION:
North Twin Creek Trib L8640.05
END DESCRIPTION:
XS GIS Cut Line= 3
      2707820.54      6812540.27      2707370.04      6812467.22
      2706950.23      6812457.66
#Sta/Elev= 30
  4543.6  372.73  4553.7  372.80  4578.6  371.89  4633.5  372.43  4700.2  368.62
  4750.8  368.19  4771.1  366.81  4801.5  366.05  4818.4  363.59  4842.0  362.94
  4885.1  363.18  4892.6  360.82  4933.5  358.79  4946.7  356.86  5004.5  355.80
  5022.0  353.79  5022.3  353.29  5025.8  353.29  5026.0  353.79  5044.0  355.89
  5051.3  354.95  5056.3  356.19  5074.0  355.62  5084.0  356.51  5134.1  357.51
  5187.0  361.06  5264.1  363.97  5284.1  363.71  5304.1  365.64  5419.9  371.46
#Mann=6,-1,0
  4543.6   0.094       0  4553.7   0.063       0  4933.5   0.035       0
  5022.0   0.035       0  5026.0   0.035       0  5187.0   0.063       0
Bank Sta=5022,5026
Exp/Cntr=0.3,0.1

Type RM Length L Ch R = 1,8357,261,261,261
BEGIN DESCRIPTION:
North Twin Creek Trib L8356.87
END DESCRIPTION:
XS GIS Cut Line= 3
      2707768.77      6812311.80      2707444.96      6812243.80
      2707054.16      6812215.42
#Sta/Elev= 30
  4667.8  367.97  4731.9  367.13  4823.9  363.17  4875.0  358.62  4885.2  358.94
  4895.6  357.63  4926.1  357.41  4935.2  356.19  4940.4  356.39  4946.5  355.30
  4956.7  355.25  4967.0  354.23  4975.2  351.11  4975.4  350.61  4978.9  350.61
  4979.2  351.11  4985.1  355.40  4990.2  354.76  5027.7  354.42  5067.8  356.30
  5077.8  359.24  5087.9  361.28  5107.6  363.58  5208.2  364.70  5258.3  363.74
  5305.7  364.26  5328.5  364.79  5338.5  368.76  5348.5  370.04  5390.5  371.39
#Mann=5,-1,0
  4667.8   0.063       0  4975.2   0.063       0  4979.2   0.063       0
  5107.6   0.125       0  5305.7   0.063       0
Bank Sta=4975.2,4979.2
Exp/Cntr=0.3,0.1

Type RM Length L Ch R = 1,8096,282,282,282
BEGIN DESCRIPTION:
North Twin Creek Trib L8095.91
END DESCRIPTION:
XS GIS Cut Line= 3
      2707935.01      6812032.00      2707574.80      6812030.29
      2707102.65      6812023.86
#Sta/Elev= 30
  4641.6  368.51  4660.6  367.58  4680.6  367.59  4750.6  363.08  4800.6  361.60
  4830.6  359.08  4860.6  358.10  4900.6  358.45  4930.6  356.15  4940.6  356.47
  4950.6  357.96  4970.6  354.00  4980.6  354.17  4990.6  352.59  4996.7  350.57
  4997.0  350.07  5000.5  350.07  5000.7  350.57  5017.4  353.87  5020.6  354.37
  5040.6  353.94  5080.6  354.78  5090.6  355.49  5180.6  356.43  5200.6  357.51
  5235.3  361.42  5250.6  363.40  5280.6  364.56  5433.2  364.54  5474.0  363.85
#Mann=6,-1,0
  4641.6   0.063       0  4996.7   0.063       0  5000.7   0.063       0
  5017.4   0.035       0  5235.3   0.125       0  5433.2   0.063       0
Bank Sta=4996.7,5000.7
Exp/Cntr=0.3,0.1

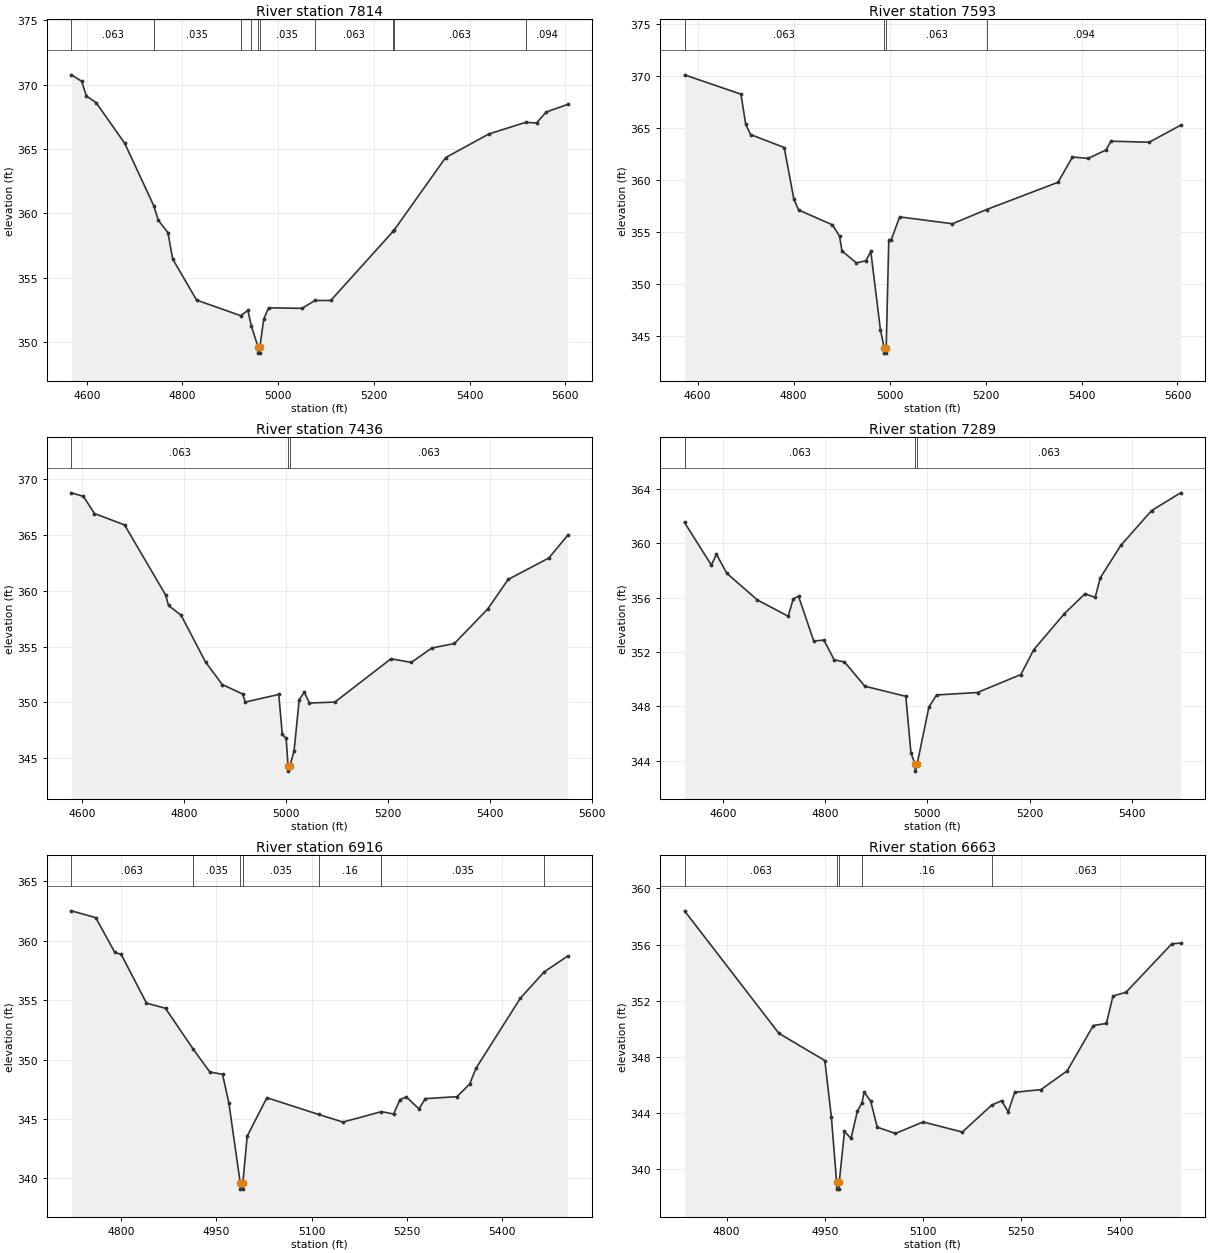
Type RM Length L Ch R = 1,7814,221,221,221
BEGIN DESCRIPTION:
North Twin Creek Trib L7814.19
END DESCRIPTION:
XS GIS Cut Line= 3
      2708057.20      6811814.86      2707626.90      6811792.93
      2707021.15      6811792.99
#Sta/Elev= 30
  4568.2  370.76  4589.4  370.26  4599.4  369.11  4619.5  368.61  4679.5  365.44
  4740.3  360.58  4749.6  359.46  4769.7  358.51  4779.7  356.45  4829.7  353.26
  4921.8  352.05  4936.8  352.46  4944.1  351.24  4957.9  349.64  4958.2  349.14
  4961.7  349.14  4961.9  349.64  4969.9  351.77  4979.9  352.66  5050.0  352.62
  5076.9  353.23  5110.0  353.23  5240.0  358.59  5242.4  358.70  5350.0  364.33
  5440.0  366.16  5517.3  367.07  5540.0  367.02  5560.0  367.87  5604.8  368.46
#Mann=10,-1,0
  4568.2   0.063       0  4740.3   0.035       0  4921.8   0.063       0
  4944.1   0.035       0  4957.9   0.035       0  4961.9   0.035       0
  5076.9   0.063       0  5240.0   0.035       0  5242.4   0.063       0
  5517.3   0.094       0
Bank Sta=4957.9,4961.9
Exp/Cntr=0.3,0.1

Type RM Length L Ch R = 1,7593,157,157,157
BEGIN DESCRIPTION:
North Twin Creek Trib L7592.5
END DESCRIPTION:
XS GIS Cut Line= 3
      2708093.35      6811647.70      2707666.15      6811618.92
      2707060.61      6811629.35
#Sta/Elev= 30
  4572.7  370.14  4690.3  368.28  4700.3  365.37  4710.4  364.40  4780.5  363.15
  4800.6  358.18  4810.6  357.14  4880.8  355.72  4895.7  354.64  4900.8  353.21
  4930.9  352.05  4950.9  352.27  4960.9  353.16  4981.0  345.61  4989.0  343.88
  4989.2  343.38  4992.7  343.38  4993.0  343.88  4998.4  354.26  5003.4  354.26
  5021.0  356.48  5131.0  355.82  5202.4  357.19  5351.1  359.81  5381.1  362.24
  5414.0  362.10  5451.1  362.92  5461.1  363.76  5541.1  363.66  5606.5  365.29
#Mann=4,-1,0
  4572.7   0.063       0  4989.0   0.063       0  4993.0   0.063       0
  5202.4   0.094       0
Bank Sta=4989,4993
Exp/Cntr=0.3,0.1

Type RM Length L Ch R = 1,7436,147,147,147
BEGIN DESCRIPTION:
North Twin Creek Trib L7436.25
END DESCRIPTION:
XS GIS Cut Line= 4
      2708069.31      6811541.52      2707651.56      6811485.24
      2707545.82      6811479.37      2707099.30      6811472.65
#Sta/Elev= 30
  4578.5  368.75  4602.0  368.43  4623.5  366.90  4682.7  365.88  4763.5  359.60
  4769.1  358.67  4793.7  357.80  4841.8  353.61  4874.5  351.60  4914.6  350.75
  4919.7  350.03  4985.5  350.71  4992.4  347.14  5000.0  346.78  5003.6  344.35
  5003.8  343.85  5007.6  344.35  5015.6  345.68  5025.6  350.25  5035.6  350.91
  5045.7  349.94  5095.7  350.03  5205.8  353.90  5245.8  353.58  5285.8  354.86
  5330.3  355.27  5395.8  358.36  5435.8  361.00  5515.8  362.92  5552.5  364.94
#Mann=3,-1,0
  4578.5   0.063       0  5003.6   0.063       0  5007.6   0.063       0
Bank Sta=5003.6,5007.6
Exp/Cntr=0.3,0.1

Type RM Length L Ch R = 1,7289,373,373,373
BEGIN DESCRIPTION:
North Twin Creek Trib L7289.15
END DESCRIPTION:
XS GIS Cut Line= 3
      2708108.53      6811370.97      2707630.88      6811360.08
      2707139.08      6811348.88
#Sta/Elev= 30
  4525.3  361.52  4577.8  358.39  4587.8  359.18  4607.8  357.79  4667.9  355.82
  4727.9  354.63  4737.9  355.91  4748.2  356.09  4777.9  352.81  4797.9  352.87
  4817.9  351.42  4837.9  351.27  4877.9  349.48  4957.9  348.74  4967.9  344.59
  4975.9  343.74  4976.2  343.24  4979.9  343.74  5003.0  347.95  5018.0  348.84
  5098.0  349.02  5182.7  350.34  5208.0  352.17  5268.0  354.82  5308.0  356.28
  5328.0  356.01  5338.0  357.45  5378.0  359.83  5438.1  362.39  5495.0  363.70
#Mann=3,-1,0
  4525.3   0.063       0  4975.9   0.063       0  4979.9   0.063       0
Bank Sta=4975.9,4979.9
Exp/Cntr=0.3,0.1

Type RM Length L Ch R = 1,6916,253,253,253
BEGIN DESCRIPTION:
North Twin Creek Trib L6916.02
END DESCRIPTION:
XS GIS Cut Line= 3
      2707854.40      6811030.92      2707573.24      6811028.84
      2707071.51      6811028.24
#Sta/Elev= 30
  4721.2  362.51  4759.6  361.93  4789.6  359.01  4799.6  358.85  4839.6  354.75
  4869.6  354.31  4913.5  350.86  4939.6  348.95  4959.6  348.76  4969.6  346.35
  4987.6  339.60  4987.9  339.10  4991.4  339.10  4991.6  339.60  4998.5  343.56
  5029.6  346.79  5111.4  345.38  5149.6  344.74  5210.4  345.62  5229.6  345.42
  5239.6  346.63  5249.6  346.86  5269.6  345.85  5279.6  346.71  5329.6  346.88
  5349.6  347.94  5359.6  349.27  5429.6  355.16  5467.1  357.37  5504.1  358.70
#Mann=7,-1,0
  4721.2   0.063       0  4913.5   0.035       0  4987.6   0.035       0
  4991.6   0.035       0  5111.4    0.16       0  5210.4   0.035       0
  5467.1   0.063       0
Bank Sta=4987.6,4991.6
Exp/Cntr=0.3,0.1

Type RM Length L Ch R = 1,6663,250,250,250
BEGIN DESCRIPTION:
North Twin Creek Trib L6662.59
END DESCRIPTION:
XS GIS Cut Line= 3
      2707840.20      6810768.67      2707571.66      6810775.54
      2707082.71      6810779.55
#Sta/Elev= 30
  4735.7  358.40  4879.9  349.68  4950.0  347.75  4960.0  343.71  4968.0  339.10
  4968.2  338.60  4971.7  338.60  4972.0  339.10  4980.0  342.70  4990.0  342.21
  4999.7  344.15  5006.8  344.75  5010.0  345.51  5020.0  344.86  5030.0  343.01
  5057.8  342.56  5100.0  343.38  5160.0  342.66  5204.8  344.58  5220.0  344.89
  5230.0  344.10  5240.0  345.49  5280.0  345.68  5320.0  347.01  5360.0  350.24
  5380.0  350.39  5390.0  352.34  5410.0  352.61  5480.0  356.06  5493.3  356.10
#Mann=5,-1,0
  4735.7   0.063       0  4968.0   0.063       0  4972.0   0.063       0
  5006.8    0.16       0  5204.8   0.063       0
Bank Sta=4968,4972
Exp/Cntr=0.3,0.1

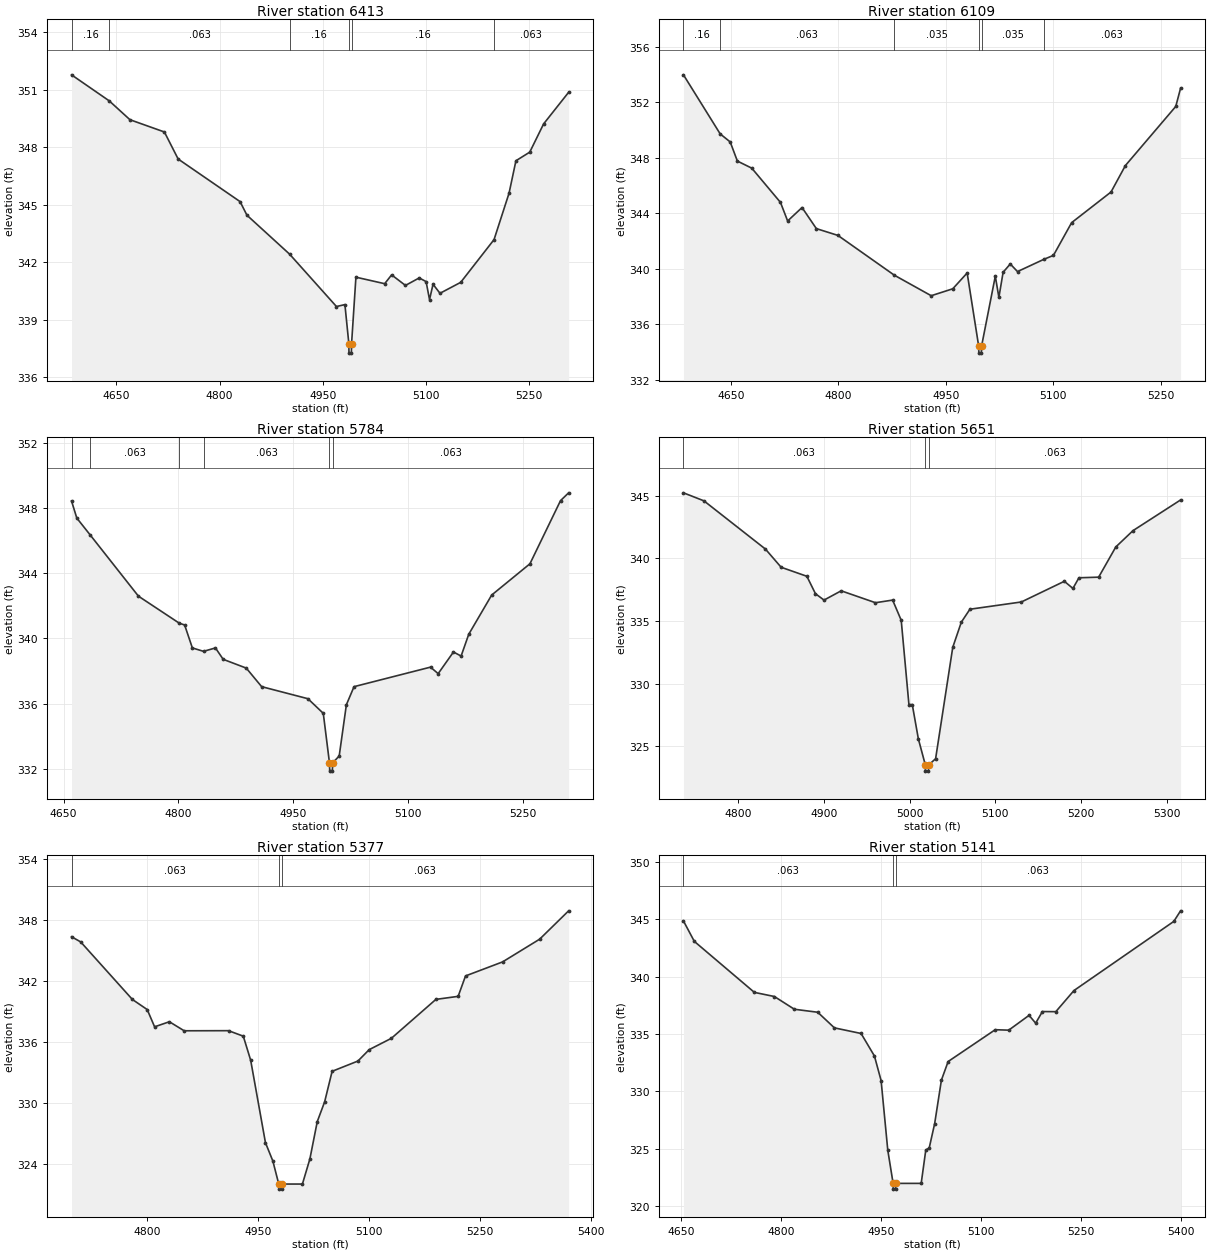
Type RM Length L Ch R = 1,6413,304,304,304
BEGIN DESCRIPTION:
North Twin Creek Trib L6412.57
END DESCRIPTION:
XS GIS Cut Line= 3
      2707990.90      6810537.45      2707574.30      6810525.36
      2707269.72      6810497.73
#Sta/Elev= 30
  4584.9  351.77  4639.8  350.41  4669.8  349.43  4719.9  348.79  4739.9  347.38
  4829.9  345.16  4839.9  344.45  4901.9  342.42  4970.0  339.69  4982.3  339.79
  4988.0  337.76  4988.2  337.26  4991.7  337.26  4992.0  337.76  4998.3  341.22
  5040.1  340.88  5050.2  341.34  5070.3  340.79  5090.3  341.18  5100.3  340.99
  5105.3  340.05  5110.4  340.85  5120.5  340.38  5150.6  340.95  5199.1  343.18
  5220.9  345.60  5230.9  347.29  5251.0  347.74  5271.1  349.21  5307.5  350.86
#Mann=6,-1,0
  4584.9    0.16       0  4639.8   0.063       0  4901.9    0.16       0
  4988.0    0.07       0  4992.0    0.16       0  5199.1   0.063       0
Bank Sta=4988,4992
Exp/Cntr=0.3,0.1

Type RM Length L Ch R = 1,6109,325,325,325
BEGIN DESCRIPTION:
North Twin Creek Trib L6109.28
END DESCRIPTION:
XS GIS Cut Line= 3
      2708041.14      6810268.44      2707624.95      6810238.17
      2707349.35      6810211.24
#Sta/Elev= 30
  4583.8  353.99  4635.1  349.73  4649.1  349.15  4659.1  347.77  4679.2  347.26
  4719.3  344.79  4729.3  343.45  4749.4  344.42  4769.4  342.90  4799.5  342.41
  4878.3  339.54  4929.8  338.06  4959.9  338.56  4980.0  339.70  4996.1  334.42
  4996.3  333.92  4999.8  333.92  5000.1  334.42  5019.3  339.47  5024.3  337.94
  5030.2  339.75  5040.2  340.35  5050.3  339.80  5086.9  340.68  5100.5  340.97
  5125.9  343.33  5180.9  345.54  5201.0  347.45  5271.3  351.71  5278.0  353.02
#Mann=6,-1,0
  4583.8    0.16       0  4635.1   0.063       0  4878.3   0.035       0
  4996.1   0.035       0  5000.1   0.035       0  5086.9   0.063       0
Bank Sta=4996.1,5000.1
Exp/Cntr=0.3,0.1

Type RM Length L Ch R = 1,5784,133,133,133
BEGIN DESCRIPTION:
North Twin Creek Trib L5783.9
END DESCRIPTION:
XS GIS Cut Line= 3
      2708062.84      6809990.98      2707719.76      6809949.40
      2707415.35      6809950.26
#Sta/Elev= 30
  4660.3  348.45  4667.2  347.40  4684.4  346.38  4747.8  342.60  4801.2  340.94
  4808.2  340.83  4818.3  339.42  4832.9  339.21  4848.5  339.42  4858.6  338.72
  4888.8  338.18  4908.9  337.04  4969.4  336.30  4989.5  335.40  4997.6  332.35
  4997.9  331.85  5001.4  331.85  5001.6  332.35  5010.3  332.78  5019.7  335.93
  5029.7  337.04  5129.7  338.24  5139.7  337.84  5159.7  339.17  5169.7  338.92
  5179.7  340.26  5209.7  342.67  5259.7  344.59  5299.7  348.47  5310.3  348.95
#Mann=6,-1,0
  4660.3    0.16       0  4684.4   0.063       0  4801.2   0.035       0
  4832.9   0.063       0  4997.6   0.063       0  5001.6   0.063       0
Bank Sta=4997.6,5001.6
Exp/Cntr=0.3,0.1

Type RM Length L Ch R = 1,5651,274,274,274
BEGIN DESCRIPTION:
North Twin Creek Trib L5651.42
END DESCRIPTION:
XS GIS Cut Line= 3
      2708039.92      6809837.20      2707773.12      6809833.72
      2707460.59      6809821.41
#Sta/Elev= 30
  4736.3  345.22  4760.2  344.58  4831.9  340.73  4850.2  339.28  4880.2  338.56
  4890.2  337.17  4900.2  336.66  4920.2  337.40  4960.2  336.45  4980.2  336.66
  4990.2  335.05  4999.2  328.32  5003.1  328.32  5010.2  325.58  5018.3  323.51
  5018.5  323.01  5022.0  323.01  5022.3  323.51  5030.3  324.00  5050.3  332.89
  5060.3  334.90  5070.3  335.93  5130.3  336.51  5180.4  338.16  5190.4  337.59
  5197.4  338.44  5220.4  338.49  5240.4  340.90  5260.4  342.20  5315.9  344.65
#Mann=3,-1,0
  4736.3   0.063       0  5018.3   0.063       0  5022.3   0.063       0
Bank Sta=5018.3,5022.3
Exp/Cntr=0.3,0.1

Type RM Length L Ch R = 1,5377,236,236,236
BEGIN DESCRIPTION:
North Twin Creek Trib L5377.19
END DESCRIPTION:
XS GIS Cut Line= 3
      2708078.41      6809559.95      2707775.17      6809559.54
      2707406.90      6809587.95
#Sta/Elev= 30
  4697.6  346.35  4710.0  345.84  4780.0  340.17  4800.0  339.18  4810.0  337.48
  4830.0  337.98  4850.0  337.09  4910.0  337.10  4930.0  336.56  4940.0  334.19
  4960.0  326.07  4970.0  324.27  4978.0  322.00  4978.3  321.50  4981.8  321.50
  4982.0  322.00  5010.0  322.00  5020.1  324.47  5030.1  328.15  5040.1  330.10
  5050.2  333.10  5085.1  334.11  5100.3  335.23  5130.4  336.35  5190.6  340.18
  5220.7  340.48  5230.7  342.49  5280.8  343.87  5331.0  346.11  5370.2  348.90
#Mann=3,-1,0
  4697.6   0.063       0  4978.0   0.063       0  4982.0   0.063       0
Bank Sta=4978,4982
Exp/Cntr=0.3,0.1

Type RM Length L Ch R = 1,5141,298,298,298
BEGIN DESCRIPTION:
North Twin Creek Trib L5141.25
END DESCRIPTION:
XS GIS Cut Line= 3
      2708122.26      6809329.33      2707775.03      6809323.58
      2707380.75      6809377.33
#Sta/Elev= 30
  4653.7  344.85  4670.0  343.07  4760.0  338.63  4790.0  338.27  4820.0  337.16
  4855.0  336.90  4880.0  335.54  4920.0  335.05  4940.0  333.09  4950.0  330.95
  4960.0  324.89  4968.0  322.00  4968.3  321.50  4971.8  321.50  4972.0  322.00
  5010.1  322.00  5017.0  324.91  5022.1  325.08  5030.3  327.21  5040.4  330.99
  5050.5  332.61  5121.1  335.38  5141.3  335.34  5171.8  336.63  5181.7  335.95
  5191.8  336.96  5211.9  336.95  5239.1  338.79  5388.8  344.81  5398.9  345.73
#Mann=3,-1,0
  4653.7   0.063       0  4968.0   0.063       0  4972.0   0.063       0
Bank Sta=4968,4972
Exp/Cntr=0.3,0.1

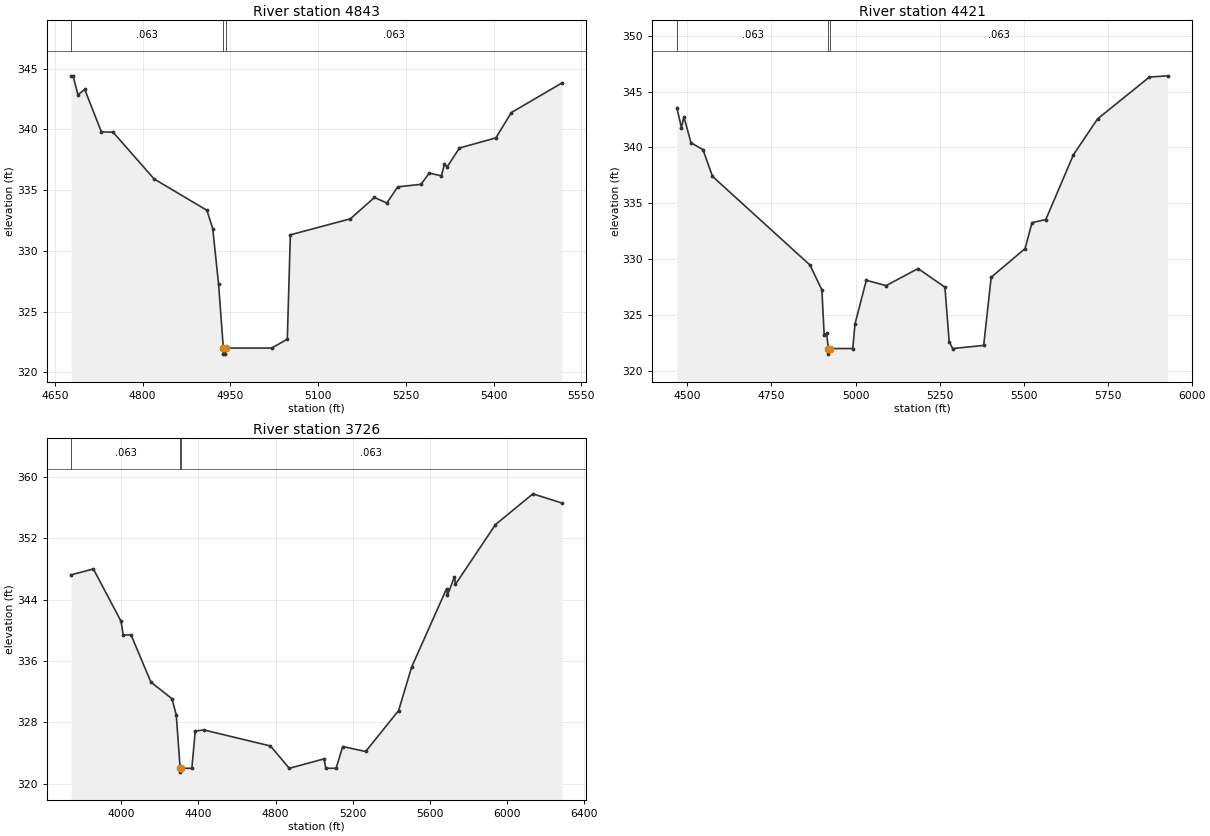
Type RM Length L Ch R = 1,4843,422,422,422
BEGIN DESCRIPTION:
North Twin Creek Trib L4842.77
END DESCRIPTION:
XS GIS Cut Line= 3
      2708097.44      6809047.35      2707770.81      6809024.76
      2707277.03      6809158.54
#Sta/Elev= 30
  4677.8  344.41  4681.0  344.41  4689.3  342.85  4700.9  343.29  4729.4  339.80
  4749.4  339.77  4819.6  335.92  4909.8  333.34  4919.8  331.83  4929.8  327.26
  4937.9  322.00  4938.1  321.50  4941.6  321.50  4941.9  322.00  5020.6  322.00
  5047.3  322.73  5052.5  331.32  5155.2  332.64  5196.3  334.40  5217.4  333.94
  5236.2  335.27  5276.0  335.48  5289.9  336.40  5310.7  336.18  5315.9  337.12
  5321.0  336.94  5341.7  338.47  5403.9  339.30  5430.2  341.38  5516.8  343.82
#Mann=3,-1,0
  4677.8   0.063       0  4937.9   0.063       0  4941.9   0.063       0
Bank Sta=4937.9,4941.9
Exp/Cntr=0.3,0.1

Type RM Length L Ch R = 1,4421,695,695,695
BEGIN DESCRIPTION:
North Twin Creek Trib L4421.02
END DESCRIPTION:
XS GIS Cut Line= 3
      2708087.54      6809009.06      2707722.96      6808616.27
      2706823.51      6808405.63
#Sta/Elev= 30
  4468.5  343.57  4482.2  341.77  4489.6  342.74  4510.6  340.42  4546.3  339.80
  4574.6  337.41  4864.3  329.48  4900.0  327.25  4906.8  323.23  4914.2  323.36
  4919.0  322.00  4919.3  321.50  4923.0  322.00  4991.9  322.00  4998.5  324.20
  5032.1  328.11  5091.0  327.63  5186.2  329.16  5266.0  327.49  5278.6  322.63
  5288.9  322.00  5381.3  322.28  5403.6  328.38  5504.5  330.95  5525.1  333.27
  5566.2  333.55  5648.3  339.35  5720.2  342.56  5874.3  346.30  5928.2  346.41
#Mann=3,-1,0
  4468.5   0.063       0  4919.0   0.063       0  4923.0   0.063       0
Bank Sta=4919,4923
Exp/Cntr=0.3,0.1

Type RM Length L Ch R = 1,3726,0,0,0
BEGIN DESCRIPTION:
North Twin Creek Trib L3726.303
END DESCRIPTION:
XS GIS Cut Line= 3
      2708201.02      6809086.04      2707675.83      6807940.93
      2706429.95      6808249.79
#Sta/Elev= 30
  3740.2  347.23  3855.2  347.99  3998.7  341.16  4009.8  339.36  4050.2  339.41
  4153.2  333.24  4262.6  331.07  4284.8  328.94  4304.8  322.00  4305.1  321.50
  4308.8  322.00  4365.6  322.00  4383.1  326.86  4427.8  327.00  4773.1  324.91
  4870.5  322.00  5051.3  323.23  5059.6  322.01  5113.2  322.00  5147.5  324.84
  5266.5  324.19  5437.2  329.53  5504.7  335.20  5685.5  345.40  5690.6  344.57
  5726.9  346.98  5732.0  345.99  5938.9  353.77  6133.1  357.79  6283.6  356.59
#Mann=3,-1,0
  3740.2   0.063       0  4304.8   0.063       0  4308.8   0.063       0
Bank Sta=4304.8,4308.8
Exp/Cntr=0.3,0.1

Chan Stop Cuts=-1