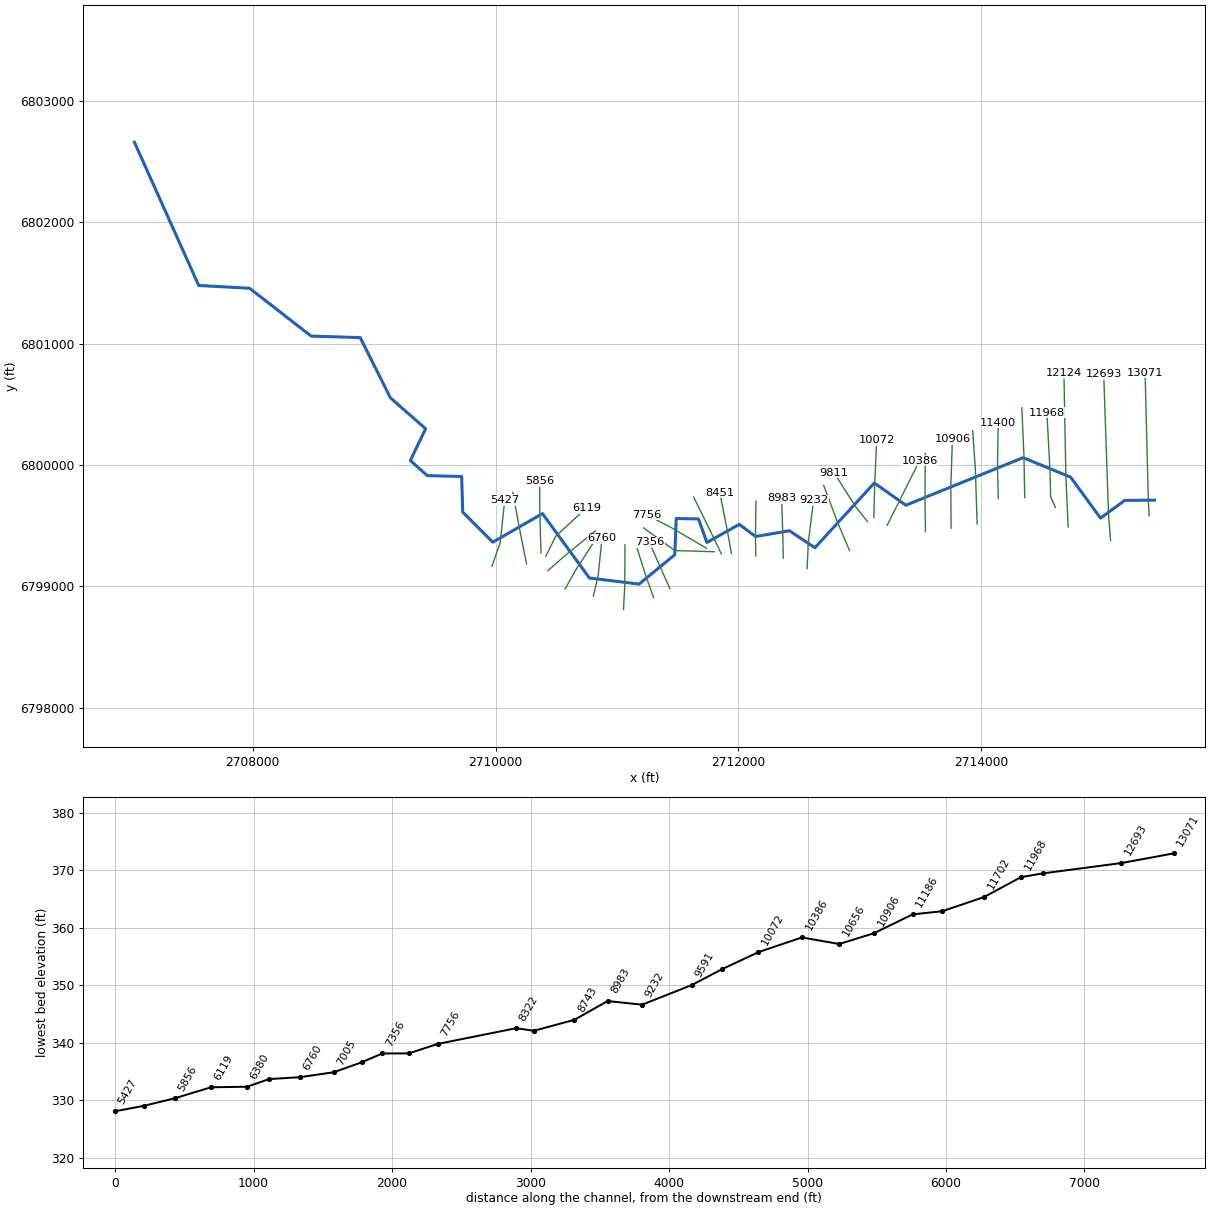
--- North Twin Creek Trib M.prj (project) ---

Proj Title=North Twin Creek Trib M Base Level Engineering
Current Plan=p01
Default Exp/Contr=0.3,0.1
English Units
Geom File=g01
Flow File=f01
Plan File=p01
BEGIN DESCRIPTION:
North Twin Creek Trib M
END DESCRIPTION:

--- North Twin Creek Trib M.p01 (plan) ---

Plan Title=Multiple Run
Short Identifier=Multiple
Geom File=g01
Flow File=f01
Subcritical Flow
K Sum by GR= 0
Std Step Tol= 0.01
Critical Tol= 0.01
Num of Std Step Trials= 20
Max Error Tol= 0.3
Flow Tol Ratio= 0.001
Split Flow NTrial= 30
Split Flow Tol= 0.02
Split Flow Ratio= 0.02
Log Output Level= 0
Friction Slope Method= 1
Unsteady Friction Slope Method= 2
Unsteady Bridges Friction Slope Method= 1
Parabolic Critical Depth
Global Vel Dist=  1 , 1 , 1
Global Log Level= 0
CheckData=True
Encroach Param= -1, 0, 0, 0
BEGIN DESCRIPTION:
Multiple Run
END DESCRIPTION:

--- North Twin Creek Trib M.f01 (steady flow) ---

Flow Title=Multiple
Number of Profiles=7
Profile Names=10-year,25-year,50-year,1pct_min,100-year,1pct_plu,500-year
River Rch & RM= North Twin Creek,Reach-1,13071
     390     509     602     354     706    1408     969
River Rch & RM= North Twin Creek,Reach-1,7356
     618     827     995     594    1185    2365    1681
River Rch & RM= North Twin Creek,Reach-1,2802
     760    1026    1242     744    1485    2964    2125
Boundary for River Rch & Prof#=North Twin Creek,Reach-1,1
Up Type=0
Dn Type=3
Dn Slope=0.005
Boundary for River Rch & Prof#=North Twin Creek,Reach-1,2
Up Type=0
Dn Type=3
Dn Slope=0.005
Boundary for River Rch & Prof#=North Twin Creek,Reach-1,3
Up Type=0
Dn Type=3
Dn Slope=0.005
Boundary for River Rch & Prof#=North Twin Creek,Reach-1,4
Up Type=0
Dn Type=3
Dn Slope=0.005
Boundary for River Rch & Prof#=North Twin Creek,Reach-1,5
Up Type=0
Dn Type=3
Dn Slope=0.005
Boundary for River Rch & Prof#=North Twin Creek,Reach-1,6
Up Type=0
Dn Type=3
Dn Slope=0.005
Boundary for River Rch & Prof#=North Twin Creek,Reach-1,7
Up Type=0
Dn Type=3
Dn Slope=0.005

--- North Twin Creek Trib M.g01 (geometry) ---

Geom Title=Existing Conditions

River Reach=North Twin Creek,Reach-1
Reach XY= 30
      2715426.00      6799711.00      2715181.85      6799708.94
      2714982.05      6799562.59      2714736.00      6799900.39
      2714344.74      6800061.15      2713379.33      6799669.01
      2713119.34      6799852.05      2712629.66      6799318.67
      2712420.14      6799458.94      2712141.34      6799410.96
      2712007.59      6799511.37      2711740.74      6799361.74
      2711670.92      6799555.97      2711487.79      6799559.38
      2711476.00      6799261.00      2711182.19      6799018.81
      2710772.76      6799069.24      2710386.41      6799600.08
      2709977.50      6799364.46      2709729.54      6799612.46
      2709721.00      6799906.00      2709437.95      6799912.92
      2709298.43      6800037.59      2709424.32      6800299.46
      2709133.81      6800554.79      2708885.84      6801050.61
      2708481.44      6801063.17      2707974.45      6801457.25
      2707555.45      6801480.44      2707026.00      6802661.00

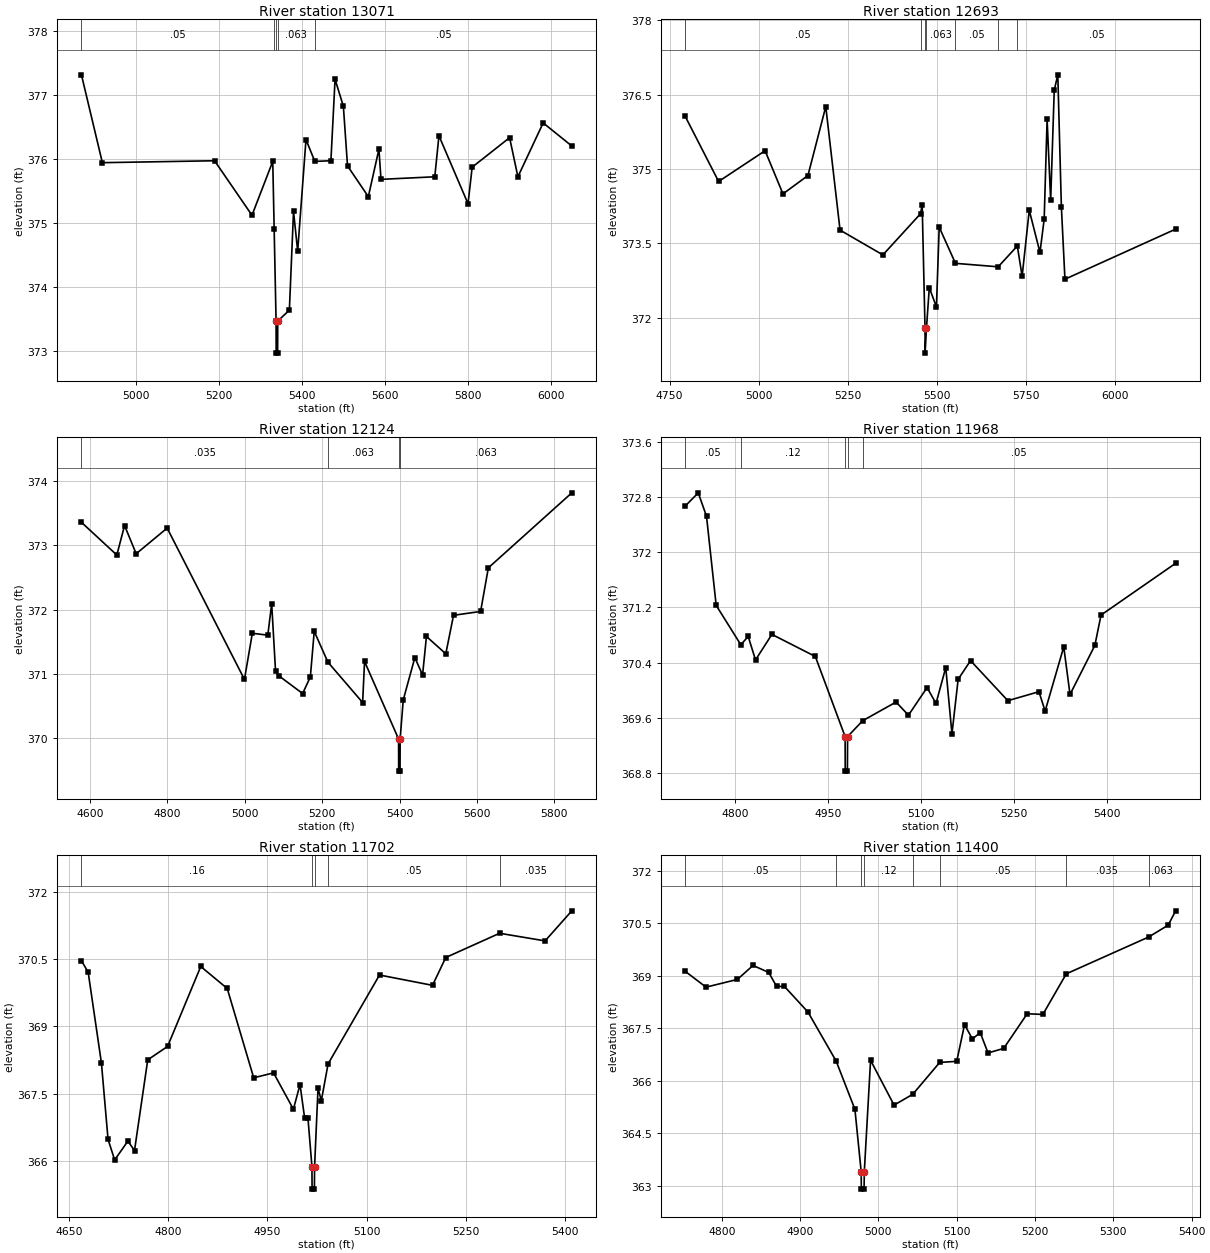
Type RM Length L Ch R = 1,13071,378,378,378
BEGIN DESCRIPTION:
North Twin Creek Trib M13071.396
END DESCRIPTION:
XS GIS Cut Line= 3
      2715382.63      6799580.69      2715376.00      6799711.00
      2715349.13      6800760.78
#Sta/Elev= 30
  4869.5  377.31  4919.9  375.94  5190.0  375.97  5280.1  375.12  5330.1  375.96
  5333.5  374.90  5338.1  373.47  5338.3  372.97  5341.8  372.97  5342.1  373.47
  5370.1  373.64  5380.1  375.18  5390.1  374.56  5410.1  376.30  5431.4  375.96
  5470.1  375.97  5480.1  377.24  5500.1  376.82  5510.1  375.89  5560.2  375.41
  5585.7  376.15  5590.7  375.68  5720.2  375.72  5730.2  376.36  5800.2  375.30
  5810.2  375.87  5900.3  376.33  5920.3  375.72  5981.1  376.56  6050.1  376.20
#Mann=5,-1,0
  4869.5    0.05       0  5333.5   0.063       0  5338.1    0.05       0
  5342.1   0.063       0  5431.4    0.05       0
Bank Sta=5338.1,5342.1
Exp/Cntr=0.3,0.1

Type RM Length L Ch R = 1,12693,569,569,569
BEGIN DESCRIPTION:
North Twin Creek Trib M12693.24
END DESCRIPTION:
XS GIS Cut Line= 3
      2715064.68      6799377.91      2715048.37      6799590.74
      2715008.11      6800751.19
#Sta/Elev= 30
  4794.1  376.06  4887.5  374.75  5017.8  375.37  5067.9  374.50  5137.9  374.87
  5187.9  376.26  5227.9  373.77  5348.0  373.27  5453.5  374.10  5458.1  374.28
  5466.1  371.79  5466.3  371.29  5470.1  371.79  5478.1  372.61  5498.1  372.22
  5505.8  373.83  5551.4  373.10  5671.2  373.03  5724.8  373.45  5738.3  372.84
  5758.3  374.17  5788.3  373.32  5800.1  373.99  5808.3  376.00  5818.3  374.37
  5828.3  376.59  5838.3  376.90  5848.3  374.24  5858.3  372.78  6168.7  373.79
#Mann=7,-1,0
  4794.1    0.05       0  5453.5   0.063       0  5466.1    0.05       0
  5470.1   0.063       0  5551.4    0.05       0  5671.2   0.035       0
  5724.8    0.05       0
Bank Sta=5466.1,5470.1
Exp/Cntr=0.3,0.1

Type RM Length L Ch R = 1,12124,156,156,156
BEGIN DESCRIPTION:
North Twin Creek Trib M12123.56
END DESCRIPTION:
XS GIS Cut Line= 3
      2714715.33      6799489.59      2714696.72      6799915.15
      2714680.72      6800756.73
#Sta/Elev= 30
  4577.6  373.36  4669.1  372.85  4689.1  373.31  4719.1  372.87  4799.2  373.27
  4999.0  370.91  5019.4  371.63  5059.4  371.60  5069.4  372.09  5079.4  371.04
  5089.4  370.96  5149.4  370.69  5169.4  370.95  5179.4  371.66  5214.7  371.18
  5304.5  370.55  5309.5  371.19  5397.5  369.98  5397.7  369.48  5401.2  369.48
  5401.5  369.98  5409.5  370.59  5439.5  371.25  5459.5  370.98  5469.5  371.58
  5519.5  371.31  5539.5  371.91  5609.5  371.97  5629.5  372.65  5845.3  373.82
#Mann=4,-1,0
  4577.6   0.035       0  5214.7   0.063       0  5397.5   0.035       0
  5401.5   0.063       0
Bank Sta=5397.5,5401.5
Exp/Cntr=0.3,0.1

Type RM Length L Ch R = 1,11968,266,266,266
BEGIN DESCRIPTION:
North Twin Creek Trib M11967.67
END DESCRIPTION:
XS GIS Cut Line= 4
      2714610.56      6799649.63      2714571.32      6799739.61
      2714566.87      6799932.94      2714540.71      6800431.11
#Sta/Elev= 30
  4719.8  372.67  4740.7  372.86  4754.0  372.52  4769.6  371.23  4809.3  370.66
  4821.2  370.78  4833.0  370.44  4859.4  370.81  4929.4  370.49  4977.4  369.33
  4977.6  368.83  4981.1  368.83  4981.4  369.33  5005.7  369.56  5059.5  369.83
  5079.5  369.64  5109.5  370.04  5123.9  369.81  5139.6  370.33  5149.6  369.37
  5159.6  370.16  5179.6  370.43  5239.7  369.85  5289.8  369.98  5299.8  369.70
  5329.8  370.63  5339.9  369.94  5379.9  370.65  5389.9  371.09  5510.2  371.84
#Mann=5,-1,0
  4719.8    0.05       0  4809.3    0.12       0  4977.4    0.07       0
  4981.4    0.12       0  5005.7    0.05       0
Bank Sta=4977.4,4981.4
Exp/Cntr=0.3,0.1

Type RM Length L Ch R = 1,11702,302,302,302
BEGIN DESCRIPTION:
North Twin Creek Trib M11702.27
END DESCRIPTION:
XS GIS Cut Line= 3
      2714357.91      6799730.77      2714351.91      6800070.01
      2714333.87      6800471.32
#Sta/Elev= 30
  4669.2  370.46  4679.4  370.20  4699.4  368.18  4709.4  366.48  4719.4  366.02
  4739.4  366.44  4749.4  366.23  4769.4  368.25  4799.4  368.55  4849.5  370.33
  4889.5  369.84  4929.5  367.85  4959.5  367.96  4989.5  367.15  4999.5  367.70
  5006.5  366.95  5011.5  366.95  5017.5  365.87  5017.7  365.37  5021.2  365.37
  5021.5  365.87  5026.7  367.62  5031.7  367.34  5041.9  368.16  5119.6  370.14
  5199.7  369.91  5219.7  370.53  5301.1  371.07  5369.8  370.90  5410.2  371.57
#Mann=5,-1,0
  4669.2    0.16       0  5017.5    0.07       0  5021.5    0.16       0
  5041.9    0.05       0  5301.1   0.035       0
Bank Sta=5017.5,5021.5
Exp/Cntr=0.3,0.1

Type RM Length L Ch R = 1,11400,214,214,214
BEGIN DESCRIPTION:
North Twin Creek Trib M11399.6
END DESCRIPTION:
XS GIS Cut Line= 3
      2714140.39      6799724.49      2714133.62      6799973.78
      2714139.67      6800350.55
#Sta/Elev= 30
  4753.4  369.12  4779.9  368.67  4819.9  368.89  4839.9  369.29  4859.9  369.09
  4870.0  368.69  4880.0  368.69  4910.0  367.96  4946.0  366.56  4970.0  365.18
  4978.0  363.40  4978.2  362.90  4981.7  362.90  4982.0  363.40  4990.0  366.58
  5020.0  365.30  5043.9  365.61  5078.3  366.52  5100.0  366.55  5110.0  367.60
  5120.0  367.19  5130.0  367.37  5140.0  366.79  5160.0  366.92  5190.0  367.91
  5210.0  367.89  5239.9  369.05  5344.9  370.10  5370.0  370.44  5379.6  370.85
#Mann=8,-1,0
  4753.4    0.05       0  4946.0    0.12       0  4978.0    0.07       0
  4982.0    0.12       0  5043.9    0.07       0  5078.3    0.05       0
  5239.9   0.035       0  5344.9   0.063       0
Bank Sta=4978,4982
Exp/Cntr=0.3,0.1

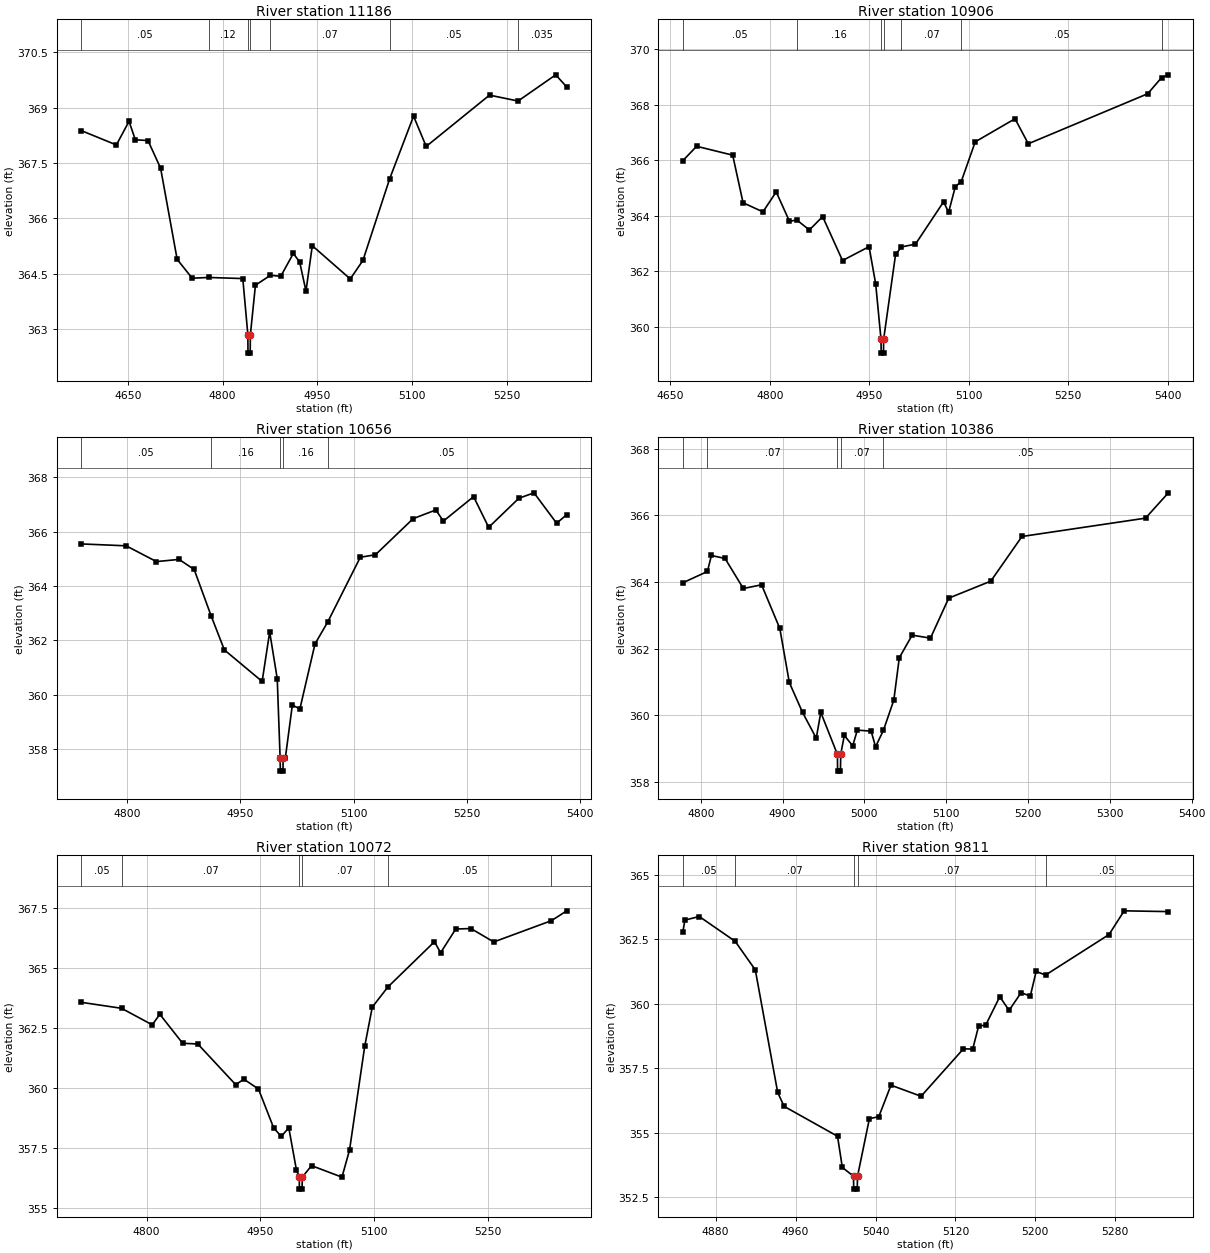
Type RM Length L Ch R = 1,11186,280,280,280
BEGIN DESCRIPTION:
North Twin Creek Trib M11185.9
END DESCRIPTION:
XS GIS Cut Line= 3
      2713965.80      6799515.35      2713952.09      6799952.30
      2713929.79      6800282.98
#Sta/Elev= 30
  4576.3  368.38  4632.0  367.99  4652.0  368.63  4662.0  368.13  4682.0  368.11
  4702.0  367.36  4728.2  364.89  4752.0  364.38  4778.0  364.40  4832.1  364.37
  4840.1  362.85  4840.3  362.35  4843.8  362.35  4844.1  362.85  4852.1  364.19
  4875.9  364.46  4892.1  364.43  4912.1  365.05  4922.1  364.82  4932.1  364.03
  4942.1  365.26  5002.2  364.36  5022.2  364.86  5064.7  367.08  5102.4  368.77
  5122.4  367.95  5222.6  369.34  5267.8  369.18  5327.4  369.89  5344.9  369.56
#Mann=7,-1,0
  4576.3    0.05       0  4778.0    0.12       0  4840.1    0.07       0
  4844.1    0.12       0  4875.9    0.07       0  5064.7    0.05       0
  5267.8   0.035       0
Bank Sta=4840.1,4844.1
Exp/Cntr=0.3,0.1

Type RM Length L Ch R = 1,10906,250,250,250
BEGIN DESCRIPTION:
North Twin Creek Trib M10906.48
END DESCRIPTION:
XS GIS Cut Line= 3
      2713751.50      6799480.09      2713749.26      6799817.76
      2713762.27      6800212.07
#Sta/Elev= 30
  4668.9  365.98  4689.8  366.50  4744.2  366.18  4759.8  364.47  4789.8  364.14
  4809.8  364.86  4829.8  363.80  4840.8  363.85  4859.8  363.49  4879.8  363.97
  4909.8  362.39  4949.8  362.89  4959.8  361.55  4967.8  359.56  4968.1  359.06
  4971.6  359.06  4971.8  359.56  4989.8  362.61  4998.7  362.88  5019.8  362.98
  5062.1  364.50  5069.8  364.13  5079.9  365.05  5088.8  365.23  5109.9  366.66
  5169.9  367.49  5189.9  366.59  5370.0  368.39  5390.9  368.97  5401.1  369.07
#Mann=7,-1,0
  4668.9    0.05       0  4840.8    0.16       0  4967.8    0.07       0
  4971.8    0.16       0  4998.7    0.07       0  5088.8    0.05       0
  5390.9   0.063       0
Bank Sta=4967.8,4971.8
Exp/Cntr=0.3,0.1

Type RM Length L Ch R = 1,10656,270,270,270
BEGIN DESCRIPTION:
North Twin Creek Trib M10656.31
END DESCRIPTION:
XS GIS Cut Line= 3
      2713540.71      6799451.42      2713536.44      6799717.62
      2713538.82      6800094.38
#Sta/Elev= 30
  4739.1  365.55  4798.7  365.48  4838.7  364.90  4868.7  364.98  4888.7  364.61
  4911.2  362.90  4928.7  361.65  4978.7  360.49  4988.7  362.31  4998.7  360.59
  5002.5  357.69  5002.8  357.19  5006.3  357.19  5006.5  357.69  5009.5  357.69
  5018.7  359.62  5028.7  359.48  5048.7  361.87  5065.6  362.68  5108.7  365.06
  5128.7  365.15  5178.7  366.48  5208.7  366.80  5218.7  366.39  5258.7  367.29
  5278.7  366.16  5318.7  367.23  5338.7  367.43  5368.7  366.31  5382.1  366.63
#Mann=5,-1,0
  4739.1    0.05       0  4911.2    0.16       0  5002.5    0.07       0
  5006.5    0.16       0  5065.6    0.05       0
Bank Sta=5002.5,5006.5
Exp/Cntr=0.3,0.1

Type RM Length L Ch R = 1,10386,314,314,314
BEGIN DESCRIPTION:
North Twin Creek Trib M10385.99
END DESCRIPTION:
XS GIS Cut Line= 3
      2713225.10      6799504.87      2713327.10      6799706.32
      2713491.42      6800035.15
#Sta/Elev= 30
  4778.1  363.98  4808.2  364.32  4813.1  364.80  4829.8  364.71  4852.1  363.81
  4874.4  363.92  4896.7  362.61  4908.3  360.99  4924.5  360.09  4941.2  359.32
  4946.8  360.09  4967.1  358.83  4967.3  358.33  4970.8  358.33  4971.1  358.83
  4975.5  359.40  4985.8  359.09  4991.4  359.56  5008.3  359.53  5013.7  359.06
  5023.4  359.56  5036.0  360.46  5042.7  361.73  5058.4  362.41  5080.8  362.32
  5103.1  363.52  5154.5  364.03  5192.6  365.37  5343.6  365.92  5371.5  366.68
#Mann=5,-1,0
  4778.1    0.05       0  4808.2    0.07       0  4967.1    0.07       0
  4971.1    0.07       0  5023.4    0.05       0
Bank Sta=4967.1,4971.1
Exp/Cntr=0.3,0.1

Type RM Length L Ch R = 1,10072,261,261,261
BEGIN DESCRIPTION:
North Twin Creek Trib M10072.25
END DESCRIPTION:
XS GIS Cut Line= 3
      2713115.17      6799567.29      2713123.22      6799857.50
      2713139.01      6800207.23
#Sta/Elev= 30
  4713.7  363.57  4766.9  363.32  4807.4  362.63  4817.4  363.07  4847.5  361.86
  4867.5  361.83  4917.5  360.13  4928.2  360.36  4947.5  359.95  4967.5  358.33
  4977.5  357.97  4987.5  358.33  4997.5  356.58  5001.3  356.27  5001.5  355.77
  5005.0  355.77  5005.3  356.27  5017.5  356.75  5057.6  356.27  5067.6  357.40
  5087.6  361.73  5097.6  363.37  5118.2  364.21  5179.6  366.10  5187.7  365.64
  5207.7  366.63  5227.7  366.65  5257.8  366.09  5333.9  366.98  5354.1  367.39
#Mann=6,-1,0
  4713.7    0.05       0  4766.9    0.07       0  5001.3    0.07       0
  5005.3    0.07       0  5118.2    0.05       0  5333.9   0.035       0
Bank Sta=5001.3,5005.3
Exp/Cntr=0.3,0.1

Type RM Length L Ch R = 1,9811,220,220,220
BEGIN DESCRIPTION:
North Twin Creek Trib M9810.9
END DESCRIPTION:
XS GIS Cut Line= 3
      2713062.59      6799534.66      2712966.05      6799655.83
      2712788.63      6799935.36
#Sta/Elev= 30
  4847.1  362.77  4849.2  363.25  4863.6  363.39  4899.5  362.43  4919.7  361.32
  4942.1  356.57  4948.5  356.03  5002.0  354.87  5006.8  353.66  5018.0  353.32
  5018.2  352.82  5021.7  352.82  5022.0  353.32  5033.9  355.55  5043.3  355.63
  5055.5  356.85  5085.6  356.42  5128.0  358.26  5137.3  358.25  5143.2  359.14
  5150.3  359.18  5164.4  360.28  5173.7  359.75  5185.8  360.44  5194.9  360.30
  5200.8  361.26  5210.2  361.12  5273.7  362.69  5288.9  363.61  5333.1  363.58
#Mann=5,-1,0
  4847.1    0.05       0  4899.5    0.07       0  5018.0    0.07       0
  5022.0    0.07       0  5210.2    0.05       0
Bank Sta=5018,5022
Exp/Cntr=0.3,0.1

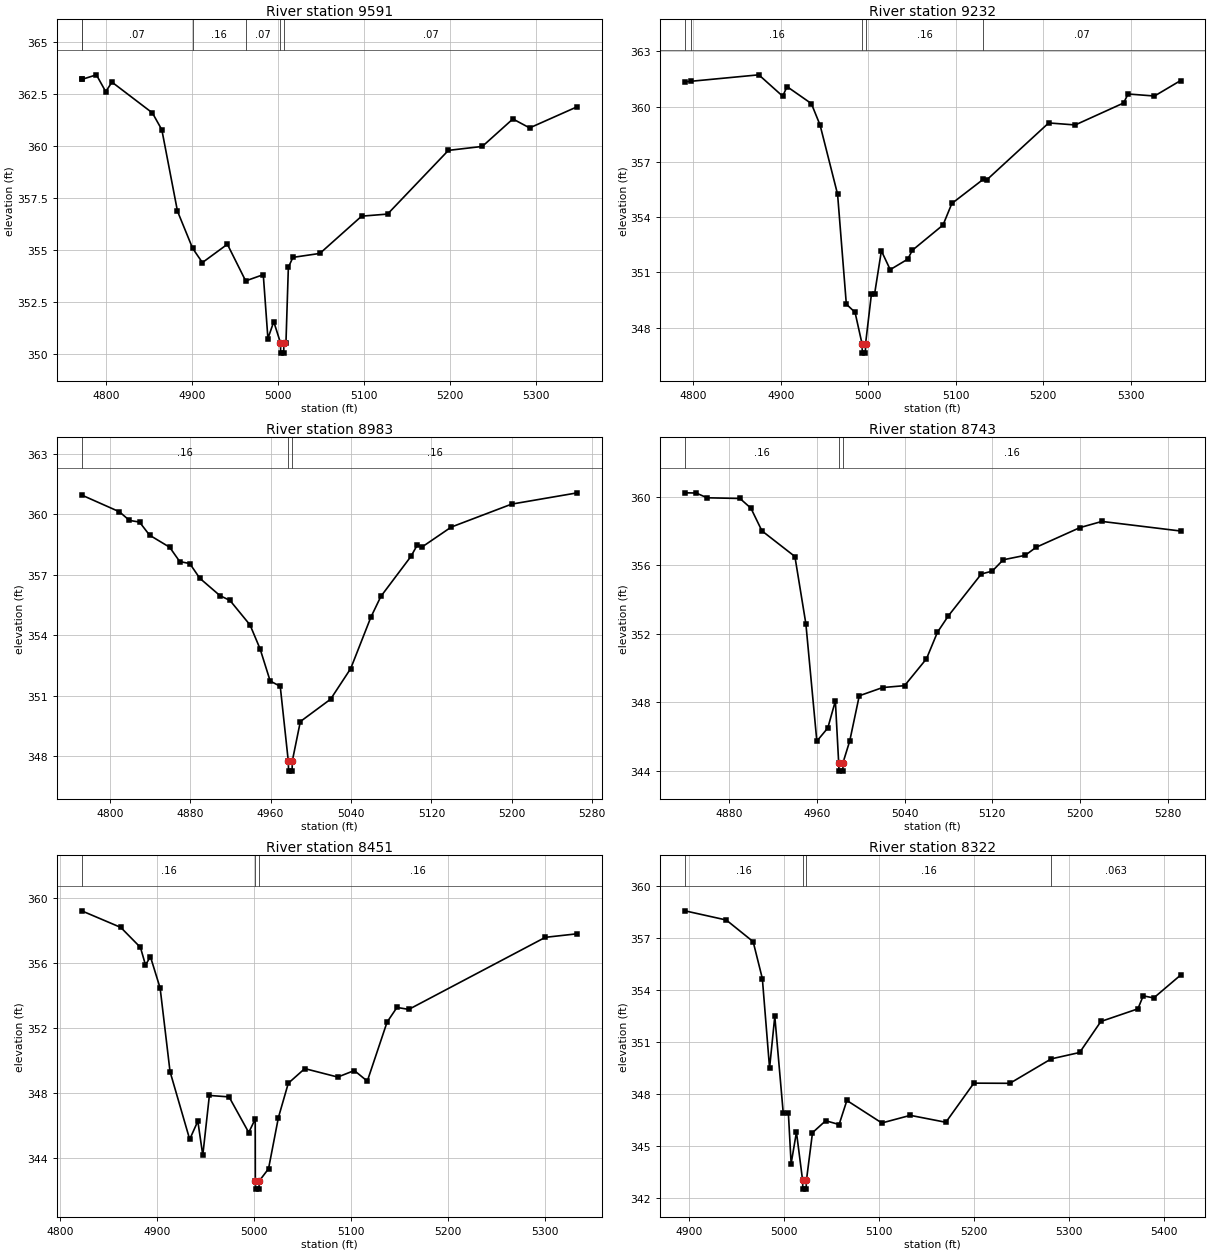
Type RM Length L Ch R = 1,9591,359,359,359
BEGIN DESCRIPTION:
North Twin Creek Trib M9590.9
END DESCRIPTION:
XS GIS Cut Line= 3
      2712915.50      6799295.29      2712822.21      6799513.99
      2712702.78      6799831.61
#Sta/Elev= 30
  4771.4  363.19  4771.6  363.19  4788.5  363.41  4799.4  362.60  4806.6  363.06
  4853.7  361.58  4864.7  360.77  4882.9  356.86  4900.5  355.08  4911.9  354.39
  4941.0  355.27  4962.3  353.51  4982.8  353.81  4988.2  350.74  4995.0  351.55
  5002.8  350.54  5003.1  350.04  5006.6  350.04  5006.8  350.54  5009.2  350.54
  5012.0  354.16  5017.3  354.64  5048.7  354.83  5097.3  356.62  5127.5  356.72
  5198.3  359.78  5237.8  359.97  5273.4  361.29  5292.9  360.86  5348.5  361.88
#Mann=6,-1,0
  4771.4    0.05       0  4771.6    0.07       0  4900.5    0.16       0
  4962.3    0.07       0  5002.8    0.07       0  5006.8    0.07       0
Bank Sta=5002.8,5006.8
Exp/Cntr=0.3,0.1

Type RM Length L Ch R = 1,9232,249,249,249
BEGIN DESCRIPTION:
North Twin Creek Trib M9231.57
END DESCRIPTION:
XS GIS Cut Line= 3
      2712565.88      6799146.58      2712575.62      6799363.30
      2712619.13      6799710.64
#Sta/Elev= 30
  4790.3  361.34  4797.3  361.37  4874.8  361.72  4902.1  360.56  4907.1  361.08
  4934.9  360.16  4944.9  358.99  4964.9  355.24  4974.9  349.28  4984.9  348.83
  4992.9  347.12  4993.2  346.62  4996.7  346.62  4996.9  347.12  5003.6  349.82
  5007.2  349.82  5015.0  352.17  5025.1  351.15  5045.2  351.72  5050.4  352.20
  5085.5  353.57  5095.6  354.74  5131.5  356.05  5136.0  356.04  5206.4  359.11
  5236.7  359.00  5292.0  360.19  5297.2  360.68  5327.4  360.57  5357.3  361.41
#Mann=5,-1,0
  4790.3    0.05       0  4797.3    0.16       0  4992.9    0.07       0
  4996.9    0.16       0  5131.5    0.07       0
Bank Sta=4992.9,4996.9
Exp/Cntr=0.3,0.1

Type RM Length L Ch R = 1,8983,240,240,240
BEGIN DESCRIPTION:
North Twin Creek Trib M8983.33
END DESCRIPTION:
XS GIS Cut Line= 3
      2712369.85      6799233.51      2712364.57      6799463.70
      2712355.61      6799726.40
#Sta/Elev= 30
  4772.1  360.95  4809.6  360.12  4819.6  359.69  4829.6  359.61  4839.6  358.96
  4859.6  358.36  4869.6  357.65  4879.6  357.55  4889.6  356.82  4909.6  355.96
  4919.6  355.72  4939.6  354.50  4949.6  353.31  4959.6  351.72  4969.6  351.46
  4977.6  347.75  4977.9  347.25  4981.4  347.25  4981.6  347.75  4989.6  349.71
  5019.7  350.82  5039.7  352.34  5059.7  354.88  5069.7  355.92  5099.7  357.91
  5105.9  358.47  5110.9  358.38  5139.7  359.36  5199.8  360.50  5265.2  361.06
#Mann=3,-1,0
  4772.1    0.16       0  4977.6    0.07       0  4981.6    0.16       0
Bank Sta=4977.6,4981.6
Exp/Cntr=0.3,0.1

Type RM Length L Ch R = 1,8743,292,292,292
BEGIN DESCRIPTION:
North Twin Creek Trib M8743.04
END DESCRIPTION:
XS GIS Cut Line= 3
      2712142.93      6799250.76      2712140.67      6799413.54
      2712144.34      6799702.82
#Sta/Elev= 30
  4839.7  360.23  4849.9  360.22  4859.9  359.94  4889.9  359.90  4899.9  359.33
  4909.9  358.01  4940.0  356.51  4950.0  352.58  4960.0  345.73  4970.0  346.50
  4976.9  348.08  4979.9  344.48  4980.2  343.98  4983.7  343.98  4983.9  344.48
  4990.0  345.74  4998.7  348.38  5020.0  348.86  5040.0  348.97  5060.0  350.54
  5070.0  352.09  5080.0  353.05  5110.0  355.49  5120.0  355.66  5130.0  356.32
  5150.0  356.58  5160.0  357.05  5200.0  358.20  5220.0  358.56  5291.8  358.00
#Mann=3,-1,0
  4839.7    0.16       0  4979.9    0.07       0  4983.9    0.16       0
Bank Sta=4979.9,4983.9
Exp/Cntr=0.3,0.1

Type RM Length L Ch R = 1,8451,129,129,129
BEGIN DESCRIPTION:
North Twin Creek Trib M8451.28
END DESCRIPTION:
XS GIS Cut Line= 3
      2711942.48      6799271.31      2711910.81      6799450.21
      2711846.40      6799773.48
#Sta/Elev= 30
  4822.0  359.19  4862.3  358.17  4882.6  356.94  4887.8  355.86  4892.9  356.37
  4902.9  354.44  4913.1  349.31  4933.4  345.14  4941.8  346.26  4946.9  344.16
  4953.7  347.84  4974.0  347.75  4994.3  345.56  5001.0  346.39  5001.1  342.58
  5001.4  342.08  5004.9  342.08  5005.1  342.58  5014.7  343.33  5024.9  346.48
  5035.1  348.59  5052.1  349.49  5086.1  348.97  5103.2  349.37  5116.6  348.72
  5137.0  352.35  5147.2  353.25  5159.4  353.13  5300.2  357.56  5333.3  357.78
#Mann=3,-1,0
  4822.0    0.16       0  5001.1    0.07       0  5005.1    0.16       0
Bank Sta=5001.1,5005.1
Exp/Cntr=0.3,0.1

Type RM Length L Ch R = 1,8322,566,566,566
BEGIN DESCRIPTION:
North Twin Creek Trib M8321.71
END DESCRIPTION:
XS GIS Cut Line= 3
      2711859.83      6799267.23      2711813.46      6799365.72
      2711631.16      6799736.35
#Sta/Elev= 30
  4895.4  358.59  4938.9  358.06  4967.2  356.81  4976.9  354.68  4984.5  349.51
  4990.0  352.50  4998.9  346.91  5004.3  346.91  5007.2  343.99  5012.8  345.81
  5019.3  343.02  5019.5  342.52  5023.0  342.52  5023.3  343.02  5029.7  345.78
  5043.6  346.47  5057.7  346.25  5065.9  347.64  5102.7  346.34  5132.7  346.78
  5170.1  346.38  5199.6  348.64  5237.5  348.63  5281.0  350.04  5311.0  350.41
  5333.3  352.20  5372.3  352.93  5377.9  353.68  5389.0  353.56  5417.3  354.88
#Mann=4,-1,0
  4895.4    0.16       0  5019.3    0.07       0  5023.3    0.16       0
  5281.0   0.063       0
Bank Sta=5019.3,5023.3
Exp/Cntr=0.3,0.1

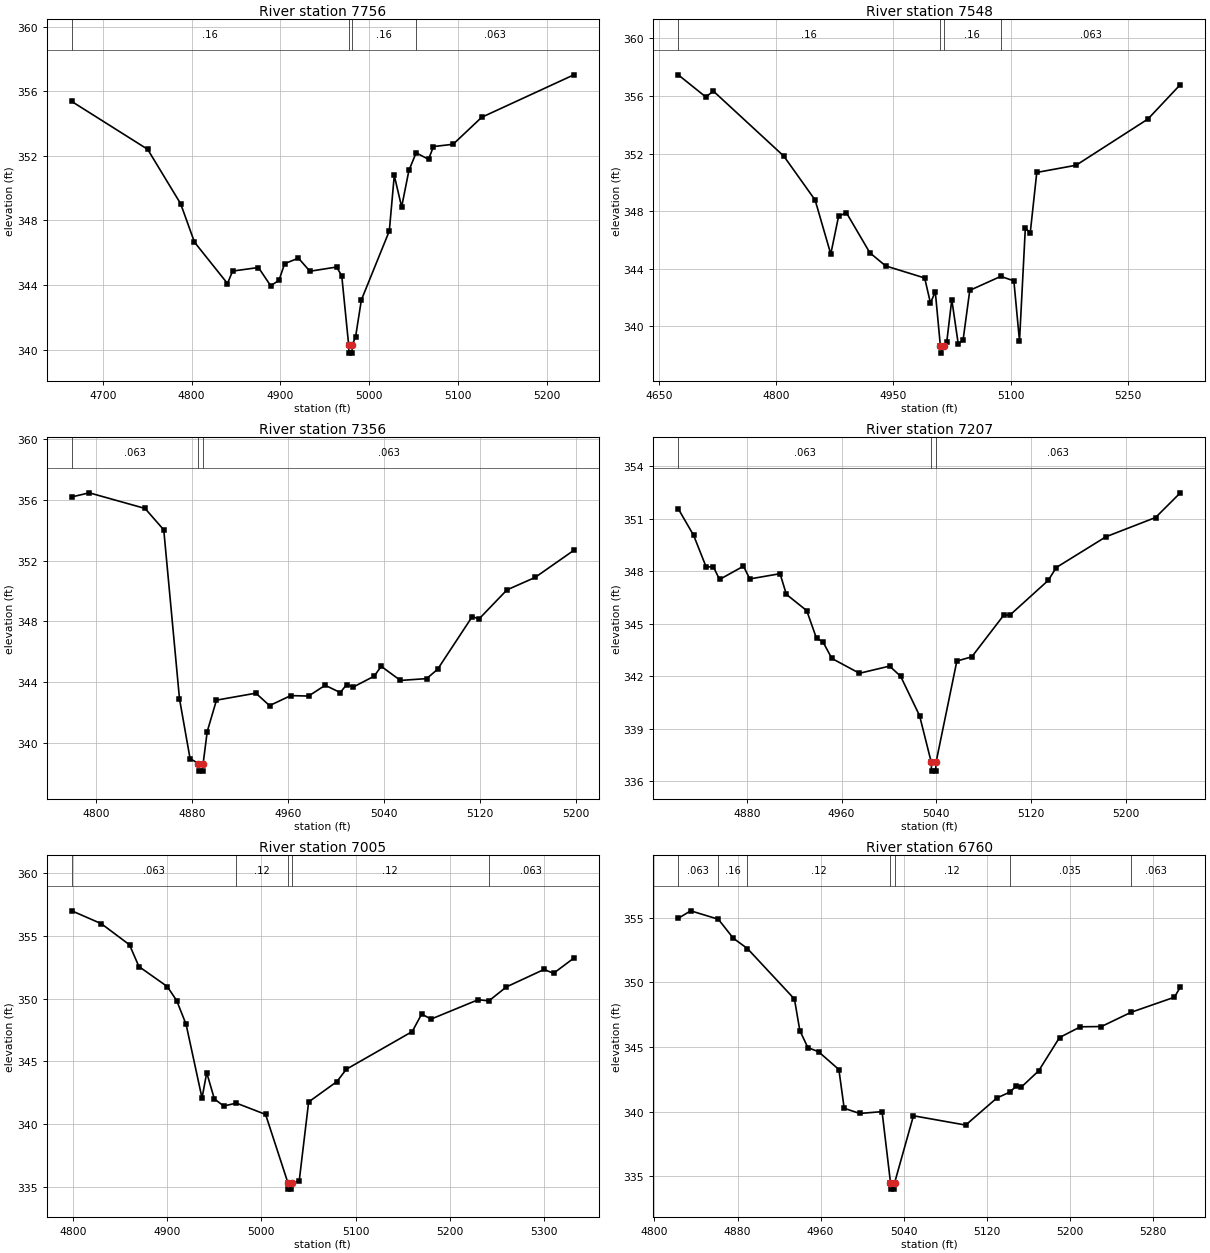
Type RM Length L Ch R = 1,7756,208,208,208
BEGIN DESCRIPTION:
North Twin Creek Trib M7755.58
END DESCRIPTION:
XS GIS Cut Line= 3
      2711737.38      6799314.22      2711446.68      6799485.04
      2711243.87      6799590.79
#Sta/Elev= 30
  4664.9  355.36  4750.4  352.40  4787.6  349.03  4803.2  346.65  4840.4  344.09
  4846.2  344.86  4875.3  345.08  4889.1  343.95  4898.5  344.29  4904.8  345.32
  4920.4  345.66  4933.3  344.85  4963.4  345.11  4969.2  344.57  4977.0  340.28
  4977.3  339.78  4980.8  339.78  4981.0  340.28  4984.8  340.79  4991.3  343.07
  5022.8  347.34  5028.4  350.78  5036.7  348.83  5044.9  351.09  5053.0  352.18
  5067.0  351.78  5072.6  352.57  5094.7  352.71  5126.9  354.38  5230.8  357.01
#Mann=4,-1,0
  4664.9    0.16       0  4977.0    0.07       0  4981.0    0.16       0
  5053.0   0.063       0
Bank Sta=4977,4981
Exp/Cntr=0.3,0.1

Type RM Length L Ch R = 1,7548,192,192,192
BEGIN DESCRIPTION:
North Twin Creek Trib M7547.847
END DESCRIPTION:
XS GIS Cut Line= 3
      2711801.04      6799286.00      2711476.08      6799295.30
      2711219.71      6799481.92
#Sta/Elev= 30
  4674.9  357.47  4710.0  355.94  4720.0  356.33  4810.0  351.82  4850.0  348.77
  4870.0  345.02  4880.0  347.65  4890.0  347.89  4920.0  345.11  4940.1  344.20
  4990.1  343.36  4997.5  341.62  5003.7  342.40  5010.2  338.64  5010.5  338.14
  5014.2  338.64  5018.4  338.93  5024.8  341.86  5033.1  338.76  5039.3  339.07
  5047.8  342.50  5087.4  343.47  5104.2  343.16  5111.4  338.98  5118.9  346.85
  5125.1  346.47  5133.5  350.69  5183.8  351.19  5275.7  354.40  5317.1  356.79
#Mann=4,-1,0
  4674.9    0.16       0  5010.2    0.07       0  5014.2    0.16       0
  5087.4   0.063       0
Bank Sta=5010.2,5014.2
Exp/Cntr=0.3,0.1

Type RM Length L Ch R = 1,7356,149,149,149
BEGIN DESCRIPTION:
North Twin Creek Trib M7355.8
END DESCRIPTION:
XS GIS Cut Line= 3
      2711436.28      6798981.08      2711344.82      6799185.09
      2711267.17      6799363.44
#Sta/Elev= 30
  4780.0  356.20  4794.6  356.47  4841.0  355.44  4856.6  354.03  4869.7  342.89
  4878.5  338.95  4885.4  338.62  4885.6  338.12  4889.1  338.12  4889.4  338.62
  4892.8  340.73  4900.5  342.80  4933.3  343.26  4944.7  342.44  4962.4  343.10
  4977.2  343.07  4991.0  343.78  5003.6  343.30  5008.9  343.83  5014.3  343.66
  5031.8  344.38  5037.7  345.03  5053.7  344.10  5075.5  344.22  5084.6  344.83
  5113.5  348.31  5119.1  348.15  5142.4  350.07  5165.8  350.89  5198.1  352.68
#Mann=3,-1,0
  4780.0   0.063       0  4885.4   0.063       0  4889.4   0.063       0
Bank Sta=4885.4,4889.4
Exp/Cntr=0.3,0.1

Type RM Length L Ch R = 1,7207,202,202,202
BEGIN DESCRIPTION:
North Twin Creek Trib M7207.18
END DESCRIPTION:
XS GIS Cut Line= 3
      2711301.12      6798908.76      2711238.24      6799085.67
      2711166.90      6799310.89
#Sta/Elev= 30
  4822.1  351.57  4835.1  350.05  4845.7  348.24  4851.7  348.26  4857.0  347.53
  4877.2  348.29  4882.5  347.56  4908.1  347.86  4913.4  346.68  4930.6  345.75
  4938.9  344.16  4944.2  343.98  4951.8  343.02  4975.1  342.17  5000.6  342.58
  5009.9  342.00  5025.9  339.75  5035.8  337.08  5036.0  336.58  5039.5  336.58
  5039.8  337.08  5057.4  342.87  5070.0  343.11  5097.1  345.50  5102.3  345.50
  5134.6  347.48  5141.3  348.21  5183.3  349.97  5225.2  351.07  5246.1  352.48
#Mann=3,-1,0
  4822.1   0.063       0  5035.8   0.063       0  5039.8   0.063       0
Bank Sta=5035.8,5039.8
Exp/Cntr=0.3,0.1

Type RM Length L Ch R = 1,7005,245,245,245
BEGIN DESCRIPTION:
North Twin Creek Trib M7004.86
END DESCRIPTION:
XS GIS Cut Line= 3
      2711053.68      6798809.78      2711064.42      6799015.28
      2711065.76      6799342.59
#Sta/Elev= 30
  4798.7  356.98  4830.0  355.96  4860.0  354.28  4870.0  352.55  4900.1  350.96
  4910.1  349.84  4920.1  347.95  4937.0  342.09  4942.0  344.11  4950.1  342.02
  4960.1  341.46  4973.4  341.69  5004.5  340.79  5028.2  335.35  5028.5  334.85
  5032.0  334.85  5032.2  335.35  5040.2  335.50  5050.2  341.78  5080.2  343.40
  5090.2  344.38  5160.2  347.38  5170.2  348.77  5180.2  348.37  5230.2  349.91
  5241.6  349.82  5260.2  350.93  5300.2  352.32  5310.2  352.01  5331.8  353.22
#Mann=5,-1,0
  4798.7   0.063       0  4973.4    0.12       0  5028.2    0.07       0
  5032.2    0.12       0  5241.6   0.063       0
Bank Sta=5028.2,5032.2
Exp/Cntr=0.3,0.1

Type RM Length L Ch R = 1,6760,222,222,222
BEGIN DESCRIPTION:
North Twin Creek Trib M6759.76
END DESCRIPTION:
XS GIS Cut Line= 3
      2710805.30      6798919.34      2710845.43      6799093.39
      2710877.04      6799396.63
#Sta/Elev= 30
  4822.9  354.96  4834.9  355.54  4861.5  354.89  4875.9  353.42  4889.5  352.62
  4934.8  348.71  4940.0  346.27  4947.7  344.95  4958.0  344.63  4977.6  343.25
  4982.7  340.25  4997.7  339.85  5019.2  339.99  5027.3  334.49  5027.5  333.99
  5031.0  333.99  5031.3  334.49  5049.4  339.67  5099.7  338.95  5129.8  341.05
  5142.2  341.50  5148.3  341.96  5153.3  341.89  5170.0  343.15  5190.1  345.73
  5210.2  346.56  5230.4  346.58  5258.9  347.68  5300.7  348.85  5306.4  349.63
#Mann=7,-1,0
  4822.9   0.063       0  4861.5    0.16       0  4889.5    0.12       0
  5027.3    0.07       0  5031.3    0.12       0  5142.2   0.035       0
  5258.9   0.063       0
Bank Sta=5027.3,5031.3
Exp/Cntr=0.3,0.1

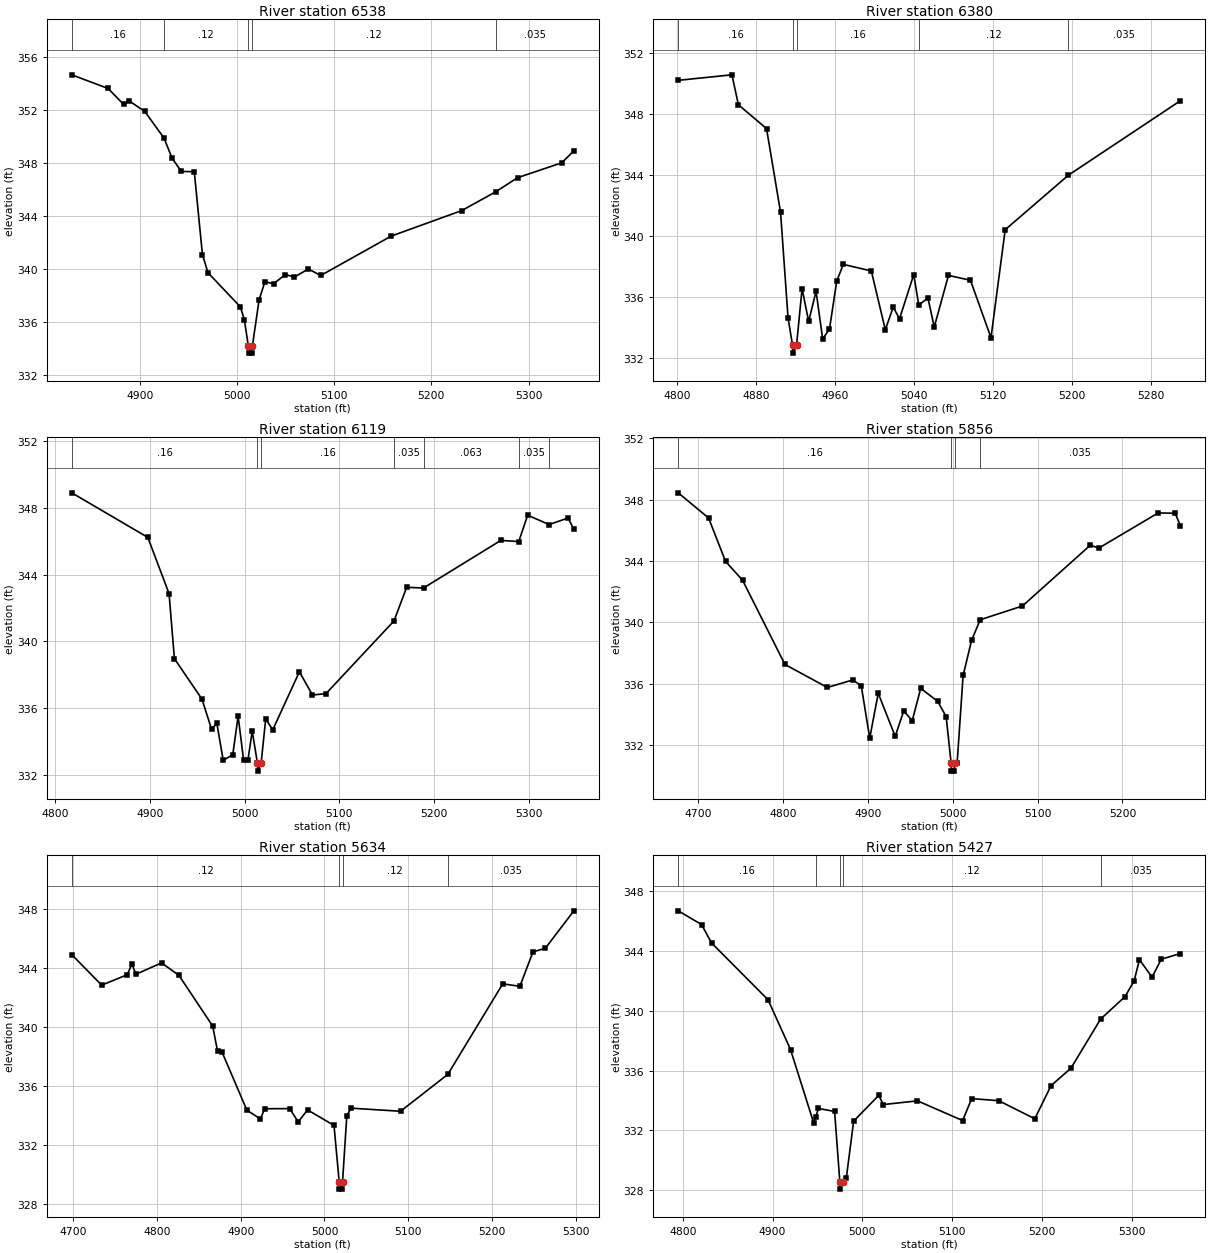
Type RM Length L Ch R = 1,6538,158,158,158
BEGIN DESCRIPTION:
North Twin Creek Trib M6537.6
END DESCRIPTION:
XS GIS Cut Line= 3
      2710574.03      6798981.10      2710658.84      6799132.42
      2710845.29      6799420.23
#Sta/Elev= 30
  4830.2  354.63  4867.6  353.60  4883.5  352.40  4889.3  352.66  4905.2  351.88
  4925.1  349.86  4933.3  348.36  4942.9  347.35  4956.2  347.33  4964.6  341.08
  4970.3  339.72  5003.7  337.14  5007.8  336.13  5011.9  334.16  5012.1  333.66
  5015.6  333.66  5015.9  334.16  5022.9  337.69  5028.9  339.04  5037.7  338.89
  5050.0  339.58  5059.2  339.39  5073.5  340.00  5086.3  339.51  5158.8  342.48
  5231.3  344.40  5266.1  345.81  5288.7  346.88  5334.2  348.00  5346.6  348.90
#Mann=5,-1,0
  4830.2    0.16       0  4925.1    0.12       0  5011.9    0.07       0
  5015.9    0.12       0  5266.1   0.035       0
Bank Sta=5011.9,5015.9
Exp/Cntr=0.3,0.1

Type RM Length L Ch R = 1,6380,261,261,261
BEGIN DESCRIPTION:
North Twin Creek Trib M6380.13
END DESCRIPTION:
XS GIS Cut Line= 3
      2710430.95      6799129.40      2710582.31      6799262.71
      2710821.35      6799455.68
#Sta/Elev= 30
  4801.0  350.19  4855.4  350.55  4862.0  348.59  4890.5  347.03  4904.7  341.56
  4912.3  334.64  4916.9  332.83  4917.2  332.33  4920.9  332.83  4926.5  336.55
  4933.2  334.41  4940.7  336.38  4947.4  333.26  4954.3  333.90  4961.6  337.03
  4968.3  338.14  4996.7  337.71  5010.9  333.86  5018.9  335.34  5025.3  334.58
  5039.7  337.47  5044.8  335.48  5054.1  335.94  5060.5  334.04  5074.9  337.42
  5097.2  337.10  5118.0  333.34  5132.4  340.41  5196.5  343.98  5309.9  348.85
#Mann=5,-1,0
  4801.0    0.16       0  4916.9    0.07       0  4920.9    0.16       0
  5044.8    0.12       0  5196.5   0.035       0
Bank Sta=4916.9,4920.9
Exp/Cntr=0.3,0.1

Type RM Length L Ch R = 1,6119,263,263,263
BEGIN DESCRIPTION:
North Twin Creek Trib M6118.61
END DESCRIPTION:
XS GIS Cut Line= 3
      2710413.47      6799247.99      2710496.11      6799414.44
      2710749.20      6799646.78
#Sta/Elev= 30
  4817.8  348.90  4898.0  346.23  4920.4  342.86  4926.0  338.97  4955.1  336.54
  4965.2  334.74  4970.8  335.09  4977.5  332.87  4987.6  333.22  4993.2  335.53
  4998.9  332.92  5003.6  332.92  5008.1  334.62  5013.5  332.73  5013.8  332.23
  5017.5  332.73  5022.3  335.36  5029.7  334.70  5057.8  338.18  5071.6  336.79
  5085.8  336.87  5157.6  341.23  5170.9  343.24  5188.7  343.20  5270.2  346.05
  5289.1  345.98  5298.5  347.56  5321.1  347.00  5341.1  347.39  5347.2  346.72
#Mann=7,-1,0
  4817.8    0.16       0  5013.5    0.07       0  5017.5    0.16       0
  5157.6   0.035       0  5188.7   0.063       0  5289.1   0.035       0
  5321.1   0.063       0
Bank Sta=5013.5,5017.5
Exp/Cntr=0.3,0.1

Type RM Length L Ch R = 1,5856,222,222,222
BEGIN DESCRIPTION:
North Twin Creek Trib M5856.27
END DESCRIPTION:
XS GIS Cut Line= 3
      2710374.26      6799275.26      2710364.95      6799601.93
      2710362.56      6799867.11
#Sta/Elev= 30
  4676.2  348.44  4712.0  346.80  4732.0  343.97  4752.0  342.75  4802.0  337.26
  4852.0  335.76  4882.0  336.25  4892.0  335.87  4902.0  332.46  4912.0  335.38
  4932.0  332.58  4942.1  334.23  4952.1  333.60  4962.1  335.70  4982.1  334.86
  4992.1  333.86  4998.0  330.81  4998.3  330.31  5001.8  330.31  5002.0  330.81
  5005.0  330.81  5012.1  336.54  5022.1  338.83  5032.2  340.17  5082.1  341.07
  5162.1  345.03  5172.1  344.84  5242.1  347.13  5262.1  347.11  5268.2  346.31
#Mann=4,-1,0
  4676.2    0.16       0  4998.0    0.07       0  5002.0    0.16       0
  5032.2   0.035       0
Bank Sta=4998,5002
Exp/Cntr=0.3,0.1

Type RM Length L Ch R = 1,5634,207,207,207
BEGIN DESCRIPTION:
North Twin Creek Trib M5634.14
END DESCRIPTION:
XS GIS Cut Line= 3
      2710254.95      6799185.97      2710194.69      6799489.81
      2710142.22      6799774.35
#Sta/Elev= 30
  4698.5  344.90  4734.2  342.83  4764.8  343.54  4770.1  344.26  4775.2  343.57
  4805.6  344.34  4826.3  343.50  4866.7  340.05  4872.4  338.36  4877.5  338.33
  4907.5  334.35  4923.6  333.76  4928.7  334.45  4958.5  334.46  4968.7  333.56
  4979.9  334.37  5011.4  333.32  5017.6  329.50  5017.9  329.00  5021.4  329.00
  5021.6  329.50  5026.7  333.98  5031.7  334.49  5090.8  334.28  5147.2  336.78
  5212.8  342.92  5233.2  342.75  5248.8  345.08  5263.7  345.34  5297.6  347.87
#Mann=4,-1,0
  4698.5    0.12       0  5017.6    0.07       0  5021.6    0.12       0
  5147.2   0.035       0
Bank Sta=5017.6,5021.6
Exp/Cntr=0.3,0.1

Type RM Length L Ch R = 1,5427,167,167,167
BEGIN DESCRIPTION:
North Twin Creek Trib M5427.47
END DESCRIPTION:
XS GIS Cut Line= 3
      2709970.40      6799166.45      2710039.42      6799365.03
      2710075.61      6799712.22
#Sta/Elev= 30
  4794.9  346.69  4820.9  345.77  4832.0  344.54  4895.0  340.73  4920.0  337.40
  4945.8  332.49  4948.1  332.91  4951.1  333.46  4969.1  333.26  4974.9  328.56
  4975.2  328.06  4978.9  328.56  4982.2  328.83  4990.3  332.61  5018.3  334.34
  5023.3  333.72  5061.4  333.97  5111.7  332.65  5121.8  334.12  5151.9  333.98
  5192.1  332.77  5210.2  334.99  5232.3  336.15  5265.5  339.45  5292.7  340.95
  5302.7  342.00  5308.7  343.41  5322.8  342.25  5332.9  343.45  5354.2  343.83
#Mann=5,-1,0
  4794.9    0.16       0  4948.1    0.12       0  4974.9    0.07       0
  4978.9    0.12       0  5265.5   0.035       0
Bank Sta=4974.9,4978.9
Exp/Cntr=0.3,0.1