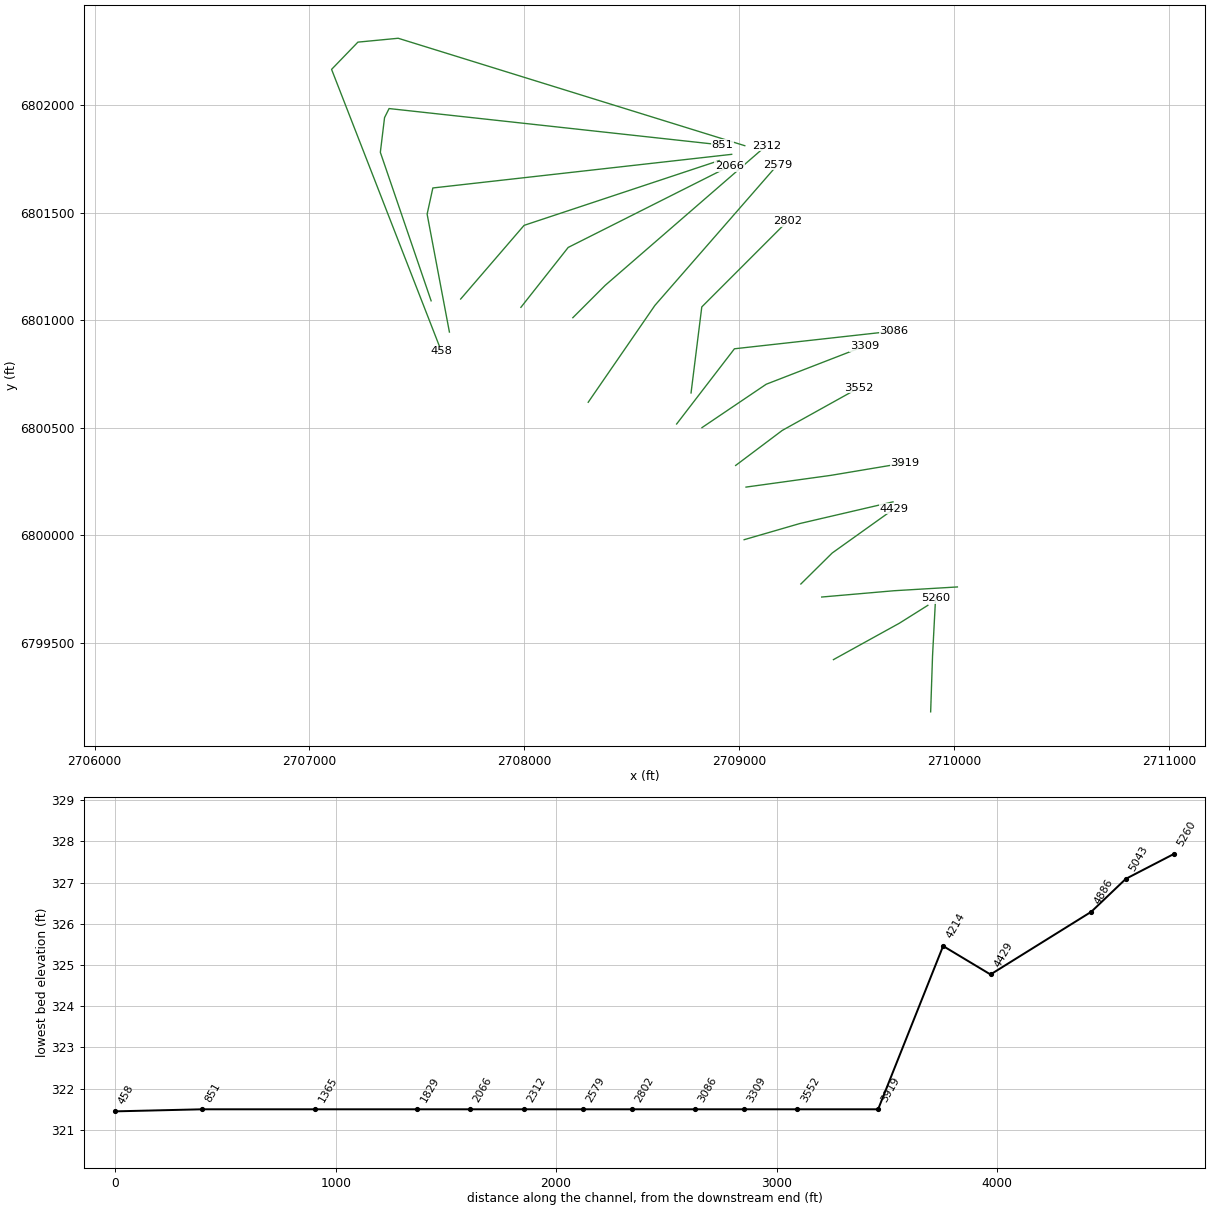
HEC-RAS study North Twin Creek Trib M.prj: North Twin Creek Trib M Base Level Engineering

--- North Twin Creek Trib M.g01 (geometry) --- (continued)

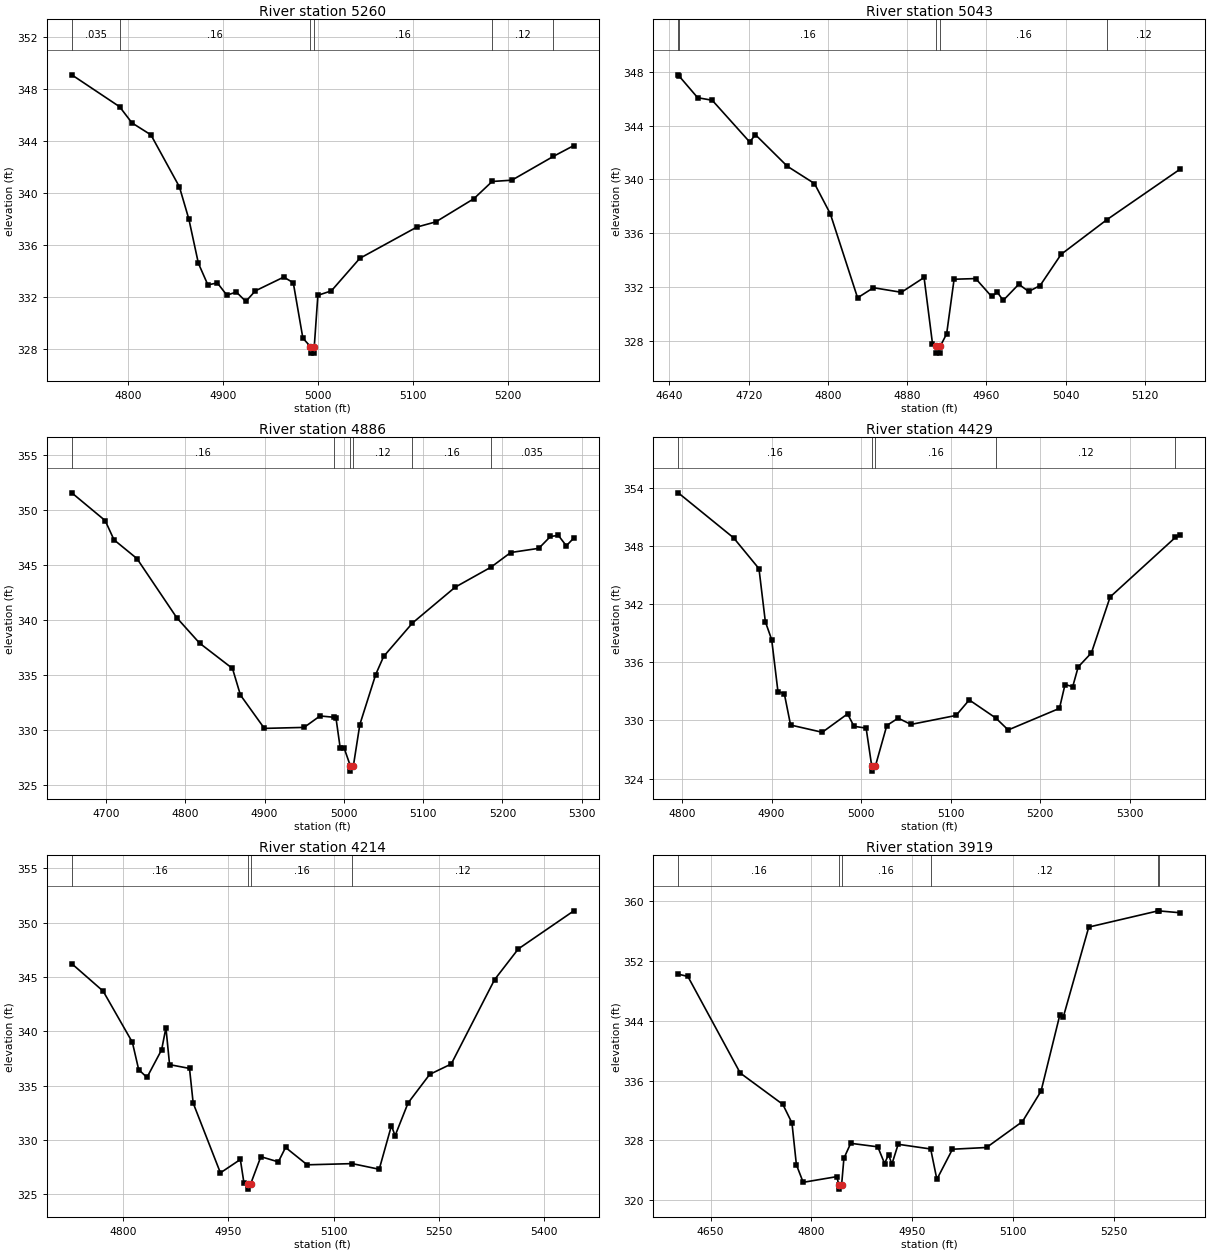
Type RM Length L Ch R = 1,5260,217,217,217
BEGIN DESCRIPTION:
North Twin Creek Trib M5260.13
END DESCRIPTION:
XS GIS Cut Line= 3
      2709891.10      6799177.69      2709899.86      6799437.61
      2709913.94      6799706.17
#Sta/Elev= 30
  4740.5  349.06  4790.9  346.61  4803.9  345.37  4823.9  344.45  4853.9  340.46
  4863.9  337.97  4873.9  334.59  4883.9  332.93  4893.9  333.08  4903.9  332.14
  4913.9  332.38  4923.9  331.66  4933.9  332.47  4963.9  333.53  4973.9  333.09
  4984.0  328.84  4992.0  328.19  4992.2  327.69  4995.7  327.69  4996.0  328.19
  4999.8  332.13  5014.0  332.47  5044.0  334.97  5104.1  337.37  5124.1  337.77
  5164.2  339.55  5183.4  340.87  5204.2  340.97  5248.0  342.80  5269.5  343.63
#Mann=6,-1,0
  4740.5   0.035       0  4790.9    0.16       0  4992.0    0.07       0
  4996.0    0.16       0  5183.4    0.12       0  5248.0   0.035       0
Bank Sta=4992,4996
Exp/Cntr=0.3,0.1

Type RM Length L Ch R = 1,5043,157,157,157
BEGIN DESCRIPTION:
North Twin Creek Trib M5043.1
END DESCRIPTION:
XS GIS Cut Line= 3
      2709438.80      6799420.61      2709745.62      6799589.95
      2709877.94      6799673.06
#Sta/Elev= 30
  4648.9  347.77  4650.0  347.66  4668.5  346.07  4683.2  345.88  4721.0  342.78
  4726.8  343.32  4758.9  340.98  4786.4  339.69  4802.4  337.44  4829.9  331.20
  4845.9  331.95  4874.1  331.61  4897.0  332.71  4905.5  327.79  4909.3  327.59
  4909.5  327.09  4913.0  327.09  4913.3  327.59  4919.8  328.53  4927.3  332.58
  4949.1  332.63  4965.1  331.30  4970.9  331.61  4976.9  331.01  4992.6  332.21
  5002.5  331.67  5014.1  332.11  5035.3  334.43  5081.4  337.00  5155.6  340.77
#Mann=5,-1,0
  4648.9   0.035       0  4650.0    0.16       0  4909.3    0.07       0
  4913.3    0.16       0  5081.4    0.12       0
Bank Sta=4909.3,4913.3
Exp/Cntr=0.3,0.1

Type RM Length L Ch R = 1,4886,457,457,457
BEGIN DESCRIPTION:
North Twin Creek Trib M4885.94
END DESCRIPTION:
XS GIS Cut Line= 3
      2709384.06      6799711.72      2709721.70      6799741.07
      2710015.46      6799758.61
#Sta/Elev= 30
  4656.8  351.56  4698.9  349.04  4710.1  347.29  4739.0  345.59  4789.2  340.22
  4818.0  337.91  4859.5  335.61  4869.5  333.20  4899.7  330.17  4949.8  330.26
  4969.9  331.30  4987.5  331.18  4990.0  331.12  4995.4  328.36  5000.4  328.36
  5008.0  326.79  5008.3  326.29  5012.0  326.79  5020.1  330.52  5040.1  335.06
  5050.1  336.70  5086.5  339.74  5140.3  342.99  5185.5  344.81  5210.4  346.14
  5245.8  346.52  5260.5  347.60  5270.5  347.69  5280.5  346.75  5290.0  347.46
#Mann=6,-1,0
  4656.8    0.16       0  4987.5    0.12       0  5008.0    0.07       0
  5012.0    0.12       0  5086.5    0.16       0  5185.5   0.035       0
Bank Sta=5008,5012
Exp/Cntr=0.3,0.1

Type RM Length L Ch R = 1,4429,215,215,215
BEGIN DESCRIPTION:
North Twin Creek Trib M4429.37
END DESCRIPTION:
XS GIS Cut Line= 3
      2709287.10      6799772.30      2709432.71      6799916.31
      2709722.52      6800123.24
#Sta/Elev= 30
  4795.7  353.50  4857.6  348.85  4885.9  345.67  4893.0  340.20  4900.1  338.34
  4907.1  332.98  4914.2  332.77  4921.2  329.53  4956.6  328.78  4984.9  330.68
  4992.0  329.40  5005.6  329.21  5011.9  325.27  5012.2  324.77  5015.9  325.27
  5028.7  329.48  5041.4  330.24  5055.7  329.59  5106.1  330.52  5120.8  332.12
  5150.5  330.25  5164.3  329.02  5221.6  331.25  5227.8  333.71  5236.4  333.49
  5242.5  335.52  5257.3  336.98  5278.2  342.75  5351.0  348.89  5356.6  349.10
#Mann=5,-1,0
  4795.7    0.16       0  5011.9    0.07       0  5015.9    0.16       0
  5150.5    0.12       0  5351.0    0.16       0
Bank Sta=5011.9,5015.9
Exp/Cntr=0.3,0.1

Type RM Length L Ch R = 1,4214,295,295,295
BEGIN DESCRIPTION:
North Twin Creek Trib M4214.48
END DESCRIPTION:
XS GIS Cut Line= 3
      2709023.10      6799978.39      2709282.49      6800053.59
      2709715.95      6800154.40
#Sta/Elev= 30
  4727.2  346.23  4771.9  343.70  4813.5  338.99  4822.5  336.47  4834.3  335.75
  4855.2  338.30  4861.3  340.33  4866.5  336.93  4894.9  336.58  4900.1  333.39
  4938.9  326.96  4967.3  328.19  4972.5  326.00  4978.1  325.96  4978.4  325.46
  4982.1  325.96  4996.5  328.45  5021.4  327.97  5031.7  329.30  5062.5  327.70
  5126.6  327.81  5165.1  327.29  5182.5  331.31  5187.7  330.38  5206.2  333.40
  5237.0  336.03  5267.7  336.99  5329.4  344.76  5363.2  347.59  5442.3  351.10
#Mann=4,-1,0
  4727.2    0.16       0  4978.1    0.07       0  4982.1    0.16       0
  5126.6    0.12       0
Bank Sta=4978.1,4982.1
Exp/Cntr=0.3,0.1

Type RM Length L Ch R = 1,3919,367,367,367
BEGIN DESCRIPTION:
North Twin Creek Trib M3918.86
END DESCRIPTION:
XS GIS Cut Line= 3
      2709031.85      6800223.06      2709425.94      6800277.52
      2709770.31      6800335.17
#Sta/Elev= 30
  4601.9  350.21  4616.2  349.91  4694.2  337.00  4757.5  332.82  4771.1  330.34
  4777.7  324.75  4787.8  322.41  4837.9  323.17  4840.9  322.00  4841.2  321.50
  4844.9  322.00  4848.4  325.62  4858.5  327.62  4898.8  327.15  4908.9  324.92
  4914.8  326.11  4919.8  324.84  4929.1  327.49  4977.5  326.86  4986.7  322.81
  5009.9  326.83  5060.6  327.06  5114.0  330.52  5141.7  334.59  5169.7  344.78
  5174.7  344.45  5212.7  356.50  5316.1  358.67  5317.2  358.66  5348.9  358.41
#Mann=6,-1,0
  4601.9    0.16       0  4840.9    0.07       0  4844.9    0.16       0
  4977.5    0.12       0  5316.1    0.16       0  5317.2    0.12       0
Bank Sta=4840.9,4844.9
Exp/Cntr=0.3,0.1

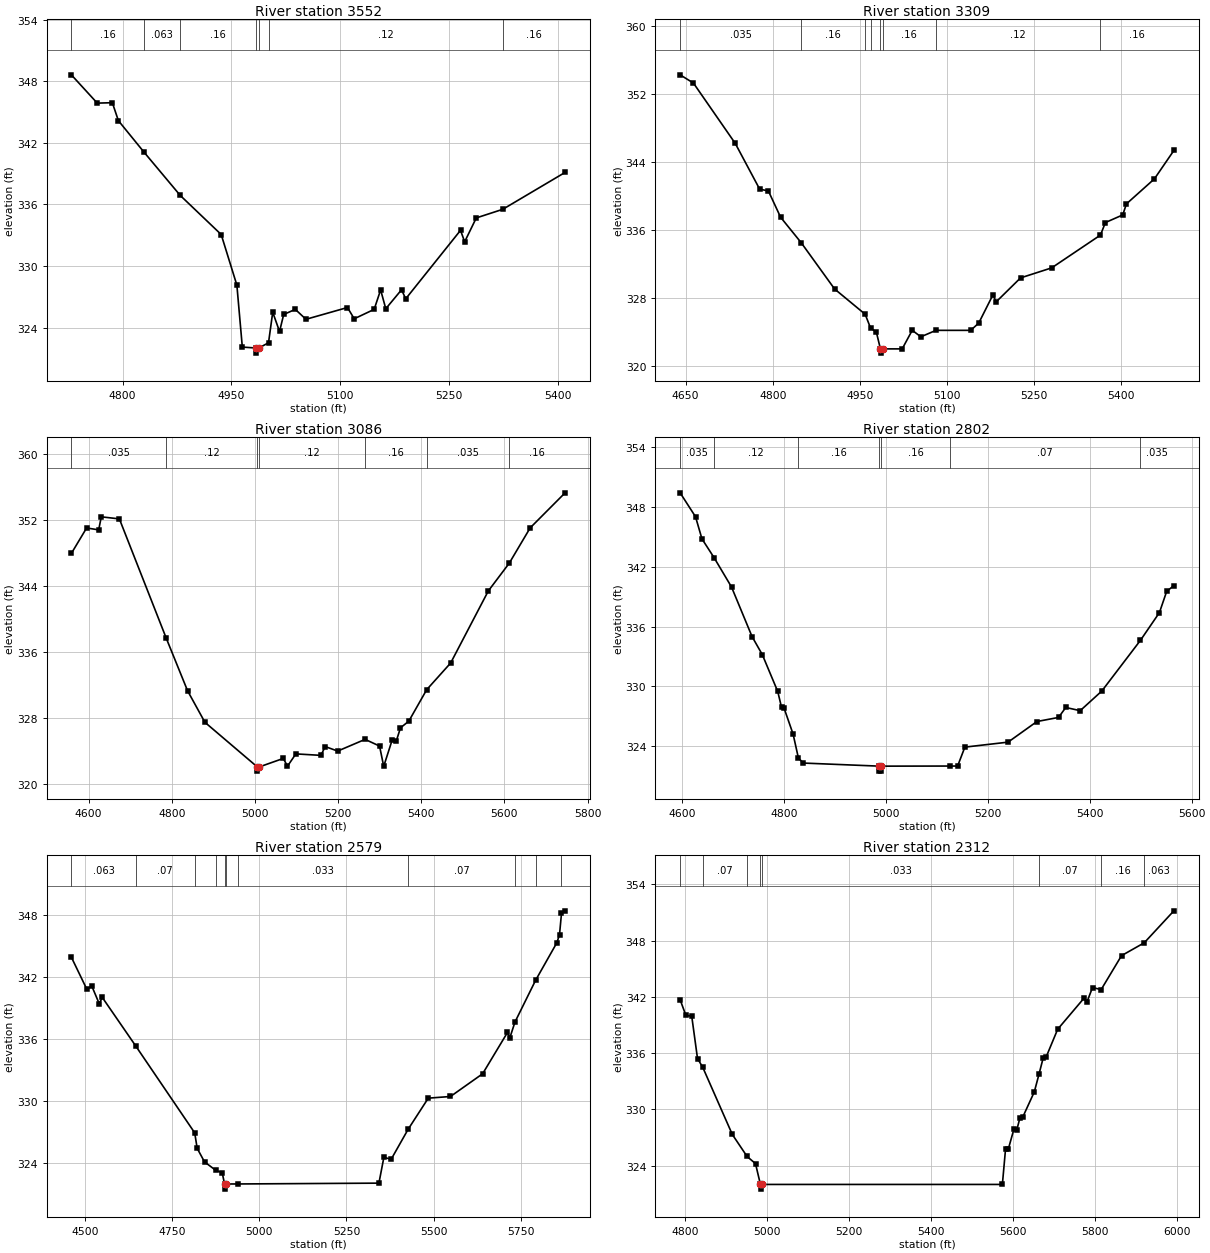
Type RM Length L Ch R = 1,3552,243,243,243
BEGIN DESCRIPTION:
North Twin Creek Trib M3552.29
END DESCRIPTION:
XS GIS Cut Line= 3
      2708983.64      6800323.71      2709200.54      6800486.68
      2709558.18      6800685.33
#Sta/Elev= 30
  4729.4  348.65  4765.1  345.89  4785.9  345.93  4794.2  344.18  4828.9  341.16
  4879.5  336.88  4935.9  333.07  4957.5  328.13  4965.0  322.09  4983.8  322.00
  4984.1  321.50  4987.8  322.00  5001.1  322.51  5006.9  325.49  5016.3  323.61
  5022.0  325.27  5038.0  325.77  5052.7  324.80  5109.9  325.95  5119.2  324.85
  5146.7  325.77  5155.6  327.67  5162.7  325.83  5184.4  327.68  5190.2  326.80
  5265.7  333.48  5271.4  332.36  5287.4  334.69  5323.9  335.53  5409.8  339.13
#Mann=7,-1,0
  4729.4    0.16       0  4828.9   0.063       0  4879.5    0.16       0
  4983.8    0.07       0  4987.8    0.16       0  5001.1    0.12       0
  5323.9    0.16       0
Bank Sta=4983.8,4987.8
Exp/Cntr=0.3,0.1

Type RM Length L Ch R = 1,3309,223,223,223
BEGIN DESCRIPTION:
North Twin Creek Trib M3309.28
END DESCRIPTION:
XS GIS Cut Line= 3
      2708826.98      6800499.78      2709125.77      6800701.44
      2709582.08      6800878.13
#Sta/Elev= 30
  4640.6  354.24  4663.5  353.27  4735.5  346.17  4777.5  340.79  4792.5  340.58
  4813.5  337.49  4849.1  334.48  4906.4  329.05  4959.1  326.07  4968.3  324.46
  4978.4  323.96  4985.3  322.00  4985.6  321.50  4989.3  322.00  5022.8  322.00
  5040.1  324.19  5054.9  323.42  5081.0  324.18  5140.7  324.18  5154.5  325.03
  5179.1  328.37  5184.4  327.52  5226.5  330.35  5280.1  331.53  5364.1  335.39
  5372.5  336.86  5402.4  337.76  5408.8  339.06  5456.9  342.00  5490.4  345.34
#Mann=8,-1,0
  4640.6   0.035       0  4849.1    0.16       0  4959.1    0.12       0
  4968.3    0.16       0  4985.3    0.07       0  4989.3    0.16       0
  5081.0    0.12       0  5364.1    0.16       0
Bank Sta=4985.3,4989.3
Exp/Cntr=0.3,0.1

Type RM Length L Ch R = 1,3086,284,284,284
BEGIN DESCRIPTION:
North Twin Creek Trib M3085.948
END DESCRIPTION:
XS GIS Cut Line= 3
      2708708.94      6800516.56      2708977.98      6800866.36
      2709719.51      6800948.79
#Sta/Elev= 30
  4558.7  347.89  4595.4  350.98  4624.4  350.75  4630.7  352.33  4674.2  352.08
  4786.8  337.63  4838.2  331.24  4879.9  327.42  5006.1  322.00  5006.3  321.50
  5010.1  322.00  5068.4  323.04  5078.5  322.10  5098.6  323.59  5159.0  323.41
  5169.1  324.48  5199.2  323.93  5265.1  325.35  5299.9  324.54  5309.9  322.08
  5330.0  325.24  5340.1  325.14  5350.2  326.75  5370.3  327.56  5413.2  331.37
  5470.9  334.61  5561.5  343.35  5611.8  346.71  5662.1  350.99  5746.1  355.24
#Mann=7,-1,0
  4558.7   0.035       0  4786.8    0.12       0  5006.1    0.07       0
  5010.1    0.12       0  5265.1    0.16       0  5413.2   0.035       0
  5611.8    0.16       0
Bank Sta=5006.1,5010.1
Exp/Cntr=0.3,0.1

Type RM Length L Ch R = 1,2802,223,223,223
BEGIN DESCRIPTION:
North Twin Creek Trib M2802.107
END DESCRIPTION:
XS GIS Cut Line= 3
      2708776.00      6800660.99      2708826.00      6801061.00
      2709226.00      6801461.00
#Sta/Elev= 30
  4596.3  349.44  4626.5  347.04  4639.1  344.82  4662.8  342.94  4697.1  339.99
  4737.4  335.01  4757.6  333.19  4787.8  329.50  4795.3  327.90  4800.4  327.80
  4818.0  325.21  4828.4  322.81  4838.2  322.31  4987.3  322.00  4987.5  321.50
  4991.1  321.50  4991.4  322.00  5125.4  322.01  5140.8  322.01  5155.0  323.91
  5239.8  324.41  5296.4  326.48  5338.8  326.89  5353.0  327.89  5381.3  327.57
  5423.7  329.54  5499.5  334.63  5536.8  337.42  5551.0  339.55  5565.1  340.12
#Mann=7,-1,0
  4596.3   0.035       0  4662.8    0.12       0  4828.4    0.16       0
  4987.3    0.07       0  4991.4    0.16       0  5125.4    0.07       0
  5499.5   0.035       0
Bank Sta=4987.3,4991.4
Exp/Cntr=0.3,0.1

Type RM Length L Ch R = 1,2579,267,267,267
BEGIN DESCRIPTION:
North Twin Creek Trib M2578.58
END DESCRIPTION:
XS GIS Cut Line= 3
      2708297.44      6800617.71      2708607.79      6801068.09
      2709178.25      6801721.85
#Sta/Elev= 30
  4461.7  343.96  4505.7  340.88  4520.6  341.14  4541.5  339.46  4550.4  340.06
  4646.6  335.34  4815.1  326.95  4822.2  325.45  4843.2  324.14  4875.4  323.32
  4893.9  323.09  4900.6  322.00  4900.8  321.50  4904.8  322.00  4938.9  322.00
  5342.9  322.08  5357.1  324.58  5378.0  324.39  5426.5  327.29  5484.3  330.31
  5547.9  330.47  5640.0  332.67  5711.2  336.67  5717.9  336.14  5732.7  337.68
  5791.6  341.71  5852.7  345.36  5860.3  346.14  5866.0  348.21  5876.3  348.45
#Mann=11,-1,0
  4461.7   0.063       0  4646.6    0.07       0  4815.1    0.16       0
  4875.4    0.07       0  4900.6   0.033       0  4904.8    0.07       0
  4938.9   0.033       0  5426.5    0.07       0  5732.7   0.035       0
  5791.6   0.063       0  5866.0    0.07       0
Bank Sta=4900.6,4904.8
Exp/Cntr=0.3,0.1

Type RM Length L Ch R = 1,2312,246,246,246
BEGIN DESCRIPTION:
North Twin Creek Trib M2312.346
END DESCRIPTION:
XS GIS Cut Line= 3
      2708225.99      6801010.99      2708376.00      6801161.00
      2709125.99      6801810.99
#Sta/Elev= 30
  4787.9  341.70  4802.0  340.02  4816.2  339.95  4830.3  335.43  4843.0  334.50
  4915.2  327.33  4951.3  324.98  4971.8  324.22  4983.8  322.00  4984.0  321.50
  4988.0  322.00  5574.1  322.00  5581.8  325.76  5588.4  325.74  5602.6  327.95
  5609.3  327.82  5616.9  329.09  5623.5  329.15  5652.0  331.87  5663.6  333.78
  5673.9  335.53  5680.5  335.55  5709.0  338.55  5772.6  341.83  5780.3  341.44
  5794.0  343.00  5815.1  342.78  5864.8  346.40  5920.2  347.77  5992.5  351.18
#Mann=8,-1,0
  4787.9   0.063       0  4843.0    0.07       0  4951.3   0.033       0
  4983.8   0.033       0  4988.0   0.033       0  5663.6    0.07       0
  5815.1    0.16       0  5920.2   0.063       0
Bank Sta=4983.8,4988
Exp/Cntr=0.3,0.1

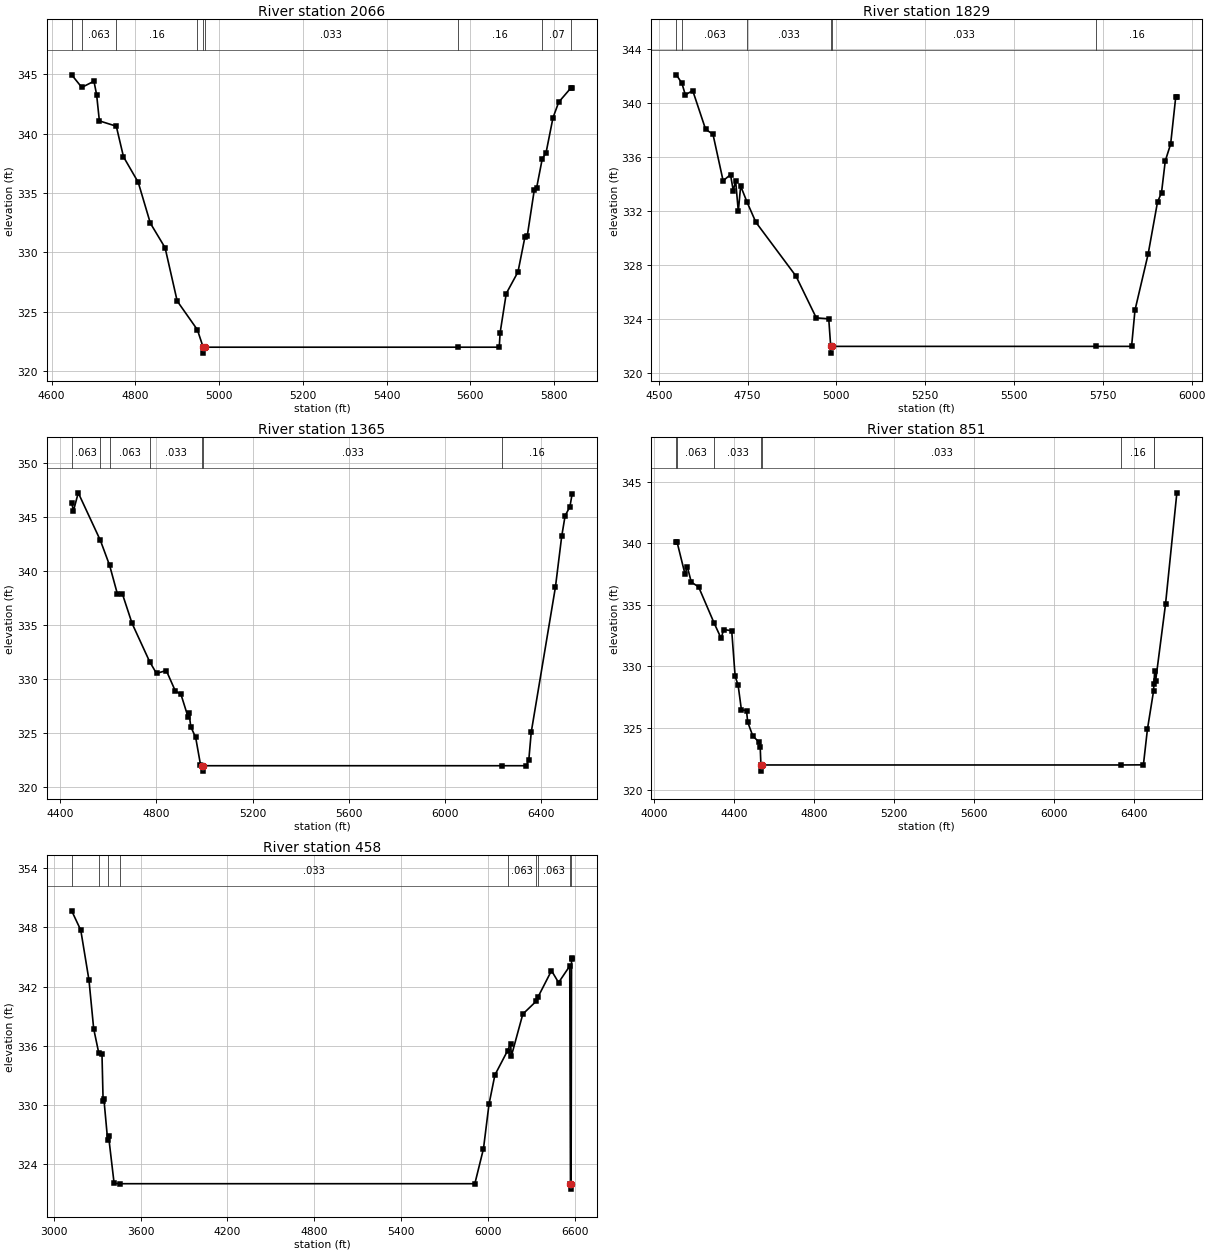
Type RM Length L Ch R = 1,2066,237,237,237
BEGIN DESCRIPTION:
Mapping XS bd404866
END DESCRIPTION:
XS GIS Cut Line= 3
      2707984.19      6801059.17      2708204.33      6801337.80
      2708954.70      6801715.13
#Sta/Elev= 30
  4648.2  344.95  4672.3  343.89  4701.4  344.41  4707.7  343.28  4714.3  341.07
  4754.7  340.62  4771.9  338.04  4807.1  335.89  4836.0  332.45  4871.2  330.38
  4900.1  325.89  4948.3  323.47  4962.1  322.00  4962.4  321.50  4966.3  322.00
  5570.1  322.00  5669.1  322.00  5671.2  323.22  5685.8  326.52  5713.8  328.34
  5730.5  331.30  5736.1  331.40  5752.8  335.26  5758.4  335.44  5771.9  337.89
  5780.7  338.36  5797.4  341.33  5811.1  342.65  5839.6  343.82  5843.2  343.80
#Mann=9,-1,0
  4648.2    0.16       0  4672.3   0.063       0  4754.7    0.16       0
  4948.3   0.033       0  4962.1   0.033       0  4966.3   0.033       0
  5570.1    0.16       0  5771.9    0.07       0  5839.6    0.16       0
Bank Sta=4962.1,4966.3
Exp/Cntr=0.3,0.1

Type RM Length L Ch R = 1,1829,464,464,464
BEGIN DESCRIPTION:
Mapping XS eebe286c
END DESCRIPTION:
XS GIS Cut Line= 3
      2707703.87      6801097.82      2707999.02      6801440.49
      2708907.00      6801741.74
#Sta/Elev= 30
  4549.5  342.10  4565.1  341.47  4574.6  340.62  4595.5  340.93  4631.7  338.07
  4652.5  337.70  4681.0  334.26  4701.9  334.71  4709.6  333.52  4716.2  334.26
  4723.8  332.00  4730.4  333.87  4748.7  332.66  4773.2  331.19  4886.2  327.20
  4943.3  324.11  4978.4  324.04  4983.9  322.00  4984.2  321.50  4988.2  322.00
  5730.9  322.00  5830.9  322.00  5840.5  324.68  5877.5  328.83  5903.9  332.68
  5915.2  333.38  5925.7  335.72  5940.9  336.98  5955.2  340.46  5958.4  340.46
#Mann=6,-1,0
  4549.5    0.16       0  4565.1   0.063       0  4748.7   0.033       0
  4983.9   0.033       0  4988.2   0.033       0  5730.9    0.16       0
Bank Sta=4983.9,4988.2
Exp/Cntr=0.3,0.1

Type RM Length L Ch R = 1,1365,514,514,514
BEGIN DESCRIPTION:
Mapping XS 42dbf493
END DESCRIPTION:
XS GIS Cut Line= 4
      2707651.45      6800944.21      2707547.77      6801492.55
      2707574.41      6801614.38      2708965.19      6801770.77
#Sta/Elev= 30
  4447.5  346.34  4454.7  345.57  4474.8  347.25  4567.0  342.84  4605.4  340.53
  4637.6  337.90  4658.0  337.93  4698.7  335.17  4771.8  331.63  4800.4  330.54
  4841.1  330.81  4878.6  328.92  4902.2  328.60  4931.0  326.55  4936.1  326.84
  4942.9  325.61  4963.3  324.62  4983.4  322.10  4991.6  322.00  4991.9  321.50
  4995.9  322.00  6236.7  322.00  6339.4  322.00  6349.5  322.56  6359.5  325.10
  6460.2  338.53  6486.2  343.21  6500.4  345.12  6520.6  345.98  6529.8  347.17
#Mann=7,-1,0
  4447.5   0.063       0  4567.0    0.16       0  4605.4   0.063       0
  4771.8   0.033       0  4991.6   0.033       0  4995.9   0.033       0
  6236.7    0.16       0
Bank Sta=4991.6,4995.9
Exp/Cntr=0.3,0.1

Type RM Length L Ch R = 1,851,393,393,393
BEGIN DESCRIPTION:
Mapping XS 495a6c49
END DESCRIPTION:
XS GIS Cut Line= 5
      2707566.38      6801089.44      2707330.02      6801780.26
      2707349.65      6801941.67      2707370.76      6801983.71
      2708922.22      6801814.01
#Sta/Elev= 30
  4111.2  340.10  4114.9  340.08  4154.3  337.49  4165.7  338.10  4185.6  336.85
  4222.2  336.46  4299.8  333.52  4334.8  332.28  4347.4  333.00  4387.6  332.90
  4404.7  329.19  4419.4  328.50  4436.0  326.48  4461.6  326.42  4467.3  325.49
  4493.3  324.34  4524.6  323.86  4529.9  323.47  4533.5  322.00  4533.8  321.50
  4537.8  322.00  6335.0  322.00  6444.5  322.01  6464.6  324.90  6495.1  327.99
  6497.2  328.61  6500.6  329.61  6505.7  328.85  6555.1  335.07  6611.7  344.10
#Mann=8,-1,0
  4111.2    0.16       0  4114.9   0.063       0  4299.8   0.033       0
  4533.5   0.033       0  4537.8   0.033       0  6335.0    0.16       0
  6495.1   0.033       0  6497.2    0.16       0
Bank Sta=4533.5,4537.8
Exp/Cntr=0.3,0.1

Type RM Length L Ch R = 1,458,0,0,0
BEGIN DESCRIPTION:
North Twin Creek Trib M1872.626
END DESCRIPTION:
XS GIS Cut Line= 5
      2709026.04      6801810.99      2707413.10      6802310.68
      2707225.63      6802292.67      2707103.12      6802165.95
      2707613.89      6800855.42
#Sta/Elev= 30
  3123.1  349.69  3186.0  347.72  3242.5  342.67  3275.1  337.73  3310.6  335.24
  3332.5  335.16  3340.3  330.41  3345.5  330.63  3371.9  326.39  3378.1  326.82
  3416.3  322.04  3457.2  322.00  5910.0  322.00  5969.7  325.55  6008.0  330.07
  6048.6  333.03  6136.8  335.51  6157.3  336.21  6162.7  334.96  6241.6  339.21
  6332.9  340.50  6347.3  340.96  6439.9  343.62  6488.9  342.41  6566.1  344.09
  6571.1  321.95  6571.4  321.45  6575.4  321.95  6578.5  344.92  6582.8  344.79
#Mann=9,-1,0
  3123.1    0.16       0  3310.6   0.033       0  3371.9    0.16       0
  3457.2   0.033       0  6136.8   0.063       0  6332.9    0.16       0
  6347.3   0.063       0  6571.1   0.033       0  6575.4   0.063       0
Bank Sta=6571.1,6575.4
Exp/Cntr=0.3,0.1

Chan Stop Cuts=-1