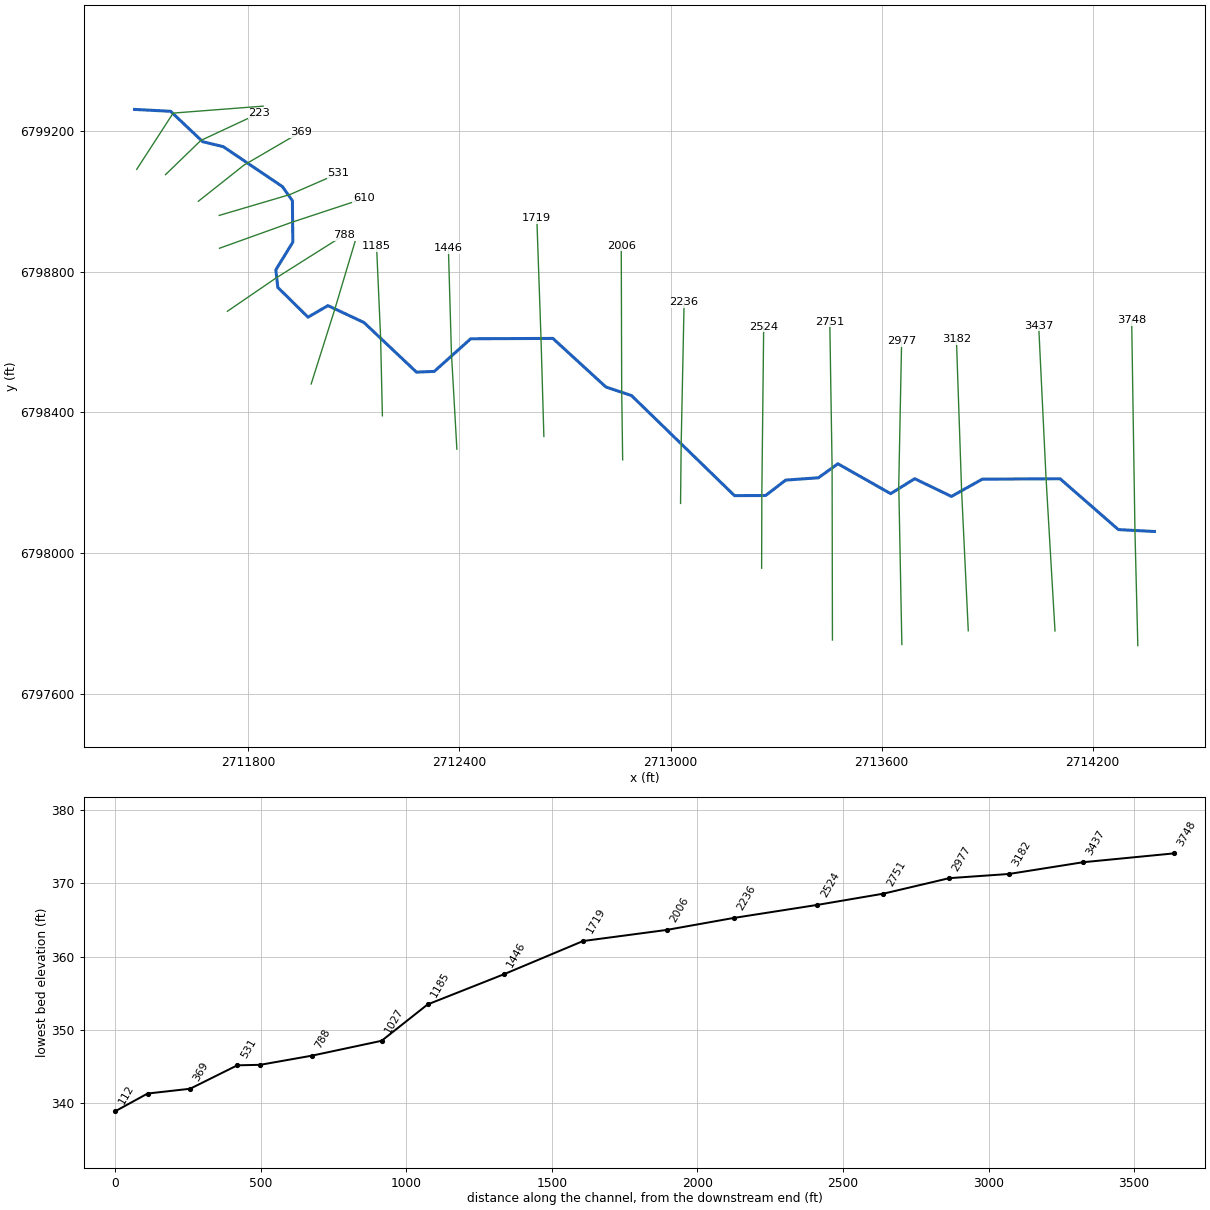
--- North Twin Creek Trib M1.prj (project) ---

Proj Title=North Twin Creek Trib M1 Base Level Engineering
Current Plan=p01
Default Exp/Contr=0.3,0.1
English Units
Geom File=g01
Flow File=f01
Plan File=p01
BEGIN DESCRIPTION:
North Twin Creek Trib M1
END DESCRIPTION:

--- North Twin Creek Trib M1.p01 (plan) ---

Plan Title=Multiple Run
Short Identifier=Multiple
Geom File=g01
Flow File=f01
Subcritical Flow
K Sum by GR= 0
Std Step Tol= 0.01
Critical Tol= 0.01
Num of Std Step Trials= 20
Max Error Tol= 0.3
Flow Tol Ratio= 0.001
Split Flow NTrial= 30
Split Flow Tol= 0.02
Split Flow Ratio= 0.02
Log Output Level= 0
Friction Slope Method= 1
Unsteady Friction Slope Method= 2
Unsteady Bridges Friction Slope Method= 1
Parabolic Critical Depth
Global Vel Dist=  1 , 1 , 1
Global Log Level= 0
CheckData=True
Encroach Param= -1, 0, 0, 0
BEGIN DESCRIPTION:
Multiple Run
END DESCRIPTION:

--- North Twin Creek Trib M1.f01 (steady flow) ---

Flow Title=Multiple
Number of Profiles=7
Profile Names=10-year,25-year,50-year,1pct_min,100-year,1pct_plu,500-year
River Rch & RM= North Twin Creek,Reach-1,3748
     196     244     280     160     320     638     414
Boundary for River Rch & Prof#=North Twin Creek,Reach-1,1
Up Type=0
Dn Type=3
Dn Slope=0.005
Boundary for River Rch & Prof#=North Twin Creek,Reach-1,2
Up Type=0
Dn Type=3
Dn Slope=0.005
Boundary for River Rch & Prof#=North Twin Creek,Reach-1,3
Up Type=0
Dn Type=3
Dn Slope=0.005
Boundary for River Rch & Prof#=North Twin Creek,Reach-1,4
Up Type=0
Dn Type=3
Dn Slope=0.005
Boundary for River Rch & Prof#=North Twin Creek,Reach-1,5
Up Type=0
Dn Type=3
Dn Slope=0.005
Boundary for River Rch & Prof#=North Twin Creek,Reach-1,6
Up Type=0
Dn Type=3
Dn Slope=0.005
Boundary for River Rch & Prof#=North Twin Creek,Reach-1,7
Up Type=0
Dn Type=3
Dn Slope=0.005

--- North Twin Creek Trib M1.g01 (geometry) ---

Geom Title=Existing Conditions

River Reach=North Twin Creek,Reach-1
Reach XY= 30
      2714376.00      6798061.00      2714273.50      6798066.35
      2714107.78      6798210.91      2713886.50      6798209.76
      2713798.80      6798160.63      2713694.38      6798211.05
      2713626.00      6798168.56      2713476.01      6798253.47
      2713420.51      6798213.67      2713327.60      6798207.14
      2713270.43      6798163.28      2713181.89      6798162.96
      2712889.21      6798447.37      2712816.32      6798471.78
      2712665.57      6798609.95      2712431.86      6798608.93
      2712328.28      6798516.08      2712277.65      6798514.10
      2712128.29      6798655.19      2712025.91      6798703.22
      2711969.31      6798670.29      2711883.48      6798754.91
      2711877.78      6798804.86      2711926.11      6798883.69
      2711924.87      6799001.56      2711896.58      6799041.41
      2711728.28      6799155.13      2711669.96      6799169.18
      2711578.49      6799255.64      2711476.00      6799261.00

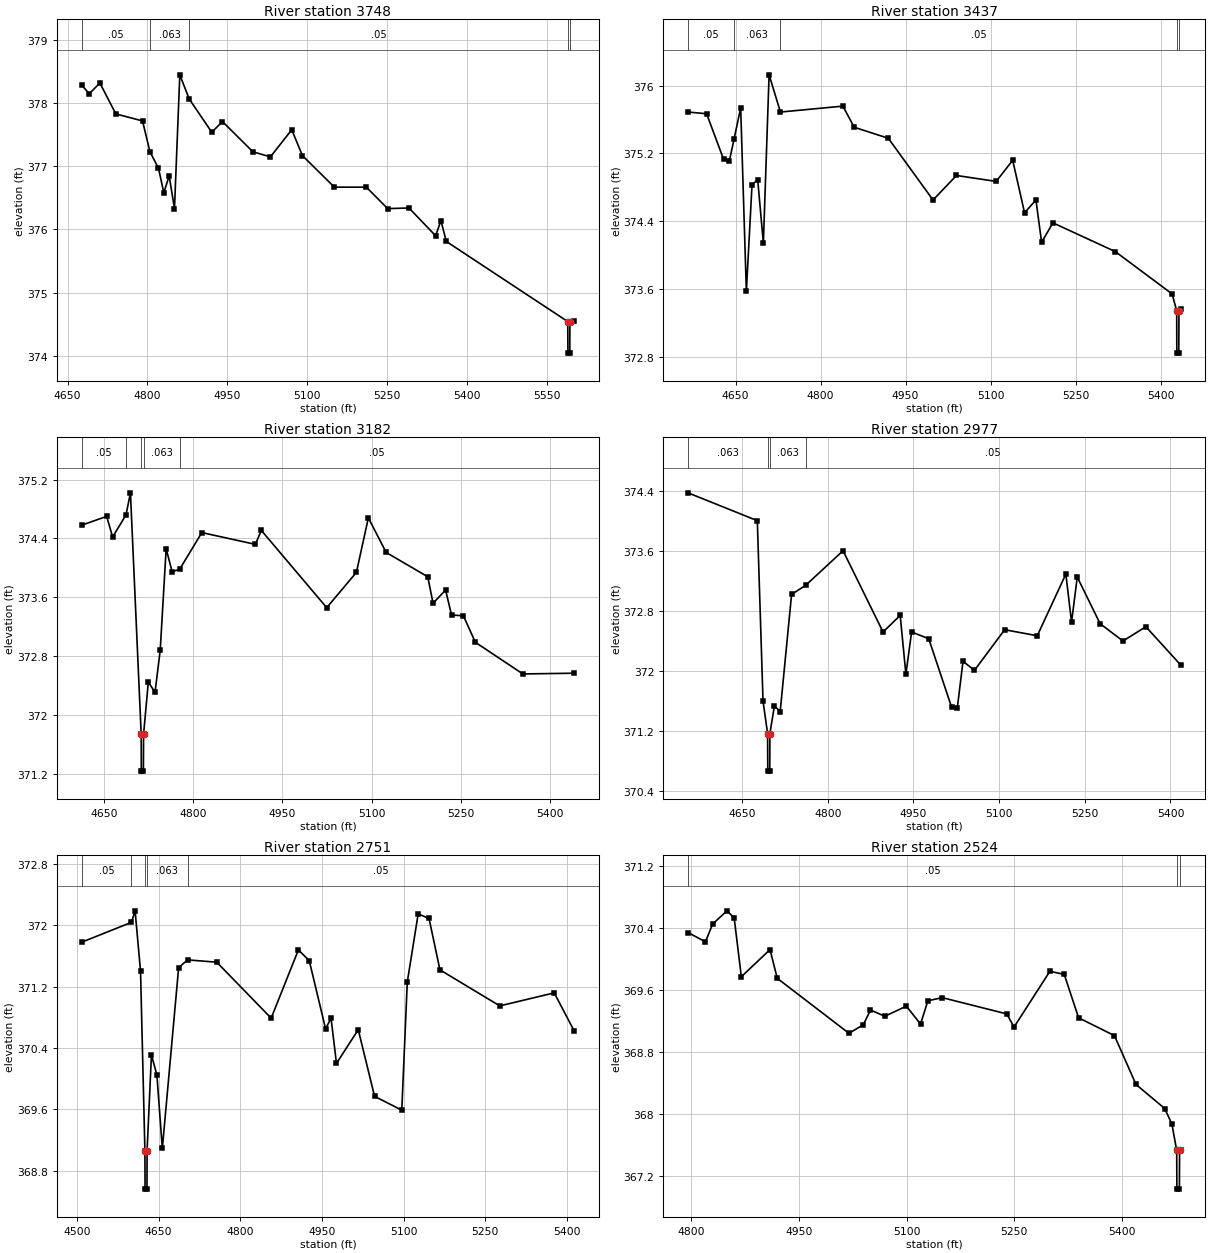
Type RM Length L Ch R = 1,3748,311,311,311
BEGIN DESCRIPTION:
North Twin Creek Trib M13748.074
END DESCRIPTION:
XS GIS Cut Line= 3
      2714328.81      6797736.64      2714320.69      6798060.24
      2714311.32      6798661.27
#Sta/Elev= 30
  4676.3  378.29  4690.7  378.15  4710.7  378.32  4740.7  377.83  4790.7  377.72
  4804.7  377.23  4820.7  376.97  4830.7  376.58  4840.7  376.85  4850.7  376.33
  4860.7  378.45  4878.2  378.07  4920.7  377.54  4940.7  377.71  4997.9  377.23
  5030.8  377.15  5070.8  377.58  5090.8  377.17  5150.8  376.67  5210.8  376.67
  5250.8  376.33  5290.8  376.34  5340.8  375.90  5350.8  376.14  5360.8  375.81
  5588.8  374.54  5589.1  374.04  5592.6  374.04  5592.8  374.54  5601.1  374.55
#Mann=5,-1,0
  4676.3    0.05       0  4804.7   0.063       0  4878.2    0.05       0
  5588.8    0.05       0  5592.8    0.05       0
Bank Sta=5588.8,5592.8
Exp/Cntr=0.3,0.1

Type RM Length L Ch R = 1,3437,255,255,255
BEGIN DESCRIPTION:
North Twin Creek Trib M13437.15
END DESCRIPTION:
XS GIS Cut Line= 3
      2714093.31      6797778.29      2714067.79      6798213.41
      2714046.90      6798646.23
#Sta/Elev= 30
  4566.2  375.69  4599.0  375.67  4629.0  375.13  4639.0  375.11  4647.4  375.37
  4659.1  375.74  4669.1  373.57  4679.1  374.83  4689.1  374.89  4699.1  374.14
  4709.2  376.13  4729.2  375.69  4839.4  375.76  4859.4  375.51  4919.5  375.38
  4998.4  374.65  5039.7  374.94  5109.8  374.87  5138.9  375.12  5159.8  374.50
  5179.9  374.65  5189.9  374.15  5209.9  374.38  5320.0  374.04  5420.1  373.54
  5428.2  373.34  5428.4  372.84  5431.9  372.84  5432.2  373.34  5435.4  373.36
#Mann=5,-1,0
  4566.2    0.05       0  4647.4   0.063       0  4729.2    0.05       0
  5428.2    0.05       0  5432.2    0.05       0
Bank Sta=5428.2,5432.2
Exp/Cntr=0.3,0.1

Type RM Length L Ch R = 1,3182,205,205,205
BEGIN DESCRIPTION:
North Twin Creek Trib M13182.03
END DESCRIPTION:
XS GIS Cut Line= 3
      2713846.72      6797778.75      2713827.79      6798175.43
      2713812.99      6798607.54
#Sta/Elev= 30
  4611.9  374.58  4654.2  374.70  4664.2  374.42  4686.7  374.72  4694.2  375.02
  4712.3  371.74  4712.5  371.24  4716.0  371.24  4716.3  371.74  4724.3  372.45
  4735.6  372.31  4744.3  372.88  4754.3  374.26  4764.3  373.95  4776.9  373.98
  4814.4  374.48  4904.5  374.32  4914.5  374.51  5024.6  373.46  5074.6  373.94
  5094.7  374.68  5124.7  374.21  5194.7  373.88  5203.6  373.52  5224.7  373.70
  5234.7  373.36  5254.7  373.35  5274.8  372.99  5354.8  372.56  5441.4  372.57
#Mann=5,-1,0
  4611.9    0.05       0  4686.7   0.063       0  4712.3    0.05       0
  4716.3   0.063       0  4776.9    0.05       0
Bank Sta=4712.3,4716.3
Exp/Cntr=0.3,0.1

Type RM Length L Ch R = 1,2977,226,226,226
BEGIN DESCRIPTION:
North Twin Creek Trib M12976.38
END DESCRIPTION:
XS GIS Cut Line= 3
      2713657.86      6797739.70      2713649.03      6798192.97
      2713657.18      6798602.13
#Sta/Elev= 30
  4555.5  374.37  4676.8  374.00  4686.8  371.60  4694.8  371.17  4695.1  370.67
  4698.6  370.67  4698.8  371.17  4706.8  371.54  4716.8  371.46  4736.8  373.02
  4761.4  373.14  4826.9  373.60  4896.9  372.52  4926.9  372.74  4936.9  371.96
  4946.9  372.52  4976.9  372.43  5016.9  371.52  5026.9  371.51  5036.9  372.13
  5056.9  372.01  5109.8  372.55  5166.9  372.47  5216.9  373.29  5226.9  372.65
  5236.9  373.25  5276.9  372.63  5316.9  372.40  5357.0  372.59  5418.1  372.08
#Mann=4,-1,0
  4555.5   0.063       0  4694.8    0.05       0  4698.8   0.063       0
  4761.4    0.05       0
Bank Sta=4694.8,4698.8
Exp/Cntr=0.3,0.1

Type RM Length L Ch R = 1,2751,227,227,227
BEGIN DESCRIPTION:
North Twin Creek Trib M12711.75
END DESCRIPTION:
XS GIS Cut Line= 3
      2713460.45      6797752.56      2713459.48      6798244.26
      2713452.90      6798657.91
#Sta/Elev= 30
  4508.3  371.78  4600.0  372.04  4606.7  372.19  4616.7  371.40  4624.7  369.06
  4625.0  368.56  4628.5  368.56  4628.7  369.06  4636.7  370.31  4646.7  370.05
  4656.7  369.09  4686.7  371.45  4703.3  371.55  4756.7  371.52  4856.7  370.79
  4906.7  371.68  4926.7  371.54  4956.7  370.65  4966.7  370.79  4976.7  370.20
  5016.7  370.64  5046.7  369.77  5096.7  369.59  5106.8  371.26  5126.8  372.15
  5146.8  372.09  5166.8  371.42  5276.8  370.95  5376.8  371.12  5413.7  370.62
#Mann=5,-1,0
  4508.3    0.05       0  4600.0   0.063       0  4624.7    0.05       0
  4628.7   0.063       0  4703.3    0.05       0
Bank Sta=4624.7,4628.7
Exp/Cntr=0.3,0.1

Type RM Length L Ch R = 1,2524,288,288,288
BEGIN DESCRIPTION:
North Twin Creek Trib M12524.26
END DESCRIPTION:
XS GIS Cut Line= 3
      2713259.14      6797956.68      2713259.73      6798171.04
      2713264.96      6798643.35
#Sta/Elev= 30
  4795.4  370.34  4819.7  370.22  4829.7  370.45  4849.7  370.62  4859.7  370.53
  4869.7  369.77  4909.7  370.12  4919.7  369.75  5019.7  369.04  5039.7  369.15
  5049.7  369.34  5069.7  369.26  5099.7  369.39  5119.4  369.16  5129.7  369.46
  5149.7  369.50  5239.7  369.29  5249.7  369.12  5299.7  369.84  5319.7  369.80
  5339.7  369.24  5389.7  369.01  5419.7  368.38  5459.7  368.07  5469.7  367.87
  5476.4  367.53  5476.7  367.03  5480.2  367.03  5480.4  367.53  5482.1  367.53
#Mann=3,-1,0
  4795.4    0.05       0  5476.4    0.05       0  5480.4    0.05       0
Bank Sta=5476.4,5480.4
Exp/Cntr=0.3,0.1

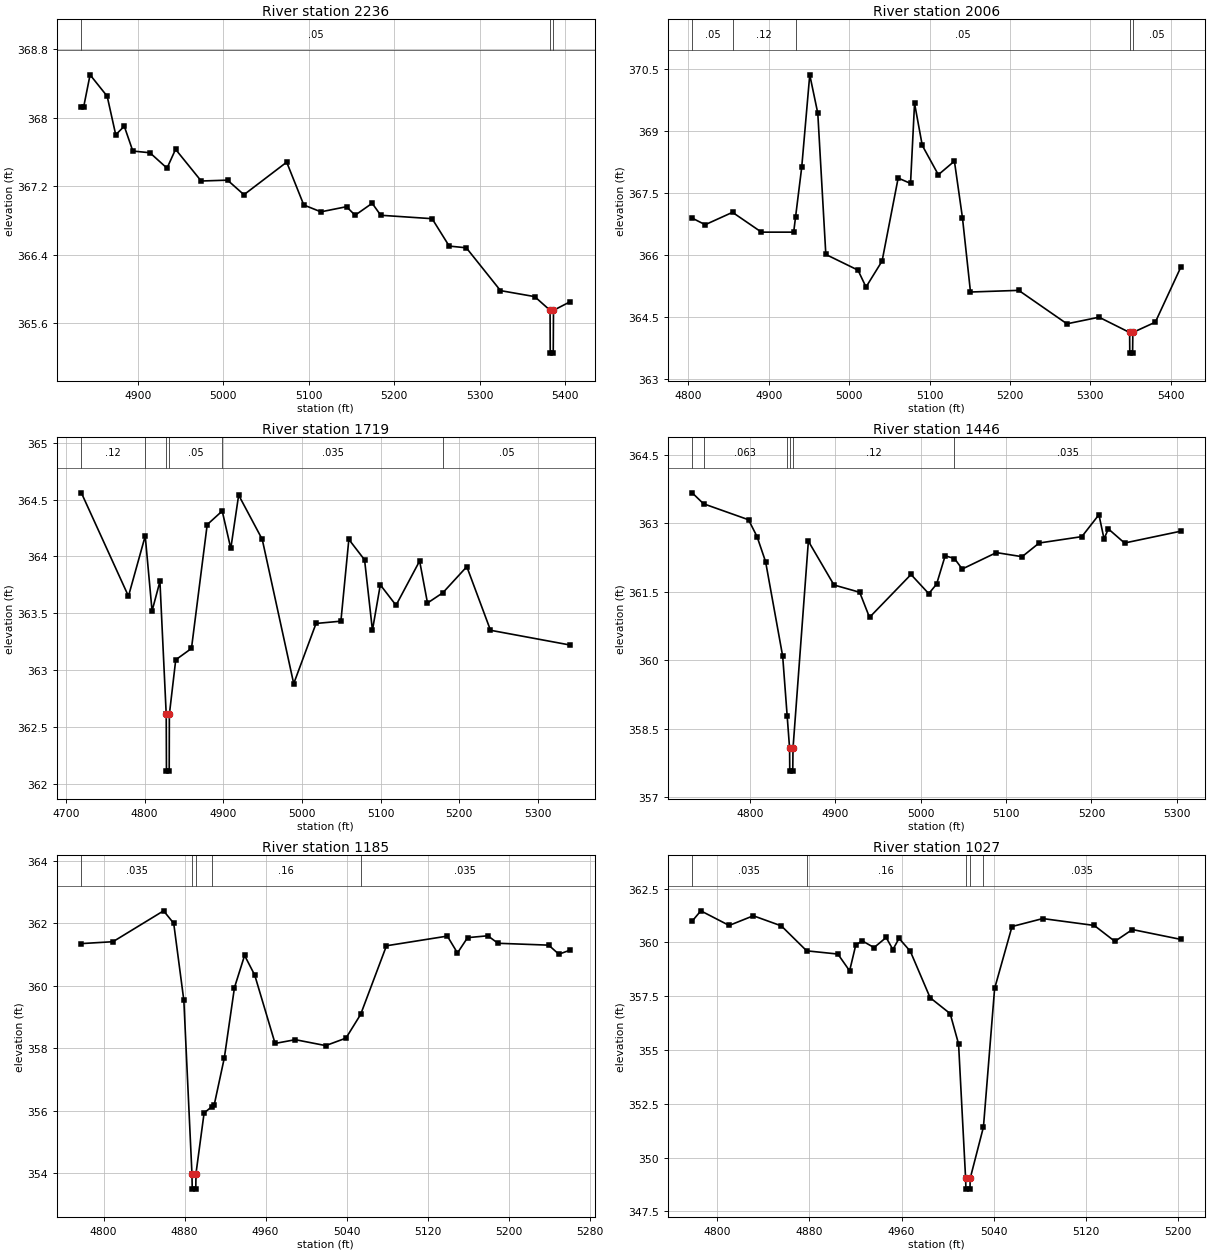
Type RM Length L Ch R = 1,2236,230,230,230
BEGIN DESCRIPTION:
North Twin Creek Trib M12236.47
END DESCRIPTION:
XS GIS Cut Line= 3
      2713028.60      6798140.81      2713030.29      6798307.57
      2713038.69      6798712.52
#Sta/Elev= 30
  4834.1  368.12  4836.7  368.12  4844.3  368.50  4864.3  368.25  4874.3  367.80
  4884.3  367.90  4894.3  367.61  4914.3  367.59  4934.3  367.41  4944.3  367.63
  4974.3  367.26  5005.1  367.27  5024.3  367.10  5074.3  367.48  5094.3  366.98
  5114.3  366.90  5144.3  366.96  5154.3  366.86  5174.3  367.00  5184.3  366.86
  5244.4  366.82  5264.4  366.50  5284.4  366.48  5324.4  365.98  5364.4  365.91
  5382.4  365.75  5382.6  365.25  5386.1  365.25  5386.4  365.75  5405.9  365.85
#Mann=3,-1,0
  4834.1    0.05       0  5382.4    0.05       0  5386.4    0.05       0
Bank Sta=5382.4,5386.4
Exp/Cntr=0.3,0.1

Type RM Length L Ch R = 1,2006,287,287,287
BEGIN DESCRIPTION:
North Twin Creek Trib M12005.99
END DESCRIPTION:
XS GIS Cut Line= 3
      2712863.95      6798264.76      2712861.22      6798463.88
      2712859.97      6798872.94
#Sta/Elev= 30
  4804.7  366.89  4820.9  366.73  4854.9  367.03  4890.9  366.55  4931.0  366.55
  4933.3  366.91  4941.0  368.12  4951.0  370.36  4961.0  369.43  4971.0  366.01
  5011.0  365.63  5021.0  365.22  5041.0  365.85  5061.0  367.86  5076.4  367.73
  5081.4  369.67  5091.0  368.65  5111.0  367.94  5131.0  368.27  5141.0  366.90
  5151.0  365.10  5211.0  365.14  5271.0  364.33  5311.0  364.49  5349.0  364.12
  5349.2  363.62  5352.7  363.62  5353.0  364.12  5381.0  364.37  5412.9  365.71
#Mann=5,-1,0
  4804.7    0.05       0  4854.9    0.12       0  4933.3    0.05       0
  5349.0    0.05       0  5353.0    0.05       0
Bank Sta=5349,5353
Exp/Cntr=0.3,0.1

Type RM Length L Ch R = 1,1719,273,273,273
BEGIN DESCRIPTION:
North Twin Creek Trib M11718.72
END DESCRIPTION:
XS GIS Cut Line= 3
      2712639.95      6798331.10      2712631.56      6798616.64
      2712619.86      6798952.27
#Sta/Elev= 30
  4719.5  364.56  4779.4  363.65  4800.7  364.18  4809.4  363.52  4819.4  363.78
  4827.4  362.61  4827.7  362.11  4831.2  362.11  4831.4  362.61  4839.5  363.09
  4859.5  363.19  4879.5  364.28  4898.6  364.40  4909.5  364.07  4919.5  364.54
  4949.5  364.15  4989.5  362.88  5017.9  363.41  5049.5  363.43  5059.6  364.15
  5079.6  363.97  5089.6  363.35  5099.6  363.75  5119.6  363.57  5149.6  363.96
  5159.6  363.59  5179.1  363.68  5209.6  363.91  5239.7  363.35  5341.0  363.22
#Mann=6,-1,0
  4719.5    0.12       0  4800.7    0.05       0  4827.4   0.035       0
  4831.4    0.05       0  4898.6   0.035       0  5179.1    0.05       0
Bank Sta=4827.4,4831.4
Exp/Cntr=0.3,0.1

Type RM Length L Ch R = 1,1446,261,261,261
BEGIN DESCRIPTION:
North Twin Creek Trib M11446.37
END DESCRIPTION:
XS GIS Cut Line= 3
      2712392.55      6798295.13      2712377.11      6798567.51
      2712368.42      6798867.07
#Sta/Elev= 30
  4732.3  363.67  4745.6  363.43  4798.3  363.08  4808.3  362.71  4818.3  362.16
  4838.3  360.09  4843.6  358.77  4846.4  358.07  4846.6  357.57  4850.1  357.57
  4850.4  358.07  4868.4  362.61  4898.4  361.65  4928.5  361.49  4940.0  360.94
  4988.6  361.88  5009.4  361.46  5018.6  361.67  5028.6  362.29  5039.5  362.23
  5048.6  362.00  5088.6  362.36  5118.7  362.27  5138.7  362.57  5188.7  362.71
  5208.7  363.19  5214.7  362.66  5219.7  362.88  5238.7  362.57  5304.8  362.83
#Mann=6,-1,0
  4732.3   0.035       0  4745.6   0.063       0  4843.6    0.12       0
  4846.4    0.07       0  4850.4    0.12       0  5039.5   0.035       0
Bank Sta=4846.4,4850.4
Exp/Cntr=0.3,0.1

Type RM Length L Ch R = 1,1185,158,158,158
BEGIN DESCRIPTION:
North Twin Creek Trib M11185.25
END DESCRIPTION:
XS GIS Cut Line= 3
      2712180.77      6798389.80      2712175.61      6798614.84
      2712164.20      6798872.19
#Sta/Elev= 30
  4778.1  361.35  4809.3  361.41  4859.3  362.40  4869.3  362.00  4879.3  359.53
  4887.3  353.98  4887.6  353.48  4891.1  353.48  4891.3  353.98  4899.3  355.92
  4906.8  356.12  4909.3  356.18  4919.3  357.69  4929.3  359.94  4939.3  360.97
  4949.3  360.34  4969.4  358.15  4989.4  358.27  5019.4  358.08  5039.4  358.32
  5053.9  359.08  5079.4  361.28  5139.5  361.59  5149.5  361.05  5159.5  361.54
  5179.5  361.60  5189.5  361.36  5239.6  361.30  5249.6  361.01  5260.8  361.14
#Mann=5,-1,0
  4778.1   0.035       0  4887.3    0.07       0  4891.3   0.035       0
  4906.8    0.16       0  5053.9   0.035       0
Bank Sta=4887.3,4891.3
Exp/Cntr=0.3,0.1

Type RM Length L Ch R = 1,1027,239,239,239
BEGIN DESCRIPTION:
North Twin Creek Trib M11026.61
END DESCRIPTION:
XS GIS Cut Line= 3
      2711978.27      6798480.40      2712045.14      6798691.95
      2712103.22      6798885.98
#Sta/Elev= 30
  4778.2  360.99  4785.7  361.47  4810.3  360.79  4831.3  361.24  4855.6  360.77
  4877.6  359.61  4904.7  359.46  4914.9  358.68  4920.2  359.87  4925.7  360.08
  4936.1  359.76  4946.6  360.23  4952.5  359.67  4957.8  360.19  4967.6  359.59
  4984.8  357.43  5002.2  356.69  5009.5  355.28  5015.6  349.03  5015.9  348.53
  5019.4  348.53  5019.6  349.03  5031.1  351.42  5040.8  357.86  5055.9  360.74
  5082.6  361.11  5127.3  360.79  5145.2  360.05  5160.4  360.60  5202.6  360.14
#Mann=5,-1,0
  4778.2   0.035       0  4877.6    0.16       0  5015.6    0.07       0
  5019.6    0.16       0  5031.1   0.035       0
Bank Sta=5015.6,5019.6
Exp/Cntr=0.3,0.1

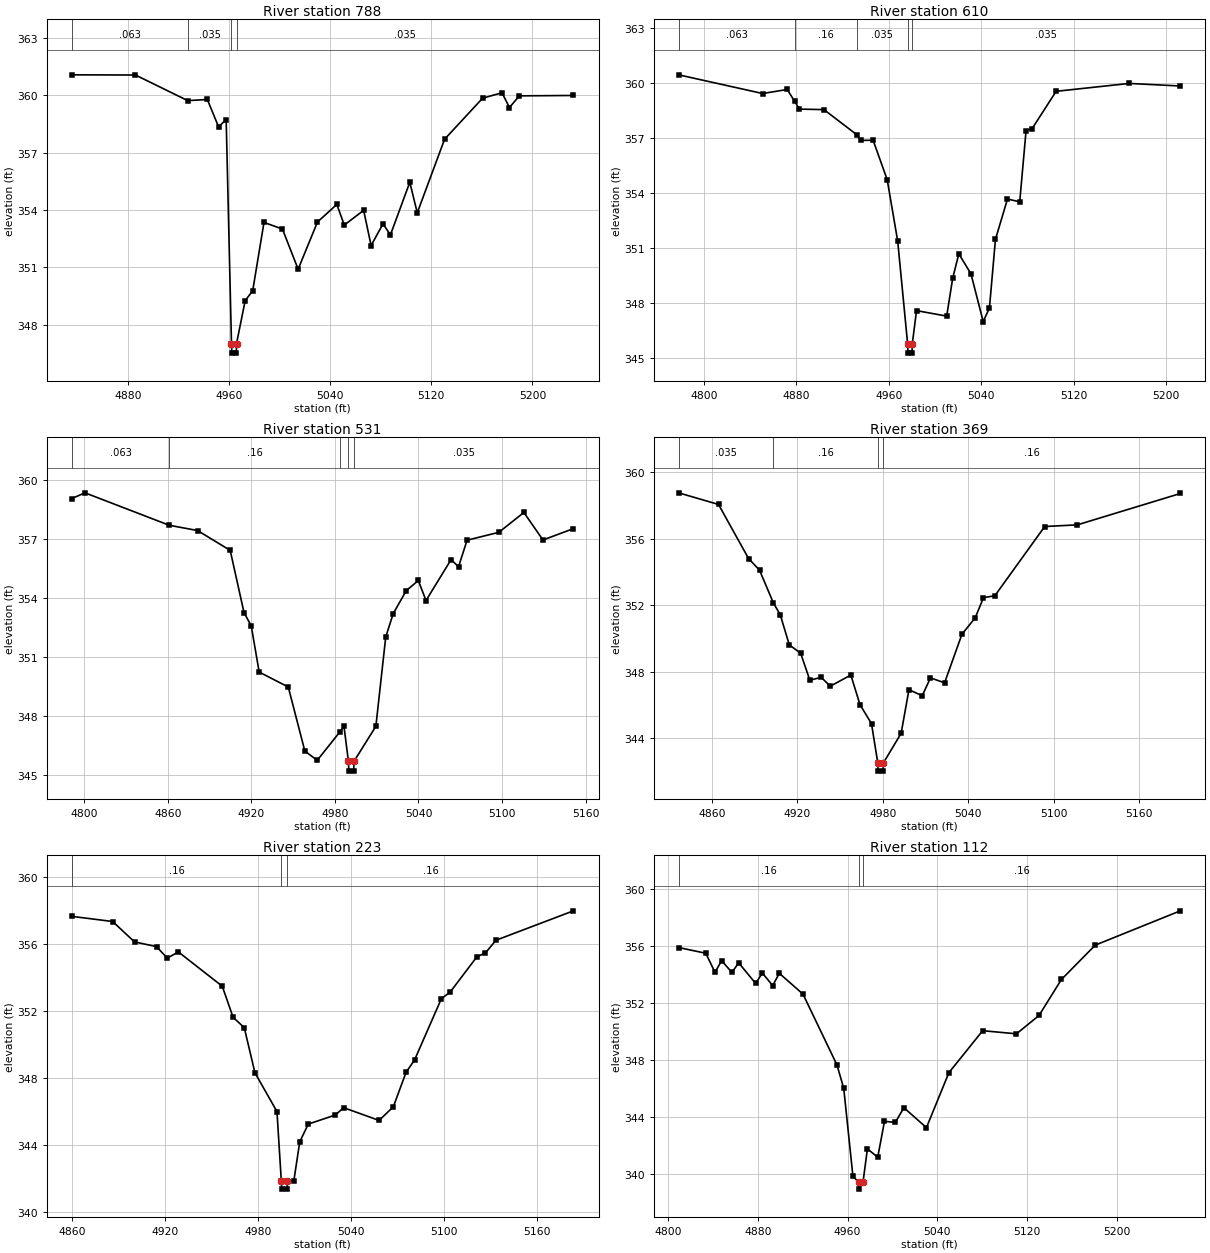
Type RM Length L Ch R = 1,788,178,178,178
BEGIN DESCRIPTION:
North Twin Creek Trib M1787.68
END DESCRIPTION:
XS GIS Cut Line= 3
      2711740.06      6798687.14      2711877.62      6798781.19
      2712072.18      6798903.99
#Sta/Elev= 30
  4835.7  361.07  4886.1  361.06  4927.4  359.72  4942.9  359.78  4951.8  358.35
  4957.8  358.73  4962.0  347.01  4962.3  346.51  4965.8  346.51  4966.0  347.01
  4972.8  349.25  4978.8  349.78  4987.7  353.35  5002.3  353.00  5014.7  350.90
  5030.0  353.37  5045.3  354.29  5051.2  353.21  5066.5  353.98  5072.4  352.14
  5081.8  353.27  5087.7  352.70  5103.0  355.45  5108.9  353.85  5130.5  357.70
  5160.6  359.85  5175.9  360.13  5181.8  359.36  5189.6  359.97  5232.4  359.99
#Mann=4,-1,0
  4835.7   0.063       0  4927.4   0.035       0  4962.0   0.035       0
  4966.0   0.035       0
Bank Sta=4962,4966
Exp/Cntr=0.3,0.1

Type RM Length L Ch R = 1,610,79,79,79
BEGIN DESCRIPTION:
North Twin Creek Trib M1609.99
END DESCRIPTION:
XS GIS Cut Line= 3
      2711717.57      6798866.29      2711923.62      6798940.27
      2712128.04      6799007.74
#Sta/Elev= 30
  4778.1  360.45  4850.8  359.43  4872.1  359.65  4878.4  359.01  4882.7  358.58
  4903.9  358.55  4932.3  357.18  4935.8  356.87  4946.4  356.88  4958.6  354.73
  4967.7  351.37  4976.3  345.76  4976.6  345.26  4980.1  345.26  4980.3  345.76
  4984.0  347.58  5010.1  347.28  5015.3  349.35  5020.6  350.68  5031.1  349.59
  5041.7  346.98  5047.1  347.73  5052.3  351.47  5062.7  353.67  5073.3  353.52
  5078.8  357.41  5084.1  357.52  5104.8  359.55  5168.0  359.98  5212.3  359.84
#Mann=5,-1,0
  4778.1   0.063       0  4878.4    0.16       0  4932.3   0.035       0
  4976.3   0.035       0  4980.3   0.035       0
Bank Sta=4976.3,4980.3
Exp/Cntr=0.3,0.1

Type RM Length L Ch R = 1,531,162,162,162
BEGIN DESCRIPTION:
North Twin Creek Trib M1530.56
END DESCRIPTION:
XS GIS Cut Line= 3
      2711716.89      6798959.67      2711917.41      6799018.81
      2712056.10      6799079.13
#Sta/Elev= 30
  4791.0  359.06  4800.5  359.35  4861.0  357.70  4881.4  357.43  4904.8  356.42
  4914.7  353.26  4919.9  352.58  4925.6  350.23  4946.5  349.47  4958.4  346.21
  4967.3  345.74  4983.7  347.20  4986.5  347.47  4989.7  345.69  4990.0  345.19
  4993.5  345.19  4993.7  345.69  5009.4  347.47  5016.5  352.02  5021.9  353.21
  5031.2  354.37  5039.9  354.89  5045.4  353.87  5063.4  355.95  5068.8  355.59
  5074.9  356.94  5097.7  357.34  5115.7  358.35  5129.4  356.95  5151.3  357.53
#Mann=5,-1,0
  4791.0   0.063       0  4861.0    0.16       0  4983.7   0.035       0
  4989.7   0.035       0  4993.7   0.035       0
Bank Sta=4989.7,4993.7
Exp/Cntr=0.3,0.1

Type RM Length L Ch R = 1,369,146,146,146
BEGIN DESCRIPTION:
North Twin Creek Trib M1368.96
END DESCRIPTION:
XS GIS Cut Line= 3
      2711657.49      6798999.87      2711787.51      6799102.86
      2711948.45      6799196.76
#Sta/Elev= 30
  4836.7  358.77  4864.7  358.07  4885.8  354.81  4893.5  354.11  4903.2  352.14
  4908.0  351.43  4914.4  349.61  4922.4  349.10  4928.8  347.48  4936.8  347.65
  4943.2  347.12  4957.6  347.79  4964.0  346.01  4972.1  344.86  4976.5  342.50
  4976.7  342.00  4980.2  342.00  4980.5  342.50  4992.9  344.28  4998.4  346.91
  5007.7  346.54  5013.5  347.62  5023.4  347.32  5035.6  350.25  5044.9  351.24
  5050.7  352.45  5058.7  352.57  5093.7  356.74  5116.6  356.84  5188.9  358.73
#Mann=4,-1,0
  4836.7   0.035       0  4903.2    0.16       0  4976.5    0.07       0
  4980.5    0.16       0
Bank Sta=4976.5,4980.5
Exp/Cntr=0.3,0.1

Type RM Length L Ch R = 1,223,111,111,111
BEGIN DESCRIPTION:
North Twin Creek Trib M1223.22
END DESCRIPTION:
XS GIS Cut Line= 3
      2711564.16      6799075.64      2711664.56      6799172.78
      2711831.32      6799250.52
#Sta/Elev= 30
  4859.9  357.67  4886.3  357.36  4900.4  356.14  4914.6  355.86  4921.5  355.17
  4928.7  355.54  4957.0  353.49  4964.0  351.63  4971.2  351.01  4978.1  348.31
  4992.3  345.99  4995.1  341.85  4995.4  341.35  4998.9  341.35  4999.1  341.85
  5003.2  341.85  5007.0  344.18  5012.5  345.24  5029.8  345.78  5035.4  346.22
  5058.2  345.46  5067.4  346.28  5075.6  348.34  5081.1  349.08  5098.4  352.75
  5104.0  353.13  5121.3  355.25  5126.8  355.48  5133.6  356.24  5183.6  358.00
#Mann=3,-1,0
  4859.9    0.16       0  4995.1    0.07       0  4999.1    0.16       0
Bank Sta=4995.1,4999.1
Exp/Cntr=0.3,0.1

Type RM Length L Ch R = 1,112,0,0,0
BEGIN DESCRIPTION:
North Twin Creek Trib M1112.348
END DESCRIPTION:
XS GIS Cut Line= 3
      2711482.21      6799090.68      2711585.81      6799250.54
      2711841.55      6799270.32
#Sta/Elev= 30
  4809.5  355.91  4833.7  355.51  4841.9  354.17  4847.8  354.99  4857.0  354.16
  4863.0  354.84  4878.1  353.39  4884.1  354.12  4893.3  353.24  4899.2  354.10
  4920.3  352.64  4950.6  347.66  4956.6  346.02  4964.8  339.84  4969.8  339.44
  4970.0  338.94  4973.8  339.44  4977.7  341.77  4986.9  341.18  4992.9  343.70
  5002.6  343.63  5010.2  344.66  5030.3  343.26  5050.3  347.12  5080.4  350.07
  5110.5  349.85  5130.6  351.14  5150.6  353.67  5180.7  356.08  5256.5  358.49
#Mann=3,-1,0
  4809.5    0.16       0  4969.8    0.07       0  4973.8    0.16       0
Bank Sta=4969.8,4973.8
Exp/Cntr=0.3,0.1

Chan Stop Cuts=-1