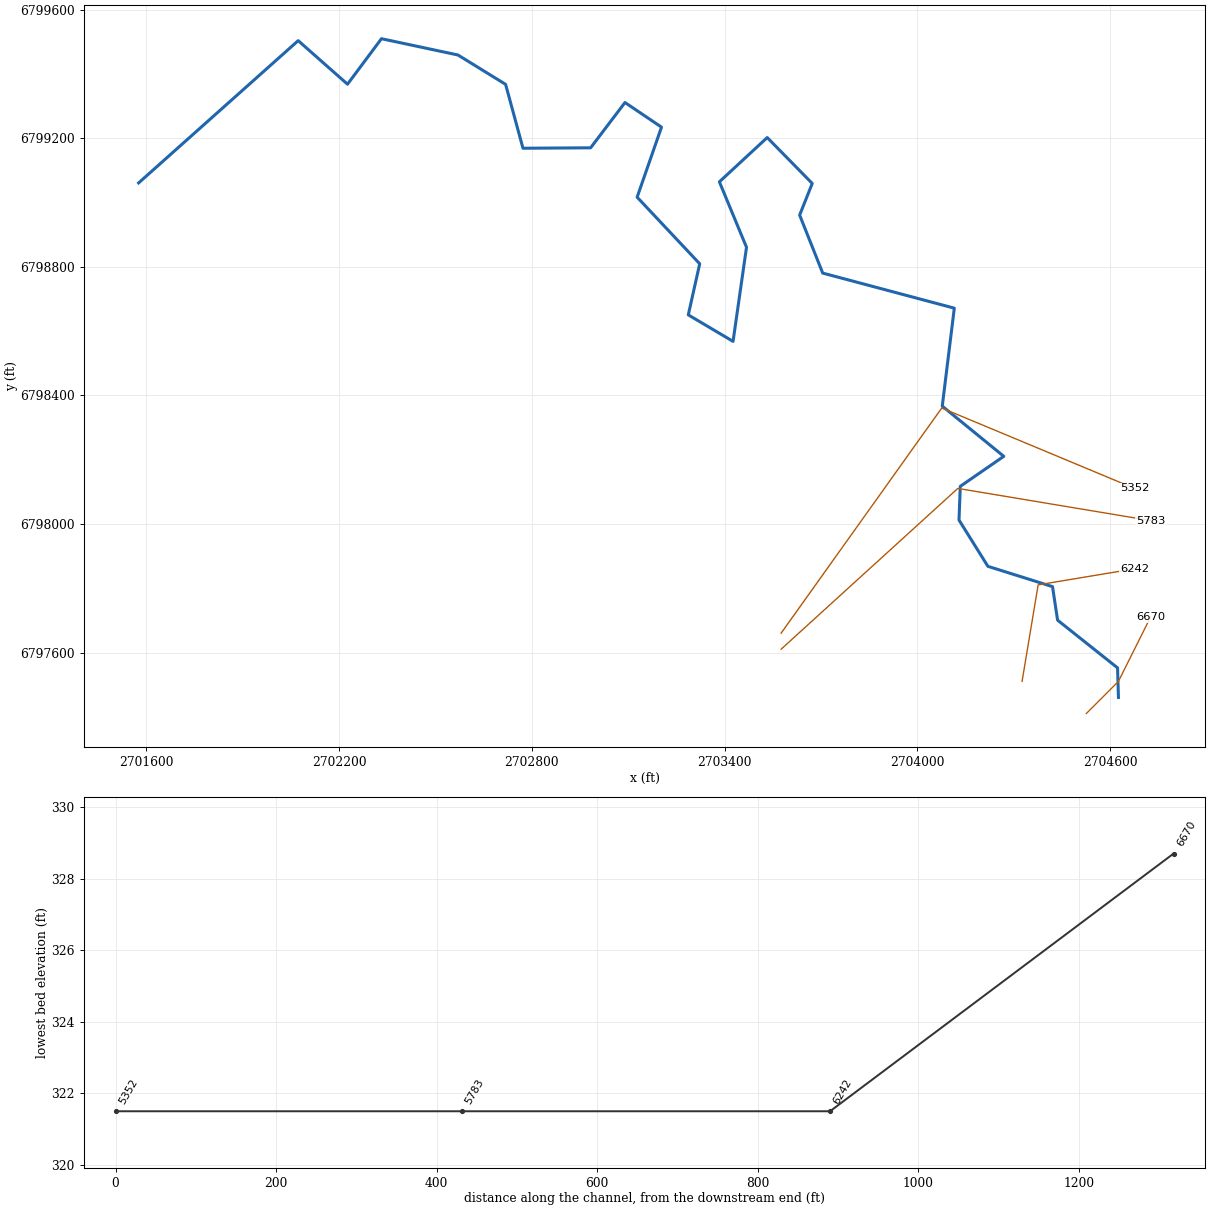
--- North Twin Creek Trib O.prj (project) ---

Proj Title=North Twin Creek Trib O Base Level Engineering
Current Plan=p01
Default Exp/Contr=0.3,0.1
English Units
Geom File=g01
Flow File=f01
Plan File=p01
BEGIN DESCRIPTION:
North Twin Creek Trib O
END DESCRIPTION:

--- North Twin Creek Trib O.p01 (plan) ---

Plan Title=Multiple Run
Short Identifier=Multiple
Geom File=g01
Flow File=f01
Subcritical Flow
K Sum by GR= 0
Std Step Tol= 0.01
Critical Tol= 0.01
Num of Std Step Trials= 20
Max Error Tol= 0.3
Flow Tol Ratio= 0.001
Split Flow NTrial= 30
Split Flow Tol= 0.02
Split Flow Ratio= 0.02
Log Output Level= 0
Friction Slope Method= 1
Unsteady Friction Slope Method= 2
Unsteady Bridges Friction Slope Method= 1
Parabolic Critical Depth
Global Vel Dist=  1 , 1 , 1
Global Log Level= 0
CheckData=True
Encroach Param= -1, 0, 0, 0
BEGIN DESCRIPTION:
Multiple Run
END DESCRIPTION:

--- North Twin Creek Trib O.f01 (steady flow) ---

Flow Title=Multiple
Number of Profiles=7
Profile Names=10-year,25-year,50-year,1pct_min,100-year,1pct_plu,500-year
River Rch & RM= North Twin Creek,Reach-1,6670
     147     171     187     101     202     404     236
Boundary for River Rch & Prof#=North Twin Creek,Reach-1,1
Up Type=0
Dn Type=3
Dn Slope=0.005
Boundary for River Rch & Prof#=North Twin Creek,Reach-1,2
Up Type=0
Dn Type=3
Dn Slope=0.005
Boundary for River Rch & Prof#=North Twin Creek,Reach-1,3
Up Type=0
Dn Type=3
Dn Slope=0.005
Boundary for River Rch & Prof#=North Twin Creek,Reach-1,4
Up Type=0
Dn Type=3
Dn Slope=0.005
Boundary for River Rch & Prof#=North Twin Creek,Reach-1,5
Up Type=0
Dn Type=3
Dn Slope=0.005
Boundary for River Rch & Prof#=North Twin Creek,Reach-1,6
Up Type=0
Dn Type=3
Dn Slope=0.005
Boundary for River Rch & Prof#=North Twin Creek,Reach-1,7
Up Type=0
Dn Type=3
Dn Slope=0.005

--- North Twin Creek Trib O.g01 (geometry) ---

Geom Title=Existing Conditions

River Reach=North Twin Creek,Reach-1
Reach XY= 30
      2704626.00      6797461.00      2704623.17      6797552.89
      2704436.53      6797701.25      2704420.75      6797805.56
      2704219.54      6797868.74      2704129.67      6798012.59
      2704133.65      6798117.45      2704269.02      6798210.80
      2704077.55      6798366.85      2704115.02      6798671.49
      2703705.43      6798780.58      2703633.59      6798961.01
      2703672.84      6799059.35      2703532.67      6799202.05
      2703383.79      6799064.42      2703468.22      6798860.90
      2703426.36      6798568.20      2703286.97      6798650.62
      2703322.54      6798809.50      2703127.73      6799016.63
      2703203.58      6799234.42      2703089.94      6799311.02
      2702982.95      6799170.17      2702772.38      6799168.86
      2702718.30      6799367.48      2702570.07      6799458.75
      2702331.85      6799509.46      2702226.21      6799367.98
      2702072.67      6799503.41      2701576.00      6799061.00

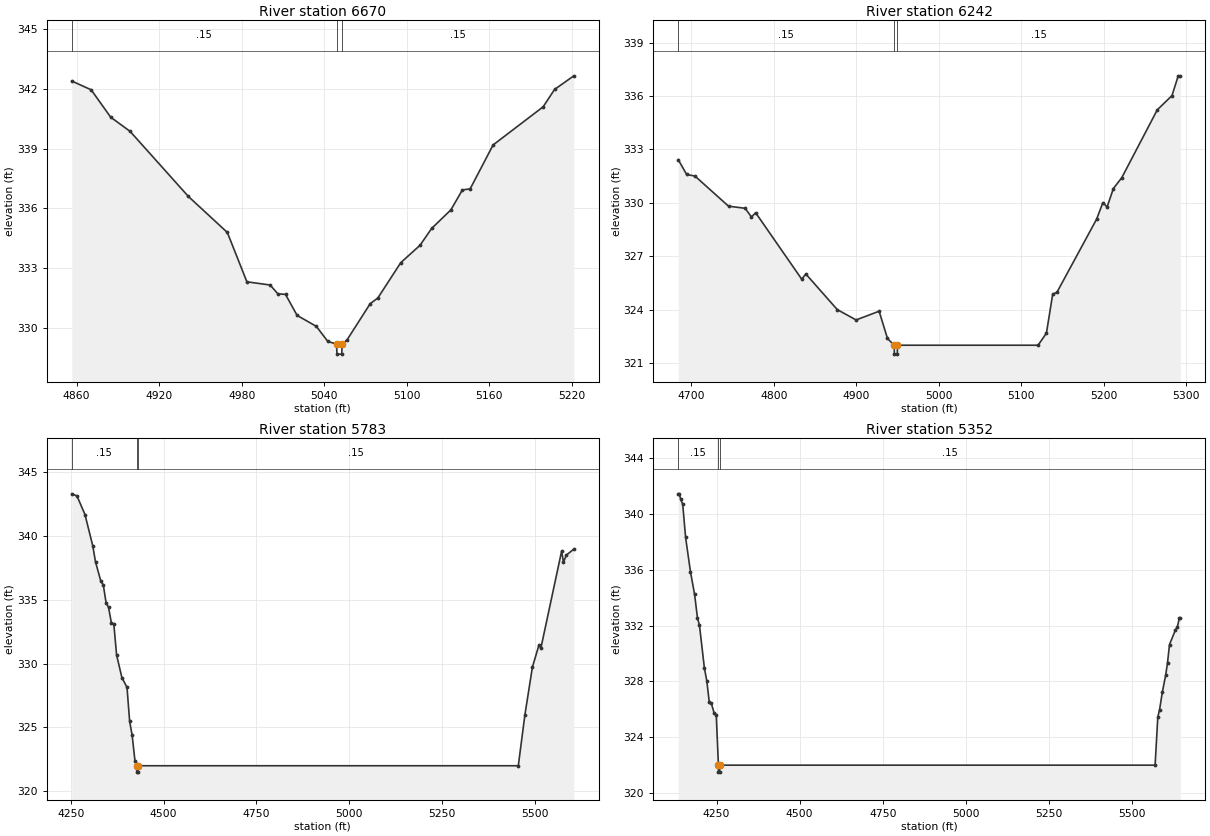
Type RM Length L Ch R = 1,6670,428,428,428
BEGIN DESCRIPTION:
North Twin Creek Trib O 4.0
END DESCRIPTION:
XS GIS Cut Line= 3
      2704526.00      6797411.00      2704626.00      6797511.00
      2704725.99      6797710.98
#Sta/Elev= 30
  4856.5  342.38  4870.6  341.94  4884.8  340.57  4898.9  339.86  4941.3  336.60
  4969.6  334.80  4983.8  332.33  5000.7  332.17  5006.3  331.73  5011.9  331.70
  5020.3  330.65  5034.3  330.10  5042.6  329.35  5049.0  329.21  5049.3  328.71
  5052.8  328.71  5053.0  329.21  5056.6  329.42  5073.4  331.23  5079.0  331.52
  5095.7  333.29  5109.7  334.16  5118.1  335.00  5132.1  335.93  5140.5  336.93
  5146.1  336.98  5162.8  339.18  5199.2  341.09  5207.5  341.96  5221.5  342.64
#Mann=3,-1,0
  4856.5    0.15       0  5049.0    0.05       0  5053.0    0.15       0
Bank Sta=5049,5053
Exp/Cntr=0.3,0.1

Type RM Length L Ch R = 1,6242,459,459,459
BEGIN DESCRIPTION:
North Twin Creek Trib O 3.0
END DESCRIPTION:
XS GIS Cut Line= 3
      2704325.99      6797510.96      2704376.00      6797811.00
      2704675.98      6797861.00
#Sta/Elev= 30
  4684.3  332.42  4694.5  331.59  4704.6  331.50  4745.2  329.81  4765.4  329.69
  4773.0  329.20  4778.1  329.44  4833.9  325.71  4838.9  326.00  4877.0  324.00
  4899.8  323.42  4927.7  323.91  4937.8  322.38  4945.9  322.00  4946.2  321.50
  4949.7  321.50  4949.9  322.00  5120.3  322.00  5130.4  322.68  5138.0  324.87
  5143.1  324.97  5191.2  329.08  5198.8  330.01  5203.9  329.76  5211.5  330.80
  5221.7  331.41  5264.7  335.22  5282.5  336.02  5290.1  337.13  5292.6  337.13
#Mann=3,-1,0
  4684.3    0.15       0  4945.9    0.05       0  4949.9    0.15       0
Bank Sta=4945.9,4949.9
Exp/Cntr=0.3,0.1

Type RM Length L Ch R = 1,5783,431,431,431
BEGIN DESCRIPTION:
North Twin Creek Trib O 2.0
END DESCRIPTION:
XS GIS Cut Line= 3
      2703575.96      6797610.97      2704126.00      6798111.00
      2704725.97      6798011.00
#Sta/Elev= 30
  4252.9  343.30  4266.8  343.14  4288.4  341.68  4309.4  339.23  4316.8  337.97
  4331.0  336.47  4337.8  336.16  4345.2  334.78  4351.9  334.40  4359.4  333.22
  4366.1  333.10  4373.6  330.67  4387.8  328.91  4401.6  328.14  4408.7  325.48
  4415.5  324.37  4422.9  322.41  4427.7  322.00  4427.9  321.50  4431.4  321.50
  4431.7  322.00  5455.0  322.00  5472.7  325.98  5493.0  329.73  5510.8  331.48
  5515.8  331.22  5571.6  338.81  5576.6  337.95  5584.3  338.50  5604.5  338.97
#Mann=3,-1,0
  4252.9    0.15       0  4427.7    0.05       0  4431.7    0.15       0
Bank Sta=4427.7,4431.7
Exp/Cntr=0.3,0.1

Type RM Length L Ch R = 1,5352,0,0,0
BEGIN DESCRIPTION:
North Twin Creek Trib O 1.0
END DESCRIPTION:
XS GIS Cut Line= 3
      2703576.01      6797661.02      2704076.00      6798361.00
      2704675.99      6798111.00
#Sta/Elev= 30
  4134.7  341.46  4137.7  341.46  4142.0  341.08  4148.2  340.71  4156.8  338.34
  4171.5  335.87  4183.8  334.26  4192.4  332.59  4198.6  332.02  4213.3  328.98
  4220.7  328.03  4228.1  326.51  4234.2  326.43  4242.8  325.73  4249.0  325.61
  4255.6  322.00  4255.8  321.50  4259.3  321.50  4259.6  322.00  5569.1  322.00
  5577.2  325.45  5582.6  325.99  5590.7  327.22  5601.0  328.47  5606.4  329.34
  5612.4  330.65  5630.3  331.70  5635.7  331.88  5642.2  332.56  5644.9  332.56
#Mann=3,-1,0
  4134.7    0.15       0  4255.6    0.05       0  4259.6    0.15       0
Bank Sta=4255.6,4259.6
Exp/Cntr=0.3,0.1

Chan Stop Cuts=-1