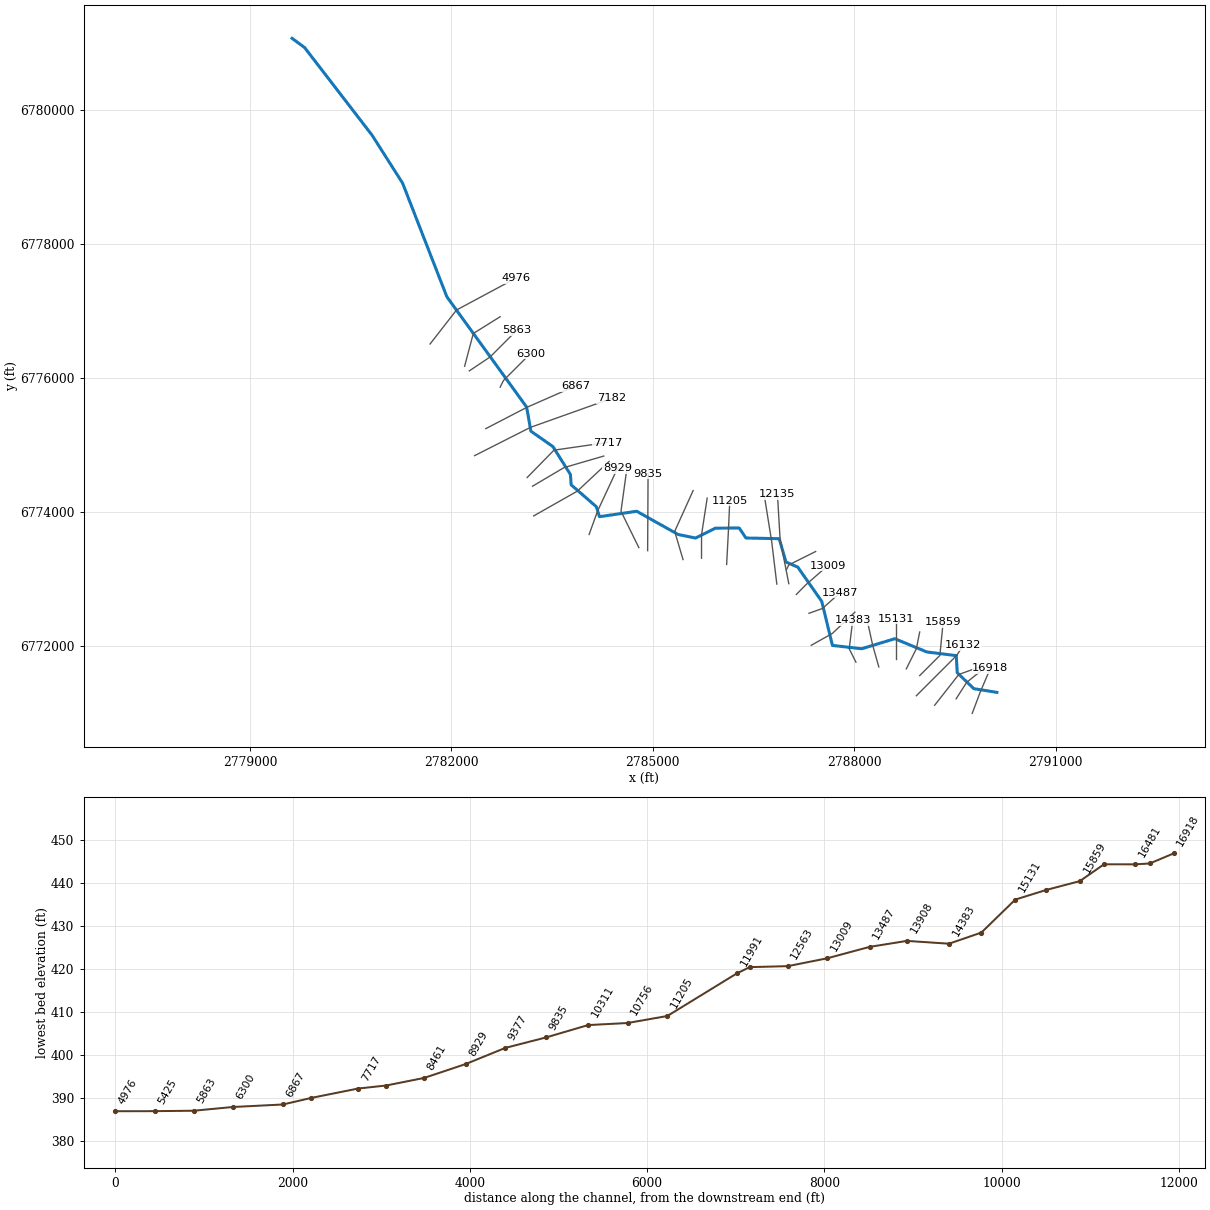
--- One Mile Creek.prj (project) ---

Proj Title=One Mile Creek Base Level Engineering
Current Plan=p01
Default Exp/Contr=0.3,0.1
English Units
Geom File=g01
Flow File=f01
Plan File=p01
BEGIN DESCRIPTION:
One Mile Creek
END DESCRIPTION:

--- One Mile Creek.p01 (plan) ---

Plan Title=Multiple Run
Short Identifier=Multiple
Geom File=g01
Flow File=f01
Subcritical Flow
K Sum by GR= 0
Std Step Tol= 0.01
Critical Tol= 0.01
Num of Std Step Trials= 20
Max Error Tol= 0.3
Flow Tol Ratio= 0.001
Split Flow NTrial= 30
Split Flow Tol= 0.02
Split Flow Ratio= 0.02
Log Output Level= 0
Friction Slope Method= 1
Unsteady Friction Slope Method= 2
Unsteady Bridges Friction Slope Method= 1
Parabolic Critical Depth
Global Vel Dist=  1 , 1 , 1
Global Log Level= 0
CheckData=True
Encroach Param= -1, 0, 0, 0
BEGIN DESCRIPTION:
Multiple Run
END DESCRIPTION:

--- One Mile Creek.f01 (steady flow) ---

Flow Title=Multiple
Number of Profiles=7
Profile Names=10-year,25-year,50-year,1pct_min,100-year,1pct_plu,500-year
River Rch & RM= One Mile Creek,Reach-1,16918
     268     344     403     236     471     939     640
River Rch & RM= One Mile Creek,Reach-1,15479
     491     655     788     472     941    1878    1345
River Rch & RM= One Mile Creek,Reach-1,13908
    1104    1541    1909    1174    2343    4674    3537
River Rch & RM= One Mile Creek,Reach-1,9377
    1333    1871    2328    1436    2865    5716    4351
River Rch & RM= One Mile Creek,Reach-1,4976
    1445    2025    2514    1546    3084    6154    4659
Boundary for River Rch & Prof#=One Mile Creek,Reach-1,1
Up Type=0
Dn Type=3
Dn Slope=0.005
Boundary for River Rch & Prof#=One Mile Creek,Reach-1,2
Up Type=0
Dn Type=3
Dn Slope=0.005
Boundary for River Rch & Prof#=One Mile Creek,Reach-1,3
Up Type=0
Dn Type=3
Dn Slope=0.005
Boundary for River Rch & Prof#=One Mile Creek,Reach-1,4
Up Type=0
Dn Type=3
Dn Slope=0.005
Boundary for River Rch & Prof#=One Mile Creek,Reach-1,5
Up Type=0
Dn Type=3
Dn Slope=0.005
Boundary for River Rch & Prof#=One Mile Creek,Reach-1,6
Up Type=0
Dn Type=3
Dn Slope=0.005
Boundary for River Rch & Prof#=One Mile Creek,Reach-1,7
Up Type=0
Dn Type=3
Dn Slope=0.005

--- One Mile Creek.g01 (geometry) ---

Geom Title=Existing Conditions

River Reach=One Mile Creek,Reach-1
Reach XY= 30
      2790126.00      6771311.00      2789781.62      6771366.62
      2789535.29      6771604.33      2789520.37      6771859.01
      2789081.94      6771913.27      2788605.97      6772110.96
      2788110.78      6771961.52      2787676.00      6772011.00
      2787516.70      6772667.67      2787159.73      6773178.21
      2786983.68      6773254.48      2786883.07      6773602.00
      2786387.53      6773612.50      2786286.12      6773761.84
      2785931.97      6773758.86      2785636.69      6773611.76
      2785377.55      6773664.75      2784760.96      6774010.66
      2784205.36      6773930.38      2784159.69      6774078.13
      2783783.82      6774404.81      2783772.46      6774559.53
      2783512.54      6774974.63      2783183.86      6775204.83
      2783120.53      6775563.45      2781931.83      6777208.70
      2781272.50      6778902.52      2780817.86      6779617.06
      2779812.37      6780924.21      2779626.00      6781061.00

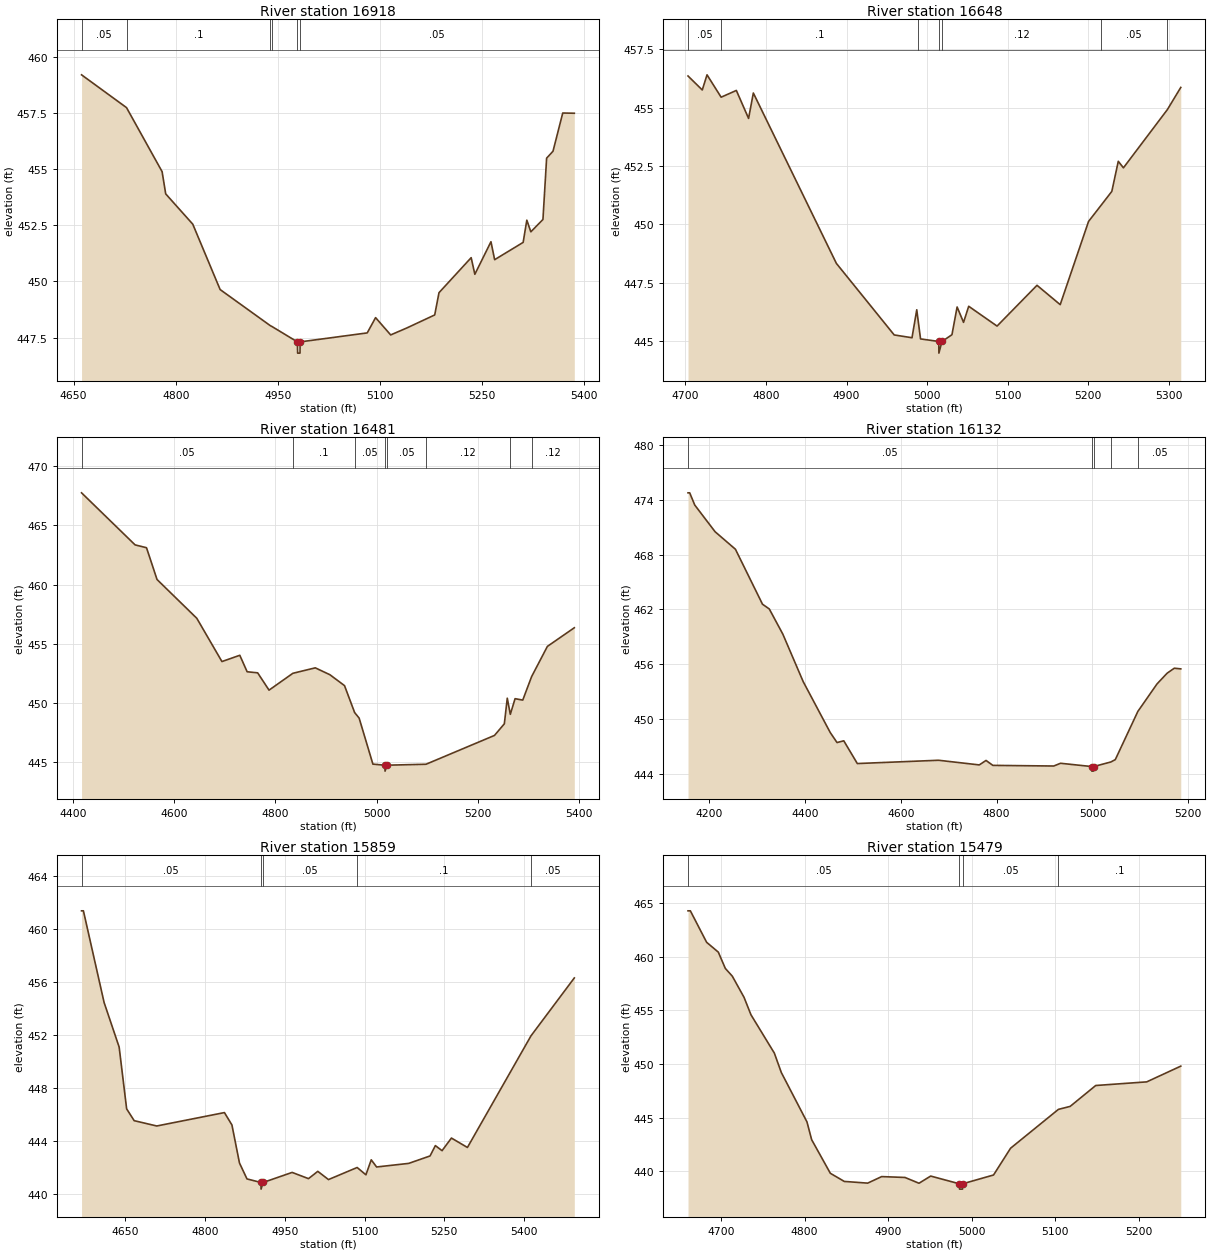
Type RM Length L Ch R = 1,16918,270,270,270
BEGIN DESCRIPTION:
One Mile Creek 40.0
END DESCRIPTION:
XS GIS Cut Line= 3
      2789758.31      6770997.97      2789876.00      6771311.00
      2790028.43      6771669.85
#Sta/Elev= 30
  4661.6  459.20  4727.7  457.74  4780.0  454.89  4785.3  453.90  4825.1  452.55
  4865.3  449.64  4939.2  448.03  4941.2  448.00  4978.9  447.31  4979.2  446.81
  4982.7  446.81  4982.9  447.31  5081.5  447.71  5093.8  448.39  5116.0  447.62
  5139.7  447.93  5180.7  448.51  5187.0  449.50  5234.3  451.06  5239.7  450.32
  5263.4  451.77  5268.8  450.97  5310.7  451.74  5316.1  452.73  5322.0  452.21
  5339.8  452.76  5345.2  455.49  5354.6  455.80  5368.9  457.50  5385.9  457.49
#Mann=6,-1,0
  4661.6    0.05       0  4727.7     0.1       0  4939.2    0.12       0
  4941.2    0.05       0  4978.9    0.03       0  4982.9    0.05       0
Bank Sta=4978.9,4982.9
Exp/Cntr=0.3,0.1

Type RM Length L Ch R = 1,16648,167,167,167
BEGIN DESCRIPTION:
One Mile Creek 39.0
END DESCRIPTION:
XS GIS Cut Line= 3
      2789518.74      6771215.38      2789676.00      6771461.00
      2789926.00      6771661.00
#Sta/Elev= 30
  4703.2  456.36  4720.9  455.76  4726.8  456.41  4744.3  455.45  4763.2  455.74
  4778.4  454.54  4784.3  455.63  4887.4  448.32  4959.2  445.25  4981.3  445.13
  4987.2  446.33  4988.8  445.90  4991.9  445.08  5014.5  444.97  5014.7  444.47
  5018.5  444.97  5030.9  445.26  5037.3  446.45  5045.3  445.79  5051.7  446.48
  5086.9  445.63  5136.5  447.38  5165.3  446.55  5200.5  450.12  5216.0  450.81
  5229.4  451.41  5237.4  452.70  5243.8  452.42  5298.4  454.92  5315.0  455.87
#Mann=7,-1,0
  4703.2    0.05       0  4744.3     0.1       0  4988.8    0.12       0
  5014.5    0.07       0  5018.5    0.12       0  5216.0    0.05       0
  5298.4    0.12       0
Bank Sta=5014.5,5018.5
Exp/Cntr=0.3,0.1

Type RM Length L Ch R = 1,16481,349,349,349
BEGIN DESCRIPTION:
One Mile Creek 38.0
END DESCRIPTION:
XS GIS Cut Line= 3
      2789198.70      6771118.91      2789558.47      6771577.66
      2789926.03      6771711.01
#Sta/Elev= 30
  4417.0  467.74  4522.8  463.35  4545.4  463.11  4566.2  460.43  4644.8  457.16
  4694.5  453.51  4729.8  454.04  4744.3  452.65  4765.1  452.56  4787.6  451.10
  4834.7  452.52  4879.0  452.98  4907.9  452.40  4936.8  451.48  4956.8  449.21
  4965.7  448.74  4992.9  444.86  5016.6  444.77  5016.9  444.27  5020.6  444.77
  5097.9  444.85  5233.2  447.28  5252.7  448.26  5258.5  450.42  5264.5  449.06
  5273.9  450.38  5289.1  450.26  5306.6  452.24  5337.8  454.79  5391.0  456.36
#Mann=8,-1,0
  4417.0    0.05       0  4834.7     0.1       0  4956.8    0.05       0
  5016.6    0.05       0  5020.6    0.05       0  5097.9    0.12       0
  5264.5     0.1       0  5306.6    0.12       0
Bank Sta=5016.6,5020.6
Exp/Cntr=0.3,0.1

Type RM Length L Ch R = 1,16132,273,273,273
BEGIN DESCRIPTION:
One Mile Creek 37.0
END DESCRIPTION:
XS GIS Cut Line= 3
      2788926.03      6771261.03      2789526.00      6771861.00
      2789626.02      6772011.03
#Sta/Elev= 30
  4155.6  474.76  4159.1  474.76  4169.7  473.42  4212.1  470.50  4254.6  468.58
  4311.1  462.56  4325.3  462.04  4353.6  459.28  4396.0  454.09  4452.5  448.51
  4466.7  447.41  4480.8  447.60  4509.1  445.11  4678.8  445.47  4763.7  444.96
  4777.8  445.45  4792.0  444.91  4919.2  444.84  4933.4  445.14  4998.6  444.78
  4998.8  444.28  5002.3  444.28  5002.6  444.78  5038.3  445.28  5047.7  445.54
  5094.8  450.82  5134.8  453.83  5155.8  455.00  5170.8  455.55  5184.4  455.48
#Mann=5,-1,0
  4155.6    0.05       0  4998.6    0.05       0  5002.6    0.05       0
  5038.3     0.1       0  5094.8    0.05       0
Bank Sta=4998.6,5002.6
Exp/Cntr=0.3,0.1

Type RM Length L Ch R = 1,15859,380,380,380
BEGIN DESCRIPTION:
One Mile Creek 36.0
END DESCRIPTION:
XS GIS Cut Line= 3
      2788976.01      6771561.01      2789276.00      6771861.00
      2789326.00      6772360.96
#Sta/Elev= 30
  4567.8  461.35  4571.3  461.35  4610.2  454.44  4638.5  451.08  4652.6  446.42
  4666.8  445.53  4709.2  445.13  4836.5  446.14  4850.6  445.21  4864.8  442.34
  4878.9  441.14  4905.2  440.87  4905.4  440.37  4909.2  440.87  4963.8  441.63
  4994.6  441.16  5012.1  441.71  5032.2  441.09  5086.1  442.00  5102.6  441.45
  5112.6  442.58  5122.7  442.04  5183.0  442.31  5223.2  442.87  5233.2  443.65
  5245.8  443.27  5263.4  444.22  5293.5  443.51  5413.1  451.93  5494.5  456.29
#Mann=5,-1,0
  4567.8    0.05       0  4905.2    0.03       0  4909.2    0.05       0
  5086.1     0.1       0  5413.1    0.05       0
Bank Sta=4905.2,4909.2
Exp/Cntr=0.3,0.1

Type RM Length L Ch R = 1,15479,348,348,348
BEGIN DESCRIPTION:
One Mile Creek 35.0
END DESCRIPTION:
XS GIS Cut Line= 3
      2788776.01      6771661.02      2788926.00      6771961.00
      2788975.99      6772210.96
#Sta/Elev= 30
  4660.3  464.31  4663.1  464.31  4682.6  461.37  4696.6  460.45  4705.0  458.93
  4713.4  458.20  4727.4  456.23  4735.7  454.60  4763.7  451.02  4772.1  449.20
  4802.8  444.59  4808.4  442.93  4830.8  439.79  4847.5  439.03  4875.5  438.87
  4892.3  439.48  4920.2  439.40  4937.0  438.86  4951.0  439.53  4985.3  438.81
  4985.6  438.31  4989.1  438.31  4989.3  438.81  5026.3  439.63  5046.7  442.13
  5104.0  445.76  5118.1  446.04  5148.7  447.99  5209.8  448.33  5250.6  449.80
#Mann=4,-1,0
  4660.3    0.05       0  4985.3    0.03       0  4989.3    0.05       0
  5104.0     0.1       0
Bank Sta=4985.3,4989.3
Exp/Cntr=0.3,0.1

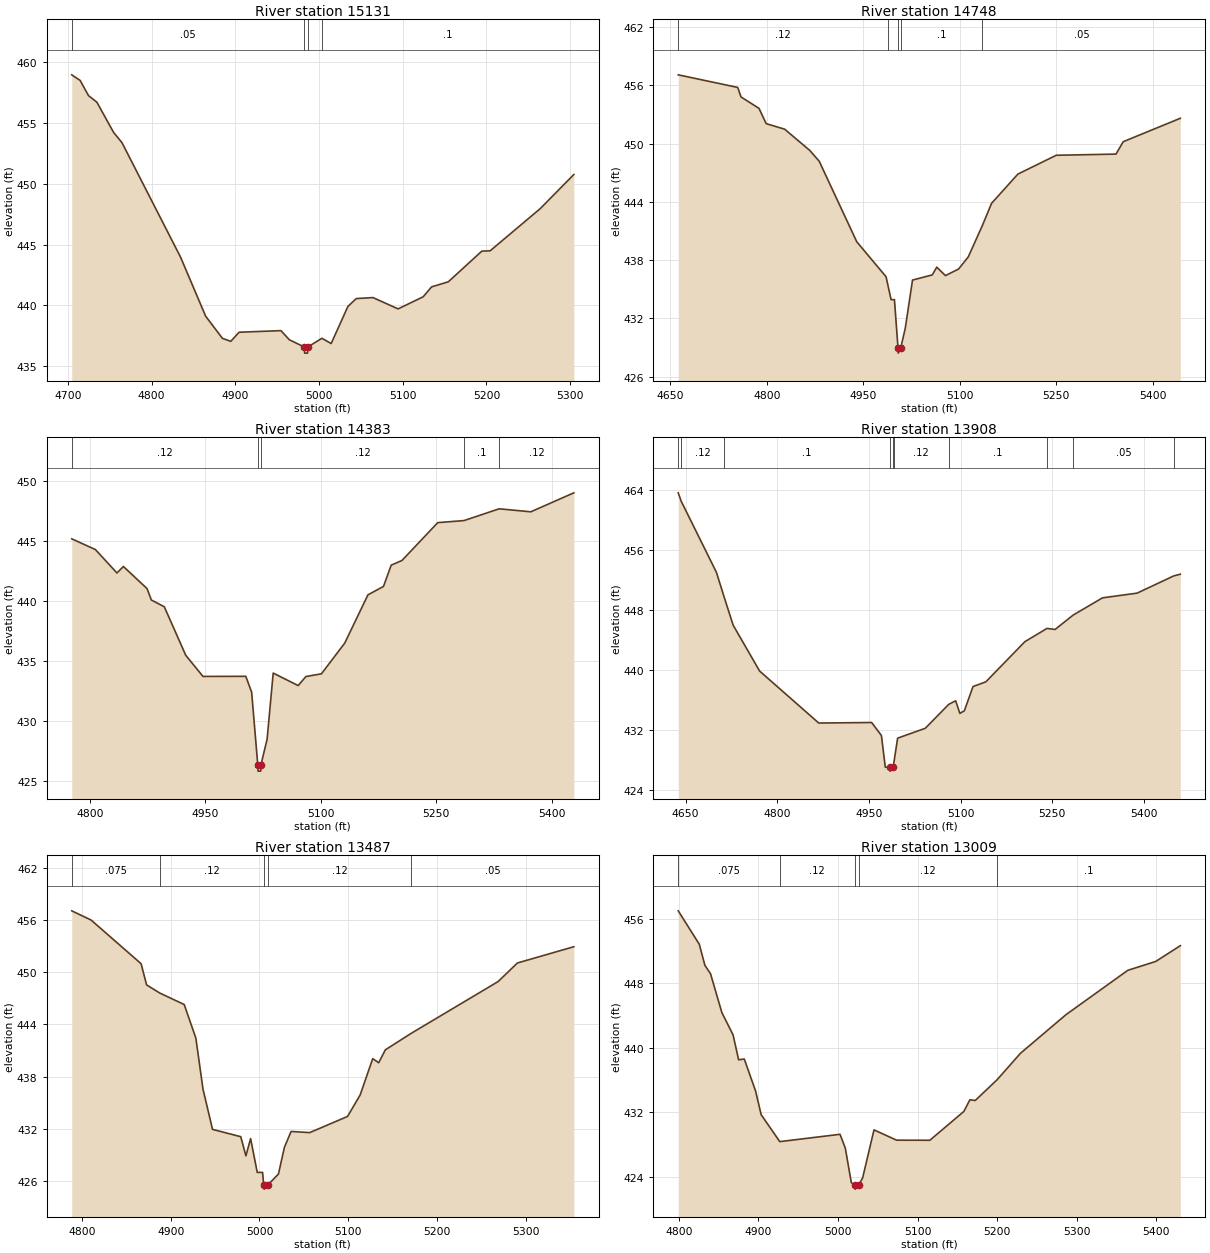
Type RM Length L Ch R = 1,15131,383,383,383
BEGIN DESCRIPTION:
One Mile Creek 34.0
END DESCRIPTION:
XS GIS Cut Line= 3
      2788626.00      6771810.98      2788626.00      6772111.00
      2788626.00      6772410.98
#Sta/Elev= 30
  4704.5  458.98  4714.5  458.52  4724.5  457.27  4734.5  456.73  4754.5  454.24
  4764.5  453.40  4834.5  443.98  4864.5  439.12  4884.5  437.30  4894.5  437.05
  4904.5  437.80  4954.5  437.93  4964.5  437.18  4982.5  436.58  4982.8  436.08
  4986.3  436.08  4986.5  436.58  5003.4  437.30  5014.5  436.87  5034.5  439.92
  5044.5  440.57  5064.5  440.65  5094.5  439.72  5124.5  440.72  5134.5  441.53
  5154.5  441.95  5194.5  444.47  5204.5  444.50  5264.5  447.98  5304.5  450.78
#Mann=4,-1,0
  4704.5    0.05       0  4982.5    0.03       0  4986.5    0.05       0
  5003.4     0.1       0
Bank Sta=4982.5,4986.5
Exp/Cntr=0.3,0.1

Type RM Length L Ch R = 1,14748,365,365,365
BEGIN DESCRIPTION:
One Mile Creek 33.0
END DESCRIPTION:
XS GIS Cut Line= 3
      2788367.16      6771690.19      2788276.00      6772011.00
      2788180.49      6772447.67
#Sta/Elev= 30
  4662.2  457.09  4754.7  455.79  4759.8  454.81  4787.8  453.63  4798.9  452.06
  4827.6  451.49  4866.7  449.30  4881.4  448.18  4939.7  439.89  4985.3  436.28
  4988.1  435.43  4993.1  433.92  4998.3  433.92  5003.9  428.91  5004.2  428.41
  5007.9  428.91  5015.1  430.96  5026.4  435.94  5057.1  436.47  5064.1  437.27
  5077.6  436.40  5098.1  437.08  5113.1  438.33  5135.0  441.56  5149.3  443.85
  5190.2  446.86  5249.8  448.80  5342.7  448.92  5354.0  450.20  5442.7  452.61
#Mann=5,-1,0
  4662.2    0.12       0  4988.1     0.1       0  5003.9    0.07       0
  5007.9     0.1       0  5135.0    0.05       0
Bank Sta=5003.9,5007.9
Exp/Cntr=0.3,0.1

Type RM Length L Ch R = 1,14383,475,475,475
BEGIN DESCRIPTION:
One Mile Creek 32.0
END DESCRIPTION:
XS GIS Cut Line= 3
      2788026.00      6771761.01      2787926.00      6771961.00
      2787978.47      6772386.48
#Sta/Elev= 30
  4776.5  445.16  4807.2  444.27  4835.2  442.32  4843.6  442.86  4874.3  441.02
  4879.9  440.07  4896.7  439.51  4924.6  435.47  4947.0  433.71  5002.6  433.72
  5010.2  432.40  5018.2  426.33  5018.5  425.83  5022.0  425.83  5022.2  426.33
  5030.3  428.49  5038.2  433.99  5070.6  432.95  5080.7  433.70  5100.9  433.93
  5131.1  436.48  5161.3  440.50  5181.5  441.20  5191.5  442.97  5205.5  443.36
  5252.0  446.51  5286.1  446.68  5331.8  447.66  5372.9  447.41  5428.8  448.99
#Mann=5,-1,0
  4776.5    0.12       0  5018.2    0.07       0  5022.2    0.12       0
  5286.1     0.1       0  5331.8    0.12       0
Bank Sta=5018.2,5022.2
Exp/Cntr=0.3,0.1

Type RM Length L Ch R = 1,13908,421,421,421
BEGIN DESCRIPTION:
One Mile Creek 31.0
END DESCRIPTION:
XS GIS Cut Line= 3
      2787360.79      6772012.96      2787676.21      6772190.79
      2788010.16      6772506.71
#Sta/Elev= 30
  4637.9  463.63  4642.7  462.52  4700.4  453.02  4713.6  449.58  4727.8  445.96
  4771.1  439.84  4867.9  432.90  4954.5  432.97  4970.5  431.23  4976.8  427.01
  4983.9  426.98  4984.5  426.48  4988.9  426.98  4990.5  427.42  4997.0  430.88
  5042.3  432.20  5080.6  435.39  5092.0  435.87  5098.9  434.19  5106.2  434.53
  5120.4  437.77  5141.4  438.40  5205.3  443.76  5241.5  445.53  5254.7  445.39
  5284.3  447.31  5332.3  449.61  5389.0  450.24  5448.7  452.53  5459.7  452.77
#Mann=10,-1,0
  4637.9    0.05       0  4642.7    0.12       0  4713.6     0.1       0
  4983.9    0.07       0  4988.9     0.1       0  4990.5    0.12       0
  5080.6     0.1       0  5241.5    0.12       0  5284.3    0.05       0
  5448.7    0.12       0
Bank Sta=4983.9,4988.9
Exp/Cntr=0.3,0.1

Type RM Length L Ch R = 1,13487,478,478,478
BEGIN DESCRIPTION:
One Mile Creek 30.0
END DESCRIPTION:
XS GIS Cut Line= 3
      2787326.62      6772490.08      2787526.00      6772561.00
      2787790.16      6772796.78
#Sta/Elev= 30
  4788.5  457.04  4810.3  455.98  4866.6  450.97  4872.8  448.54  4887.5  447.61
  4915.2  446.28  4928.3  442.43  4936.4  436.55  4947.1  431.95  4978.9  431.11
  4984.7  428.91  4990.0  430.89  4997.5  427.01  5003.5  427.01  5004.7  425.59
  5005.4  425.09  5009.7  425.59  5021.4  426.83  5028.1  429.89  5035.6  431.71
  5056.6  431.58  5099.2  433.43  5113.4  435.89  5127.6  440.07  5134.3  439.60
  5141.8  441.08  5170.7  442.96  5268.9  448.92  5290.6  451.05  5354.2  452.92
#Mann=5,-1,0
  4788.5   0.075       0  4887.5    0.12       0  5004.7    0.07       0
  5009.7    0.12       0  5170.7    0.05       0
Bank Sta=5004.7,5009.7
Exp/Cntr=0.3,0.1

Type RM Length L Ch R = 1,13009,446,446,446
BEGIN DESCRIPTION:
One Mile Creek 29.0
END DESCRIPTION:
XS GIS Cut Line= 3
      2787138.50      6772771.12      2787276.00      6772911.00
      2787603.25      6773197.22
#Sta/Elev= 30
  4799.2  457.01  4825.7  452.85  4832.7  450.24  4839.8  449.19  4854.0  444.38
  4868.1  441.60  4875.1  438.51  4882.2  438.60  4896.4  434.63  4903.4  431.69
  4926.8  428.34  5002.5  429.25  5009.1  427.55  5016.7  423.25  5020.8  422.94
  5021.4  422.44  5025.8  422.94  5030.9  423.83  5045.2  429.80  5073.6  428.52
  5115.4  428.51  5158.1  432.09  5165.7  433.54  5172.4  433.45  5200.2  436.06
  5229.3  439.32  5286.3  444.10  5364.1  449.62  5399.2  450.72  5430.1  452.68
#Mann=5,-1,0
  4799.2   0.075       0  4926.8    0.12       0  5020.8    0.07       0
  5025.8    0.12       0  5200.2     0.1       0
Bank Sta=5020.8,5025.8
Exp/Cntr=0.3,0.1

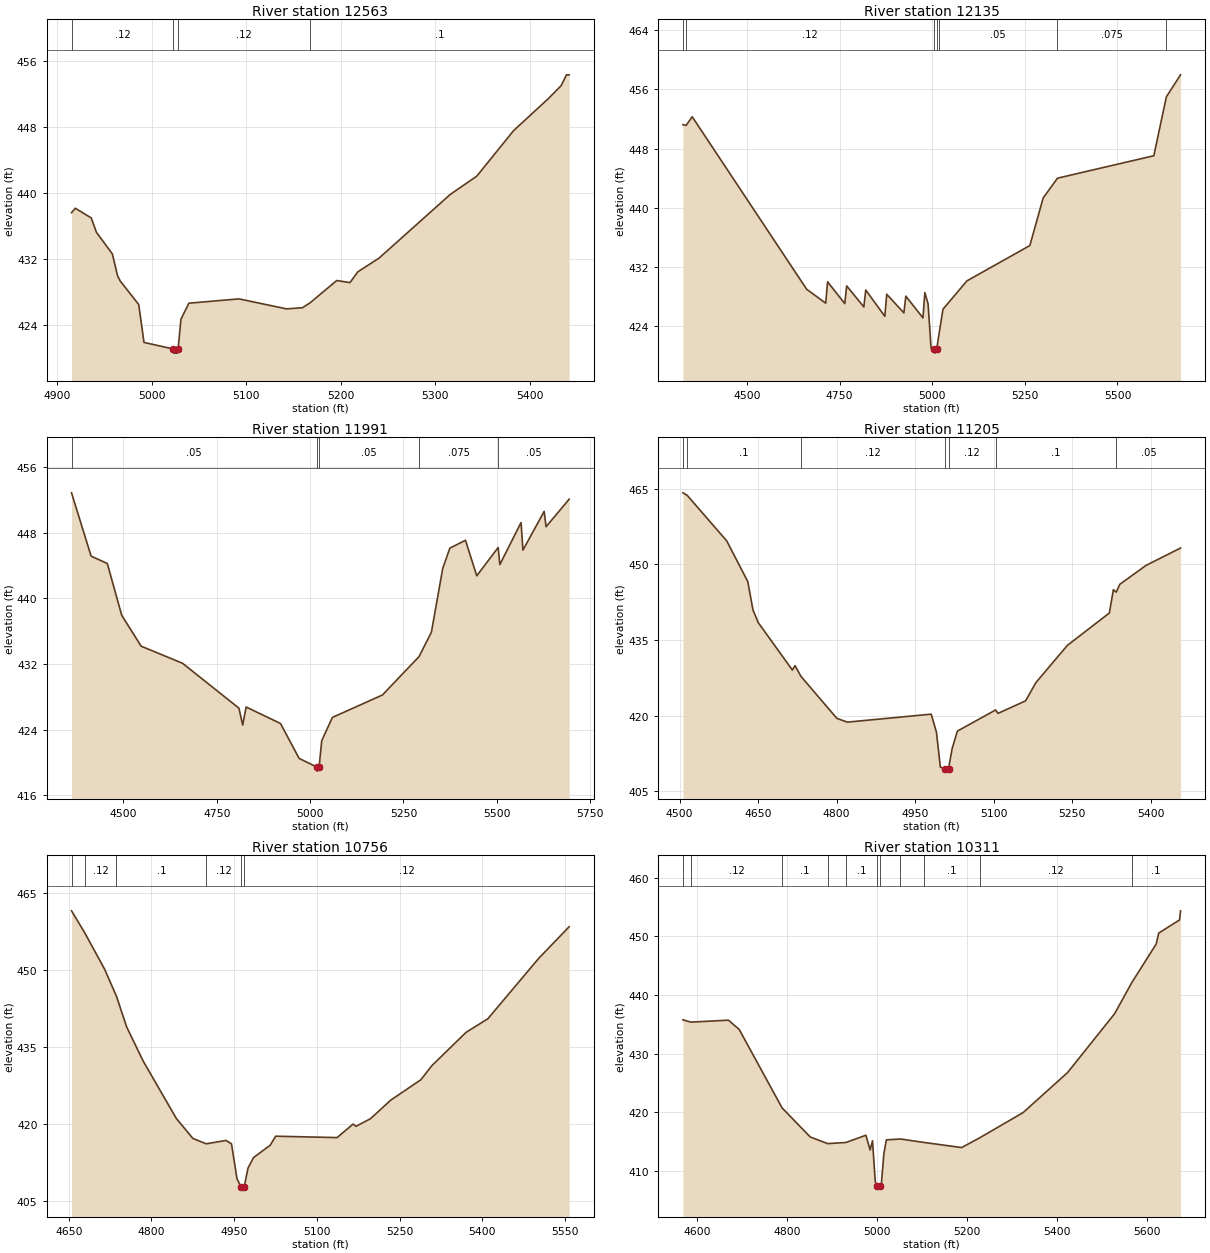
Type RM Length L Ch R = 1,12563,428,428,428
BEGIN DESCRIPTION:
One Mile Creek 28.0
END DESCRIPTION:
XS GIS Cut Line= 3
      2786990.45      6773139.90      2787026.00      6773211.00
      2787426.00      6773411.00
#Sta/Elev= 30
  4915.2  437.65  4919.2  438.19  4936.0  437.02  4941.6  435.26  4958.4  432.65
  4963.9  430.01  4966.7  429.37  4986.3  426.51  4991.9  421.91  5022.9  421.11
  5023.5  420.61  5027.3  420.61  5028.0  421.11  5031.0  424.72  5039.4  426.67
  5092.5  427.19  5142.8  425.98  5159.6  426.12  5167.5  426.70  5195.9  429.42
  5209.9  429.17  5218.3  430.48  5240.7  432.14  5316.1  439.87  5344.1  442.08
  5383.2  447.62  5419.5  451.45  5433.5  453.07  5439.1  454.38  5441.9  454.38
#Mann=4,-1,0
  4915.2    0.12       0  5022.9    0.07       0  5028.0    0.12       0
  5167.5     0.1       0
Bank Sta=5022.9,5028
Exp/Cntr=0.3,0.1

Type RM Length L Ch R = 1,12135,144,144,144
BEGIN DESCRIPTION:
One Mile Creek 27.0
END DESCRIPTION:
XS GIS Cut Line= 3
      2787025.85      6772931.76      2786896.52      6773591.91
      2786856.92      6774261.04
#Sta/Elev= 30
  4327.3  451.25  4336.1  451.16  4352.3  452.32  4661.2  429.02  4712.6  427.14
  4717.7  430.02  4764.1  427.08  4769.2  429.47  4815.6  426.63  4820.7  428.92
  4872.2  425.36  4877.3  428.34  4923.7  425.82  4928.8  428.09  4975.1  425.15
  4980.2  428.56  4988.9  427.06  4997.0  421.07  5006.1  420.89  5007.1  420.39
  5012.1  420.89  5017.5  422.66  5029.1  426.32  5093.8  430.15  5263.6  434.92
  5299.6  441.35  5338.2  444.02  5598.2  447.05  5632.1  455.01  5670.3  457.98
#Mann=7,-1,0
  4327.3   0.075       0  4336.1    0.12       0  5006.1    0.07       0
  5012.1    0.12       0  5017.5    0.05       0  5338.2   0.075       0
  5632.1    0.05       0
Bank Sta=5006.1,5012.1
Exp/Cntr=0.3,0.1

Type RM Length L Ch R = 1,11991,786,786,786
BEGIN DESCRIPTION:
One Mile Creek 26.0
END DESCRIPTION:
XS GIS Cut Line= 3
      2786847.50      6772925.92      2786770.98      6773560.22
      2786660.90      6774245.23
#Sta/Elev= 30
  4361.1  452.85  4413.5  445.14  4456.9  444.24  4495.5  437.93  4547.5  434.17
  4658.3  432.09  4809.4  426.62  4819.5  424.56  4828.7  426.76  4920.8  424.75
  4970.6  420.50  5018.0  419.45  5019.0  418.95  5024.1  419.45  5031.2  422.66
  5059.7  425.49  5193.6  428.22  5291.8  432.90  5324.9  435.87  5355.3  443.65
  5374.3  446.11  5416.1  447.07  5446.4  442.74  5503.7  446.19  5508.2  444.11
  5565.0  449.23  5570.1  445.87  5626.9  450.59  5632.0  448.72  5693.8  452.07
#Mann=5,-1,0
  4361.1    0.05       0  5018.0    0.03       0  5024.1    0.05       0
  5291.8   0.075       0  5503.7    0.05       0
Bank Sta=5018,5024.1
Exp/Cntr=0.3,0.1

Type RM Length L Ch R = 1,11205,449,449,449
BEGIN DESCRIPTION:
One Mile Creek 25.0
END DESCRIPTION:
XS GIS Cut Line= 3
      2786099.98      6773217.39      2786126.00      6773711.00
      2786146.69      6774166.83
#Sta/Elev= 30
  4506.5  464.18  4514.6  463.69  4590.2  454.65  4630.3  446.61  4640.3  440.98
  4650.3  438.47  4715.6  429.06  4720.6  429.94  4731.9  427.82  4800.5  419.49
  4820.5  418.74  4980.8  420.32  4990.8  416.75  4998.3  409.81  5007.7  409.53
  5008.8  409.03  5013.9  409.53  5020.8  413.50  5030.8  416.96  5103.8  421.15
  5108.5  420.48  5161.0  422.95  5181.0  426.60  5241.0  433.96  5321.1  440.36
  5328.8  444.99  5334.2  444.49  5341.1  446.05  5391.2  449.80  5457.1  453.24
#Mann=7,-1,0
  4506.5    0.05       0  4514.6     0.1       0  4731.9    0.12       0
  5007.7    0.07       0  5013.9    0.12       0  5103.8     0.1       0
  5334.2    0.05       0
Bank Sta=5007.7,5013.9
Exp/Cntr=0.3,0.1

Type RM Length L Ch R = 1,10756,445,445,445
BEGIN DESCRIPTION:
One Mile Creek 24.0
END DESCRIPTION:
XS GIS Cut Line= 3
      2785726.00      6773311.03      2785726.00      6773661.00
      2785809.93      6774206.81
#Sta/Elev= 30
  4655.1  461.56  4679.4  457.22  4715.1  450.19  4736.5  444.95  4755.1  438.95
  4785.1  432.30  4845.1  421.15  4875.1  417.27  4899.2  416.22  4935.1  416.87
  4945.1  416.22  4955.1  409.41  4962.0  407.90  4963.0  407.40  4968.2  407.90
  4975.1  411.50  4985.1  413.54  5015.2  415.94  5025.3  417.70  5136.6  417.43
  5165.7  420.07  5170.8  419.62  5197.3  421.12  5234.0  424.73  5288.4  428.68
  5308.6  431.45  5370.6  437.93  5409.8  440.54  5502.2  452.32  5557.3  458.46
#Mann=6,-1,0
  4655.1     0.1       0  4679.4    0.12       0  4736.5     0.1       0
  4899.2    0.12       0  4962.0    0.07       0  4968.2    0.12       0
Bank Sta=4962,4968.2
Exp/Cntr=0.3,0.1

Type RM Length L Ch R = 1,10311,476,476,476
BEGIN DESCRIPTION:
One Mile Creek 23.0
END DESCRIPTION:
XS GIS Cut Line= 3
      2785450.35      6773291.03      2785326.00      6773711.00
      2785601.05      6774319.97
#Sta/Elev= 30
  4568.2  435.76  4585.8  435.37  4669.4  435.70  4693.3  434.12  4788.7  420.75
  4851.3  415.80  4890.1  414.67  4930.7  414.87  4974.9  416.10  4984.4  413.58
  4989.6  415.16  4995.8  408.15  5000.5  407.42  5001.5  406.92  5006.7  407.42
  5008.9  407.42  5015.0  413.02  5020.5  415.31  5051.7  415.46  5103.5  414.88
  5187.8  414.00  5228.1  415.67  5324.4  419.96  5423.2  426.77  5528.0  436.82
  5566.1  442.11  5620.4  448.69  5625.9  450.54  5672.2  452.78  5674.4  454.33
#Mann=11,-1,0
  4568.2     0.1       0  4585.8    0.12       0  4788.7     0.1       0
  4890.1    0.12       0  4930.7     0.1       0  5000.5    0.07       0
  5006.7     0.1       0  5051.7    0.12       0  5103.5     0.1       0
  5228.1    0.12       0  5566.1     0.1       0
Bank Sta=5000.5,5006.7
Exp/Cntr=0.3,0.1

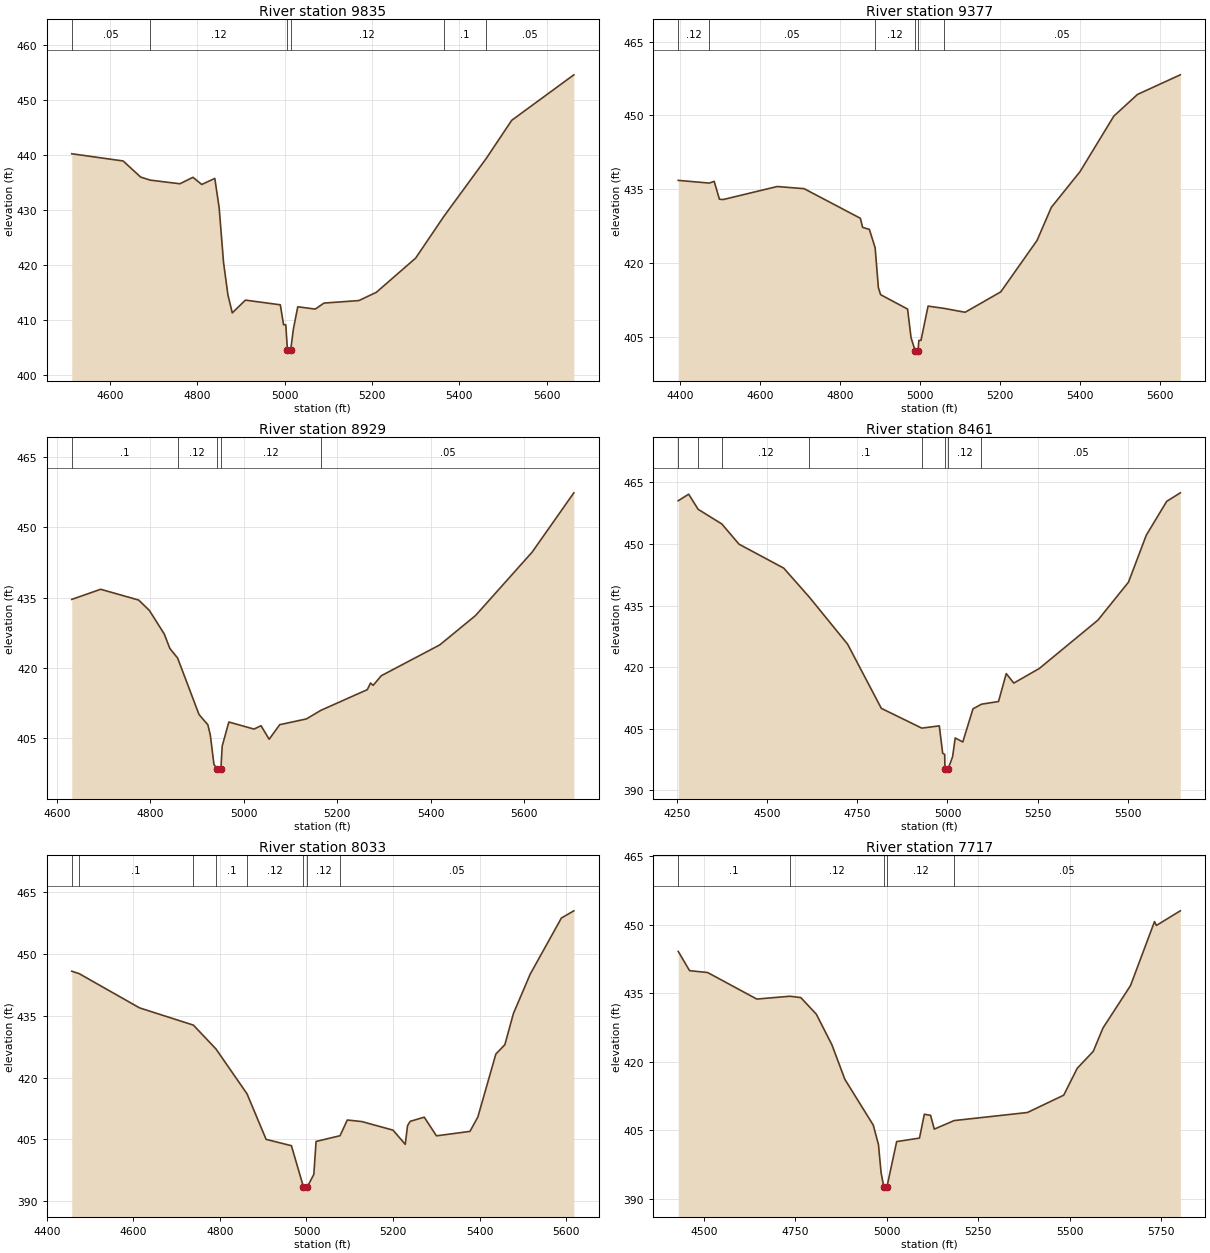
Type RM Length L Ch R = 1,9835,458,458,458
BEGIN DESCRIPTION:
One Mile Creek 22.0
END DESCRIPTION:
XS GIS Cut Line= 3
      2784922.90      6773423.28      2784926.00      6773911.00
      2784929.32      6774573.37
#Sta/Elev= 30
  4512.3  440.26  4630.0  438.95  4670.0  436.03  4691.9  435.47  4760.0  434.81
  4790.0  435.98  4810.0  434.68  4840.0  435.78  4850.0  430.41  4860.0  420.49
  4870.0  414.63  4880.0  411.35  4910.0  413.67  4990.0  412.82  4997.5  409.20
  5002.5  409.20  5006.4  404.54  5007.6  404.04  5013.6  404.54  5020.0  408.43
  5030.0  412.46  5070.0  412.04  5090.0  413.13  5170.0  413.59  5210.0  415.09
  5300.0  421.30  5364.2  428.83  5462.1  439.45  5520.0  446.33  5662.4  454.60
#Mann=6,-1,0
  4512.3    0.05       0  4691.9    0.12       0  5006.4    0.07       0
  5013.6    0.12       0  5364.2     0.1       0  5462.1    0.05       0
Bank Sta=5006.4,5013.6
Exp/Cntr=0.3,0.1

Type RM Length L Ch R = 1,9377,448,448,448
BEGIN DESCRIPTION:
One Mile Creek 21.0
END DESCRIPTION:
XS GIS Cut Line= 3
      2784792.20      6773468.51      2784526.00      6774011.00
      2784615.16      6774655.57
#Sta/Elev= 30
  4395.3  436.79  4472.8  436.24  4485.2  436.59  4498.3  432.95  4507.7  432.89
  4642.7  435.54  4710.0  435.10  4850.6  429.07  4856.2  427.22  4873.1  426.81
  4887.5  423.07  4895.6  414.95  4901.2  413.52  4968.6  410.59  4977.3  404.74
  4987.5  402.12  4988.6  401.62  4994.7  402.12  4996.8  404.21  5002.1  404.21
  5019.8  411.19  5059.1  410.74  5112.4  409.94  5201.5  414.09  5292.3  424.58
  5327.9  431.30  5399.7  438.58  5484.2  449.88  5543.3  454.29  5650.3  458.28
#Mann=6,-1,0
  4395.3    0.12       0  4472.8    0.05       0  4887.5    0.12       0
  4987.5    0.07       0  4994.7    0.12       0  5059.1    0.05       0
Bank Sta=4987.5,4994.7
Exp/Cntr=0.3,0.1

Type RM Length L Ch R = 1,8929,468,468,468
BEGIN DESCRIPTION:
One Mile Creek 20.0
END DESCRIPTION:
XS GIS Cut Line= 3
      2784051.18      6773664.66      2784176.00      6774011.00
      2784473.91      6774652.00
#Sta/Elev= 30
  4631.9  434.61  4693.7  436.78  4775.2  434.47  4798.1  432.25  4830.0  427.20
  4841.9  424.12  4858.6  422.05  4904.4  409.97  4923.3  407.78  4928.6  405.56
  4936.3  399.32  4942.7  398.36  4943.9  397.86  4951.2  398.36  4954.0  403.23
  4968.2  408.37  5022.1  406.86  5037.1  407.58  5054.5  404.69  5077.2  407.80
  5134.2  409.03  5165.5  410.88  5264.7  415.30  5271.6  416.72  5277.1  416.21
  5294.5  418.27  5419.9  424.88  5496.3  431.15  5617.6  444.73  5706.9  457.42
#Mann=5,-1,0
  4631.9     0.1       0  4858.6    0.12       0  4942.7    0.07       0
  4951.2    0.12       0  5165.5    0.05       0
Bank Sta=4942.7,4951.2
Exp/Cntr=0.3,0.1

Type RM Length L Ch R = 1,8461,428,428,428
BEGIN DESCRIPTION:
One Mile Creek 19.0
END DESCRIPTION:
XS GIS Cut Line= 3
      2783225.64      6773941.78      2783876.00      6774311.00
      2784347.69      6774752.74
#Sta/Elev= 30
  4252.4  460.54  4281.4  462.14  4307.7  458.45  4373.5  454.88  4421.3  449.95
  4545.3  444.12  4616.7  437.02  4722.7  425.58  4816.3  409.94  4928.7  405.12
  4977.3  405.67  4986.6  399.02  4992.3  398.70  4993.1  395.14  4994.4  394.64
  5001.6  395.14  5014.2  398.15  5021.5  402.73  5042.5  401.75  5070.9  409.83
  5094.3  410.95  5141.7  411.61  5163.2  418.41  5184.2  416.10  5255.0  419.66
  5417.7  431.44  5502.7  440.71  5552.0  452.14  5608.7  460.39  5646.5  462.47
#Mann=8,-1,0
  4252.4    0.12       0  4307.7     0.1       0  4373.5    0.12       0
  4616.7     0.1       0  4928.7    0.12       0  4993.1    0.07       0
  5001.6    0.12       0  5094.3    0.05       0
Bank Sta=4993.1,5001.6
Exp/Cntr=0.3,0.1

Type RM Length L Ch R = 1,8033,316,316,316
BEGIN DESCRIPTION:
One Mile Creek 18.0
END DESCRIPTION:
XS GIS Cut Line= 3
      2783208.68      6774384.74      2783676.00      6774661.00
      2784269.14      6774833.92
#Sta/Elev= 30
  4457.4  445.83  4474.3  445.25  4614.1  436.92  4738.6  432.73  4790.9  426.92
  4862.6  416.03  4906.7  404.97  4965.2  403.43  4993.1  393.38  4994.3  392.88
  5001.7  393.38  5017.0  396.47  5022.2  404.46  5077.6  405.86  5094.4  409.67
  5127.9  409.30  5200.1  407.21  5228.4  403.76  5233.6  408.30  5239.8  409.35
  5272.3  410.36  5300.5  405.83  5377.9  406.91  5396.1  410.37  5437.8  425.70
  5458.6  427.97  5478.4  435.54  5517.1  445.09  5589.3  458.75  5618.1  460.50
#Mann=8,-1,0
  4457.4    0.12       0  4474.3     0.1       0  4738.6    0.12       0
  4790.9     0.1       0  4862.6    0.12       0  4993.1    0.07       0
  5001.7    0.12       0  5077.6    0.05       0
Bank Sta=4993.1,5001.7
Exp/Cntr=0.3,0.1

Type RM Length L Ch R = 1,7717,535,535,535
BEGIN DESCRIPTION:
One Mile Creek 17.0
END DESCRIPTION:
XS GIS Cut Line= 3
      2783128.86      6774514.35      2783527.58      6774921.69
      2784321.40      6775035.95
#Sta/Elev= 30
  4430.0  444.15  4461.0  439.94  4510.4  439.53  4644.8  433.73  4735.3  434.35
  4765.0  434.05  4807.4  430.42  4849.9  423.74  4885.3  416.19  4963.0  406.17
  4977.2  401.90  4984.3  395.79  4991.7  392.68  4993.0  392.18  5000.3  392.68
  5026.9  402.57  5089.3  403.34  5102.5  408.55  5119.6  408.31  5129.7  405.30
  5184.1  407.17  5384.3  408.93  5483.4  412.72  5520.2  418.58  5564.2  422.31
  5590.6  427.39  5666.1  436.70  5731.5  450.67  5736.6  449.82  5802.0  453.02
#Mann=5,-1,0
  4430.0     0.1       0  4735.3    0.12       0  4991.7    0.07       0
  5000.3    0.12       0  5184.1    0.05       0
Bank Sta=4991.7,5000.3
Exp/Cntr=0.3,0.1

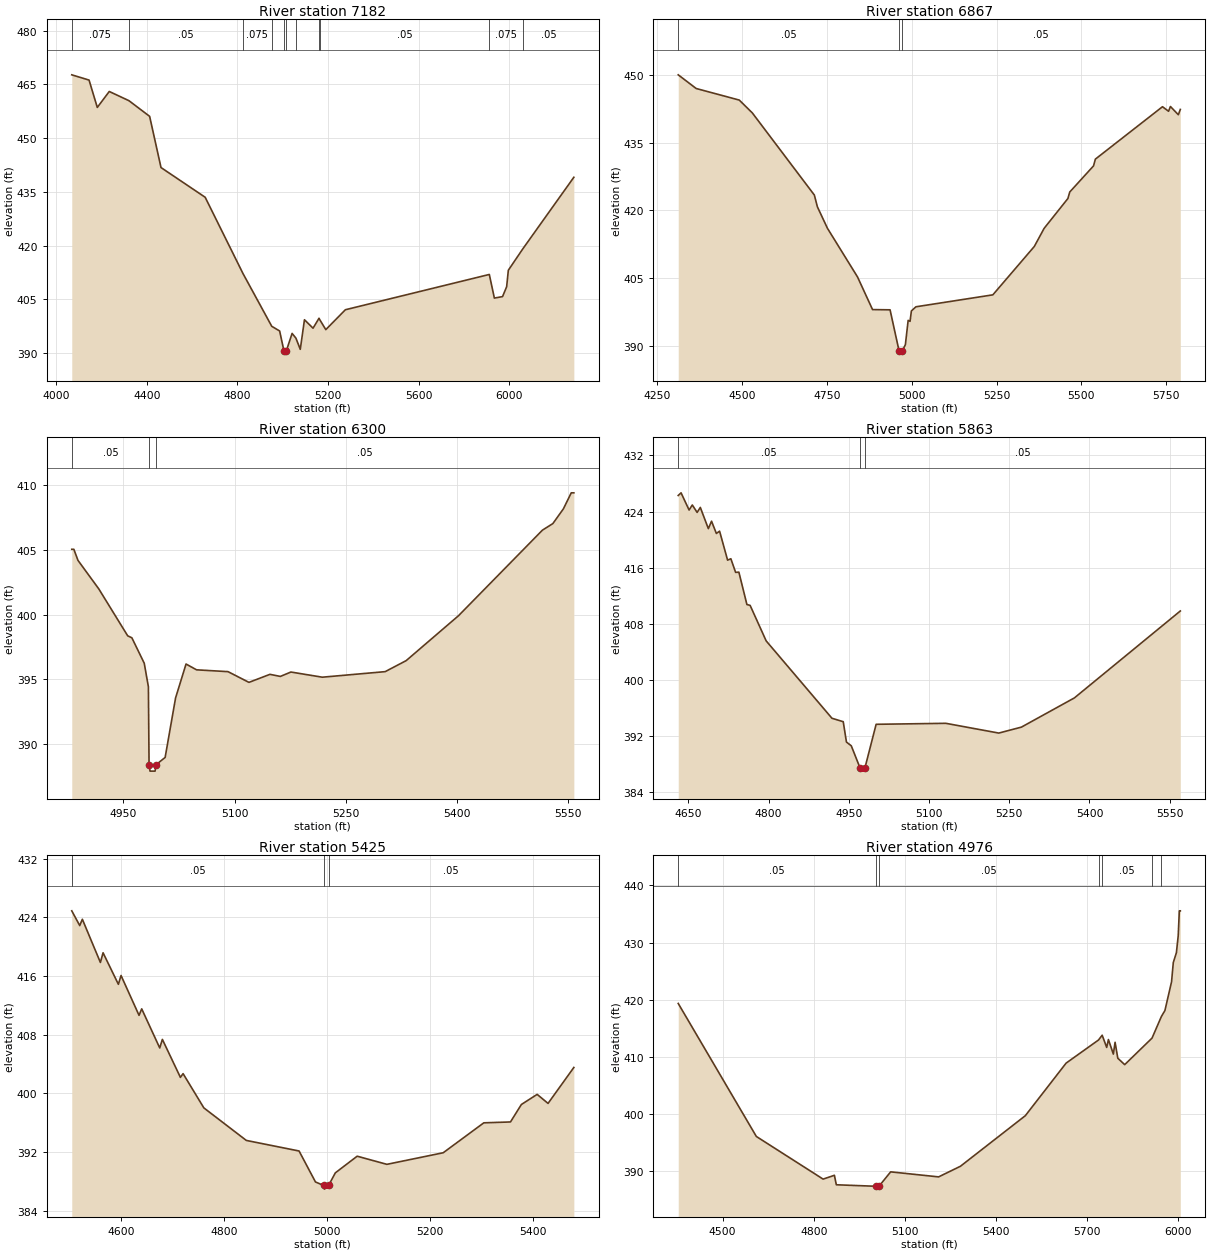
Type RM Length L Ch R = 1,7182,315,315,315
BEGIN DESCRIPTION:
One Mile Creek 16.0
END DESCRIPTION:
XS GIS Cut Line= 3
      2782345.57      6774840.20      2783176.00      6775261.00
      2784385.20      6775692.37
#Sta/Elev= 30
  4069.1  467.66  4145.4  466.19  4181.7  458.56  4234.5  463.01  4321.1  460.45
  4412.6  456.07  4462.8  441.77  4657.6  433.48  4824.2  412.21  4951.3  397.46
  4986.1  396.15  5005.5  390.47  5006.8  389.97  5014.9  390.47  5041.0  395.47
  5057.9  394.16  5077.1  391.03  5095.6  399.29  5133.4  396.93  5159.7  399.70
  5162.6  399.36  5189.7  396.53  5276.1  402.08  5911.0  411.93  5933.3  405.34
  5969.4  405.75  5987.5  408.50  5994.9  413.10  6058.9  419.09  6283.9  439.06
#Mann=11,-1,0
  4069.1   0.075       0  4321.1    0.05       0  4824.2   0.075       0
  4951.3    0.05       0  5005.5    0.05       0  5014.9    0.05       0
  5057.9     0.1       0  5159.7   0.075       0  5162.6    0.05       0
  5911.0   0.075       0  6058.9    0.05       0
Bank Sta=5005.5,5014.9
Exp/Cntr=0.3,0.1

Type RM Length L Ch R = 1,6867,567,567,567
BEGIN DESCRIPTION:
One Mile Creek 15.0
END DESCRIPTION:
XS GIS Cut Line= 3
      2782512.18      6775242.73      2783122.45      6775559.53
      2783846.93      6775878.04
#Sta/Elev= 30
  4312.4  449.97  4365.2  446.95  4492.2  444.39  4530.8  441.54  4713.4  423.40
  4722.3  420.81  4752.0  416.05  4840.5  405.31  4884.8  398.09  4936.4  398.04
  4962.9  388.97  4964.2  388.47  4972.3  388.97  4981.5  390.33  4989.7  395.71
  4995.3  395.49  4999.2  397.80  5012.7  398.71  5239.2  401.35  5361.4  412.05
  5390.2  416.04  5460.3  422.64  5465.7  424.07  5535.8  429.85  5541.2  431.34
  5738.9  442.92  5756.8  441.92  5762.3  442.97  5785.6  441.15  5791.4  442.32
#Mann=3,-1,0
  4312.4    0.05       0  4962.9    0.04       0  4972.3    0.05       0
Bank Sta=4962.9,4972.3
Exp/Cntr=0.3,0.1

Type RM Length L Ch R = 1,6300,437,437,437
BEGIN DESCRIPTION:
One Mile Creek 14.0
END DESCRIPTION:
XS GIS Cut Line= 3
      2782725.99      6775860.99      2782776.00      6775961.00
      2783176.00      6776361.00
#Sta/Elev= 30
  4880.2  405.05  4883.0  405.05  4888.6  404.19  4916.6  401.99  4955.7  398.35
  4961.3  398.20  4978.0  396.23  4983.6  394.41  4984.5  388.38  4985.8  387.88
  4992.6  387.88  4994.0  388.38  5006.2  388.94  5020.3  393.55  5034.4  396.17
  5048.6  395.72  5091.0  395.58  5119.3  394.75  5147.6  395.37  5161.7  395.21
  5175.9  395.55  5218.3  395.15  5303.1  395.58  5331.4  396.43  5402.1  399.91
  5515.3  406.53  5529.4  407.04  5543.6  408.18  5554.2  409.42  5557.7  409.42
#Mann=3,-1,0
  4880.2    0.05       0  4984.5    0.04       0  4994.0    0.05       0
Bank Sta=4984.5,4994
Exp/Cntr=0.3,0.1

Type RM Length L Ch R = 1,5863,438,438,438
BEGIN DESCRIPTION:
One Mile Creek 13.0
END DESCRIPTION:
XS GIS Cut Line= 3
      2782266.13      6776103.37      2782576.00      6776311.00
      2782976.01      6776711.01
#Sta/Elev= 30
  4631.1  426.28  4636.4  426.66  4651.4  424.21  4657.4  424.93  4666.4  423.87
  4672.4  424.58  4687.4  421.56  4693.4  422.62  4702.4  420.87  4708.4  421.20
  4723.4  417.07  4729.5  417.27  4738.4  415.33  4744.5  415.36  4759.5  410.75
  4765.5  410.63  4795.5  405.57  4918.5  394.55  4939.6  394.06  4945.6  391.16
  4954.6  390.63  4970.8  387.52  4972.2  387.02  4980.3  387.52  5001.1  393.69
  5131.4  393.83  5230.4  392.44  5272.8  393.29  5371.8  397.45  5569.8  409.83
#Mann=3,-1,0
  4631.1    0.05       0  4970.8    0.04       0  4980.3    0.05       0
Bank Sta=4970.8,4980.3
Exp/Cntr=0.3,0.1

Type RM Length L Ch R = 1,5425,449,449,449
BEGIN DESCRIPTION:
One Mile Creek 12.0
END DESCRIPTION:
XS GIS Cut Line= 3
      2782196.63      6776172.59      2782326.00      6776661.00
      2782726.04      6776911.02
#Sta/Elev= 30
  4503.4  424.87  4518.9  422.86  4524.0  423.72  4559.1  417.83  4564.3  419.15
  4594.1  414.85  4599.3  416.05  4634.3  410.62  4639.5  411.50  4674.6  406.17
  4679.7  407.34  4714.8  402.16  4720.0  402.67  4760.4  398.00  4843.1  393.56
  4945.7  392.12  4977.6  387.90  4993.5  387.42  4994.9  386.92  5003.1  387.42
  5016.3  389.14  5058.8  391.41  5116.6  390.30  5226.2  391.88  5305.2  395.96
  5357.1  396.08  5378.3  398.46  5409.0  399.84  5430.2  398.61  5480.4  403.51
#Mann=3,-1,0
  4503.4    0.05       0  4993.5    0.04       0  5003.1    0.05       0
Bank Sta=4993.5,5003.1
Exp/Cntr=0.3,0.1

Type RM Length L Ch R = 1,4976,420,420,420
BEGIN DESCRIPTION:
One Mile Creek 11.0
END DESCRIPTION:
XS GIS Cut Line= 3
      2781681.94      6776504.38      2782076.00      6777011.00
      2782967.35      6777489.08
#Sta/Elev= 30
  4353.8  419.37  4611.0  396.11  4830.9  388.65  4868.0  389.32  4874.4  387.66
  5004.1  387.40  5005.5  386.90  5014.8  387.40  5053.3  389.92  5211.2  389.04
  5283.1  390.90  5496.7  399.74  5631.1  408.94  5737.8  412.98  5749.8  413.82
  5764.7  411.68  5770.4  413.06  5786.6  410.52  5792.3  412.58  5801.3  409.79
  5824.0  408.67  5914.0  413.31  5944.8  417.09  5956.4  418.13  5978.3  423.17
  5984.0  426.53  5994.2  428.24  6000.2  431.20  6003.9  435.57  6007.1  435.57
#Mann=7,-1,0
  4353.8    0.05       0  5004.1    0.04       0  5014.8    0.05       0
  5737.8    0.12       0  5749.8    0.05       0  5914.0    0.12       0
  5944.8    0.05       0
Bank Sta=5004.1,5014.8
Exp/Cntr=0.3,0.1