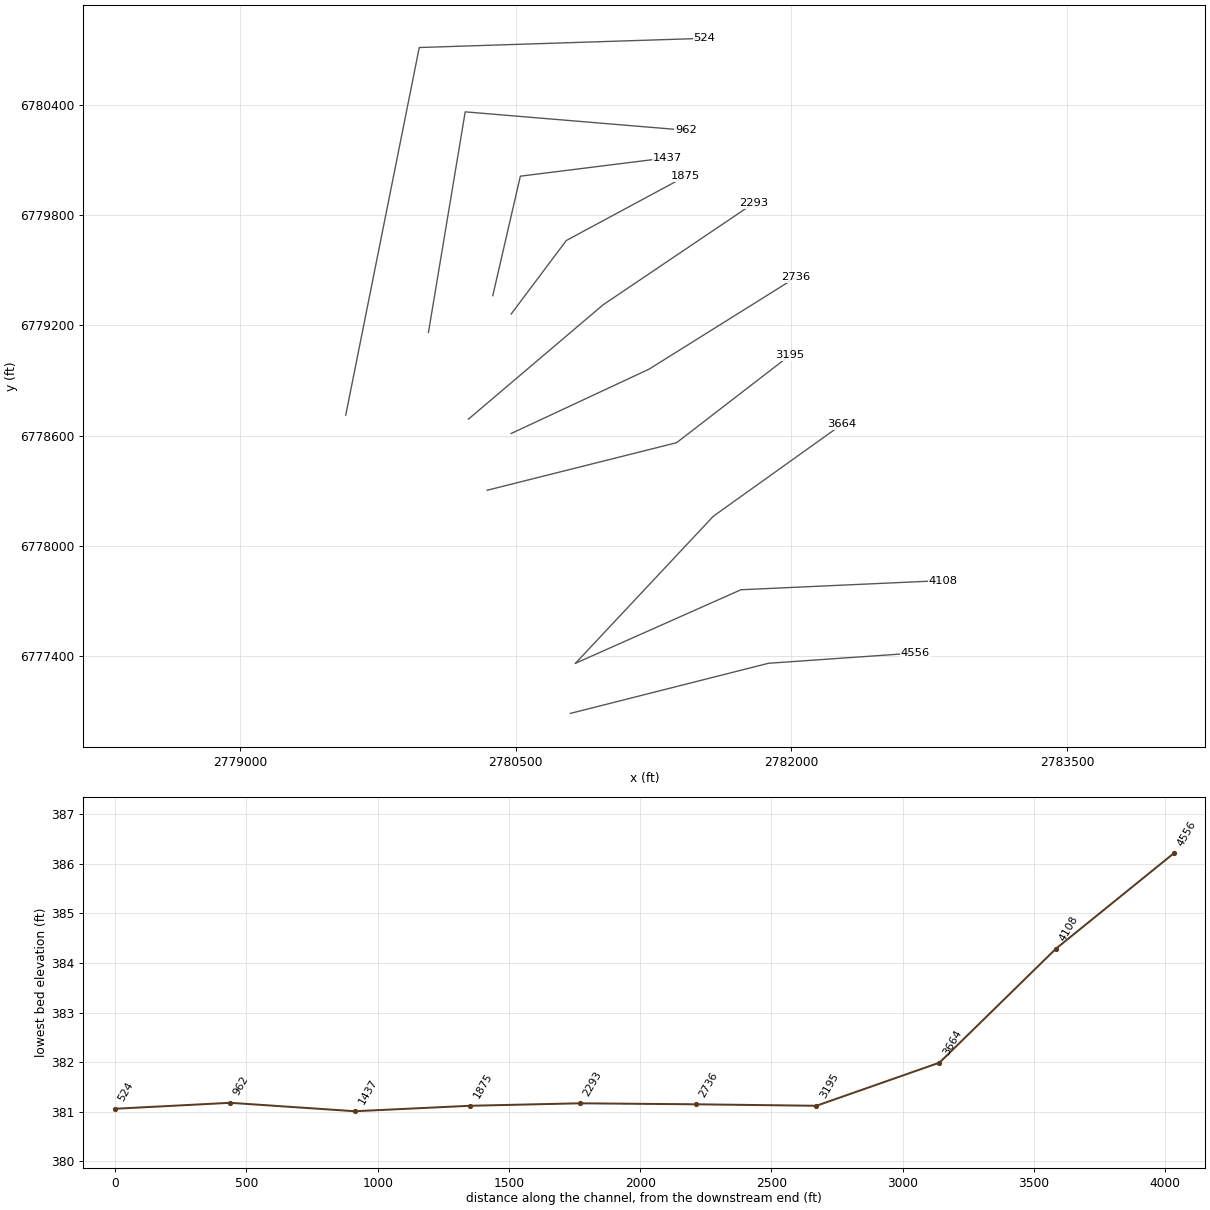
HEC-RAS study One Mile Creek.prj: One Mile Creek Base Level Engineering

--- One Mile Creek.g01 (geometry) --- (continued)

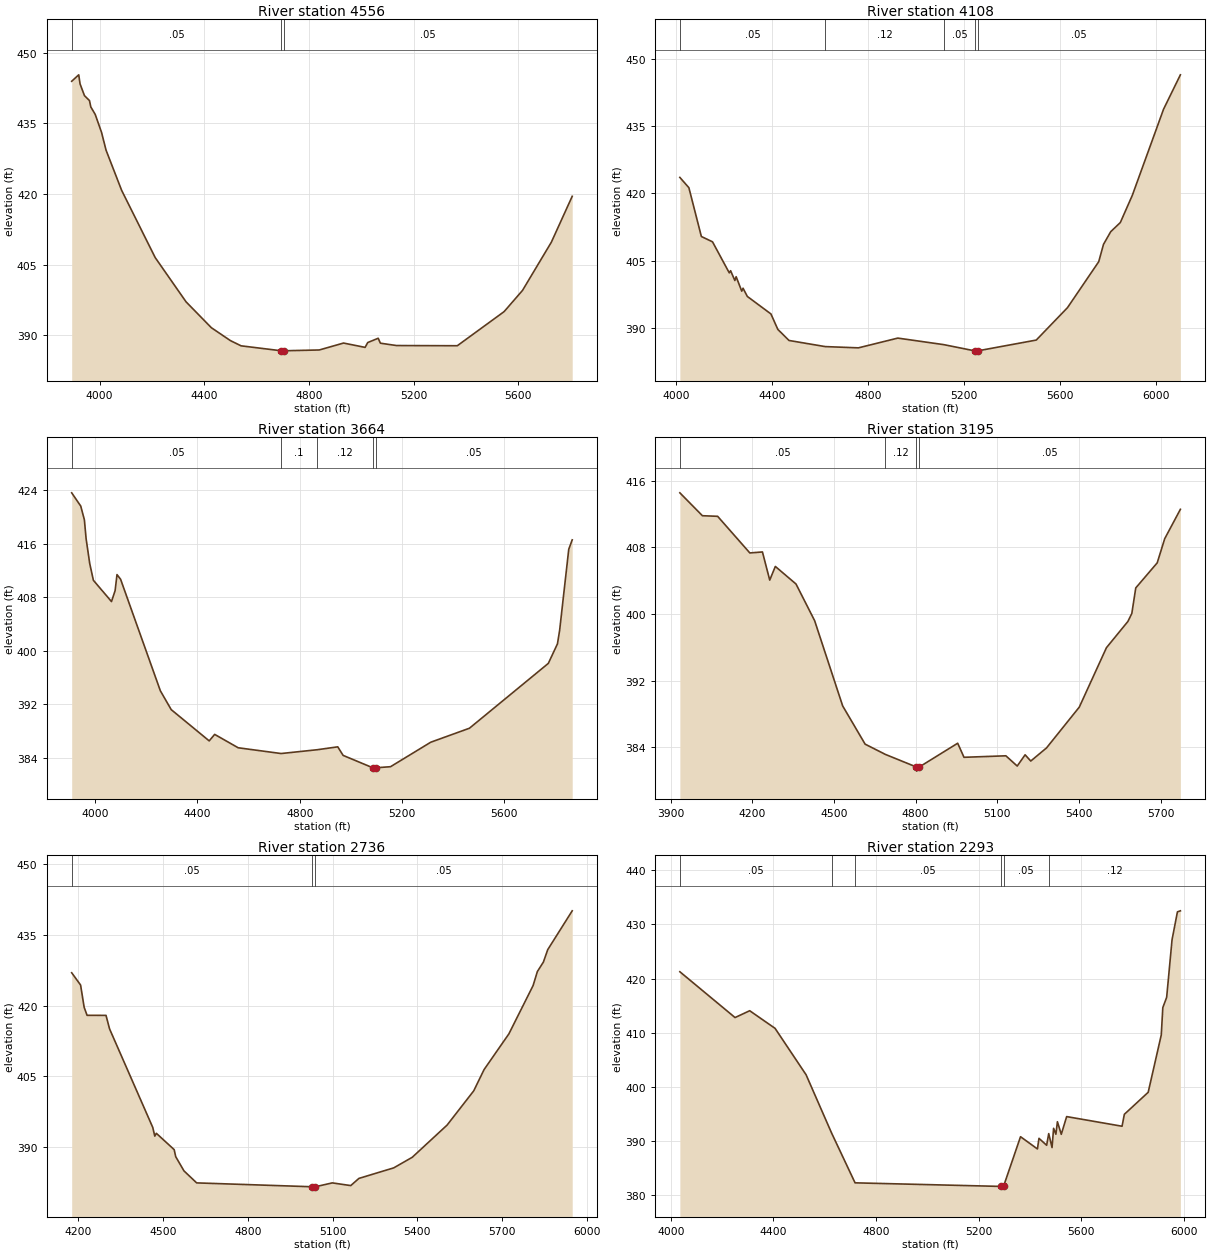
Type RM Length L Ch R = 1,4556,448,448,448
BEGIN DESCRIPTION:
One Mile Creek 10.0
END DESCRIPTION:
XS GIS Cut Line= 3
      2780798.82      6777088.42      2781876.00      6777361.00
      2782675.52      6777416.84
#Sta/Elev= 30
  3893.5  443.97  3920.4  445.34  3925.5  443.41  3942.2  440.93  3961.4  439.87
  3966.6  438.51  3983.4  436.93  4007.6  433.11  4024.7  429.35  4084.4  420.79
  4212.6  406.51  4330.5  397.11  4427.0  391.62  4499.7  388.88  4540.7  387.76
  4694.3  386.71  4695.7  386.21  4705.0  386.71  4839.6  386.88  4932.4  388.35
  5014.7  387.43  5024.7  388.46  5064.8  389.37  5073.1  388.32  5134.9  387.82
  5367.0  387.78  5545.9  395.03  5616.1  399.53  5726.4  409.78  5806.1  419.53
#Mann=3,-1,0
  3893.5    0.05       0  4694.3    0.04       0  4705.0    0.05       0
Bank Sta=4694.3,4705
Exp/Cntr=0.3,0.1

Type RM Length L Ch R = 1,4108,444,444,444
BEGIN DESCRIPTION:
One Mile Creek 9.0
END DESCRIPTION:
XS GIS Cut Line= 3
      2780825.97      6777360.99      2781726.00      6777761.00
      2782826.05      6777811.00
#Sta/Elev= 30
  4015.1  423.58  4052.7  421.28  4104.7  410.37  4151.2  409.18  4221.0  402.24
  4226.5  402.72  4244.3  400.53  4249.7  401.38  4273.0  398.15  4278.5  398.80
  4296.2  396.97  4394.7  393.05  4423.4  389.60  4470.0  387.12  4621.0  385.75
  4759.3  385.47  4923.4  387.65  5114.7  386.19  5244.9  384.79  5246.3  384.29
  5255.7  384.79  5500.5  387.21  5630.7  394.46  5760.8  404.73  5780.8  408.62
  5810.9  411.45  5850.9  413.49  5900.9  419.58  6031.1  438.84  6101.2  446.52
#Mann=5,-1,0
  4015.1    0.05       0  4621.0    0.12       0  5114.7    0.05       0
  5244.9    0.07       0  5255.7    0.05       0
Bank Sta=5244.9,5255.7
Exp/Cntr=0.3,0.1

Type RM Length L Ch R = 1,3664,469,469,469
BEGIN DESCRIPTION:
One Mile Creek 8.0
END DESCRIPTION:
XS GIS Cut Line= 3
      2780825.99      6777360.99      2781576.00      6778161.00
      2782275.98      6778660.98
#Sta/Elev= 30
  3908.5  423.58  3943.9  421.60  3958.1  419.55  3964.9  416.71  3979.1  413.00
  3993.3  410.51  4064.1  407.33  4078.3  408.97  4085.6  411.36  4099.7  410.66
  4255.1  394.00  4297.6  391.18  4446.1  386.51  4467.5  387.48  4559.4  385.48
  4727.2  384.62  4868.9  385.19  4948.7  385.62  4969.7  384.34  5085.7  382.49
  5087.2  381.99  5096.5  382.49  5155.0  382.65  5312.3  386.31  5463.5  388.40
  5771.9  398.09  5807.6  401.01  5816.2  403.05  5851.8  415.15  5865.3  416.55
#Mann=5,-1,0
  3908.5    0.05       0  4727.2     0.1       0  4868.9    0.12       0
  5085.7    0.07       0  5096.5    0.05       0
Bank Sta=5085.7,5096.5
Exp/Cntr=0.3,0.1

Type RM Length L Ch R = 1,3195,459,459,459
BEGIN DESCRIPTION:
One Mile Creek 7.0
END DESCRIPTION:
XS GIS Cut Line= 3
      2780345.63      6778302.38      2781376.00      6778561.00
      2781991.51      6779035.65
#Sta/Elev= 30
  3933.3  414.54  4016.2  411.79  4072.1  411.72  4190.5  407.32  4236.8  407.44
  4263.6  404.06  4284.2  405.70  4360.2  403.59  4428.6  399.19  4531.7  388.95
  4614.2  384.36  4688.5  383.13  4802.3  381.62  4803.8  381.12  4813.4  381.62
  4954.4  384.47  4977.6  382.78  5131.5  382.96  5173.2  381.73  5202.2  383.08
  5223.0  382.33  5281.0  383.91  5401.4  388.81  5501.1  395.94  5579.9  399.09
  5594.4  400.05  5608.9  403.12  5687.7  406.13  5715.4  409.04  5772.9  412.56
#Mann=4,-1,0
  3933.3    0.05       0  4688.5    0.12       0  4802.3    0.03       0
  4813.4    0.05       0
Bank Sta=4802.3,4813.4
Exp/Cntr=0.3,0.1

Type RM Length L Ch R = 1,2736,443,443,443
BEGIN DESCRIPTION:
One Mile Creek 6.0
END DESCRIPTION:
XS GIS Cut Line= 3
      2780476.01      6778611.01      2781226.00      6778961.00
      2782025.97      6779460.98
#Sta/Elev= 30
  4177.1  426.95  4208.6  424.35  4221.2  419.64  4231.5  417.94  4298.5  417.93
  4311.1  415.07  4464.0  394.20  4471.1  392.37  4476.6  392.97  4539.7  389.51
  4545.2  388.02  4574.4  385.01  4619.3  382.47  5028.0  381.65  5029.5  381.15
  5039.3  381.65  5099.1  382.47  5164.5  381.90  5193.4  383.42  5316.6  385.65
  5382.1  387.89  5505.3  394.70  5599.7  401.96  5636.2  406.45  5724.1  414.02
  5809.6  424.23  5824.9  427.22  5846.1  429.21  5861.5  431.84  5948.1  440.06
#Mann=3,-1,0
  4177.1    0.05       0  5028.0    0.03       0  5039.3    0.05       0
Bank Sta=5028,5039.3
Exp/Cntr=0.3,0.1

Type RM Length L Ch R = 1,2293,418,418,418
BEGIN DESCRIPTION:
One Mile Creek 5.0
END DESCRIPTION:
XS GIS Cut Line= 3
      2780243.91      6778689.49      2780976.00      6779311.00
      2781796.87      6779864.90
#Sta/Elev= 30
  4035.2  421.27  4250.3  412.82  4307.4  414.08  4406.2  410.83  4527.1  402.27
  4626.4  391.53  4718.0  382.33  5285.2  381.67  5286.7  381.17  5296.5  381.67
  5362.8  390.84  5428.7  388.58  5434.7  390.54  5464.6  389.26  5472.7  391.41
  5485.6  388.84  5491.7  392.39  5500.6  391.30  5506.6  393.60  5521.6  391.28
  5542.6  394.55  5758.5  392.77  5767.4  394.97  5860.3  399.03  5911.3  409.61
  5917.3  414.65  5932.3  416.55  5953.3  427.18  5974.3  432.32  5985.8  432.51
#Mann=6,-1,0
  4035.2    0.05       0  4626.4    0.12       0  4718.0    0.05       0
  5285.2    0.03       0  5296.5    0.05       0  5472.7    0.12       0
Bank Sta=5285.2,5296.5
Exp/Cntr=0.3,0.1

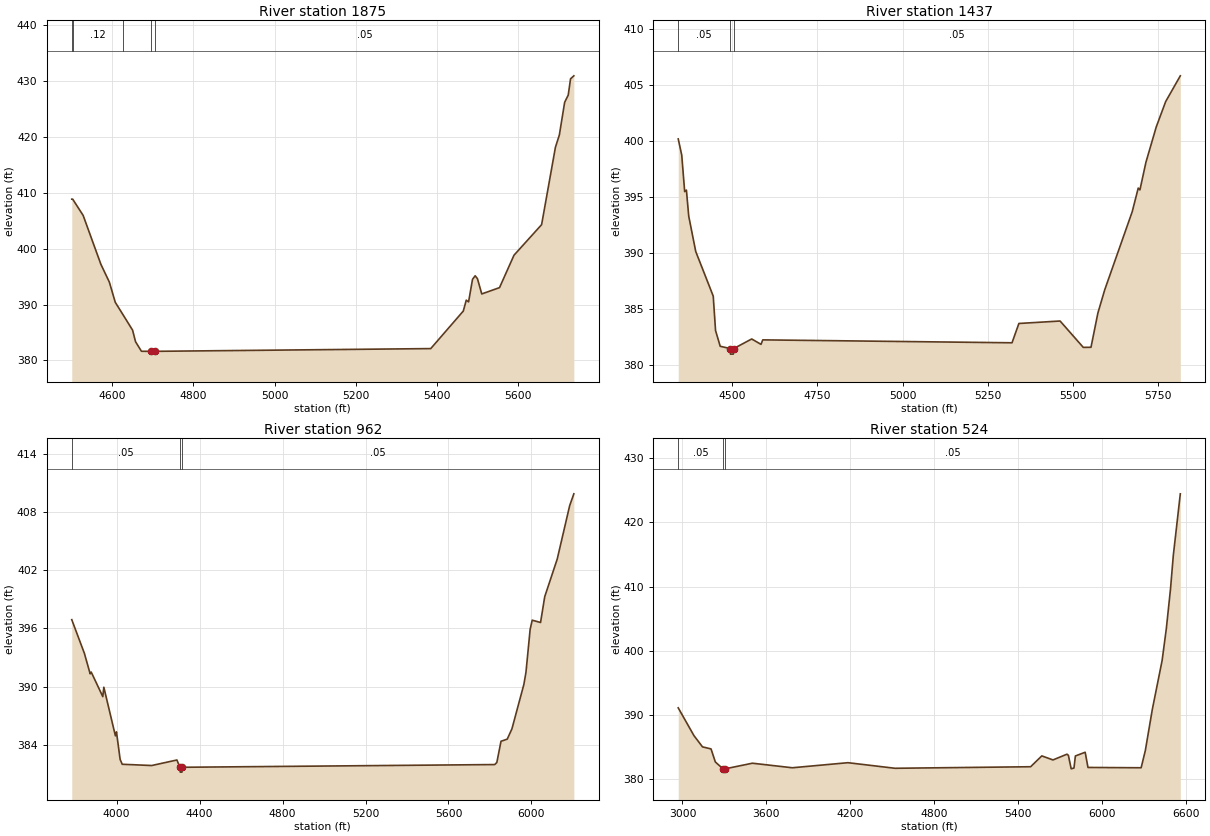
Type RM Length L Ch R = 1,1875,438,438,438
BEGIN DESCRIPTION:
One Mile Creek 4.0
END DESCRIPTION:
XS GIS Cut Line= 3
      2780476.02      6779261.03      2780776.00      6779661.00
      2781426.00      6780011.00
#Sta/Elev= 30
  4499.8  408.85  4502.1  408.85  4527.9  405.94  4571.6  397.20  4592.5  394.01
  4607.1  390.39  4626.8  388.10  4649.8  385.41  4657.1  383.34  4671.6  381.63
  4694.1  381.62  4695.7  381.12  4705.4  381.62  5385.1  382.11  5465.4  388.83
  5472.7  390.78  5478.4  390.47  5488.1  394.50  5494.6  395.14  5500.3  394.62
  5510.9  391.89  5554.7  393.02  5590.4  398.82  5658.5  404.29  5692.6  418.14
  5702.3  420.35  5715.3  426.17  5724.2  427.49  5729.9  430.39  5738.0  430.92
#Mann=5,-1,0
  4499.8    0.05       0  4502.1    0.12       0  4626.8    0.05       0
  4694.1    0.03       0  4705.4    0.05       0
Bank Sta=4694.1,4705.4
Exp/Cntr=0.3,0.1

Type RM Length L Ch R = 1,1437,475,475,475
BEGIN DESCRIPTION:
One Mile Creek 3.0
END DESCRIPTION:
XS GIS Cut Line= 3
      2780375.99      6779360.95      2780526.00      6780011.00
      2781326.04      6780111.01
#Sta/Elev= 30
  4341.7  400.18  4352.0  398.74  4360.6  395.49  4365.7  395.62  4372.5  393.30
  4393.1  390.15  4444.4  386.18  4451.2  383.11  4464.9  381.71  4493.5  381.51
  4495.0  381.01  4503.2  381.01  4504.8  381.51  4557.3  382.36  4584.6  381.88
  4589.8  382.28  5321.2  382.02  5341.4  383.74  5462.3  383.96  5530.4  381.61
  5553.0  381.62  5573.2  384.67  5593.3  386.74  5674.0  393.70  5691.6  395.80
  5696.6  395.64  5714.3  398.11  5744.5  401.25  5772.2  403.51  5815.1  405.80
#Mann=3,-1,0
  4341.7    0.05       0  4493.5    0.03       0  4504.8    0.05       0
Bank Sta=4493.5,4504.8
Exp/Cntr=0.3,0.1

Type RM Length L Ch R = 1,962,438,438,438
BEGIN DESCRIPTION:
One Mile Creek 2.0
END DESCRIPTION:
XS GIS Cut Line= 3
      2780026.00      6779160.98      2780226.00      6780361.00
      2781425.96      6780261.00
#Sta/Elev= 30
  3783.7  396.89  3844.6  393.42  3872.4  391.31  3877.5  391.49  3933.3  388.96
  3938.3  389.93  3994.1  384.92  3999.2  385.33  4016.9  382.49  4027.0  381.99
  4169.0  381.86  4290.6  382.43  4305.2  381.68  4306.8  381.18  4315.0  381.18
  4316.5  381.68  5823.1  381.96  5833.2  382.18  5853.2  384.36  5883.3  384.58
  5905.9  385.64  5963.6  390.23  5973.6  391.48  5993.7  395.89  6003.7  396.84
  6043.9  396.60  6064.0  399.26  6124.2  403.13  6184.4  408.65  6204.4  409.86
#Mann=3,-1,0
  3783.7    0.05       0  4305.2    0.03       0  4316.5    0.05       0
Bank Sta=4305.2,4316.5
Exp/Cntr=0.3,0.1

Type RM Length L Ch R = 1,524,0,0,0
BEGIN DESCRIPTION:
One Mile Creek 1.0
END DESCRIPTION:
XS GIS Cut Line= 3
      2779576.00      6778710.98      2779976.00      6780711.00
      2781525.97      6780761.00
#Sta/Elev= 30
  2969.8  391.08  3082.0  386.76  3143.2  385.00  3204.4  384.68  3235.0  382.65
  3290.5  381.56  3292.1  381.06  3301.8  381.56  3500.1  382.45  3785.7  381.74
  4183.4  382.53  4519.9  381.66  5489.7  381.90  5569.7  383.59  5649.8  382.96
  5749.8  383.86  5759.8  383.68  5779.8  381.58  5799.8  381.70  5809.8  383.58
  5879.9  384.16  5899.9  381.79  6280.1  381.74  6310.1  384.43  6360.1  390.85
  6430.2  398.48  6460.2  403.43  6490.2  409.64  6510.2  414.86  6560.2  424.45
#Mann=3,-1,0
  2969.8    0.05       0  3290.5    0.03       0  3301.8    0.05       0
Bank Sta=3290.5,3301.8
Exp/Cntr=0.3,0.1

Chan Stop Cuts=-1