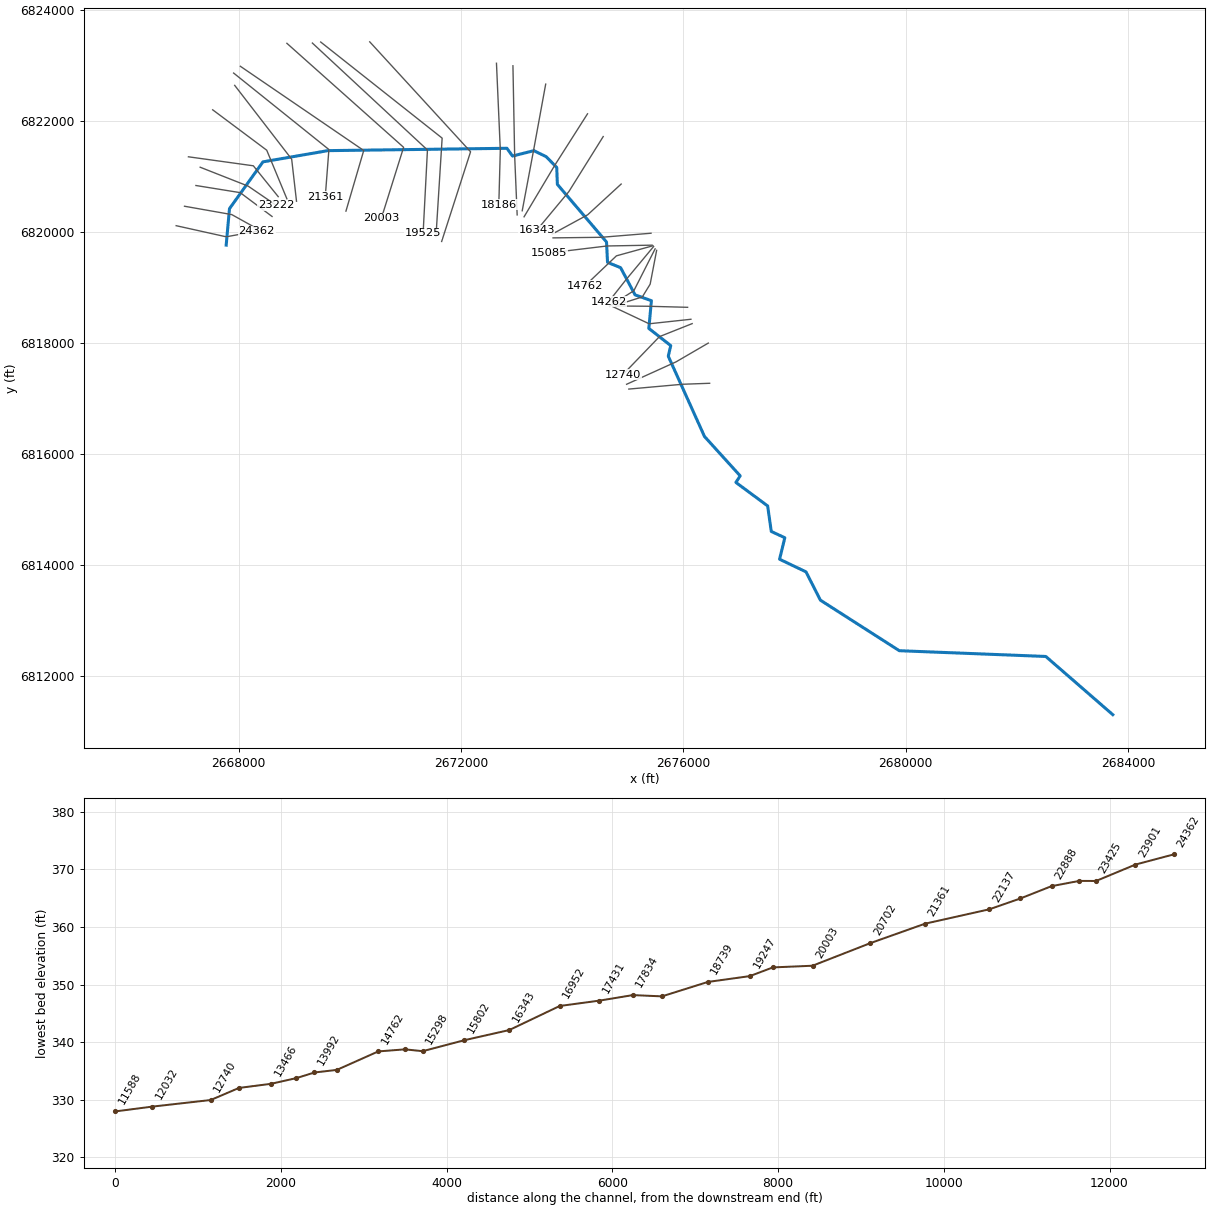
--- Persimmon Branch.prj (project) ---

Proj Title=Persimmon Branch Base Level Engineering
Current Plan=p01
Default Exp/Contr=0.3,0.1
English Units
Geom File=g01
Flow File=f01
Plan File=p01
BEGIN DESCRIPTION:
Persimmon Branch
END DESCRIPTION:

--- Persimmon Branch.p01 (plan) ---

Plan Title=Multiple Run
Short Identifier=Multiple
Geom File=g01
Flow File=f01
Subcritical Flow
K Sum by GR= 0
Std Step Tol= 0.01
Critical Tol= 0.01
Num of Std Step Trials= 20
Max Error Tol= 0.3
Flow Tol Ratio= 0.001
Split Flow NTrial= 30
Split Flow Tol= 0.02
Split Flow Ratio= 0.02
Log Output Level= 0
Friction Slope Method= 1
Unsteady Friction Slope Method= 2
Unsteady Bridges Friction Slope Method= 1
Parabolic Critical Depth
Global Vel Dist=  1 , 1 , 1
Global Log Level= 0
CheckData=True
Encroach Param= -1, 0, 0, 0
BEGIN DESCRIPTION:
Multiple Run
END DESCRIPTION:

--- Persimmon Branch.f01 (steady flow) ---

Flow Title=Multiple
Number of Profiles=7
Profile Names=10-year,25-year,50-year,1pct_min,100-year,1pct_plu,500-year
River Rch & RM= Persimmon Branch,Reach-1,24362
     401     525     621     365     729    1455    1003
River Rch & RM= Persimmon Branch,Reach-1,22512
     666     895    1079     645    1288    2569    1832
River Rch & RM= Persimmon Branch,Reach-1,17431
     974    1334    1630     986    1966    3923    2864
River Rch & RM= Persimmon Branch,Reach-1,13466
    1021    1402    1715    1039    2072    4134    3026
River Rch & RM= Persimmon Branch,Reach-1,12740
    1516    2121    2628    1609    3210    6404    4794
River Rch & RM= Persimmon Branch,Reach-1,9718
    1706    2398    2981    1830    3652    7286    5486
River Rch & RM= Persimmon Branch,Reach-1,7716
    1699    2379    2949    1805    3602    7186    5378
River Rch & RM= Persimmon Branch,Reach-1,4299
    1861    2607    3232    1977    3946    7872    5886
River Rch & RM= Persimmon Branch,Reach-1,3038
    1942    2717    3366    2057    4104    8188    6108
Boundary for River Rch & Prof#=Persimmon Branch,Reach-1,1
Up Type=0
Dn Type=3
Dn Slope=0.005
Boundary for River Rch & Prof#=Persimmon Branch,Reach-1,2
Up Type=0
Dn Type=3
Dn Slope=0.005
Boundary for River Rch & Prof#=Persimmon Branch,Reach-1,3
Up Type=0
Dn Type=3
Dn Slope=0.005
Boundary for River Rch & Prof#=Persimmon Branch,Reach-1,4
Up Type=0
Dn Type=3
Dn Slope=0.005
Boundary for River Rch & Prof#=Persimmon Branch,Reach-1,5
Up Type=0
Dn Type=3
Dn Slope=0.005
Boundary for River Rch & Prof#=Persimmon Branch,Reach-1,6
Up Type=0
Dn Type=3
Dn Slope=0.005
Boundary for River Rch & Prof#=Persimmon Branch,Reach-1,7
Up Type=0
Dn Type=3
Dn Slope=0.005

--- Persimmon Branch.g01 (geometry) ---

Geom Title=Existing Conditions

River Reach=Persimmon Branch,Reach-1
Reach XY= 30
      2667776.00      6819761.00      2667835.41      6820417.62
      2668437.53      6821259.50      2669605.57      6821461.53
      2672826.31      6821503.77      2672927.28      6821364.38
      2673310.59      6821460.98      2673532.06      6821352.86
      2673722.46      6821159.54      2673733.69      6820854.52
      2674618.26      6819817.46      2674636.34      6819450.88
      2674870.96      6819355.92      2675131.44      6818866.25
      2675426.00      6818761.00      2675379.18      6818262.41
      2675773.18      6817953.05      2675729.04      6817762.42
      2676381.26      6816316.47      2677023.05      6815609.00
      2676945.17      6815491.03      2677517.03      6815067.67
      2677581.83      6814608.69      2677825.48      6814495.45
      2677731.30      6814108.46      2678206.37      6813881.68
      2678466.20      6813371.48      2679885.62      6812462.27
      2682520.56      6812358.84      2683726.00      6811311.00

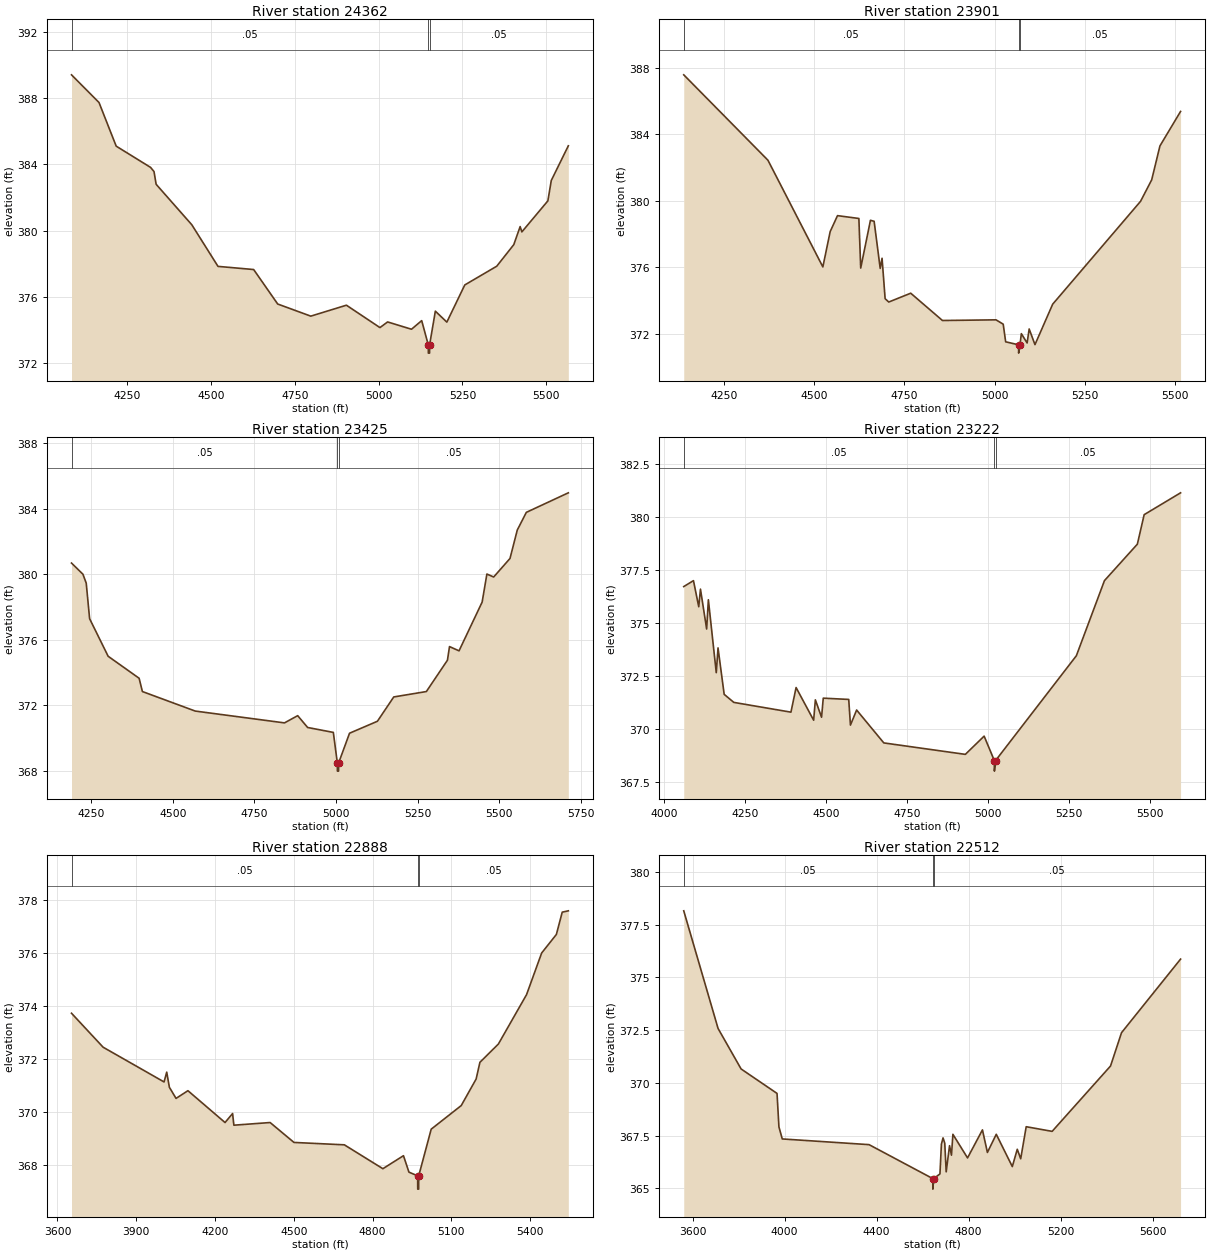
Type RM Length L Ch R = 1,24362,461,461,461
BEGIN DESCRIPTION:
Persimmon Branch 35
END DESCRIPTION:
XS GIS Cut Line= 3
      2666875.98      6820111.01      2667776.00      6819911.00
      2668326.00      6820011.00
#Sta/Elev= 30
  4084.6  389.39  4166.6  387.72  4217.8  385.09  4320.2  383.81  4330.5  383.56
  4336.9  382.79  4443.2  380.35  4521.3  377.84  4627.6  377.65  4699.3  375.57
  4797.9  374.84  4904.1  375.50  5004.0  374.15  5026.9  374.49  5098.1  374.05
  5128.5  374.57  5148.1  373.11  5148.4  372.61  5151.9  372.61  5152.1  373.11
  5169.2  375.14  5203.5  374.48  5256.9  376.72  5352.2  377.85  5403.0  379.15
  5422.0  380.24  5427.1  379.92  5504.6  381.79  5514.8  383.02  5565.6  385.11
#Mann=3,-1,0
  4084.6    0.05       0  5148.1    0.04       0  5152.1    0.05       0
Bank Sta=5148.1,5152.1
Exp/Cntr=0.3,0.1

Type RM Length L Ch R = 1,23901,476,476,476
BEGIN DESCRIPTION:
Persimmon Branch 34
END DESCRIPTION:
XS GIS Cut Line= 3
      2667026.04      6820460.99      2667876.00      6820311.00
      2668326.02      6820060.99
#Sta/Elev= 30
  4138.0  387.57  4371.5  382.44  4523.8  376.03  4544.1  378.15  4564.4  379.11
  4623.7  378.94  4628.8  375.96  4655.8  378.83  4666.0  378.77  4682.9  375.94
  4688.0  376.55  4696.5  374.12  4706.6  373.92  4767.5  374.45  4855.5  372.81
  5004.0  372.85  5024.0  372.59  5030.8  371.53  5066.6  371.35  5066.8  370.85
  5070.6  371.35  5074.3  372.02  5090.3  371.46  5096.0  372.30  5112.1  371.36
  5161.2  373.79  5404.9  379.97  5435.8  381.26  5458.7  383.30  5515.9  385.37
#Mann=3,-1,0
  4138.0    0.05       0  5066.6    0.04       0  5070.6    0.05       0
Bank Sta=5066.6,5070.6
Exp/Cntr=0.3,0.1

Type RM Length L Ch R = 1,23425,203,203,203
BEGIN DESCRIPTION:
Persimmon Branch 349
END DESCRIPTION:
XS GIS Cut Line= 3
      2667231.48      6820834.07      2668027.93      6820705.78
      2668601.30      6820276.81
#Sta/Elev= 30
  4189.3  380.68  4224.3  380.00  4234.4  379.46  4244.8  377.29  4301.6  375.00
  4396.5  373.66  4406.6  372.85  4568.6  371.66  4842.1  370.94  4882.6  371.38
  4913.0  370.66  4991.8  370.36  5004.1  368.50  5004.3  368.00  5007.8  368.00
  5008.1  368.50  5041.5  370.31  5127.0  371.04  5177.0  372.52  5277.0  372.85
  5341.6  374.76  5347.9  375.59  5377.1  375.33  5447.9  378.30  5462.5  380.01
  5483.3  379.83  5533.3  380.96  5555.6  382.69  5583.4  383.77  5712.1  384.96
#Mann=3,-1,0
  4189.3    0.05       0  5004.1    0.04       0  5008.1    0.05       0
Bank Sta=5004.1,5008.1
Exp/Cntr=0.3,0.1

Type RM Length L Ch R = 1,23222,334,334,334
BEGIN DESCRIPTION:
Persimmon Branch 348
END DESCRIPTION:
XS GIS Cut Line= 3
      2667308.12      6821163.03      2668170.91      6820823.15
      2668671.60      6820481.10
#Sta/Elev= 30
  4060.0  376.71  4090.0  376.99  4106.3  375.76  4111.6  376.59  4130.7  374.71
  4136.0  376.09  4160.4  372.65  4165.8  373.82  4184.8  371.63  4214.6  371.25
  4390.9  370.79  4406.8  371.95  4461.0  370.41  4466.3  371.37  4485.4  370.55
  4490.7  371.45  4569.3  371.39  4574.6  370.18  4593.7  370.89  4677.6  369.34
  4929.3  368.80  4987.3  369.66  5018.7  368.51  5019.0  368.01  5022.7  368.51
  5272.0  373.45  5358.7  376.99  5460.3  378.71  5481.3  380.10  5593.7  381.13
#Mann=3,-1,0
  4060.0    0.05       0  5018.7    0.04       0  5022.7    0.05       0
Bank Sta=5018.7,5022.7
Exp/Cntr=0.3,0.1

Type RM Length L Ch R = 1,22888,376,376,376
BEGIN DESCRIPTION:
Persimmon Branch 347
END DESCRIPTION:
XS GIS Cut Line= 3
      2667096.81      6821350.69      2668264.44      6821188.83
      2668711.97      6820633.52
#Sta/Elev= 30
  3653.4  373.73  3773.7  372.45  4005.9  371.14  4016.0  371.51  4026.1  370.94
  4051.5  370.52  4096.8  370.81  4238.1  369.61  4266.8  369.95  4271.8  369.51
  4409.8  369.61  4500.6  368.86  4692.4  368.77  4839.2  367.87  4917.6  368.36
  4938.4  367.74  4971.6  367.60  4971.9  367.10  4975.4  367.10  4975.6  367.60
  5023.2  369.36  5137.6  370.25  5194.3  371.25  5208.7  371.88  5279.1  372.57
  5386.3  374.43  5443.8  376.00  5499.9  376.70  5522.2  377.54  5545.4  377.59
#Mann=3,-1,0
  3653.4    0.05       0  4971.6    0.04       0  4975.6    0.05       0
Bank Sta=4971.6,4975.6
Exp/Cntr=0.3,0.1

Type RM Length L Ch R = 1,22512,375,375,375
BEGIN DESCRIPTION:
Persimmon Branch 346
END DESCRIPTION:
XS GIS Cut Line= 3
      2667532.82      6822196.47      2668505.32      6821469.37
      2668867.77      6820594.97
#Sta/Elev= 30
  3561.1  378.16  3710.4  372.58  3810.5  370.66  3966.8  369.50  3975.1  367.91
  3989.6  367.34  4367.0  367.07  4644.2  365.46  4644.5  364.96  4648.2  365.46
  4675.4  365.68  4681.7  367.09  4688.8  367.39  4696.3  367.14  4702.5  365.78
  4717.1  367.02  4725.5  366.57  4731.7  367.56  4795.4  366.44  4860.2  367.77
  4881.8  366.70  4920.3  367.56  4990.1  366.03  5011.7  366.85  5026.6  366.40
  5050.5  367.92  5163.3  367.70  5417.3  370.80  5465.1  372.38  5721.9  375.87
#Mann=3,-1,0
  3561.1    0.05       0  4644.2    0.04       0  4648.2    0.05       0
Bank Sta=4644.2,4648.2
Exp/Cntr=0.3,0.1

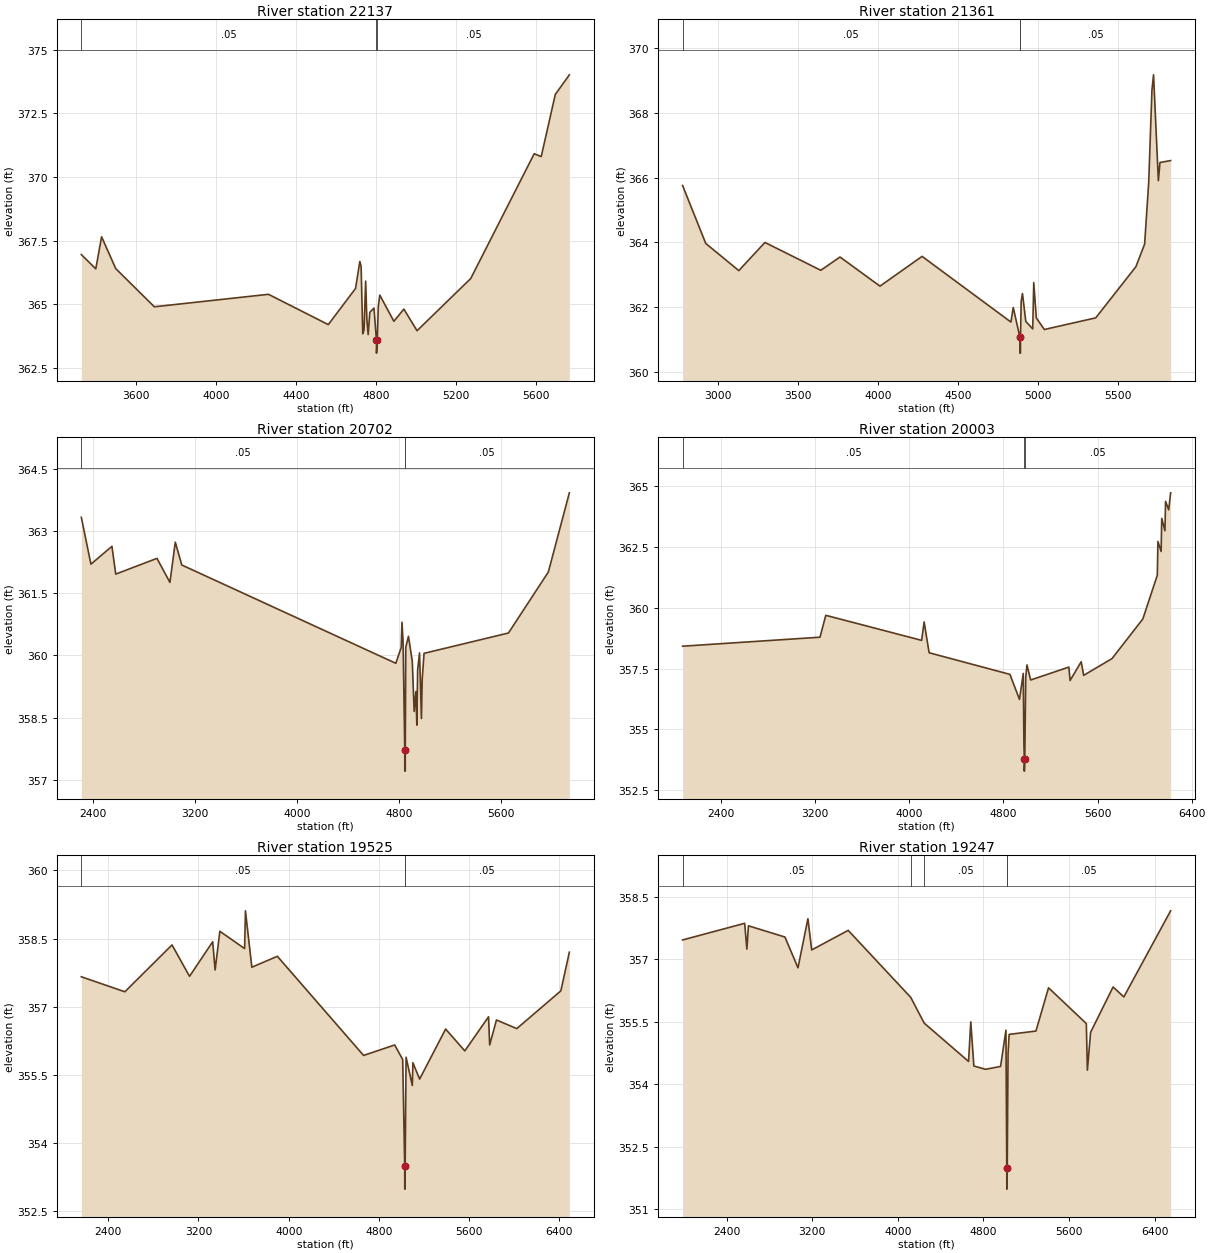
Type RM Length L Ch R = 1,22137,776,776,776
BEGIN DESCRIPTION:
Persimmon Branch 345
END DESCRIPTION:
XS GIS Cut Line= 3
      2667929.00      6822636.19      2668954.16      6821307.62
      2669041.02      6820551.31
#Sta/Elev= 30
  3326.6  366.95  3399.0  366.39  3428.0  367.65  3498.6  366.40  3691.6  364.90
  4262.2  365.39  4561.1  364.20  4697.3  365.62  4718.8  366.68  4725.1  366.49
  4733.3  363.84  4739.6  363.98  4747.8  365.91  4754.0  364.38  4760.5  363.81
  4768.6  364.68  4789.4  364.85  4801.9  363.58  4802.1  363.08  4805.9  363.58
  4811.0  364.90  4818.4  365.36  4889.0  364.33  4938.8  364.81  5004.7  363.96
  5273.1  366.01  5590.3  370.91  5625.4  370.80  5695.8  373.24  5766.0  374.01
#Mann=3,-1,0
  3326.6    0.05       0  4801.9    0.04       0  4805.9    0.05       0
Bank Sta=4801.9,4805.9
Exp/Cntr=0.3,0.1

Type RM Length L Ch R = 1,21361,659,659,659
BEGIN DESCRIPTION:
Persimmon Branch 3420
END DESCRIPTION:
XS GIS Cut Line= 3
      2667909.77      6822857.71      2669623.82      6821481.67
      2669558.48      6820634.74
#Sta/Elev= 30
  2781.7  365.76  2926.3  363.97  3132.7  363.13  3295.9  364.00  3644.7  363.14
  3764.8  363.55  4014.4  362.65  4277.2  363.57  4832.1  361.54  4846.5  361.99
  4887.7  361.08  4887.9  360.58  4891.4  360.58  4891.7  361.08  4896.1  362.19
  4904.1  362.42  4924.9  361.56  4968.1  361.33  4974.5  362.76  4990.5  361.67
  5040.6  361.31  5361.6  361.67  5612.3  363.25  5666.9  363.95  5692.5  365.87
  5712.6  368.71  5722.6  369.18  5752.7  365.91  5762.7  366.47  5829.2  366.53
#Mann=3,-1,0
  2781.7    0.05       0  4887.7    0.04       0  4891.7    0.05       0
Bank Sta=4887.7,4891.7
Exp/Cntr=0.3,0.1

Type RM Length L Ch R = 1,20702,699,699,699
BEGIN DESCRIPTION:
Persimmon Branch 3419
END DESCRIPTION:
XS GIS Cut Line= 3
      2668030.59      6822979.81      2670250.34      6821464.05
      2669930.52      6820372.96
#Sta/Elev= 30
  2309.1  363.33  2384.5  362.20  2549.1  362.63  2578.9  361.96  2902.0  362.34
  3003.6  361.76  3045.6  362.73  3096.4  362.18  4773.8  359.81  4816.2  360.19
  4822.2  360.80  4831.1  360.31  4844.0  357.71  4844.3  357.21  4847.8  357.21
  4848.0  357.71  4852.1  360.20  4873.1  360.46  4902.9  359.86  4917.8  358.65
  4931.2  359.13  4938.8  358.32  4944.9  359.65  4959.8  360.06  4974.7  358.48
  4980.8  359.43  4995.3  360.05  5656.7  360.54  5969.3  362.01  6134.0  363.92
#Mann=3,-1,0
  2309.1    0.05       0  4844.0    0.03       0  4848.0    0.05       0
Bank Sta=4844,4848
Exp/Cntr=0.3,0.1

Type RM Length L Ch R = 1,20003,478,478,478
BEGIN DESCRIPTION:
Persimmon Branch 3421
END DESCRIPTION:
XS GIS Cut Line= 3
      2668868.20      6823392.75      2670967.85      6821521.14
      2670567.95      6820245.48
#Sta/Elev= 30
  2071.5  358.42  3239.8  358.79  3289.1  359.69  4104.3  358.66  4125.2  359.42
  4167.8  358.15  4855.0  357.26  4936.0  356.23  4968.2  357.30  4973.7  354.40
  4977.0  353.78  4977.2  353.28  4981.0  353.78  4989.2  357.14  4999.6  357.65
  5031.1  357.03  5356.0  357.56  5366.4  357.01  5460.8  357.78  5481.7  357.22
  5722.8  357.91  5984.8  359.54  6107.9  361.34  6113.2  362.73  6140.4  362.32
  6145.6  363.68  6172.8  363.17  6178.1  364.38  6204.8  364.03  6221.1  364.73
#Mann=3,-1,0
  2071.5    0.05       0  4977.0    0.03       0  4981.0    0.05       0
Bank Sta=4977,4981
Exp/Cntr=0.3,0.1

Type RM Length L Ch R = 1,19525,278,278,278
BEGIN DESCRIPTION:
Persimmon Branch 3422
END DESCRIPTION:
XS GIS Cut Line= 3
      2669326.66      6823397.46      2671396.60      6821473.29
      2671318.84      6819975.75
#Sta/Elev= 30
  2161.7  357.66  2547.8  357.33  2965.6  358.36  3120.9  357.67  3326.2  358.43
  3347.7  357.81  3389.7  358.66  3609.1  358.28  3616.4  359.11  3673.1  357.87
  3899.3  358.11  4663.5  355.93  4939.5  356.16  5010.2  355.84  5028.2  353.49
  5028.4  352.99  5031.9  352.99  5032.2  353.49  5040.2  355.89  5095.6  355.27
  5100.6  355.77  5160.4  355.41  5390.7  356.51  5560.9  356.03  5771.2  356.78
  5781.2  356.16  5841.3  356.71  6021.5  356.52  6412.0  357.35  6487.4  358.20
#Mann=3,-1,0
  2161.7    0.05       0  5028.2    0.03       0  5032.2    0.05       0
Bank Sta=5028.2,5032.2
Exp/Cntr=0.3,0.1

Type RM Length L Ch R = 1,19247,508,508,508
BEGIN DESCRIPTION:
Persimmon Branch 3423
END DESCRIPTION:
XS GIS Cut Line= 3
      2669476.19      6823416.25      2671660.95      6821686.82
      2671549.58      6819914.43
#Sta/Elev= 30
  1987.6  357.47  2567.8  357.87  2588.6  357.25  2603.1  357.81  2944.4  357.54
  3066.3  356.80  3159.2  357.98  3194.5  357.23  3535.8  357.70  4120.4  356.09
  4246.4  355.47  4660.9  354.55  4681.7  355.50  4710.6  354.44  4819.9  354.36
  4960.2  354.43  5010.3  355.30  5018.3  351.98  5018.6  351.48  5022.3  351.98
  5030.3  354.75  5040.4  355.20  5290.8  355.28  5408.5  356.32  5761.8  355.46
  5771.8  354.34  5801.9  355.25  6012.3  356.34  6112.5  356.10  6549.9  358.17
#Mann=5,-1,0
  1987.6    0.05       0  4120.4    0.12       0  4246.4    0.05       0
  5018.3    0.03       0  5022.3    0.05       0
Bank Sta=5018.3,5022.3
Exp/Cntr=0.3,0.1

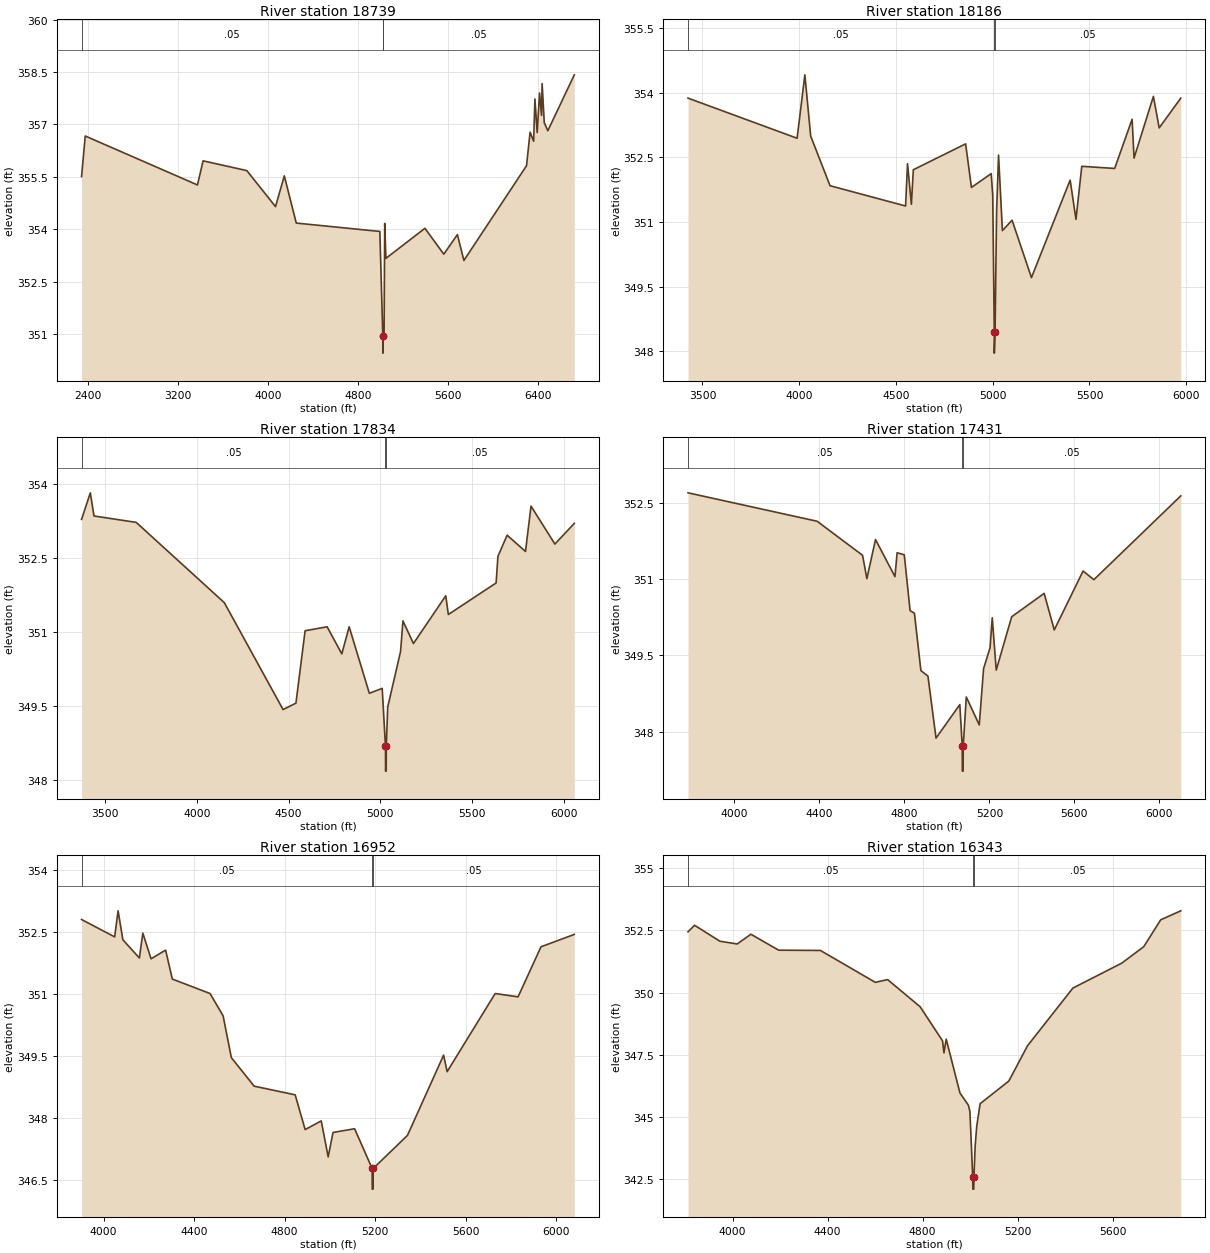
Type RM Length L Ch R = 1,18739,553,553,553
BEGIN DESCRIPTION:
Persimmon Branch 3418
END DESCRIPTION:
XS GIS Cut Line= 3
      2670358.35      6823419.68      2672172.43      6821441.24
      2671652.20      6819826.82
#Sta/Elev= 30
  2342.9  355.51  2375.7  356.67  3373.4  355.27  3423.3  355.96  3812.4  355.68
  4067.1  354.65  4145.4  355.53  4251.5  354.18  4994.5  353.94  5020.8  350.96
  5021.1  350.46  5024.8  350.96  5032.2  350.96  5037.9  354.17  5048.4  353.17
  5395.4  354.03  5563.2  353.29  5684.0  353.85  5741.8  353.11  6298.4  355.82
  6330.2  356.78  6361.7  356.52  6373.0  357.73  6393.2  356.77  6414.2  357.90
  6431.9  357.26  6437.1  358.17  6456.2  357.05  6487.8  356.82  6723.3  358.42
#Mann=3,-1,0
  2342.9    0.05       0  5020.8    0.03       0  5024.8    0.05       0
Bank Sta=5020.8,5024.8
Exp/Cntr=0.3,0.1

Type RM Length L Ch R = 1,18186,352,352,352
BEGIN DESCRIPTION:
Persimmon Branch 337
END DESCRIPTION:
XS GIS Cut Line= 3
      2672638.26      6823034.26      2672707.46      6821472.03
      2672680.29      6820489.57
#Sta/Elev= 30
  3425.4  353.87  3989.2  352.94  4029.3  354.41  4059.3  352.99  4159.4  351.84
  4549.8  351.37  4559.8  352.35  4579.8  351.41  4589.8  352.21  4860.1  352.81
  4890.1  351.80  4992.2  352.12  5000.2  351.62  5008.2  348.46  5008.4  347.96
  5012.2  348.46  5020.2  351.25  5030.2  352.55  5050.2  350.80  5100.2  351.04
  5200.3  349.71  5400.3  351.97  5430.4  351.06  5460.4  352.29  5630.4  352.24
  5720.5  353.38  5730.5  352.48  5830.5  353.91  5860.5  353.18  5972.0  353.87
#Mann=3,-1,0
  3425.4    0.05       0  5008.2    0.03       0  5012.2    0.05       0
Bank Sta=5008.2,5012.2
Exp/Cntr=0.3,0.1

Type RM Length L Ch R = 1,17834,403,403,403
BEGIN DESCRIPTION:
Persimmon Branch 333
END DESCRIPTION:
XS GIS Cut Line= 3
      2672934.67      6822988.75      2672965.34      6821373.72
      2673010.58      6820305.29
#Sta/Elev= 30
  3371.6  353.29  3419.4  353.83  3439.4  353.36  3669.4  353.23  4149.5  351.60
  4469.5  349.43  4539.6  349.56  4589.6  351.03  4709.6  351.11  4789.6  350.56
  4829.6  351.11  4939.6  349.76  5009.7  349.86  5027.5  348.68  5027.9  348.18
  5031.5  348.18  5031.9  348.68  5039.7  349.48  5109.7  350.61  5122.7  351.23
  5179.8  350.77  5356.0  351.74  5370.0  351.36  5630.2  352.00  5640.2  352.54
  5690.3  352.97  5790.4  352.64  5820.4  353.56  5950.5  352.79  6056.3  353.21
#Mann=3,-1,0
  3371.6    0.05       0  5027.5    0.04       0  5031.9    0.05       0
Bank Sta=5027.5,5031.9
Exp/Cntr=0.3,0.1

Type RM Length L Ch R = 1,17431,479,479,479
BEGIN DESCRIPTION:
Persimmon Branch 334
END DESCRIPTION:
XS GIS Cut Line= 3
      2673523.88      6822658.71      2673307.09      6821474.66
      2673101.59      6820379.20
#Sta/Elev= 30
  3782.2  352.70  4389.8  352.14  4603.3  351.47  4623.7  351.01  4664.3  351.78
  4755.8  351.05  4766.0  351.52  4799.6  351.48  4827.0  350.38  4847.3  350.33
  4877.8  349.20  4911.1  349.09  4949.0  347.87  5060.9  348.53  5072.3  347.72
  5072.8  347.22  5076.5  347.22  5077.1  347.72  5091.4  348.68  5152.4  348.13
  5172.8  349.24  5203.3  349.65  5213.5  350.24  5232.3  349.21  5305.1  350.26
  5457.8  350.72  5505.3  350.00  5640.8  351.16  5691.7  350.99  6100.5  352.64
#Mann=3,-1,0
  3782.2    0.05       0  5072.3    0.04       0  5077.1    0.05       0
Bank Sta=5072.3,5077.1
Exp/Cntr=0.3,0.1

Type RM Length L Ch R = 1,16952,609,609,609
BEGIN DESCRIPTION:
Persimmon Branch 335
END DESCRIPTION:
XS GIS Cut Line= 3
      2674276.28      6822124.37      2673696.40      6821212.98
      2673134.84      6820270.88
#Sta/Elev= 30
  3902.8  352.81  4049.0  352.39  4064.2  353.02  4085.4  352.32  4158.2  351.88
  4173.5  352.48  4209.9  351.86  4274.2  352.07  4303.8  351.37  4470.6  351.02
  4528.2  350.48  4564.6  349.47  4665.4  348.78  4846.6  348.57  4890.6  347.73
  4961.7  347.94  4992.4  347.07  5013.8  347.66  5109.2  347.75  5186.6  346.79
  5187.1  346.29  5190.8  346.29  5191.4  346.79  5342.8  347.59  5502.4  349.53
  5518.0  349.13  5730.2  351.02  5831.4  350.94  5932.6  352.15  6079.8  352.45
#Mann=3,-1,0
  3902.8    0.05       0  5186.6    0.04       0  5191.4    0.05       0
Bank Sta=5186.6,5191.4
Exp/Cntr=0.3,0.1

Type RM Length L Ch R = 1,16343,541,541,541
BEGIN DESCRIPTION:
Persimmon Branch 336
END DESCRIPTION:
XS GIS Cut Line= 3
      2674558.56      6821714.89      2673940.73      6820724.75
      2673360.79      6820026.59
#Sta/Elev= 30
  3812.6  352.44  3840.3  352.70  3946.8  352.06  4019.6  351.95  4077.4  352.34
  4194.4  351.70  4370.0  351.69  4601.2  350.41  4653.1  350.52  4789.9  349.43
  4884.3  348.06  4890.2  347.58  4899.7  348.13  4957.5  345.97  4993.0  345.48
  4999.5  345.22  5011.2  342.61  5011.9  342.11  5015.7  342.11  5016.5  342.61
  5021.6  343.84  5028.1  344.63  5042.5  345.54  5163.6  346.45  5241.7  347.86
  5433.1  350.18  5638.8  351.18  5731.3  351.84  5802.9  352.92  5887.3  353.28
#Mann=3,-1,0
  3812.6    0.05       0  5011.2    0.03       0  5016.5    0.05       0
Bank Sta=5011.2,5016.5
Exp/Cntr=0.3,0.1

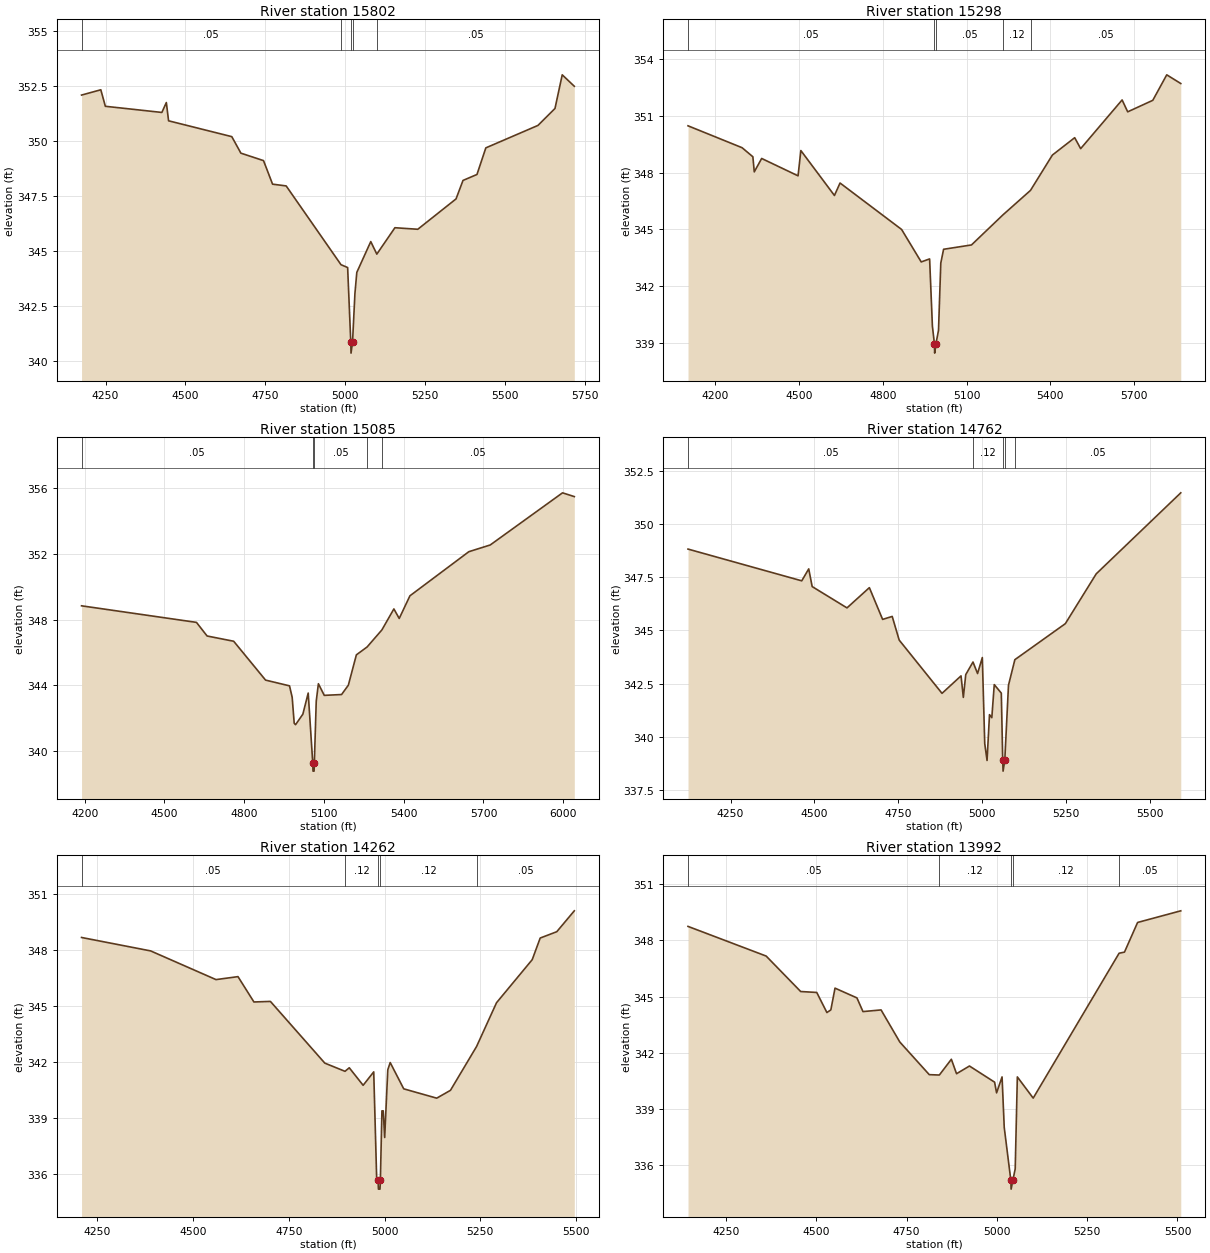
Type RM Length L Ch R = 1,15802,504,504,504
BEGIN DESCRIPTION:
Persimmon Branch 332
END DESCRIPTION:
XS GIS Cut Line= 3
      2674881.44      6820860.41      2674279.06      6820306.98
      2673642.82      6819960.66
#Sta/Elev= 30
  4174.9  352.08  4235.2  352.32  4249.4  351.57  4426.3  351.29  4440.3  351.74
  4447.3  350.91  4645.2  350.19  4673.6  349.44  4744.5  349.10  4772.8  348.03
  4815.4  347.95  4987.0  344.37  5007.8  344.24  5017.6  340.85  5018.4  340.35
  5023.1  340.85  5030.6  343.06  5036.5  344.02  5080.2  345.42  5099.1  344.85
  5155.8  346.05  5227.4  345.98  5347.1  347.36  5368.9  348.20  5412.6  348.47
  5440.4  349.68  5603.5  350.70  5656.8  351.47  5679.5  353.00  5717.3  352.48
#Mann=5,-1,0
  4174.9    0.05       0  4987.0    0.12       0  5017.6    0.07       0
  5023.1    0.12       0  5099.1    0.05       0
Bank Sta=5017.6,5023.1
Exp/Cntr=0.3,0.1

Type RM Length L Ch R = 1,15298,213,213,213
BEGIN DESCRIPTION:
Persimmon Branch 331
END DESCRIPTION:
XS GIS Cut Line= 3
      2675419.16      6819975.31      2674527.31      6819902.12
      2673655.72      6819891.64
#Sta/Elev= 30
  4101.5  350.48  4295.3  349.32  4334.0  348.84  4339.0  348.04  4365.5  348.75
  4496.0  347.83  4506.0  349.17  4626.4  346.79  4646.5  347.45  4867.2  344.99
  4937.5  343.27  4967.6  343.43  4977.6  339.87  4984.8  338.94  4985.7  338.44
  4990.4  338.94  4999.5  339.65  5007.7  343.21  5017.7  343.94  5117.7  344.17
  5230.3  345.76  5329.3  347.06  5407.7  348.93  5487.7  349.85  5509.1  349.27
  5657.7  351.85  5677.7  351.22  5767.7  351.83  5817.7  353.18  5868.0  352.72
#Mann=5,-1,0
  4101.5    0.05       0  4984.8    0.03       0  4990.4    0.05       0
  5230.3    0.12       0  5329.3    0.05       0
Bank Sta=4984.8,4990.4
Exp/Cntr=0.3,0.1

Type RM Length L Ch R = 1,15085,323,323,323
BEGIN DESCRIPTION:
Persimmon Branch 330
END DESCRIPTION:
XS GIS Cut Line= 3
      2675438.22      6819760.69      2674626.78      6819745.84
      2673592.00      6819621.47
#Sta/Elev= 30
  4188.0  348.84  4620.3  347.83  4660.3  347.00  4760.3  346.68  4880.3  344.31
  4970.4  343.96  4980.4  343.26  4988.0  341.68  4993.0  341.59  5020.5  342.23
  5040.7  343.52  5057.8  339.26  5058.8  338.76  5062.8  338.76  5063.8  339.26
  5070.9  343.02  5079.0  344.09  5101.1  343.38  5166.2  343.43  5191.7  344.00
  5221.9  345.85  5262.2  346.33  5317.9  347.37  5363.0  348.65  5383.1  348.07
  5423.4  349.45  5645.0  352.14  5725.5  352.55  5997.5  355.73  6041.8  355.50
#Mann=5,-1,0
  4188.0    0.05       0  5057.8    0.03       0  5063.8    0.05       0
  5262.2    0.12       0  5317.9    0.05       0
Bank Sta=5057.8,5063.8
Exp/Cntr=0.3,0.1

Type RM Length L Ch R = 1,14762,500,500,500
BEGIN DESCRIPTION:
Persimmon Branch 329
END DESCRIPTION:
XS GIS Cut Line= 3
      2675452.89      6819749.70      2674796.35      6819568.45
      2674225.58      6819025.01
#Sta/Elev= 30
  4123.1  348.82  4462.2  347.33  4483.0  347.89  4493.3  347.06  4597.1  346.06
  4663.8  347.01  4703.3  345.52  4731.9  345.66  4752.7  344.55  4880.4  342.05
  4937.1  342.87  4944.0  341.86  4951.2  342.93  4972.8  343.52  4986.4  342.98
  5000.6  343.73  5007.8  339.69  5014.7  338.90  5022.0  341.05  5028.9  340.91
  5036.2  342.46  5057.2  342.06  5061.4  338.90  5062.5  338.40  5067.5  338.90
  5078.6  342.43  5097.6  343.63  5248.1  345.32  5340.3  347.66  5592.3  351.46
#Mann=5,-1,0
  4123.1    0.05       0  4972.8    0.12       0  5061.4    0.07       0
  5067.5    0.12       0  5097.6    0.05       0
Bank Sta=5061.4,5067.5
Exp/Cntr=0.3,0.1

Type RM Length L Ch R = 1,14262,270,270,270
BEGIN DESCRIPTION:
Persimmon Branch 328
END DESCRIPTION:
XS GIS Cut Line= 3
      2675465.18      6819735.82      2674961.99      6819130.67
      2674653.48      6818739.13
#Sta/Elev= 30
  4209.6  348.69  4389.8  347.97  4560.4  346.43  4617.7  346.59  4659.3  345.23
  4702.3  345.26  4844.2  341.95  4896.9  341.51  4908.0  341.70  4944.2  340.76
  4971.8  341.48  4979.6  335.69  4983.1  335.69  4984.1  335.19  4988.2  335.19
  4989.2  335.69  4993.2  339.39  4996.6  339.39  5000.4  337.96  5008.5  341.59
  5014.8  341.98  5050.1  340.57  5136.2  340.07  5172.0  340.49  5240.1  342.84
  5292.2  345.19  5385.3  347.50  5406.1  348.66  5449.4  349.00  5495.1  350.12
#Mann=5,-1,0
  4209.6    0.05       0  4896.9    0.12       0  4983.1    0.07       0
  4989.2    0.12       0  5240.1    0.05       0
Bank Sta=4983.1,4989.2
Exp/Cntr=0.3,0.1

Type RM Length L Ch R = 1,13992,217,217,217
BEGIN DESCRIPTION:
Persimmon Branch 327
END DESCRIPTION:
XS GIS Cut Line= 3
      2675492.47      6819693.92      2675110.22      6818941.50
      2674672.02      6818660.33
#Sta/Elev= 30
  4144.5  348.74  4360.9  347.16  4456.5  345.27  4501.0  345.22  4529.1  344.15
  4540.0  344.29  4551.6  345.45  4612.3  344.93  4629.0  344.20  4679.1  344.29
  4731.0  342.58  4812.6  340.84  4840.5  340.82  4873.8  341.66  4888.1  340.89
  4923.9  341.30  4993.5  340.44  4999.0  339.87  5014.2  340.72  5020.2  338.03
  5038.3  335.24  5039.3  334.74  5044.4  335.24  5050.6  335.82  5056.5  340.72
  5100.4  339.59  5338.3  347.31  5353.2  347.37  5389.5  348.95  5509.1  349.57
#Mann=5,-1,0
  4144.5    0.05       0  4840.5    0.12       0  5038.3    0.07       0
  5044.4    0.12       0  5338.3    0.05       0
Bank Sta=5038.3,5044.4
Exp/Cntr=0.3,0.1

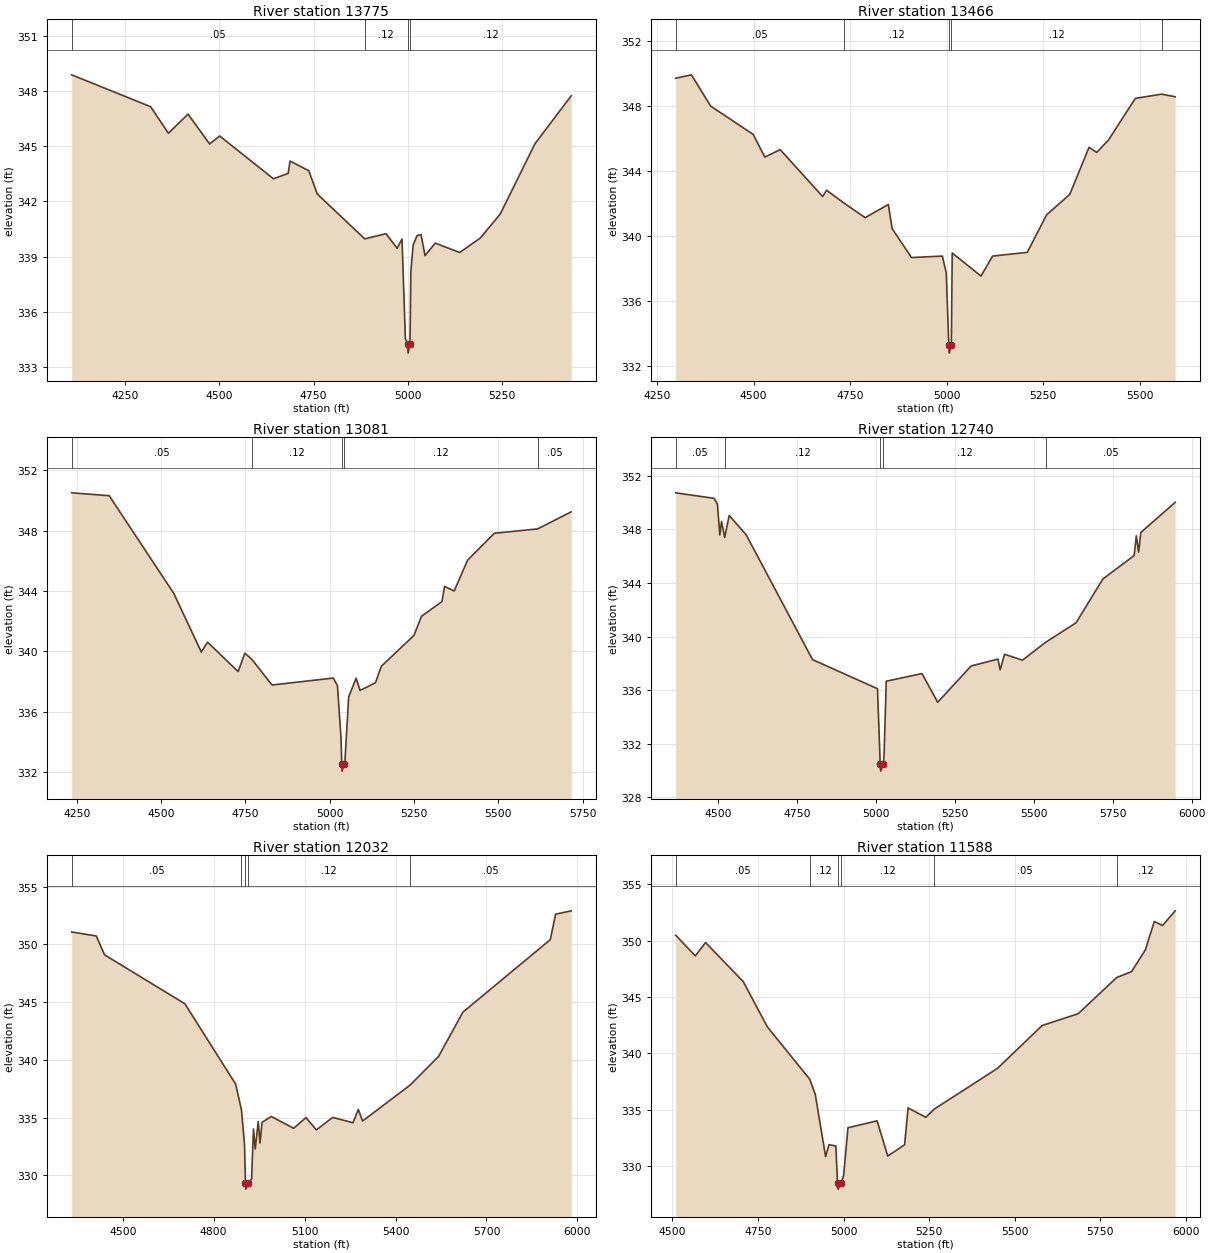
Type RM Length L Ch R = 1,13775,309,309,309
BEGIN DESCRIPTION:
Persimmon Branch 319
END DESCRIPTION:
XS GIS Cut Line= 4
      2675519.52      6819666.28      2675403.08      6819058.23
      2675261.58      6818828.79      2674846.53      6818698.09
#Sta/Elev= 30
  4108.7  348.87  4318.1  347.14  4365.1  345.70  4417.1  346.74  4474.3  345.12
  4501.0  345.55  4643.5  343.23  4682.4  343.52  4687.5  344.19  4737.0  343.67
  4759.8  342.40  4885.4  339.97  4941.6  340.25  4971.3  339.46  4984.2  339.96
  4993.1  334.56  4999.3  334.27  5000.3  333.77  5005.4  334.27  5007.6  338.20
  5013.7  339.64  5024.2  340.15  5034.7  340.20  5045.2  339.06  5072.3  339.74
  5137.0  339.23  5191.9  340.02  5244.6  341.32  5336.5  345.13  5432.5  347.73
#Mann=4,-1,0
  4108.7    0.05       0  4885.4    0.12       0  4999.3    0.07       0
  5005.4    0.12       0
Bank Sta=4999.3,5005.4
Exp/Cntr=0.3,0.1

Type RM Length L Ch R = 1,13466,385,385,385
BEGIN DESCRIPTION:
Persimmon Branch 236
END DESCRIPTION:
XS GIS Cut Line= 3
      2676076.91      6818642.14      2675359.85      6818661.14
      2674782.78      6818665.88
#Sta/Elev= 30
  4298.0  349.71  4338.9  349.92  4388.9  347.99  4499.0  346.25  4529.0  344.85
  4569.0  345.31  4679.0  342.42  4689.0  342.81  4734.1  342.02  4789.1  341.12
  4849.1  341.93  4859.1  340.44  4909.1  338.66  4989.2  338.75  4999.2  337.71
  5005.9  333.27  5007.0  332.77  5012.4  333.27  5014.7  338.94  5089.2  337.52
  5119.2  338.75  5209.2  338.98  5259.2  341.29  5319.2  342.55  5369.2  345.45
  5389.2  345.14  5419.2  345.89  5489.2  348.47  5557.3  348.73  5592.4  348.57
#Mann=5,-1,0
  4298.0    0.05       0  4734.1    0.12       0  5005.9    0.07       0
  5012.4    0.12       0  5557.3    0.05       0
Bank Sta=5005.9,5012.4
Exp/Cntr=0.3,0.1

Type RM Length L Ch R = 1,13081,341,341,341
BEGIN DESCRIPTION:
Persimmon Branch 235
END DESCRIPTION:
XS GIS Cut Line= 3
      2676136.64      6818426.97      2675385.10      6818345.65
      2674729.47      6818655.28
#Sta/Elev= 30
  4235.0  350.51  4346.3  350.32  4537.4  343.86  4619.4  339.96  4638.0  340.61
  4728.5  338.66  4748.6  339.88  4769.3  339.47  4829.1  337.77  5010.8  338.23
  5023.1  337.72  5033.6  334.26  5035.9  332.56  5036.9  332.06  5042.4  332.56
  5045.2  332.73  5056.3  336.98  5078.4  338.22  5090.2  337.41  5135.7  337.92
  5153.0  339.01  5249.6  341.05  5272.4  342.33  5332.8  343.30  5340.7  344.31
  5369.0  344.00  5409.0  346.05  5488.3  347.83  5616.8  348.12  5716.0  349.25
#Mann=5,-1,0
  4235.0    0.05       0  4769.3    0.12       0  5035.9    0.07       0
  5042.4    0.12       0  5616.8    0.05       0
Bank Sta=5035.9,5042.4
Exp/Cntr=0.3,0.1

Type RM Length L Ch R = 1,12740,708,708,708
BEGIN DESCRIPTION:
Persimmon Branch 232
END DESCRIPTION:
XS GIS Cut Line= 3
      2676158.95      6818348.66      2675570.21      6818114.17
      2674911.85      6817431.40
#Sta/Elev= 30
  4365.7  350.73  4487.3  350.32  4498.0  349.89  4505.7  347.58  4511.1  348.59
  4521.1  347.40  4535.4  349.04  4589.3  347.59  4799.4  338.28  5005.1  336.11
  5013.7  330.46  5015.1  329.96  5023.6  330.46  5025.9  331.20  5032.8  336.67
  5146.0  337.24  5195.7  335.10  5301.7  337.81  5386.6  338.32  5393.5  337.52
  5407.6  338.68  5464.2  338.24  5537.3  339.57  5634.0  341.03  5718.9  344.30
  5818.0  346.05  5824.9  347.52  5832.1  346.31  5839.1  347.77  5947.9  350.02
#Mann=5,-1,0
  4365.7    0.05       0  4521.1    0.12       0  5013.7    0.07       0
  5023.6    0.12       0  5537.3    0.05       0
Bank Sta=5013.7,5023.6
Exp/Cntr=0.3,0.1

Type RM Length L Ch R = 1,12032,444,444,444
BEGIN DESCRIPTION:
Persimmon Branch 234
END DESCRIPTION:
XS GIS Cut Line= 3
      2676448.88      6817998.28      2675868.23      6817660.03
      2674979.21      6817257.00
#Sta/Elev= 30
  4331.4  351.08  4412.7  350.73  4440.0  349.10  4705.1  344.86  4872.6  337.90
  4891.7  335.66  4901.8  332.70  4904.8  329.31  4906.2  328.81  4914.8  329.31
  4925.0  329.68  4931.3  334.02  4937.1  332.29  4947.1  334.67  4952.8  332.80
  4959.7  334.60  4990.1  335.10  5063.9  334.08  5104.6  335.00  5138.7  333.94
  5192.5  335.02  5259.6  334.56  5277.2  335.71  5291.3  334.71  5448.1  337.82
  5542.2  340.31  5622.4  344.14  5910.5  350.41  5928.1  352.62  5979.5  352.91
#Mann=5,-1,0
  4331.4    0.05       0  4891.7    0.12       0  4904.8    0.07       0
  4914.8    0.12       0  5448.1    0.05       0
Bank Sta=4904.8,4914.8
Exp/Cntr=0.3,0.1

Type RM Length L Ch R = 1,11588,262,262,262
BEGIN DESCRIPTION:
Persimmon Branch 233
END DESCRIPTION:
XS GIS Cut Line= 3
      2676473.48      6817274.94      2675985.79      6817257.38
      2675019.29      6817170.63
#Sta/Elev= 30
  4509.9  350.48  4567.4  348.65  4597.4  349.83  4707.5  346.36  4777.6  342.36
  4901.4  337.72  4917.6  336.37  4947.7  330.87  4957.7  331.92  4977.7  331.80
  4982.6  328.48  4984.0  327.98  4992.8  328.48  5000.3  329.18  5013.0  333.42
  5098.1  334.03  5129.2  330.91  5178.4  331.91  5188.5  335.18  5240.3  334.34
  5263.9  335.05  5449.5  338.68  5580.0  342.48  5685.0  343.52  5797.6  346.73
  5841.1  347.26  5881.2  349.18  5907.3  351.69  5931.4  351.34  5968.3  352.64
#Mann=6,-1,0
  4509.9    0.05       0  4901.4    0.12       0  4982.6    0.07       0
  4992.8    0.12       0  5263.9    0.05       0  5797.6    0.12       0
Bank Sta=4982.6,4992.8
Exp/Cntr=0.3,0.1