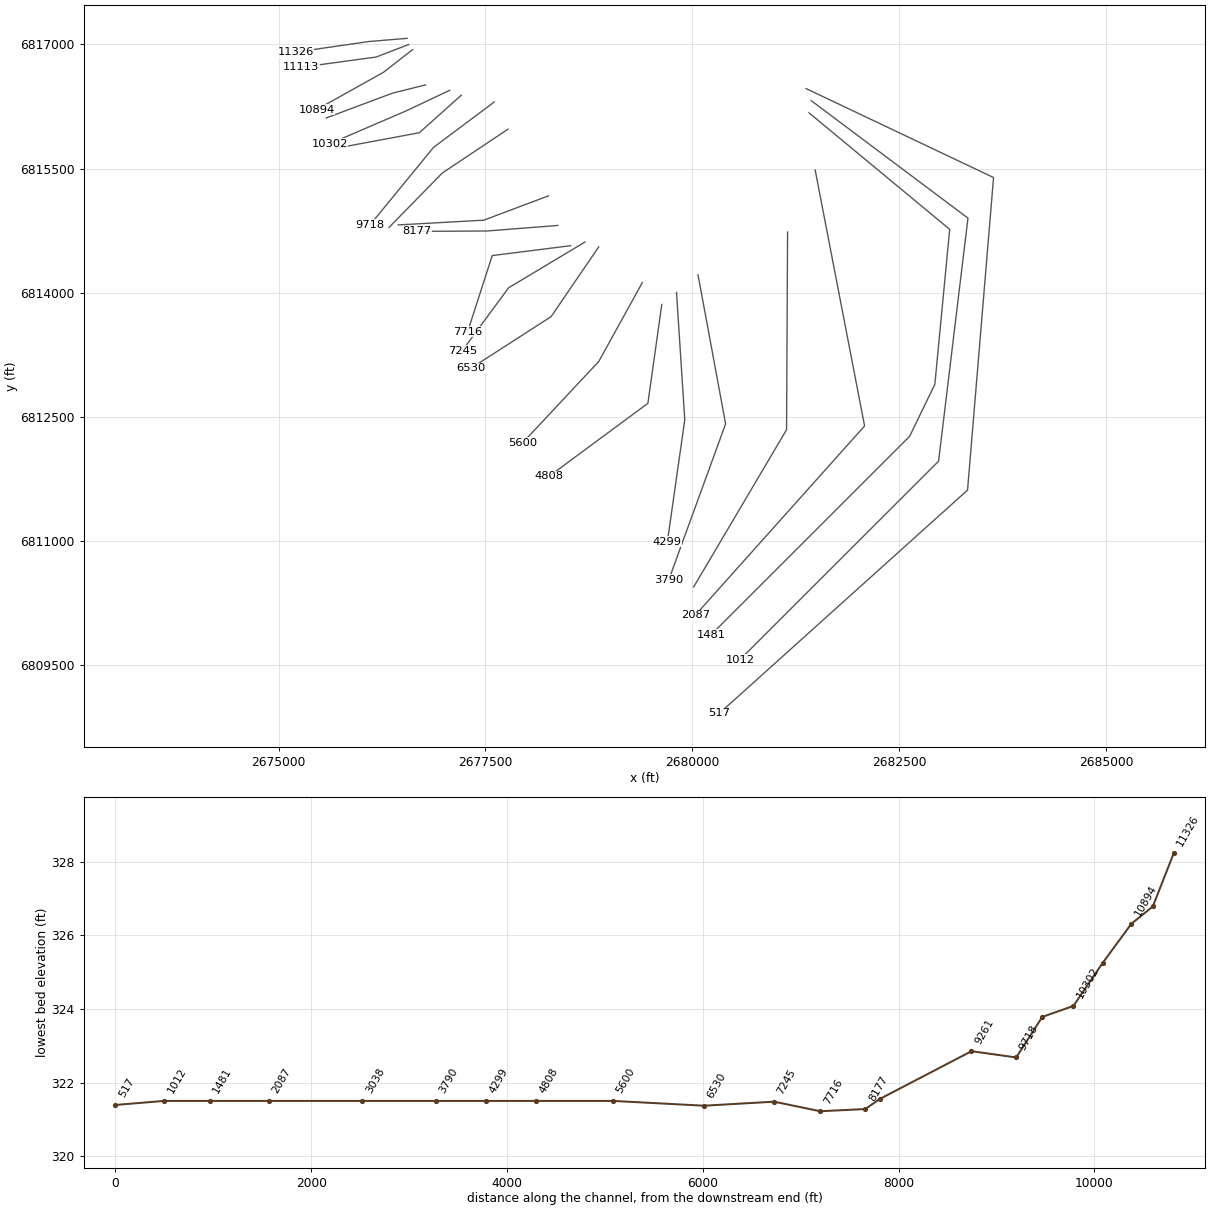
HEC-RAS study Persimmon Branch.prj: Persimmon Branch Base Level Engineering

--- Persimmon Branch.g01 (geometry) --- (continued)

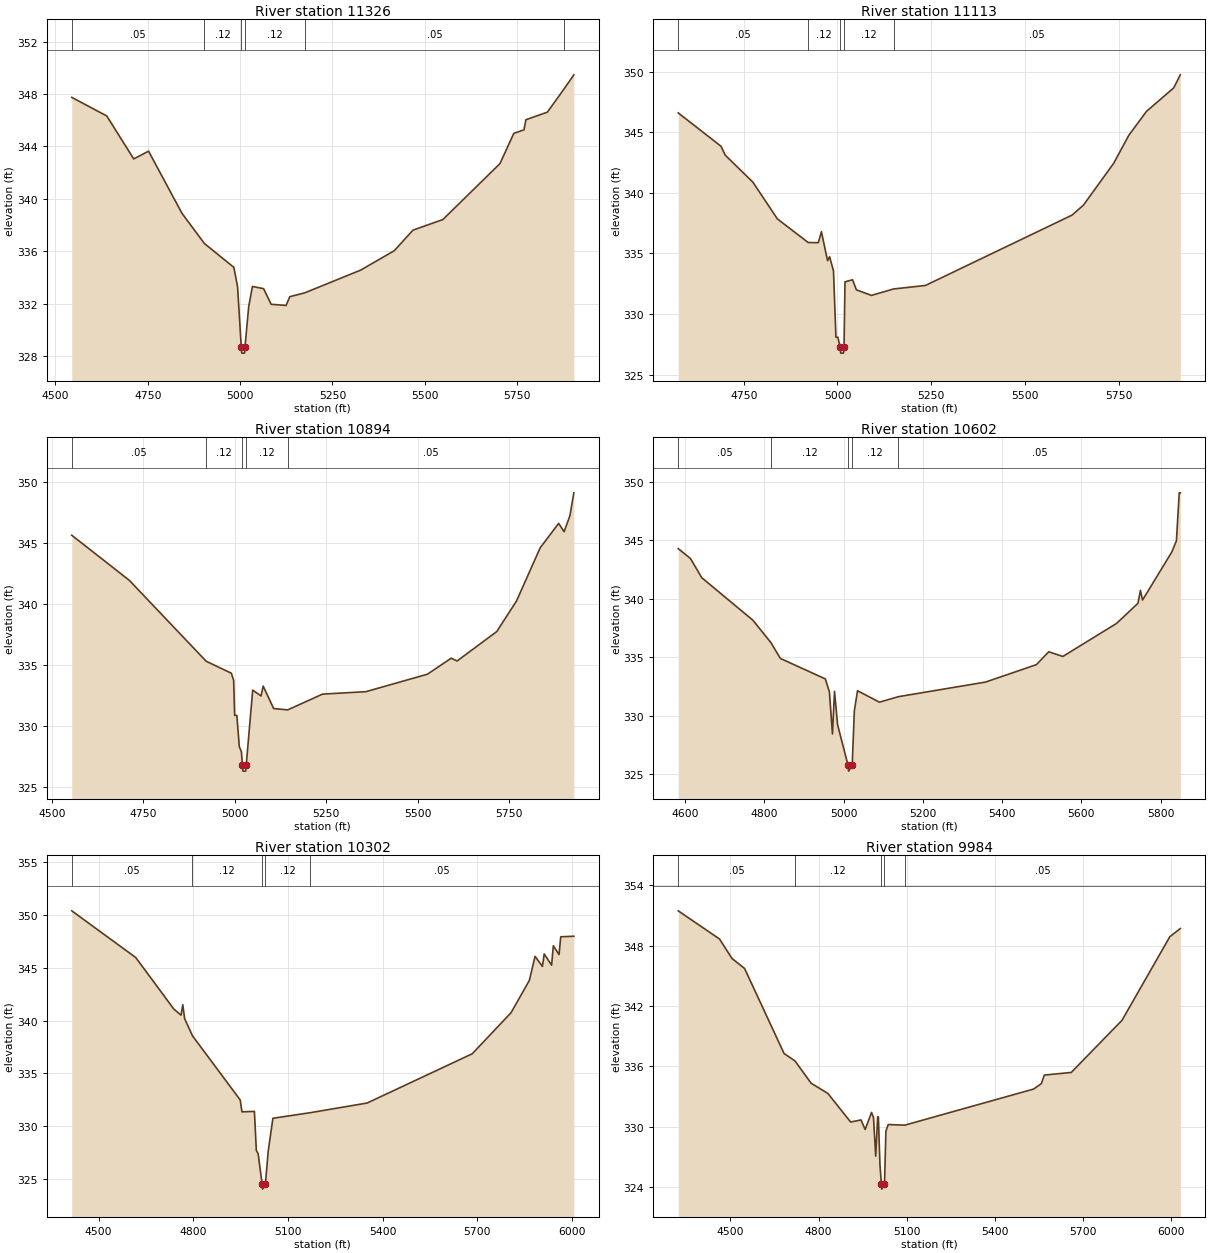
Type RM Length L Ch R = 1,11326,213,213,213
BEGIN DESCRIPTION:
Persimmon Branch 230
END DESCRIPTION:
XS GIS Cut Line= 3
      2676553.16      6817074.07      2676090.97      6817035.41
      2675205.13      6816907.00
#Sta/Elev= 30
  4544.5  347.75  4639.2  346.33  4712.2  343.05  4752.4  343.64  4842.7  338.90
  4903.5  336.59  4983.2  334.77  4993.2  333.30  5003.2  328.72  5004.6  328.22
  5012.0  328.22  5013.4  328.72  5023.4  331.78  5033.5  333.31  5063.8  333.14
  5084.1  331.95  5124.5  331.86  5134.6  332.53  5174.9  332.82  5326.6  334.56
  5417.4  336.04  5468.0  337.61  5548.9  338.42  5703.4  342.69  5740.9  345.00
  5768.5  345.27  5773.6  346.04  5831.8  346.62  5877.6  348.42  5903.4  349.47
#Mann=6,-1,0
  4544.5    0.05       0  4903.5    0.12       0  5003.2    0.07       0
  5013.4    0.12       0  5174.9    0.05       0  5877.6    0.12       0
Bank Sta=5003.2,5013.4
Exp/Cntr=0.3,0.1

Type RM Length L Ch R = 1,11113,219,219,219
BEGIN DESCRIPTION:
Persimmon Branch 231
END DESCRIPTION:
XS GIS Cut Line= 3
      2676572.45      6816999.16      2676178.85      6816847.71
      2675269.85      6816724.12
#Sta/Elev= 30
  4575.3  346.59  4689.4  343.84  4700.5  343.11  4774.4  340.88  4839.7  337.85
  4922.0  335.90  4949.0  335.89  4957.2  336.79  4973.6  334.40  4979.0  334.73
  4989.4  333.56  4995.9  328.09  5001.0  328.09  5007.2  327.28  5008.6  326.78
  5016.1  326.78  5017.5  327.28  5020.1  332.66  5040.3  332.83  5050.4  332.00
  5090.7  331.54  5149.5  332.07  5234.7  332.36  5625.6  338.16  5655.9  338.98
  5736.6  342.43  5777.0  344.74  5824.3  346.72  5896.7  348.65  5914.4  349.73
#Mann=5,-1,0
  4575.3    0.05       0  4922.0    0.12       0  5007.2    0.07       0
  5017.5    0.12       0  5149.5    0.05       0
Bank Sta=5007.2,5017.5
Exp/Cntr=0.3,0.1

Type RM Length L Ch R = 1,10894,292,292,292
BEGIN DESCRIPTION:
Persimmon Branch 229
END DESCRIPTION:
XS GIS Cut Line= 3
      2676620.06      6816937.83      2676266.68      6816662.60
      2675459.74      6816211.90
#Sta/Elev= 30
  4554.6  345.61  4711.9  341.92  4922.0  335.30  4990.7  334.32  4997.0  333.74
  4999.8  330.87  5005.8  330.87  5012.5  328.31  5018.3  327.89  5021.0  326.81
  5022.5  326.31  5030.0  326.31  5031.4  326.81  5049.1  332.94  5071.9  332.46
  5077.7  333.27  5106.4  331.43  5144.8  331.32  5239.9  332.61  5358.4  332.81
  5526.6  334.24  5591.7  335.55  5607.7  335.32  5716.2  337.73  5769.9  340.22
  5835.0  344.59  5885.3  346.58  5900.2  345.90  5916.1  347.21  5926.8  349.08
#Mann=5,-1,0
  4554.6    0.05       0  4922.0    0.12       0  5021.0    0.07       0
  5031.4    0.12       0  5144.8    0.05       0
Bank Sta=5021,5031.4
Exp/Cntr=0.3,0.1

Type RM Length L Ch R = 1,10602,300,300,300
BEGIN DESCRIPTION:
Persimmon Branch 33
END DESCRIPTION:
XS GIS Cut Line= 3
      2676775.98      6816511.00      2676376.00      6816411.00
      2675575.99      6816111.00
#Sta/Elev= 30
  4582.8  344.29  4613.7  343.44  4642.1  341.80  4770.9  338.17  4816.5  336.25
  4840.5  334.89  4953.9  333.14  4964.2  332.03  4971.9  328.43  4977.1  332.08
  4984.8  329.23  5011.2  325.75  5012.7  325.25  5021.7  325.75  5027.1  330.40
  5035.1  332.13  5090.3  331.15  5138.5  331.62  5358.2  332.87  5486.4  334.36
  5517.5  335.46  5553.1  335.06  5688.4  337.88  5742.7  339.61  5748.9  340.71
  5754.3  339.89  5828.1  344.00  5839.7  344.96  5846.8  349.06  5849.5  349.06
#Mann=5,-1,0
  4582.8    0.05       0  4816.5    0.12       0  5011.2    0.07       0
  5021.7    0.12       0  5138.5    0.05       0
Bank Sta=5011.2,5021.7
Exp/Cntr=0.3,0.1

Type RM Length L Ch R = 1,10302,318,318,318
BEGIN DESCRIPTION:
Persimmon Branch 183
END DESCRIPTION:
XS GIS Cut Line= 3
      2677069.32      6816446.36      2676539.64      6816195.80
      2675616.28      6815798.13
#Sta/Elev= 30
  4415.0  350.36  4617.8  345.95  4738.6  341.08  4761.3  340.51  4766.9  341.49
  4772.7  340.18  4797.6  338.56  4948.9  332.50  4954.4  331.38  4993.9  331.42
  5000.0  327.72  5005.7  327.43  5018.2  324.58  5019.7  324.08  5028.7  324.58
  5037.6  327.66  5052.5  330.77  5171.2  331.30  5351.1  332.21  5684.2  336.86
  5807.3  340.74  5865.3  343.79  5883.3  346.06  5906.9  345.11  5912.3  346.29
  5935.8  345.23  5941.3  347.06  5959.4  346.23  5964.8  347.91  6006.3  347.96
#Mann=5,-1,0
  4415.0    0.05       0  4797.6    0.12       0  5018.2    0.07       0
  5028.7    0.12       0  5171.2    0.05       0
Bank Sta=5018.2,5028.7
Exp/Cntr=0.3,0.1

Type RM Length L Ch R = 1,9984,266,266,266
BEGIN DESCRIPTION:
Persimmon Branch 182
END DESCRIPTION:
XS GIS Cut Line= 3
      2677208.73      6816387.02      2676701.22      6815932.64
      2675691.01      6815744.36
#Sta/Elev= 30
  4322.5  351.45  4463.0  348.65  4505.6  346.71  4548.3  345.72  4682.8  337.26
  4719.8  336.53  4774.8  334.31  4831.6  333.30  4909.4  330.45  4944.5  330.66
  4958.7  329.71  4980.4  331.41  4987.1  330.88  4994.6  327.06  5001.2  330.96
  5003.7  330.96  5009.0  326.25  5013.9  324.28  5015.3  323.78  5024.5  324.28
  5029.3  329.53  5037.2  330.20  5093.6  330.14  5532.0  333.73  5558.3  334.27
  5568.5  335.12  5660.0  335.38  5833.0  340.57  5995.7  348.88  6031.3  349.69
#Mann=5,-1,0
  4322.5    0.05       0  4719.8    0.12       0  5013.9    0.07       0
  5024.5    0.12       0  5093.6    0.05       0
Bank Sta=5013.9,5024.5
Exp/Cntr=0.3,0.1

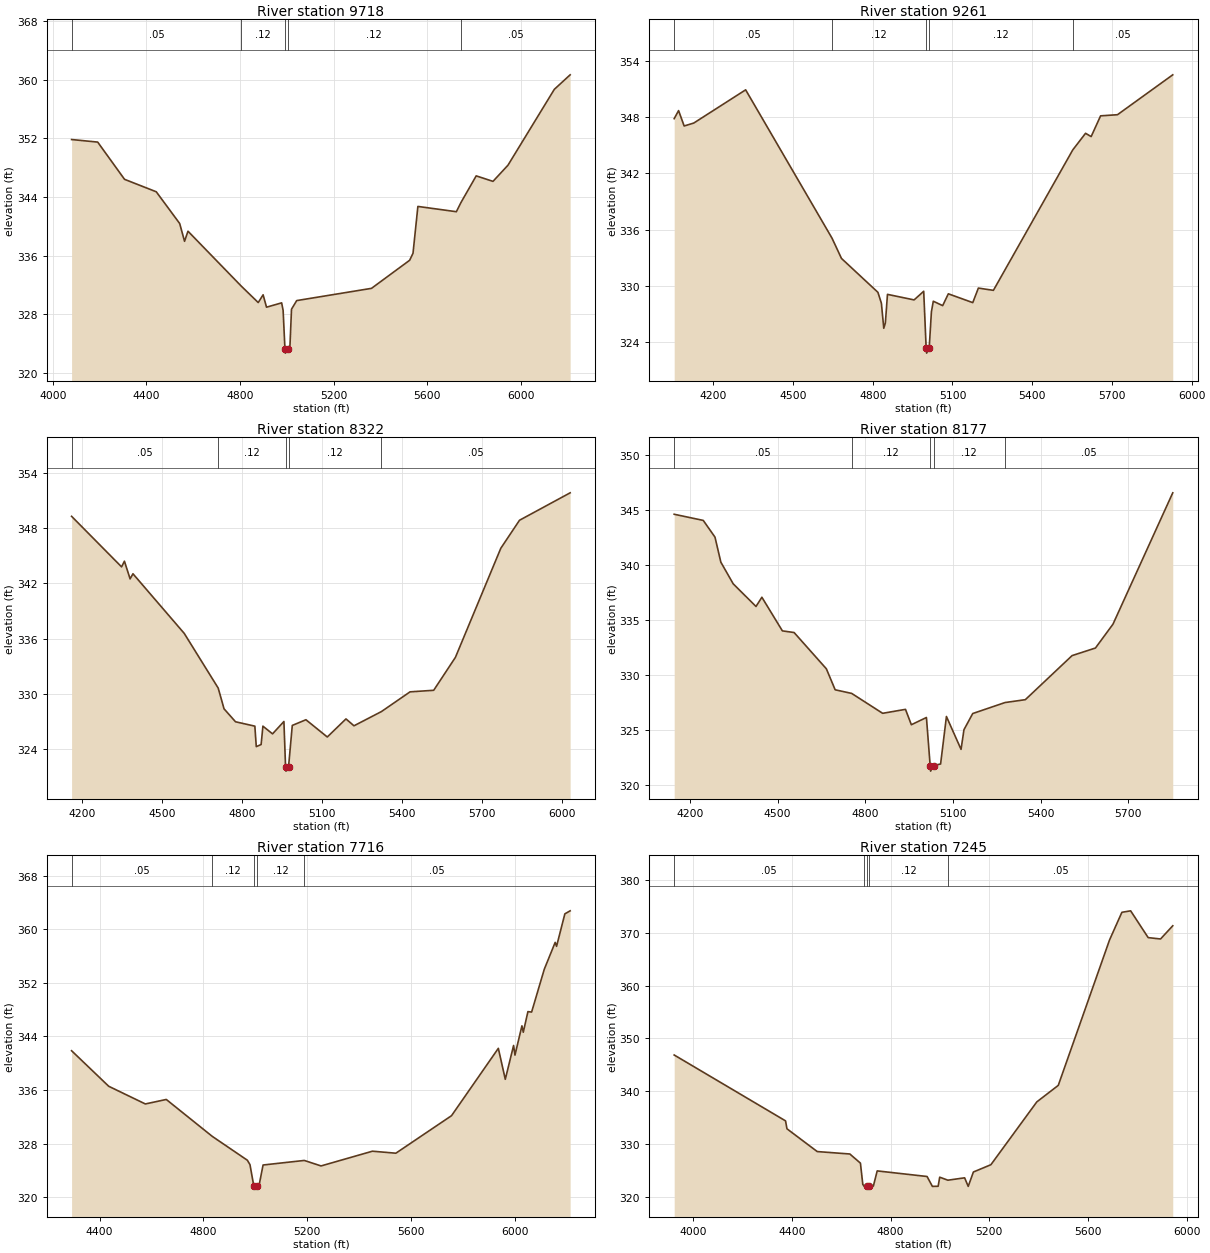
Type RM Length L Ch R = 1,9718,457,457,457
BEGIN DESCRIPTION:
Persimmon Branch 151
END DESCRIPTION:
XS GIS Cut Line= 3
      2677607.50      6816304.86      2676872.68      6815755.42
      2676105.19      6814817.42
#Sta/Elev= 30
  4080.4  351.83  4191.9  351.48  4306.5  346.40  4442.0  344.70  4542.1  340.37
  4562.9  337.94  4577.5  339.32  4805.3  331.82  4877.6  329.58  4898.4  330.64
  4913.0  328.95  4977.6  329.54  4983.9  328.51  4991.8  323.18  4993.3  322.68
  5003.1  323.18  5013.2  323.73  5019.7  328.67  5041.9  329.85  5361.4  331.52
  5524.3  335.35  5538.7  336.31  5559.5  342.70  5723.9  341.98  5743.6  343.24
  5808.6  346.87  5880.3  346.12  5944.2  348.32  6142.3  358.68  6209.9  360.66
#Mann=5,-1,0
  4080.4    0.05       0  4805.3    0.12       0  4991.8    0.07       0
  5003.1    0.12       0  5743.6    0.05       0
Bank Sta=4991.8,5003.1
Exp/Cntr=0.3,0.1

Type RM Length L Ch R = 1,9261,939,939,939
BEGIN DESCRIPTION:
Persimmon Branch 150
END DESCRIPTION:
XS GIS Cut Line= 3
      2677773.43      6815975.98      2676979.40      6815446.04
      2676335.16      6814787.77
#Sta/Elev= 30
  4053.2  347.83  4069.7  348.69  4090.7  347.05  4126.7  347.36  4322.0  350.90
  4647.1  335.09  4682.5  332.94  4819.6  329.33  4832.7  328.17  4841.7  325.50
  4847.7  326.07  4855.6  329.11  4955.8  328.52  4991.9  329.44  5001.2  323.35
  5002.8  322.85  5012.5  323.35  5020.9  327.25  5028.0  328.38  5063.3  327.91
  5084.6  329.17  5176.5  328.23  5197.6  329.78  5254.2  329.54  5552.7  344.50
  5600.8  346.27  5621.9  345.92  5657.4  348.13  5720.9  348.25  5928.9  352.50
#Mann=5,-1,0
  4053.2    0.05       0  4647.1    0.12       0  5001.2    0.07       0
  5012.5    0.12       0  5552.7    0.05       0
Bank Sta=5001.2,5012.5
Exp/Cntr=0.3,0.1

Type RM Length L Ch R = 1,8322,145,145,145
BEGIN DESCRIPTION:
Persimmon Branch 149
END DESCRIPTION:
XS GIS Cut Line= 3
      2678261.47      6815169.27      2677479.95      6814875.12
      2676446.27      6814817.91
#Sta/Elev= 30
  4160.8  349.32  4348.3  343.81  4359.0  344.43  4380.3  342.50  4391.0  343.06
  4583.4  336.56  4710.8  330.60  4732.7  328.34  4775.7  326.93  4848.3  326.45
  4853.6  324.22  4871.8  324.45  4878.5  326.45  4914.6  325.61  4957.3  326.96
  4963.4  322.05  4965.0  321.55  4974.8  322.05  4988.7  326.53  5039.9  327.15
  5120.0  325.27  5190.1  327.24  5220.1  326.49  5323.1  328.04  5430.5  330.19
  5519.2  330.36  5600.7  333.95  5771.0  345.84  5841.1  348.89  6031.1  351.88
#Mann=5,-1,0
  4160.8    0.05       0  4710.8    0.12       0  4963.4    0.07       0
  4974.8    0.12       0  5323.1    0.05       0
Bank Sta=4963.4,4974.8
Exp/Cntr=0.3,0.1

Type RM Length L Ch R = 1,8177,461,461,461
BEGIN DESCRIPTION:
Persimmon Branch 148
END DESCRIPTION:
XS GIS Cut Line= 3
      2678375.19      6814811.58      2677518.09      6814744.34
      2676671.44      6814739.70
#Sta/Elev= 30
  4146.2  344.65  4245.7  344.09  4285.8  342.57  4305.9  340.29  4348.2  338.32
  4426.2  336.26  4446.3  337.10  4516.5  334.04  4556.6  333.89  4667.0  330.59
  4697.1  328.68  4753.7  328.35  4859.7  326.54  4937.8  326.90  4957.9  325.50
  5009.5  326.16  5022.3  321.78  5023.9  321.28  5033.7  321.78  5058.0  321.93
  5078.0  326.25  5128.0  323.26  5138.0  325.05  5168.0  326.52  5278.5  327.52
  5348.0  327.78  5508.0  331.79  5588.0  332.48  5648.0  334.65  5852.6  346.60
#Mann=5,-1,0
  4146.2    0.05       0  4753.7    0.12       0  5022.3    0.07       0
  5033.7    0.12       0  5278.5    0.05       0
Bank Sta=5022.3,5033.7
Exp/Cntr=0.3,0.1

Type RM Length L Ch R = 1,7716,471,471,471
BEGIN DESCRIPTION:
Persimmon Branch 152
END DESCRIPTION:
XS GIS Cut Line= 3
      2678527.88      6814566.41      2677582.29      6814447.02
      2677284.86      6813526.16
#Sta/Elev= 30
  4292.2  341.87  4435.2  336.57  4576.3  333.93  4657.0  334.60  4833.9  329.10
  4969.4  325.53  4979.5  324.87  4994.0  321.72  4995.5  321.22  5005.4  321.72
  5014.4  321.76  5029.9  324.82  5188.8  325.50  5253.2  324.68  5451.3  326.88
  5541.5  326.58  5756.0  332.18  5936.3  342.23  5963.1  337.61  5995.1  342.66
  6000.4  341.22  6027.2  345.59  6032.4  344.63  6050.3  347.71  6064.5  347.64
  6113.3  354.03  6155.3  358.04  6160.6  357.45  6192.6  362.30  6213.0  362.75
#Mann=5,-1,0
  4292.2    0.05       0  4833.9    0.12       0  4994.0    0.07       0
  5005.4    0.12       0  5188.8    0.05       0
Bank Sta=4994,5005.4
Exp/Cntr=0.3,0.1

Type RM Length L Ch R = 1,7245,715,715,715
BEGIN DESCRIPTION:
Persimmon Branch 147
END DESCRIPTION:
XS GIS Cut Line= 3
      2678703.00      6814610.94      2677780.09      6814057.38
      2677220.71      6813297.46
#Sta/Elev= 30
  3923.6  346.87  4374.7  334.40  4380.5  332.90  4503.1  328.59  4635.2  328.13
  4678.1  326.40  4687.7  322.37  4693.7  322.00  4703.2  321.98  4704.8  321.48
  4714.8  321.98  4730.4  322.04  4746.0  324.93  4948.1  323.87  4969.6  322.00
  4992.9  322.02  4999.3  323.74  5032.3  323.17  5100.2  323.62  5114.8  322.00
  5135.7  324.72  5206.6  326.10  5392.6  337.99  5479.6  341.12  5687.2  368.63
  5737.3  373.88  5772.8  374.16  5843.8  369.09  5893.9  368.83  5943.4  371.33
#Mann=5,-1,0
  3923.6    0.05       0  4693.7    0.12       0  4703.2    0.07       0
  4714.8    0.12       0  5032.3    0.05       0
Bank Sta=4703.2,4714.8
Exp/Cntr=0.3,0.1

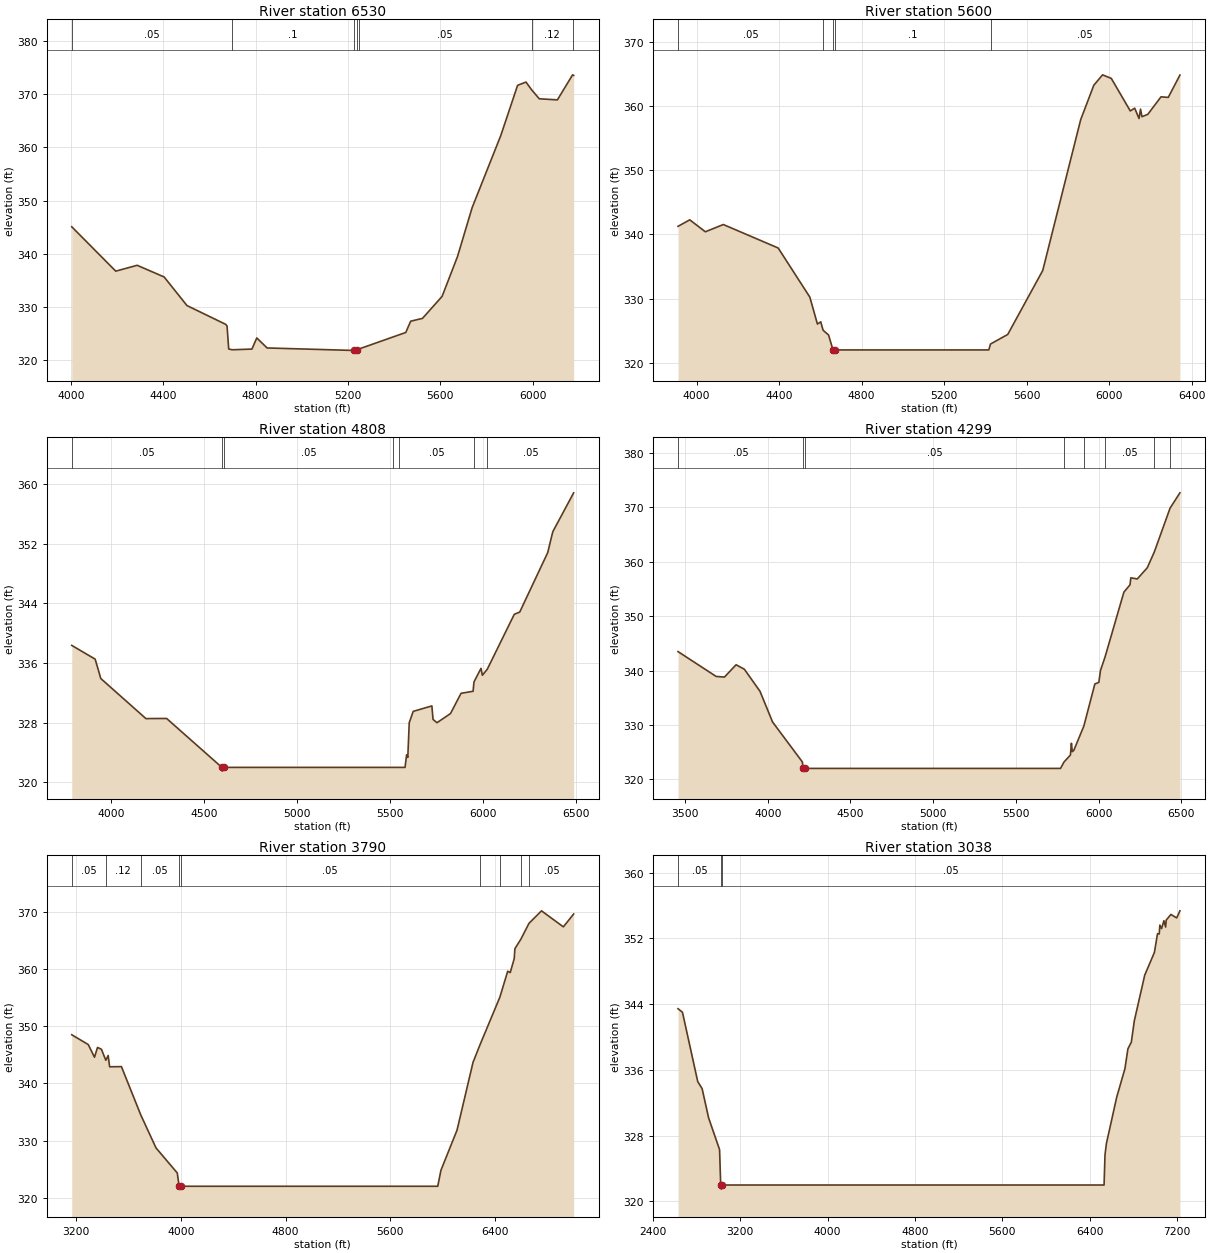
Type RM Length L Ch R = 1,6530,930,930,930
BEGIN DESCRIPTION:
Persimmon Branch 146
END DESCRIPTION:
XS GIS Cut Line= 3
      2678868.95      6814552.25      2678293.47      6813708.41
      2677326.08      6813085.28
#Sta/Elev= 30
  4004.6  345.09  4195.0  336.76  4287.7  337.86  4404.3  335.67  4503.2  330.30
  4670.6  326.78  4676.6  326.47  4683.9  322.15  4698.4  322.00  4784.4  322.13
  4805.3  324.22  4850.1  322.34  5226.6  321.87  5228.2  321.37  5238.2  321.87
  5247.7  322.15  5450.2  325.25  5471.3  327.36  5522.6  327.90  5607.3  332.02
  5674.0  339.50  5737.4  348.69  5861.5  362.24  5934.1  371.65  5970.4  372.26
  5994.6  370.82  6027.9  369.12  6106.4  368.92  6172.1  373.62  6176.7  373.51
#Mann=7,-1,0
  4004.6    0.05       0  4698.4     0.1       0  5226.6    0.07       0
  5238.2     0.1       0  5247.7    0.05       0  5994.6    0.12       0
  6172.1    0.05       0
Bank Sta=5226.6,5238.2
Exp/Cntr=0.3,0.1

Type RM Length L Ch R = 1,5600,792,792,792
BEGIN DESCRIPTION:
Persimmon Branch 145
END DESCRIPTION:
XS GIS Cut Line= 3
      2679395.89      6814120.45      2678869.88      6813166.88
      2677951.72      6812185.29
#Sta/Elev= 30
  3910.2  341.27  3967.1  342.28  4042.7  340.42  4129.8  341.55  4395.7  337.89
  4549.1  330.24  4586.0  326.03  4602.0  326.38  4613.4  325.07  4639.9  324.33
  4661.5  322.00  4663.1  321.50  4673.2  322.00  5416.7  322.00  5425.0  322.92
  5508.5  324.41  5678.2  334.38  5862.2  357.90  5925.7  363.26  5968.2  364.89
  6010.7  364.33  6102.7  359.26  6124.0  359.69  6145.0  358.08  6152.3  359.54
  6159.2  358.36  6187.5  358.73  6251.5  361.46  6286.7  361.37  6343.3  364.85
#Mann=5,-1,0
  3910.2    0.05       0  4613.4     0.1       0  4661.5    0.07       0
  4673.2     0.1       0  5425.0    0.05       0
Bank Sta=4661.5,4673.2
Exp/Cntr=0.3,0.1

Type RM Length L Ch R = 1,4808,509,509,509
BEGIN DESCRIPTION:
Persimmon Branch 144
END DESCRIPTION:
XS GIS Cut Line= 3
      2679631.05      6813855.47      2679463.18      6812660.36
      2678265.73      6811775.59
#Sta/Elev= 30
  3790.0  338.35  3915.7  336.51  3946.0  333.91  4188.3  328.54  4299.4  328.56
  4596.5  322.00  4598.1  321.50  4608.2  322.00  5517.3  322.00  5549.5  322.00
  5580.1  322.00  5588.5  323.69  5594.8  323.34  5602.6  327.99  5624.0  329.51
  5724.2  330.24  5730.4  328.43  5751.8  327.99  5824.4  329.22  5880.8  331.93
  5945.5  332.20  5950.4  333.46  5988.0  335.27  5995.6  334.35  6021.8  335.16
  6166.8  342.52  6196.1  342.82  6346.4  350.79  6373.5  353.58  6485.7  358.80
#Mann=7,-1,0
  3790.0    0.05       0  4596.5    0.03       0  4608.2    0.05       0
  5517.3     0.1       0  5549.5    0.05       0  5950.4   0.075       0
  6021.8    0.05       0
Bank Sta=4596.5,4608.2
Exp/Cntr=0.3,0.1

Type RM Length L Ch R = 1,4299,509,509,509
BEGIN DESCRIPTION:
Persimmon Branch 128
END DESCRIPTION:
XS GIS Cut Line= 3
      2679808.97      6814001.10      2679908.88      6812462.07
      2679698.69      6810985.73
#Sta/Elev= 30
  3457.8  343.48  3688.4  338.91  3738.5  338.80  3808.6  341.06  3858.7  340.24
  3953.1  336.19  4029.1  330.54  4209.5  323.18  4213.4  322.00  4215.1  321.50
  4225.7  322.00  5769.7  322.00  5790.8  323.18  5829.4  324.46  5835.4  326.62
  5840.5  325.08  5849.6  325.30  5910.5  329.78  5977.1  337.53  6001.1  337.82
  6011.2  340.02  6038.7  342.49  6152.6  354.42  6189.6  355.77  6194.6  357.05
  6233.5  356.84  6294.1  358.91  6336.5  361.81  6431.8  369.87  6491.3  372.68
#Mann=8,-1,0
  3457.8    0.05       0  4213.4    0.03       0  4225.7    0.05       0
  5790.8     0.1       0  5910.5   0.075       0  6038.7    0.05       0
  6336.5   0.075       0  6431.8    0.05       0
Bank Sta=4213.4,4225.7
Exp/Cntr=0.3,0.1

Type RM Length L Ch R = 1,3790,752,752,752
BEGIN DESCRIPTION:
Persimmon Branch 129
END DESCRIPTION:
XS GIS Cut Line= 3
      2680068.91      6814214.67      2680402.50      6812412.29
      2679716.06      6810526.96
#Sta/Elev= 30
  3164.9  348.49  3291.0  346.78  3338.8  344.56  3361.9  346.27  3391.7  345.96
  3425.4  344.03  3443.2  344.86  3454.8  342.89  3544.9  342.92  3692.6  334.49
  3809.3  328.71  3972.1  324.32  3986.2  322.00  3987.9  321.50  3998.5  322.00
  5964.6  322.00  5989.0  324.79  6112.2  331.82  6234.5  343.67  6286.8  346.68
  6439.9  355.07  6499.8  359.60  6519.0  359.36  6549.6  361.79  6554.9  363.54
  6601.0  365.22  6662.7  367.98  6758.3  370.16  6925.5  367.36  7004.3  369.60
#Mann=9,-1,0
  3164.9    0.05       0  3425.4    0.12       0  3692.6    0.05       0
  3986.2    0.03       0  3998.5    0.05       0  6286.8   0.075       0
  6439.9    0.05       0  6601.0   0.075       0  6662.7    0.05       0
Bank Sta=3986.2,3998.5
Exp/Cntr=0.3,0.1

Type RM Length L Ch R = 1,3038,951,951,951
BEGIN DESCRIPTION:
Persimmon Branch 102
END DESCRIPTION:
XS GIS Cut Line= 3
      2681151.17      6814731.60      2681138.99      6812341.54
      2680016.26      6810439.70
#Sta/Elev= 30
  2629.4  343.45  2670.0  343.02  2810.0  334.58  2850.0  333.73  2910.0  330.15
  3010.0  326.31  3020.0  322.18  3023.8  322.00  3025.5  321.50  3036.3  322.00
  6532.9  322.00  6541.4  325.66  6554.3  327.05  6649.9  332.75  6724.1  336.15
  6751.4  338.57  6782.7  339.38  6809.9  341.97  6905.5  347.54  6994.2  350.30
  7022.6  352.58  7038.3  352.54  7044.1  353.62  7059.7  353.20  7081.2  354.16
  7096.8  353.39  7102.6  354.24  7145.5  354.92  7198.2  354.50  7228.0  355.36
#Mann=3,-1,0
  2629.4    0.05       0  3023.8    0.03       0  3036.3    0.05       0
Bank Sta=3023.8,3036.3
Exp/Cntr=0.3,0.1

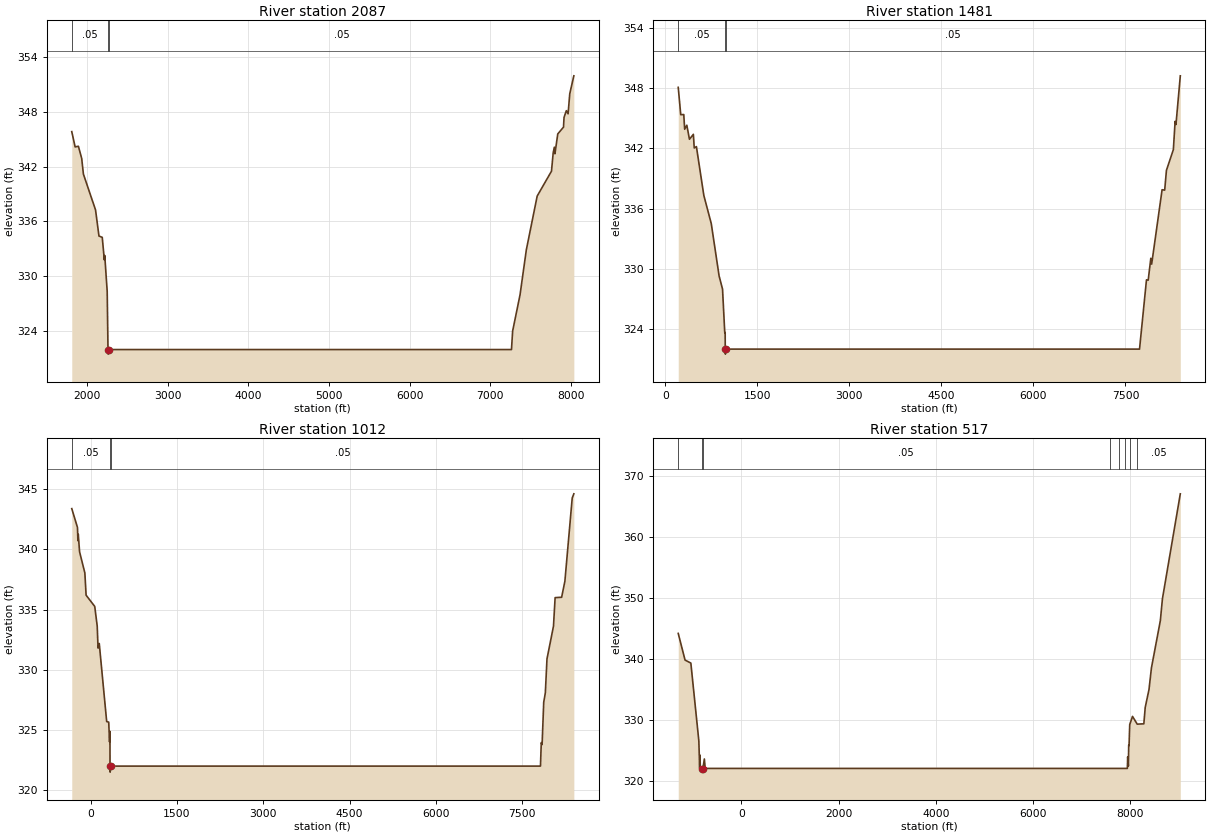
Type RM Length L Ch R = 1,2087,606,606,606
BEGIN DESCRIPTION:
Persimmon Branch 91
END DESCRIPTION:
XS GIS Cut Line= 3
      2681484.52      6815481.91      2682081.86      6812386.56
      2680036.90      6810099.02
#Sta/Elev= 30
  1813.2  345.82  1854.9  344.15  1895.3  344.22  1936.3  342.89  1957.4  341.18
  2107.8  337.26  2150.2  334.41  2191.0  334.26  2216.6  331.80  2221.7  332.28
  2252.1  328.37  2262.2  322.00  2264.0  321.50  2274.8  322.00  7261.4  322.00
  7275.6  324.02  7367.5  327.99  7445.3  332.90  7579.9  338.78  7757.1  341.50
  7778.0  343.49  7792.2  344.12  7799.7  343.40  7834.8  345.57  7905.9  346.31
  7912.6  347.38  7941.0  348.11  7962.7  347.77  7983.6  349.97  8034.0  351.92
#Mann=3,-1,0
  1813.2    0.05       0  2262.2    0.03       0  2274.8    0.05       0
Bank Sta=2262.2,2274.8
Exp/Cntr=0.3,0.1

Type RM Length L Ch R = 1,1481,469,469,469
BEGIN DESCRIPTION:
Persimmon Branch 32
END DESCRIPTION:
XS GIS Cut Line= 5
      2681410.51      6816172.96      2683110.11      6814764.34
      2682930.86      6812890.13      2682626.00      6812261.00
      2680226.02      6809861.02
#Sta/Elev= 30
   211.1  348.08   252.0  345.36   301.5  345.37   315.8  343.91   351.0  344.31
   394.0  342.91   457.8  343.40   472.1  342.04   507.3  342.18   628.4  337.31
   749.5  334.51   877.2  329.29   933.1  327.98   969.6  323.62   976.1  323.65
   977.4  322.00   979.3  321.50   990.5  322.00  7729.8  322.00  7843.0  328.90
  7871.3  328.87  7913.7  331.05  7927.8  330.47  8097.5  337.88  8140.0  337.84
  8168.3  339.81  8281.4  341.88  8309.7  344.69  8323.8  344.38  8394.5  349.23
#Mann=3,-1,0
   211.1    0.05       0   977.4    0.03       0   990.5    0.05       0
Bank Sta=977.4,990.5
Exp/Cntr=0.3,0.1

Type RM Length L Ch R = 1,1012,495,495,495
BEGIN DESCRIPTION:
Persimmon Branch 31
END DESCRIPTION:
XS GIS Cut Line= 4
      2681436.69      6816320.71      2683331.11      6814899.86
      2682976.00      6811961.00      2680576.00      6809561.00
#Sta/Elev= 30
  -328.0  343.38  -228.9  341.82  -221.4  340.72  -215.1  341.25  -192.2  339.79
  -100.5  338.04   -78.9  336.19    71.1  335.26   114.0  333.63   128.6  331.80
   149.5  332.18   278.6  325.70   314.0  325.65   328.6  324.00   334.9  324.88
   336.7  322.00   338.5  321.50   349.8  322.00  7814.6  322.00  7828.7  323.95
  7842.9  323.79  7871.1  327.30  7899.4  328.09  7927.7  330.90  8040.8  333.62
  8069.1  335.99  8182.3  336.02  8238.8  337.35  8366.1  344.26  8394.4  344.61
#Mann=3,-1,0
  -328.0    0.05       0   336.7    0.03       0   349.8    0.05       0
Bank Sta=336.7,349.8
Exp/Cntr=0.3,0.1

Type RM Length L Ch R = 1,517,0,0,0
BEGIN DESCRIPTION:
Persimmon Branch 30
END DESCRIPTION:
XS GIS Cut Line= 4
      2681374.67      6816466.55      2683640.25      6815390.79
      2683326.00      6811611.00      2680326.02      6808911.02
#Sta/Elev= 30
 -1300.5  344.19 -1160.0  339.81 -1040.8  339.32  -876.2  326.52  -859.0  322.00
  -853.5  324.19  -845.2  322.00  -807.4  321.89  -805.6  321.39  -794.3  321.89
  -762.6  323.55  -745.5  322.00  7581.5  322.00  7770.2  322.00  7893.0  322.00
  7946.3  322.00  7953.0  323.90  7967.2  322.38  7974.0  325.82  7981.4  325.76
  7995.1  329.21  8052.4  330.55  8149.2  329.28  8285.6  329.33  8314.0  332.03
  8391.8  334.97  8441.9  338.52  8625.7  346.31  8668.3  349.89  9036.4  367.14
#Mann=8,-1,0
 -1300.5    0.05       0  -807.4    0.03       0  -794.3    0.05       0
  7581.5     0.1       0  7770.2   0.075       0  7893.0     0.1       0
  7995.1   0.075       0  8149.2    0.05       0
Bank Sta=-807.4,-794.3
Exp/Cntr=0.3,0.1

Chan Stop Cuts=-1