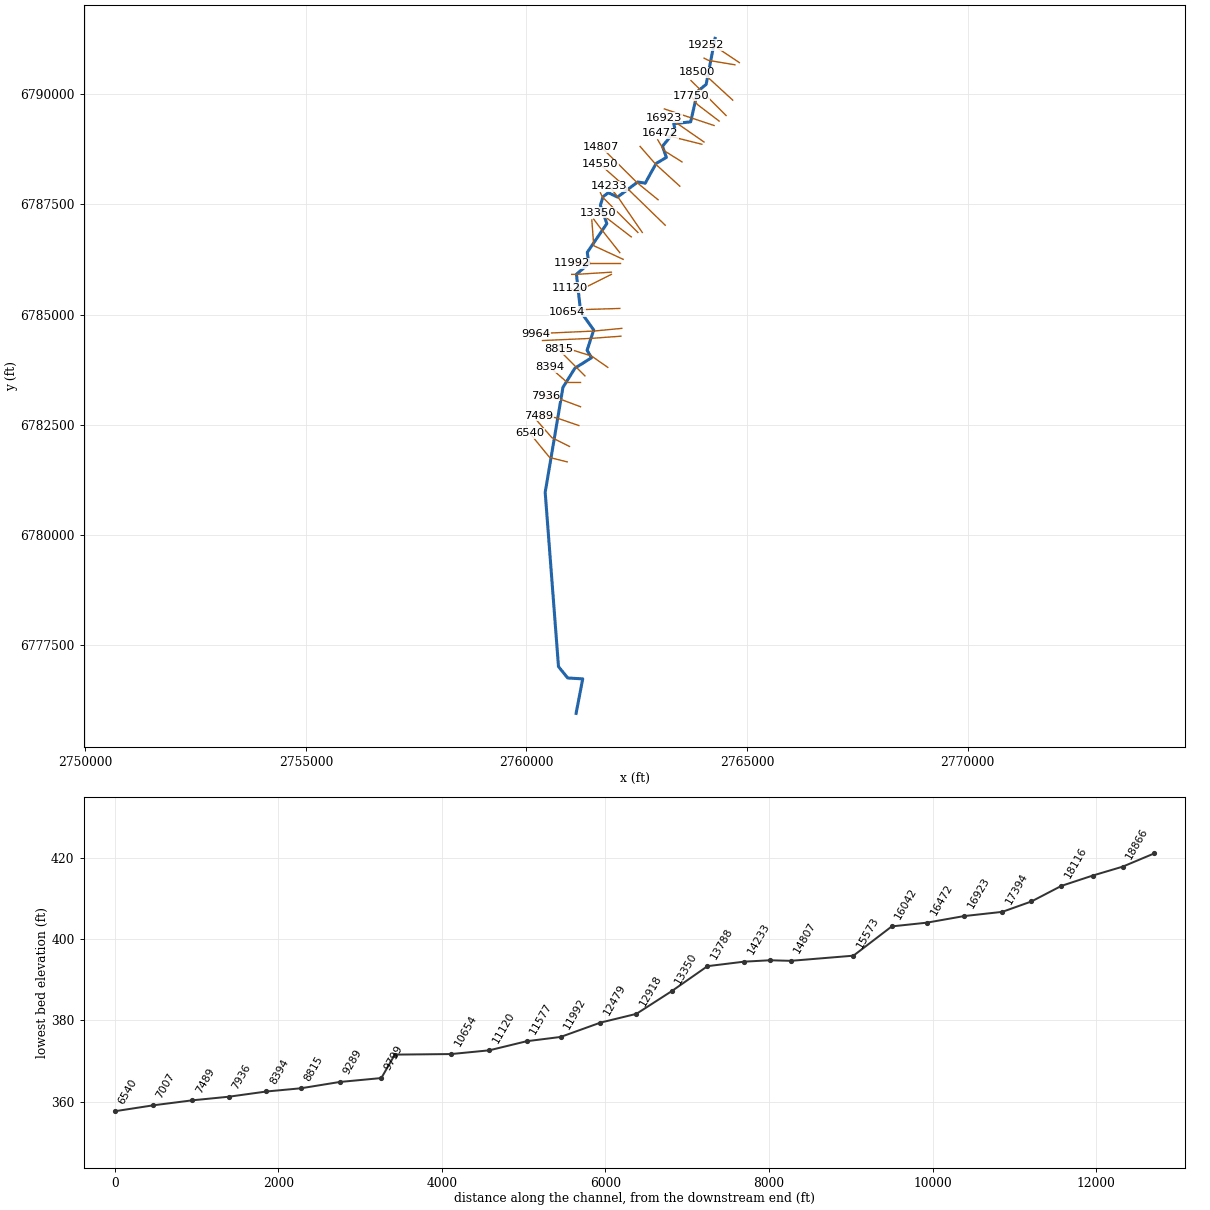
--- Pickens Branch.prj (project) ---

Proj Title=Pickens Branch Base Level Engineering
Current Plan=p01
Default Exp/Contr=0.3,0.1
English Units
Geom File=g01
Flow File=f01
Plan File=p01
BEGIN DESCRIPTION:
Pickens Branch
END DESCRIPTION:

--- Pickens Branch.p01 (plan) ---

Plan Title=Multiple Run
Short Identifier=Multiple
Geom File=g01
Flow File=f01
Subcritical Flow
K Sum by GR= 0
Std Step Tol= 0.01
Critical Tol= 0.01
Num of Std Step Trials= 20
Max Error Tol= 0.3
Flow Tol Ratio= 0.001
Split Flow NTrial= 30
Split Flow Tol= 0.02
Split Flow Ratio= 0.02
Log Output Level= 0
Friction Slope Method= 1
Unsteady Friction Slope Method= 2
Unsteady Bridges Friction Slope Method= 1
Parabolic Critical Depth
Global Vel Dist=  1 , 1 , 1
Global Log Level= 0
CheckData=True
Encroach Param= -1, 0, 0, 0
BEGIN DESCRIPTION:
Multiple Run
END DESCRIPTION:

--- Pickens Branch.f01 (steady flow) ---

Flow Title=Multiple
Number of Profiles=7
Profile Names=10-year,25-year,50-year,1pct_min,100-year,1pct_plu,500-year
River Rch & RM= Pickens Branch,Reach-1,19252
     737    1021    1259     773    1542    3077    2319
River Rch & RM= Pickens Branch,Reach-1,16923
    1020    1428    1773    1093    2182    4353    3313
River Rch & RM= Pickens Branch,Reach-1,11992
    1264    1786    2231    1383    2760    5507    4236
River Rch & RM= Pickens Branch,Reach-1,9964
    1201    1675    2073    1272    2539    5065    3818
River Rch & RM= Pickens Branch,Reach-1,4176
    1542    2175    2713    1677    3346    6677    5106
River Rch & RM= Pickens Branch,Reach-1,2232
    1678    2371    2963    1833    3656    7296    5588
Boundary for River Rch & Prof#=Pickens Branch,Reach-1,1
Up Type=0
Dn Type=3
Dn Slope=0.005
Boundary for River Rch & Prof#=Pickens Branch,Reach-1,2
Up Type=0
Dn Type=3
Dn Slope=0.005
Boundary for River Rch & Prof#=Pickens Branch,Reach-1,3
Up Type=0
Dn Type=3
Dn Slope=0.005
Boundary for River Rch & Prof#=Pickens Branch,Reach-1,4
Up Type=0
Dn Type=3
Dn Slope=0.005
Boundary for River Rch & Prof#=Pickens Branch,Reach-1,5
Up Type=0
Dn Type=3
Dn Slope=0.005
Boundary for River Rch & Prof#=Pickens Branch,Reach-1,6
Up Type=0
Dn Type=3
Dn Slope=0.005
Boundary for River Rch & Prof#=Pickens Branch,Reach-1,7
Up Type=0
Dn Type=3
Dn Slope=0.005

--- Pickens Branch.g01 (geometry) ---

Geom Title=Existing Conditions

River Reach=Pickens Branch,Reach-1
Reach XY= 30
      2764276.00      6791261.00      2764073.95      6790216.84
      2763879.45      6790059.75      2763723.07      6789368.85
      2763339.36      6789324.80      2763373.02      6789169.34
      2763083.80      6788814.41      2763172.63      6788562.28
      2762939.40      6788424.73      2762692.71      6787977.29
      2762523.58      6788005.59      2762064.02      6787662.95
      2761855.93      6787761.51      2761736.51      6787670.81
      2761676.09      6787476.39      2761822.97      6787062.39
      2761379.29      6786409.64      2761414.91      6786150.92
      2761134.07      6785914.31      2761228.14      6785066.94
      2761524.95      6784650.89      2761375.64      6784190.79
      2761475.52      6784021.47      2761098.99      6783784.52
      2760827.64      6783349.17      2760425.50      6780971.17
      2760727.05      6777021.43      2760934.21      6776763.83
      2761276.27      6776742.53      2761126.00      6775961.00

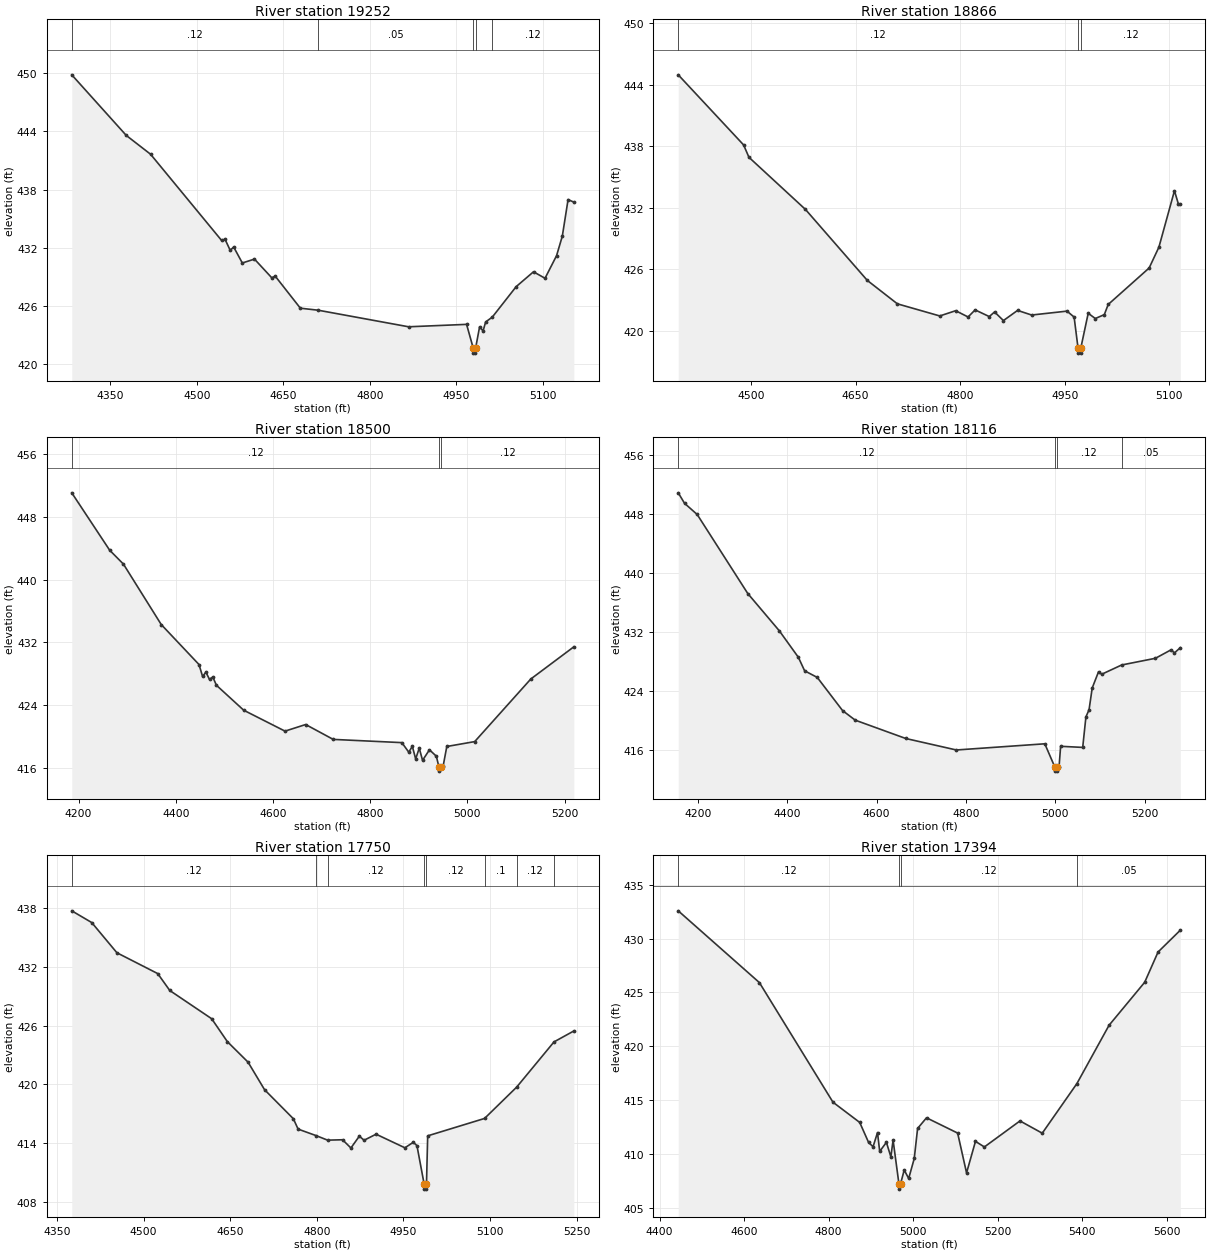
Type RM Length L Ch R = 1,19252,386,386,386
BEGIN DESCRIPTION:
Pickens Branch 39.0
END DESCRIPTION:
XS GIS Cut Line= 3
      2764825.98      6790711.01      2764226.00      6791111.00
      2764075.99      6791111.00
#Sta/Elev= 30
  4283.1  449.85  4377.7  443.59  4419.8  441.65  4543.0  432.75  4549.0  432.87
  4558.0  431.72  4564.0  432.07  4579.0  430.42  4600.1  430.82  4630.1  428.89
  4636.1  429.06  4679.7  425.75  4710.8  425.54  4867.5  423.83  4968.1  424.08
  4979.7  421.61  4979.9  421.11  4983.4  421.11  4983.7  421.61  4990.7  423.83
  4996.7  423.40  5001.2  424.33  5012.7  424.83  5054.2  427.98  5084.2  429.51
  5104.2  428.84  5124.2  431.17  5134.2  433.19  5144.2  436.97  5154.2  436.70
#Mann=5,-1,0
  4283.1    0.12       0  4710.8    0.05       0  4979.7    0.05       0
  4983.7    0.05       0  5012.7    0.12       0
Bank Sta=4979.7,4983.7
Exp/Cntr=0.3,0.1

Type RM Length L Ch R = 1,18866,366,366,366
BEGIN DESCRIPTION:
Pickens Branch 38.0
END DESCRIPTION:
XS GIS Cut Line= 3
      2764726.03      6790660.99      2764126.00      6790761.00
      2764026.01      6790810.99
#Sta/Elev= 30
  4395.7  444.95  4489.5  438.12  4497.1  436.92  4578.2  431.84  4666.9  424.93
  4710.0  422.65  4770.8  421.47  4793.6  421.98  4811.4  421.37  4821.5  422.06
  4841.8  421.41  4849.4  421.86  4862.1  421.02  4882.4  422.01  4902.6  421.56
  4953.3  421.94  4963.5  421.36  4969.1  418.35  4969.3  417.85  4972.8  417.85
  4973.1  418.35  4983.7  421.73  4993.9  421.22  5006.8  421.60  5012.4  422.59
  5071.1  426.14  5085.1  428.17  5107.4  433.66  5113.0  432.38  5115.8  432.38
#Mann=3,-1,0
  4395.7    0.12       0  4969.1    0.07       0  4973.1    0.12       0
Bank Sta=4969.1,4973.1
Exp/Cntr=0.3,0.1

Type RM Length L Ch R = 1,18500,384,384,384
BEGIN DESCRIPTION:
Pickens Branch 37.0
END DESCRIPTION:
XS GIS Cut Line= 3
      2764676.03      6789860.97      2764076.00      6790411.00
      2763870.98      6790488.32
#Sta/Elev= 30
  4186.0  451.01  4264.0  443.72  4292.4  441.95  4370.1  434.28  4447.8  429.20
  4455.2  427.68  4462.0  428.24  4469.4  427.30  4476.2  427.62  4483.6  426.57
  4539.7  423.40  4624.8  420.74  4667.3  421.58  4724.0  419.69  4865.2  419.28
  4879.4  418.07  4886.8  418.81  4893.6  417.21  4901.0  418.58  4907.8  417.03
  4922.0  418.37  4936.2  417.55  4941.6  416.16  4941.8  415.66  4945.6  416.16
  4950.3  416.35  4957.7  418.79  5015.1  419.41  5130.5  427.36  5219.1  431.45
#Mann=3,-1,0
  4186.0    0.12       0  4941.6    0.07       0  4945.6    0.12       0
Bank Sta=4941.6,4945.6
Exp/Cntr=0.3,0.1

Type RM Length L Ch R = 1,18116,366,366,366
BEGIN DESCRIPTION:
Pickens Branch 36.0
END DESCRIPTION:
XS GIS Cut Line= 3
      2764526.00      6789511.00      2763926.00      6790111.00
      2763729.68      6790303.39
#Sta/Elev= 30
  4156.1  450.89  4170.2  449.47  4198.5  447.95  4311.7  437.22  4382.4  432.15
  4424.8  428.57  4438.9  426.73  4467.2  425.83  4523.8  421.33  4552.1  420.03
  4665.2  417.54  4778.4  415.98  4976.3  416.82  4999.1  413.61  4999.3  413.11
  5002.8  413.11  5003.1  413.61  5008.1  413.61  5011.7  416.48  5061.1  416.33
  5068.3  420.47  5075.3  421.44  5082.4  424.40  5096.6  426.61  5103.6  426.26
  5148.3  427.52  5223.9  428.43  5259.2  429.59  5266.3  429.15  5279.5  429.87
#Mann=4,-1,0
  4156.1    0.12       0  4999.1    0.07       0  5003.1    0.12       0
  5148.3    0.05       0
Bank Sta=4999.1,5003.1
Exp/Cntr=0.3,0.1

Type RM Length L Ch R = 1,17750,356,356,356
BEGIN DESCRIPTION:
Pickens Branch 35.0
END DESCRIPTION:
XS GIS Cut Line= 3
      2764368.85      6789385.24      2763876.00      6789761.00
      2763725.97      6789961.04
#Sta/Elev= 30
  4375.6  437.75  4410.2  436.55  4453.8  433.46  4524.5  431.33  4545.4  429.60
  4618.0  426.71  4645.1  424.37  4681.0  422.27  4709.6  419.45  4759.5  416.48
  4767.7  415.42  4799.1  414.75  4818.8  414.29  4844.7  414.33  4859.2  413.49
  4873.8  414.70  4882.0  414.28  4902.8  414.90  4952.7  413.51  4967.3  414.07
  4973.6  413.73  4986.1  409.78  4986.3  409.28  4989.8  409.28  4990.1  409.78
  4992.2  414.73  5090.7  416.51  5146.4  419.72  5211.0  424.34  5245.4  425.46
#Mann=8,-1,0
  4375.6    0.12       0  4799.1     0.1       0  4818.8    0.12       0
  4986.1    0.07       0  4990.1    0.12       0  5090.7     0.1       0
  5146.4    0.12       0  5211.0    0.05       0
Bank Sta=4986.1,4990.1
Exp/Cntr=0.3,0.1

Type RM Length L Ch R = 1,17394,471,471,471
BEGIN DESCRIPTION:
Pickens Branch 34.0
END DESCRIPTION:
XS GIS Cut Line= 3
      2764253.59      6789285.42      2763726.00      6789461.00
      2763125.99      6789661.00
#Sta/Elev= 30
  4444.0  432.59  4636.1  425.92  4810.3  414.80  4873.6  412.92  4894.6  411.06
  4905.2  410.66  4915.7  411.98  4920.9  410.23  4936.8  411.07  4947.3  409.72
  4952.6  411.27  4966.4  407.22  4966.7  406.72  4970.4  407.22  4978.9  408.50
  4989.5  407.71  5002.7  409.57  5010.6  412.36  5031.7  413.35  5105.4  411.93
  5126.5  408.23  5147.6  411.16  5168.7  410.64  5253.0  413.06  5305.7  411.92
  5387.7  416.53  5463.8  421.95  5548.2  425.95  5579.8  428.76  5632.5  430.79
#Mann=4,-1,0
  4444.0    0.12       0  4966.4    0.07       0  4970.4    0.12       0
  5387.7    0.05       0
Bank Sta=4966.4,4970.4
Exp/Cntr=0.3,0.1

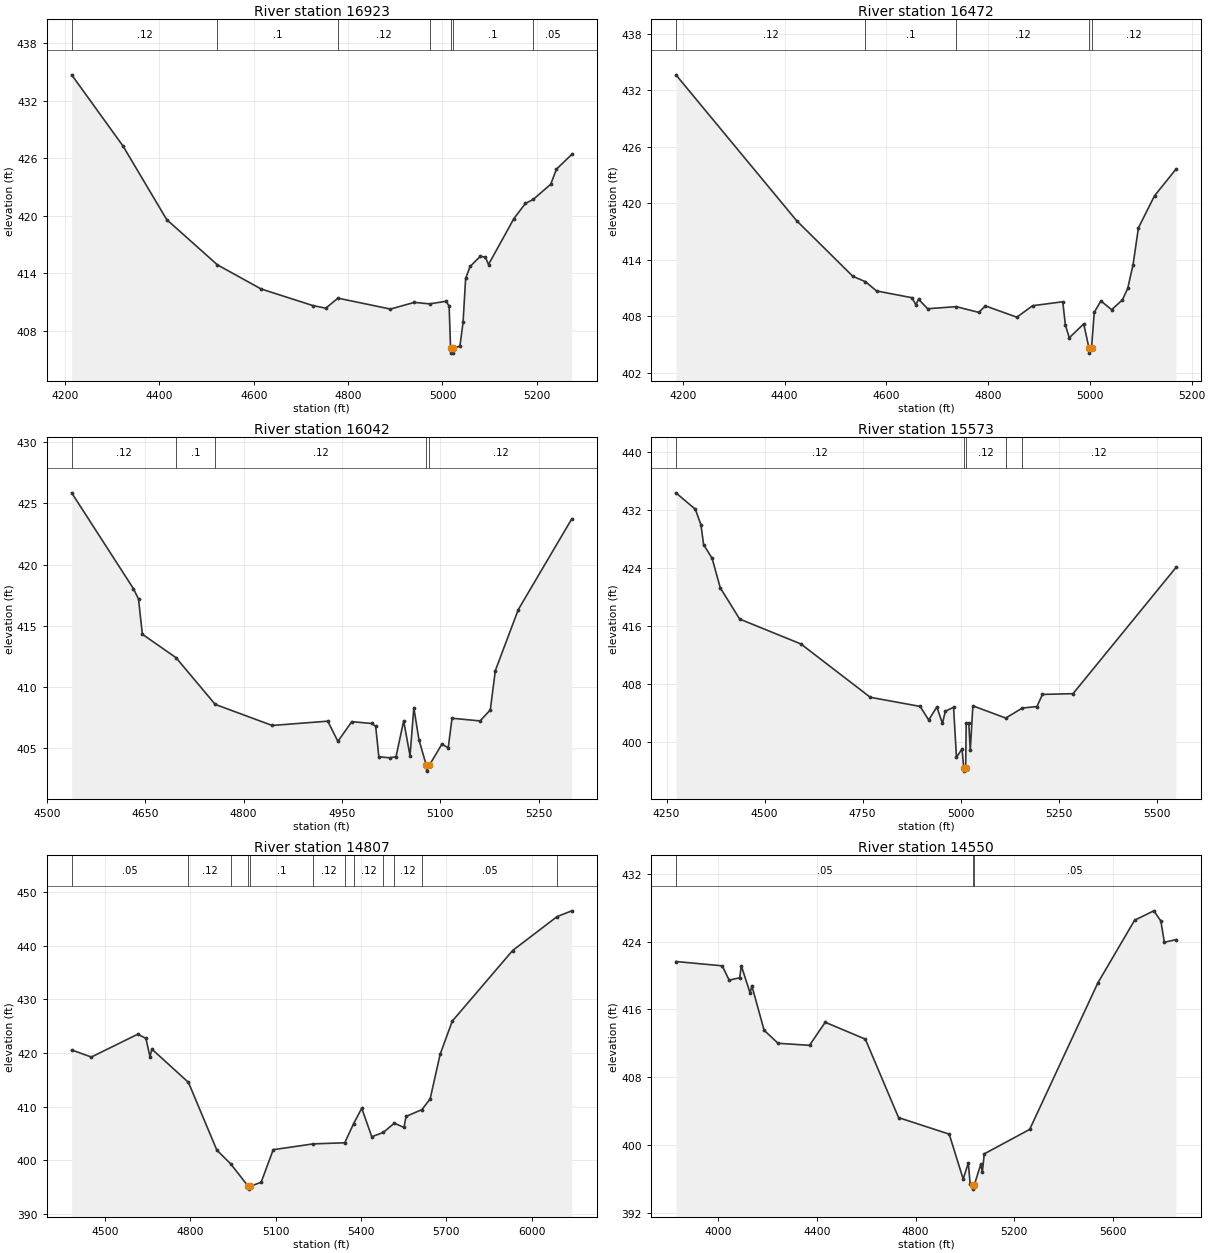
Type RM Length L Ch R = 1,16923,451,451,451
BEGIN DESCRIPTION:
Pickens Branch 33.0
END DESCRIPTION:
XS GIS Cut Line= 3
      2764026.03      6788910.98      2763376.00      6789361.00
      2763125.96      6789461.02
#Sta/Elev= 30
  4214.1  434.72  4322.9  427.29  4415.5  419.61  4522.9  414.89  4615.5  412.37
  4725.0  410.64  4752.7  410.36  4778.4  411.41  4889.8  410.27  4940.5  410.97
  4972.7  410.81  5007.4  411.08  5014.1  410.60  5017.2  406.17  5017.7  405.67
  5021.4  405.67  5021.9  406.17  5037.0  406.40  5043.7  408.90  5049.1  413.46
  5058.6  414.72  5080.1  415.77  5090.9  415.70  5097.6  414.92  5151.4  419.71
  5175.7  421.29  5192.8  421.73  5229.5  423.30  5241.6  424.87  5274.0  426.41
#Mann=7,-1,0
  4214.1    0.12       0  4522.9     0.1       0  4778.4    0.12       0
  4972.7     0.1       0  5017.2    0.07       0  5021.9     0.1       0
  5192.8    0.05       0
Bank Sta=5017.2,5021.9
Exp/Cntr=0.3,0.1

Type RM Length L Ch R = 1,16472,430,430,430
BEGIN DESCRIPTION:
Pickens Branch 32.0
END DESCRIPTION:
XS GIS Cut Line= 3
      2763975.96      6788861.01      2763176.00      6789061.00
      2763025.99      6789111.00
#Sta/Elev= 30
  4186.4  433.64  4423.4  418.15  4534.2  412.22  4558.9  411.65  4580.6  410.67
  4650.2  409.95  4657.9  409.21  4663.1  409.79  4681.1  408.78  4737.2  409.00
  4781.6  408.39  4794.5  409.08  4856.4  407.88  4887.3  409.10  4946.6  409.52
  4951.7  407.07  4959.4  405.69  4987.8  407.17  4998.3  404.56  4998.8  404.06
  5003.1  404.56  5008.4  408.39  5021.5  409.61  5042.6  408.68  5063.7  409.71
  5074.2  410.93  5084.8  413.48  5095.3  417.38  5126.9  420.78  5169.1  423.62
#Mann=5,-1,0
  4186.4    0.12       0  4558.9     0.1       0  4737.2    0.12       0
  4998.3    0.07       0  5003.1    0.12       0
Bank Sta=4998.3,5003.1
Exp/Cntr=0.3,0.1

Type RM Length L Ch R = 1,16042,469,469,469
BEGIN DESCRIPTION:
Pickens Branch 31.0
END DESCRIPTION:
XS GIS Cut Line= 3
      2763526.00      6788461.00      2763126.00      6788711.00
      2762976.02      6788960.96
#Sta/Elev= 30
  4537.5  425.87  4631.8  418.04  4639.5  417.20  4645.4  414.32  4696.7  412.41
  4756.6  408.59  4843.5  406.87  4928.4  407.22  4943.8  405.57  4965.0  407.18
  4995.6  407.03  5001.5  406.79  5006.3  404.31  5022.8  404.23  5032.5  404.31
  5044.2  407.25  5053.9  404.39  5059.7  408.32  5067.5  405.71  5078.6  403.64
  5079.3  403.14  5083.6  403.64  5102.5  405.34  5112.2  405.05  5118.0  407.46
  5160.8  407.24  5176.4  408.14  5184.1  411.35  5219.1  416.33  5300.7  423.74
#Mann=5,-1,0
  4537.5    0.12       0  4696.7     0.1       0  4756.6    0.12       0
  5078.6    0.07       0  5083.6    0.12       0
Bank Sta=5078.6,5083.6
Exp/Cntr=0.3,0.1

Type RM Length L Ch R = 1,15573,766,766,766
BEGIN DESCRIPTION:
Pickens Branch 30.0
END DESCRIPTION:
XS GIS Cut Line= 3
      2763475.96      6787911.03      2762926.00      6788411.00
      2762575.98      6788811.03
#Sta/Elev= 30
  4273.9  434.38  4323.5  432.11  4337.7  429.95  4344.5  427.22  4366.1  425.34
  4387.0  421.25  4436.4  416.94  4592.5  413.50  4769.5  406.13  4896.5  404.87
  4918.2  403.00  4939.1  404.79  4953.3  402.52  4960.7  404.21  4981.7  404.75
  4989.1  397.84  5003.3  399.00  5007.5  396.43  5008.2  395.93  5012.6  396.43
  5013.8  402.59  5020.5  402.59  5024.3  398.82  5030.9  404.95  5114.8  403.26
  5157.1  404.65  5194.2  404.85  5208.4  406.53  5286.2  406.63  5548.7  424.07
#Mann=5,-1,0
  4273.9    0.12       0  5007.5    0.07       0  5012.6    0.12       0
  5114.8     0.1       0  5157.1    0.12       0
Bank Sta=5007.5,5012.6
Exp/Cntr=0.3,0.1

Type RM Length L Ch R = 1,14807,257,257,257
BEGIN DESCRIPTION:
Pickens Branch 29.0
END DESCRIPTION:
XS GIS Cut Line= 3
      2762984.47      6787602.14      2762505.86      6787991.38
      2761697.11      6788795.95
#Sta/Elev= 30
  4383.1  420.57  4452.3  419.25  4615.3  423.50  4644.1  422.73  4658.4  419.28
  4664.9  420.73  4793.5  414.54  4893.3  401.93  4942.3  399.35  5004.1  395.16
  5004.8  394.66  5009.3  395.16  5049.1  395.94  5091.6  402.00  5231.3  403.08
  5343.0  403.29  5374.2  406.86  5402.7  409.72  5438.0  404.41  5478.6  405.22
  5517.2  406.94  5551.2  406.14  5558.3  408.19  5614.3  409.47  5643.1  411.46
  5678.4  419.78  5720.9  425.94  5933.0  439.08  6089.1  445.39  6140.8  446.47
#Mann=12,-1,0
  4383.1    0.05       0  4793.5    0.12       0  4942.3     0.1       0
  5004.1    0.07       0  5009.3     0.1       0  5231.3    0.12       0
  5343.0     0.1       0  5374.2    0.12       0  5478.6     0.1       0
  5517.2    0.12       0  5614.3    0.05       0  6089.1    0.12       0
Bank Sta=5004.1,5009.3
Exp/Cntr=0.3,0.1

Type RM Length L Ch R = 1,14550,317,317,317
BEGIN DESCRIPTION:
Pickens Branch 28.0
END DESCRIPTION:
XS GIS Cut Line= 3
      2763145.48      6787025.56      2762305.97      6787841.07
      2761665.57      6788407.12
#Sta/Elev= 30
  3829.6  421.66  4016.9  421.15  4045.2  419.46  4087.7  419.74  4094.6  421.14
  4130.1  417.93  4137.1  418.80  4186.7  413.55  4243.3  412.01  4370.6  411.77
  4434.2  414.49  4596.7  412.50  4731.2  403.24  4936.3  401.29  4992.9  395.99
  5013.7  397.89  5021.3  395.36  5032.9  395.30  5033.6  394.80  5038.1  395.30
  5063.9  397.71  5070.6  396.83  5078.2  398.96  5262.2  401.85  5538.2  419.13
  5687.1  426.53  5764.9  427.64  5793.3  426.45  5807.6  423.93  5854.7  424.24
#Mann=3,-1,0
  3829.6    0.05       0  5032.9    0.05       0  5038.1    0.05       0
Bank Sta=5032.9,5038.1
Exp/Cntr=0.3,0.1

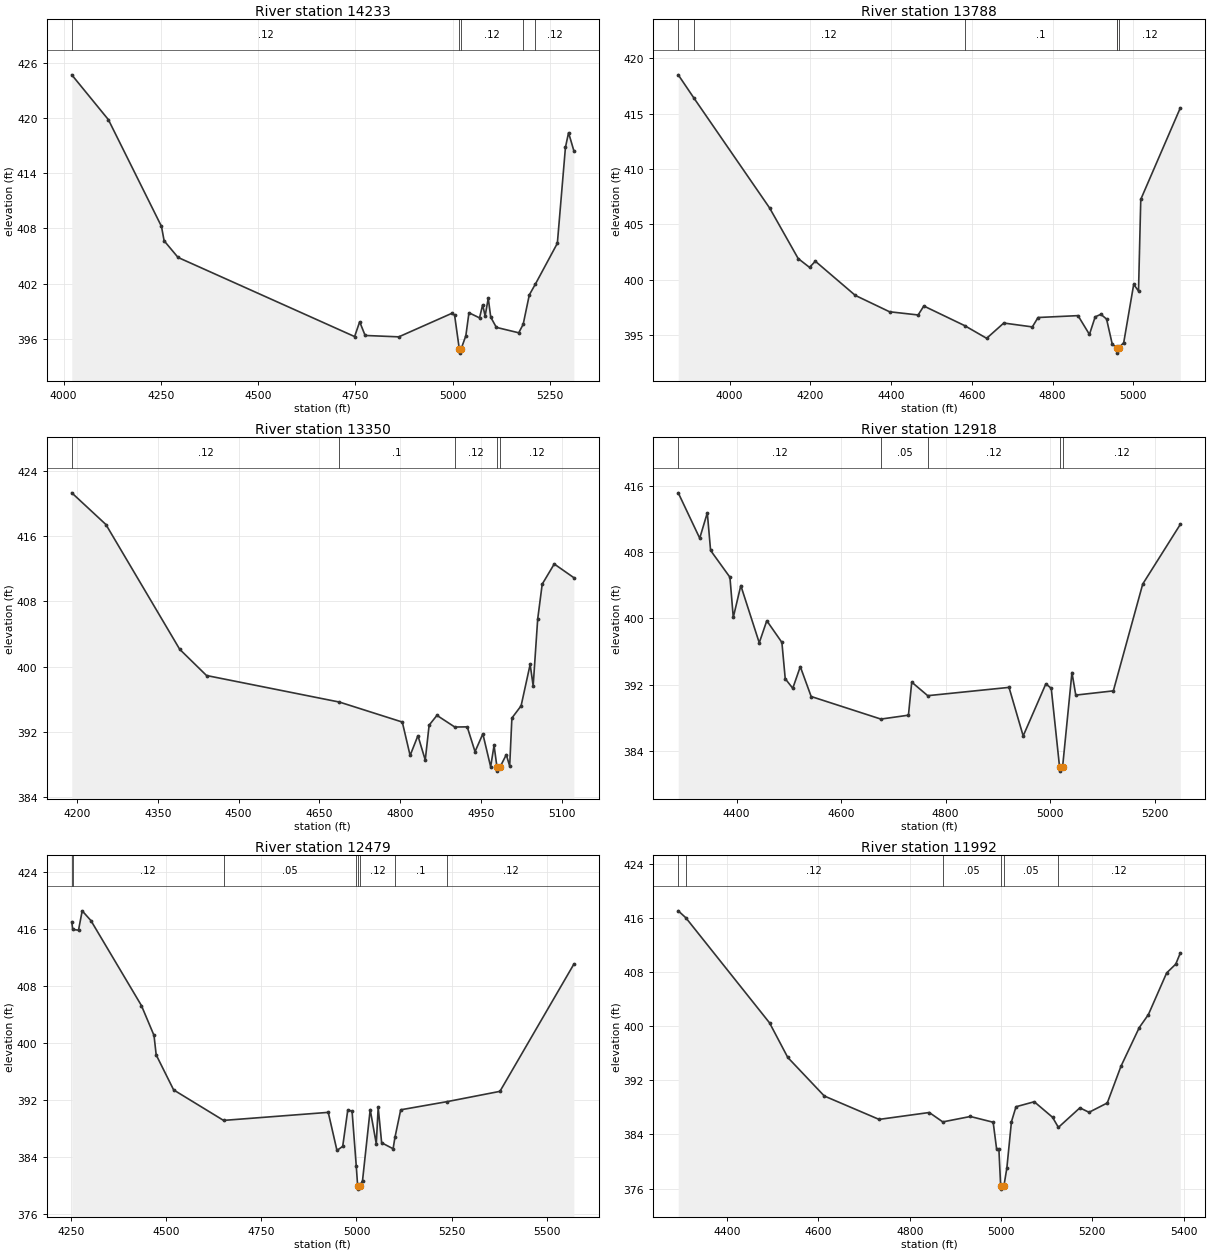
Type RM Length L Ch R = 1,14233,445,445,445
BEGIN DESCRIPTION:
Pickens Branch 27.0
END DESCRIPTION:
XS GIS Cut Line= 3
      2762626.01      6786860.99      2762076.00      6787661.00
      2761876.00      6787911.00
#Sta/Elev= 30
  4021.0  424.70  4115.1  419.83  4251.6  408.23  4258.5  406.66  4294.3  404.85
  4748.3  396.25  4761.3  397.86  4775.3  396.37  4861.9  396.22  4999.0  398.79
  5005.4  398.57  5017.3  394.95  5018.0  394.45  5022.5  394.95  5034.3  396.34
  5042.3  398.84  5069.5  398.28  5077.5  399.70  5083.9  398.49  5091.9  400.42
  5098.3  398.36  5112.7  397.25  5170.3  396.66  5181.7  397.58  5197.5  400.78
  5213.2  401.96  5269.6  406.39  5290.4  416.82  5298.4  418.41  5312.0  416.45
#Mann=5,-1,0
  4021.0    0.12       0  5017.3    0.07       0  5022.5    0.12       0
  5181.7     0.1       0  5213.2    0.12       0
Bank Sta=5017.3,5022.5
Exp/Cntr=0.3,0.1

Type RM Length L Ch R = 1,13788,438,438,438
BEGIN DESCRIPTION:
Pickens Branch 26.0
END DESCRIPTION:
XS GIS Cut Line= 3
      2762525.99      6786861.01      2761726.00      6787661.00
      2761675.98      6787761.04
#Sta/Elev= 30
  3873.0  418.51  3911.1  416.45  4099.3  406.47  4170.0  401.90  4198.2  401.10
  4212.4  401.66  4311.4  398.57  4396.2  397.09  4467.0  396.80  4481.1  397.61
  4582.0  395.84  4636.7  394.69  4679.1  396.07  4749.8  395.72  4763.9  396.57
  4862.9  396.74  4891.2  395.04  4905.4  396.63  4919.5  396.86  4933.6  396.43
  4947.8  394.14  4958.9  393.86  4959.3  393.85  4960.0  393.35  4964.6  393.85
  4976.1  394.30  5000.8  399.57  5012.7  398.96  5018.3  407.25  5116.2  415.52
#Mann=6,-1,0
  3873.0    0.05       0  3911.1    0.12       0  4582.0     0.1       0
  4958.9    0.12       0  4959.3    0.07       0  4964.6    0.12       0
Bank Sta=4959.3,4964.6
Exp/Cntr=0.3,0.1

Type RM Length L Ch R = 1,13350,432,432,432
BEGIN DESCRIPTION:
Pickens Branch 25.0
END DESCRIPTION:
XS GIS Cut Line= 3
      2762376.01      6786760.99      2761726.00      6787261.00
      2761625.98      6787311.01
#Sta/Elev= 30
  4190.5  421.33  4253.9  417.44  4390.8  402.14  4440.6  398.92  4687.4  395.66
  4804.0  393.21  4818.5  389.11  4833.0  391.54  4846.6  388.55  4853.8  392.83
  4868.3  394.03  4901.4  392.60  4924.5  392.62  4939.0  389.58  4953.5  391.76
  4968.0  387.72  4974.3  390.35  4979.7  387.69  4980.6  387.19  4985.4  387.69
  4997.0  389.21  5003.3  387.81  5007.4  393.70  5024.5  395.20  5041.3  400.28
  5046.9  397.65  5055.3  405.85  5063.7  410.13  5086.0  412.60  5122.4  410.92
#Mann=5,-1,0
  4190.5    0.12       0  4687.4     0.1       0  4901.4    0.12       0
  4979.7    0.07       0  4985.4    0.12       0
Bank Sta=4979.7,4985.4
Exp/Cntr=0.3,0.1

Type RM Length L Ch R = 1,12918,439,439,439
BEGIN DESCRIPTION:
Pickens Branch 24.0
END DESCRIPTION:
XS GIS Cut Line= 3
      2762116.13      6786403.25      2761676.00      6786961.00
      2761525.99      6787161.01
#Sta/Elev= 30
  4288.5  415.13  4329.6  409.66  4344.1  412.72  4350.4  408.19  4387.4  404.96
  4393.8  400.12  4408.2  403.96  4443.5  397.06  4457.9  399.72  4486.8  397.11
  4493.2  392.73  4507.6  391.58  4522.0  394.19  4542.8  390.59  4676.2  387.87
  4728.9  388.34  4735.2  392.32  4765.8  390.69  4921.3  391.69  4948.4  385.84
  4991.8  392.12  5002.1  391.57  5018.0  382.10  5018.9  381.60  5023.8  382.10
  5041.7  393.48  5049.0  390.76  5120.9  391.27  5177.1  404.14  5249.0  411.33
#Mann=5,-1,0
  4288.5    0.12       0  4676.2    0.05       0  4765.8    0.12       0
  5018.0    0.07       0  5023.8    0.12       0
Bank Sta=5018,5023.8
Exp/Cntr=0.3,0.1

Type RM Length L Ch R = 1,12479,487,487,487
BEGIN DESCRIPTION:
Pickens Branch 23.0
END DESCRIPTION:
XS GIS Cut Line= 3
      2762192.07      6786252.72      2761526.00      6786561.00
      2761482.36      6787144.61
#Sta/Elev= 30
  4251.9  416.99  4254.4  415.92  4269.6  415.81  4279.3  418.53  4302.2  417.16
  4434.9  405.23  4468.0  401.03  4473.7  398.30  4519.6  393.38  4650.7  389.10
  4925.8  390.23  4948.7  384.88  4963.8  385.46  4977.2  390.59  4988.4  390.38
  4999.4  382.69  5003.0  379.95  5004.0  379.45  5008.8  379.95  5015.9  380.66
  5036.0  390.62  5052.0  385.81  5057.0  390.93  5066.1  385.96  5096.2  385.12
  5101.0  386.70  5116.2  390.59  5238.5  391.74  5376.9  393.18  5571.1  411.04
#Mann=8,-1,0
  4251.9    0.05       0  4254.4    0.12       0  4650.7    0.05       0
  4999.4    0.12       0  5003.0    0.07       0  5008.8    0.12       0
  5101.0     0.1       0  5238.5    0.12       0
Bank Sta=5003,5008.8
Exp/Cntr=0.3,0.1

Type RM Length L Ch R = 1,11992,415,415,415
BEGIN DESCRIPTION:
Pickens Branch 22.0
END DESCRIPTION:
XS GIS Cut Line= 3
      2762125.97      6786161.00      2761426.00      6786161.00
      2761025.97      6786161.00
#Sta/Elev= 30
  4292.7  417.07  4309.4  416.04  4492.7  400.51  4532.7  395.39  4612.7  389.69
  4732.7  386.23  4842.7  387.25  4872.3  385.86  4932.7  386.66  4982.7  385.81
  4990.2  381.87  4995.2  381.87  4999.1  376.42  5000.2  375.92  5006.3  376.42
  5012.7  379.05  5022.7  385.88  5032.7  388.10  5072.7  388.84  5112.7  386.55
  5125.6  385.05  5172.7  387.94  5192.7  387.28  5232.7  388.66  5262.7  394.09
  5302.7  399.80  5322.7  401.72  5362.7  407.88  5382.7  409.19  5392.7  410.83
#Mann=6,-1,0
  4292.7    0.05       0  4309.4    0.12       0  4872.3    0.05       0
  4999.1    0.05       0  5006.3    0.05       0  5125.6    0.12       0
Bank Sta=4999.1,5006.3
Exp/Cntr=0.3,0.1

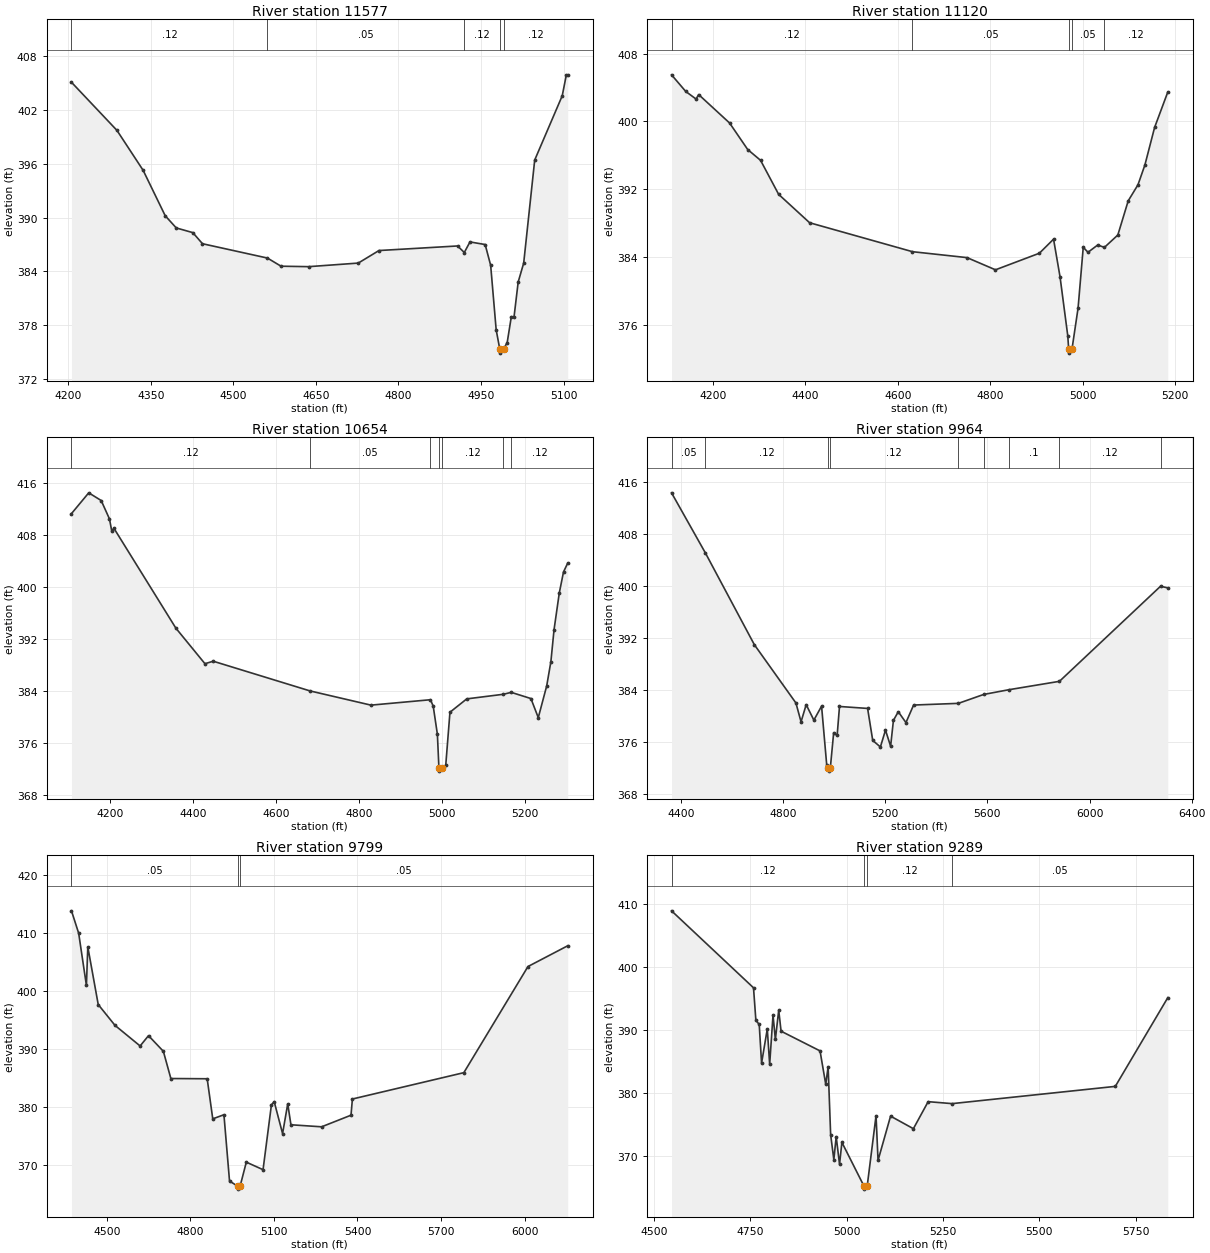
Type RM Length L Ch R = 1,11577,457,457,457
BEGIN DESCRIPTION:
Pickens Branch 21.0
END DESCRIPTION:
XS GIS Cut Line= 3
      2761925.99      6785961.00      2761126.00      6785911.00
      2761026.05      6785911.00
#Sta/Elev= 30
  4206.1  405.10  4288.7  399.73  4336.3  395.27  4376.4  390.20  4396.5  388.84
  4426.5  388.32  4444.1  387.08  4562.1  385.48  4586.8  384.57  4636.9  384.52
  4727.1  384.92  4764.7  386.32  4907.5  386.83  4919.7  386.10  4930.0  387.28
  4957.6  386.99  4967.6  384.67  4977.6  377.47  4984.0  375.37  4985.1  374.87
  4991.3  375.37  4997.6  376.04  5005.1  378.93  5010.1  378.93  5017.6  382.81
  5027.6  384.92  5047.6  396.42  5097.6  403.59  5105.1  405.93  5107.6  405.93
#Mann=5,-1,0
  4206.1    0.12       0  4562.1    0.05       0  4919.7    0.12       0
  4984.0    0.07       0  4991.3    0.12       0
Bank Sta=4984,4991.3
Exp/Cntr=0.3,0.1

Type RM Length L Ch R = 1,11120,466,466,466
BEGIN DESCRIPTION:
Pickens Branch 20.0
END DESCRIPTION:
XS GIS Cut Line= 3
      2761925.97      6785910.98      2761126.00      6785511.00
      2760975.97      6785611.02
#Sta/Elev= 30
  4109.9  405.50  4140.6  403.54  4163.0  402.64  4168.6  403.17  4235.6  399.81
  4274.8  396.68  4302.7  395.40  4341.9  391.38  4408.9  388.03  4631.7  384.61
  4749.9  383.91  4811.4  382.47  4906.5  384.43  4937.2  386.09  4951.2  381.66
  4968.0  374.67  4969.9  373.13  4971.0  372.63  4977.2  373.13  4990.3  377.95
  5001.5  385.13  5011.8  384.54  5032.8  385.40  5047.4  385.12  5076.4  386.58
  5098.9  390.62  5120.0  392.51  5135.0  394.85  5156.0  399.28  5184.6  403.47
#Mann=5,-1,0
  4109.9    0.12       0  4631.7    0.05       0  4969.9    0.05       0
  4977.2    0.05       0  5047.4    0.12       0
Bank Sta=4969.9,4977.2
Exp/Cntr=0.3,0.1

Type RM Length L Ch R = 1,10654,690,690,690
BEGIN DESCRIPTION:
Pickens Branch 19.0
END DESCRIPTION:
XS GIS Cut Line= 3
      2762117.58      6785139.08      2761226.00      6785111.00
      2760925.96      6785060.99
#Sta/Elev= 30
  4107.2  411.24  4148.8  414.43  4178.8  413.25  4198.8  410.42  4204.4  408.52
  4209.4  409.00  4358.9  393.65  4428.9  388.20  4448.9  388.58  4682.3  384.02
  4829.1  381.84  4972.6  382.67  4979.2  381.67  4989.2  377.37  4992.9  372.21
  4994.1  371.71  5000.5  372.21  5009.4  372.64  5019.5  380.75  5060.0  382.80
  5147.4  383.50  5167.3  383.80  5214.7  382.85  5232.4  379.92  5252.7  384.79
  5262.8  388.52  5270.4  393.42  5283.1  399.08  5293.2  402.28  5303.4  403.65
#Mann=7,-1,0
  4107.2    0.12       0  4682.3    0.05       0  4972.6    0.12       0
  4992.9    0.07       0  5000.5    0.12       0  5147.4     0.1       0
  5167.3    0.12       0
Bank Sta=4992.9,5000.5
Exp/Cntr=0.3,0.1

Type RM Length L Ch R = 1,9964,165,165,165
BEGIN DESCRIPTION:
Pickens Branch 18.0
END DESCRIPTION:
XS GIS Cut Line= 3
      2762160.98      6784687.26      2761526.50      6784626.32
      2760221.34      6784567.17
#Sta/Elev= 30
  4362.6  414.40  4495.6  405.12  4686.8  391.04  4849.8  382.06  4869.9  379.16
  4890.0  381.80  4920.1  379.42  4950.3  381.57  4970.4  372.53  4976.3  372.07
  4977.5  371.57  4984.6  372.07  4997.7  377.49  5011.3  377.06  5020.5  381.52
  5130.6  381.22  5150.7  376.29  5180.7  375.29  5200.7  377.88  5220.7  375.40
  5231.8  379.39  5250.8  380.71  5280.8  379.04  5310.8  381.74  5486.3  382.00
  5585.3  383.37  5684.2  384.10  5882.1  385.39  6278.0  400.02  6306.5  399.77
#Mann=9,-1,0
  4362.6    0.05       0  4495.6    0.12       0  4976.3    0.07       0
  4984.6    0.12       0  5486.3     0.1       0  5585.3    0.12       0
  5684.2     0.1       0  5882.1    0.12       0  6278.0     0.1       0
Bank Sta=4976.3,4984.6
Exp/Cntr=0.3,0.1

Type RM Length L Ch R = 1,9799,510,510,510
BEGIN DESCRIPTION:
Pickens Branch 17.0
END DESCRIPTION:
XS GIS Cut Line= 3
      2762141.76      6784510.15      2761476.00      6784461.00
      2760363.48      6784411.31
#Sta/Elev= 30
  4373.4  413.76  4399.2  409.90  4427.0  400.91  4432.0  407.55  4469.4  397.61
  4529.6  394.02  4619.8  390.47  4649.9  392.25  4703.2  389.55  4730.1  384.86
  4860.5  384.82  4880.5  377.91  4920.6  378.62  4940.7  367.19  4970.2  366.30
  4971.5  365.80  4978.6  366.30  5000.9  370.45  5061.0  369.15  5091.0  380.31
  5101.0  380.88  5131.1  375.37  5149.6  380.50  5161.1  376.89  5271.2  376.54
  5376.7  378.54  5381.7  381.33  5781.7  385.87  6011.9  404.16  6154.6  407.74
#Mann=3,-1,0
  4373.4    0.05       0  4970.2    0.05       0  4978.6    0.05       0
Bank Sta=4970.2,4978.6
Exp/Cntr=0.3,0.1

Type RM Length L Ch R = 1,9289,474,474,474
BEGIN DESCRIPTION:
Pickens Branch 16.0
END DESCRIPTION:
XS GIS Cut Line= 3
      2761844.12      6783803.21      2761476.00      6784061.00
      2760675.96      6784311.01
#Sta/Elev= 30
  4545.7  408.90  4758.4  396.71  4764.5  391.57  4773.2  390.90  4779.3  384.78
  4794.1  390.19  4800.3  384.60  4809.0  392.39  4815.1  388.53  4823.8  393.16
  4829.9  389.84  4931.0  386.72  4945.8  381.43  4952.0  384.22  4958.5  373.46
  4966.8  369.50  4972.9  373.14  4981.6  368.77  4987.7  372.24  5044.8  365.33
  5046.0  364.83  5053.4  365.33  5076.3  376.46  5081.5  369.38  5114.0  376.39
  5173.2  374.40  5211.5  378.68  5273.7  378.37  5697.1  381.10  5833.3  395.15
#Mann=4,-1,0
  4545.7    0.12       0  5044.8    0.07       0  5053.4    0.12       0
  5273.7    0.05       0
Bank Sta=5044.8,5053.4
Exp/Cntr=0.3,0.1

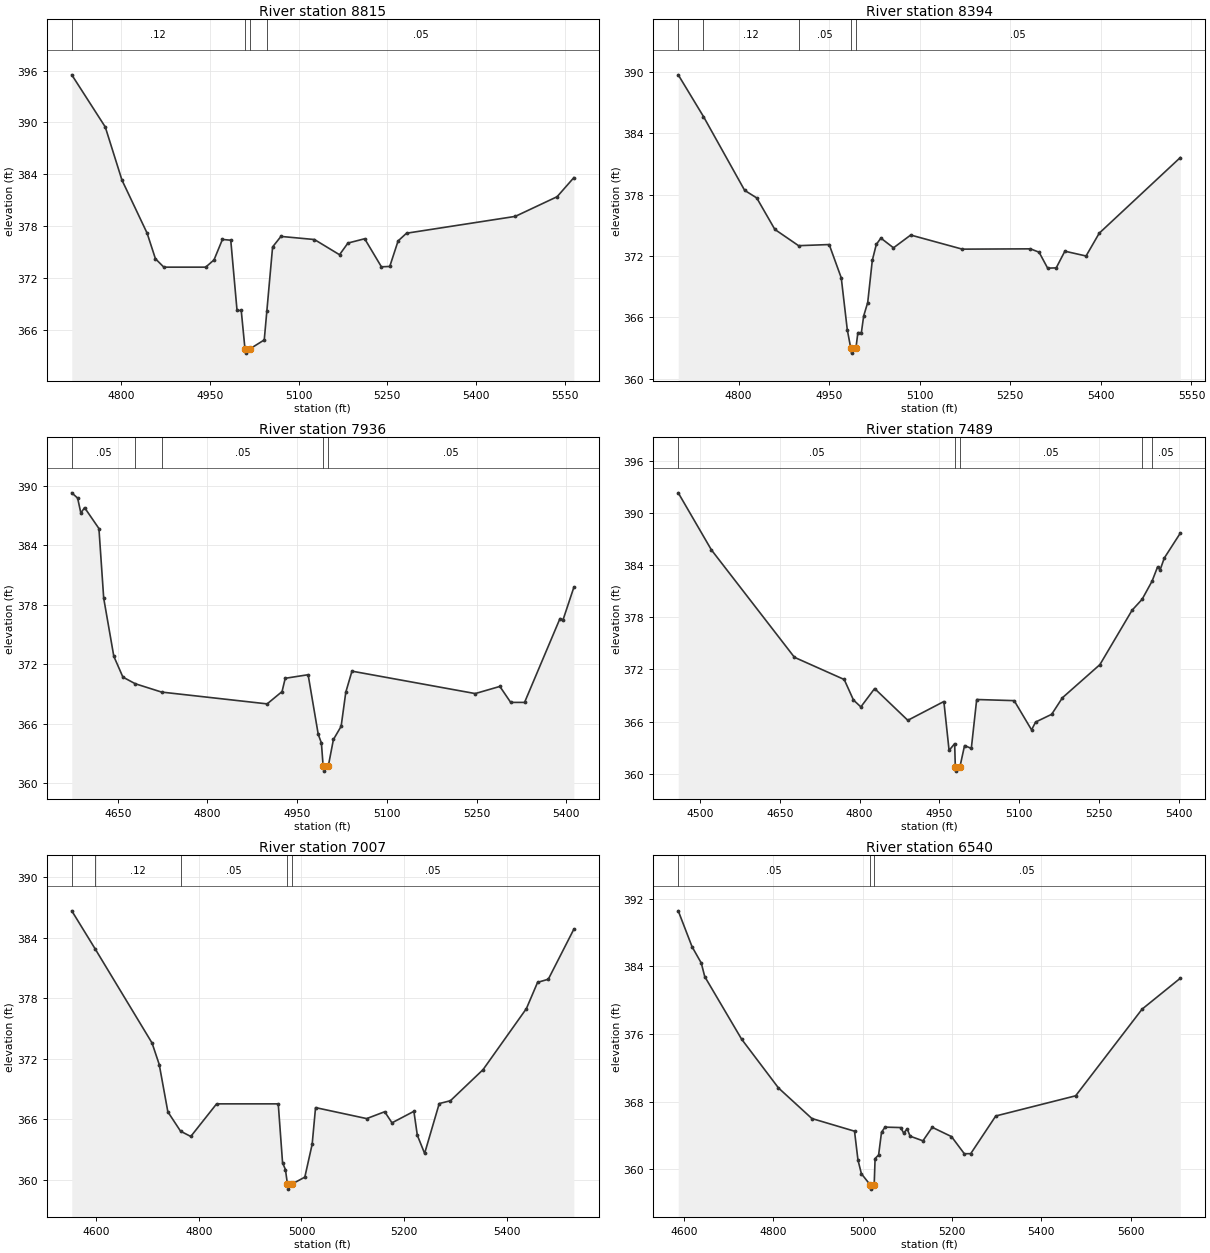
Type RM Length L Ch R = 1,8815,421,421,421
BEGIN DESCRIPTION:
Pickens Branch 15.0
END DESCRIPTION:
XS GIS Cut Line= 3
      2761326.00      6783611.00      2761126.00      6783811.00
      2760726.02      6784210.98
#Sta/Elev= 30
  4716.7  395.52  4773.3  389.48  4801.5  383.33  4844.0  377.18  4858.1  374.21
  4872.3  373.24  4943.0  373.24  4957.1  374.08  4971.3  376.45  4985.4  376.36
  4996.0  368.22  5003.1  368.22  5009.4  363.78  5010.6  363.28  5018.0  363.78
  5042.0  364.81  5046.4  368.17  5056.1  375.58  5070.2  376.80  5126.8  376.44
  5169.2  374.68  5183.4  376.03  5211.7  376.53  5240.0  373.28  5254.1  373.32
  5268.2  376.28  5282.4  377.17  5466.2  379.12  5536.9  381.40  5565.2  383.61
#Mann=4,-1,0
  4716.7    0.12       0  5009.4    0.07       0  5018.0    0.12       0
  5046.4    0.05       0
Bank Sta=5009.4,5018
Exp/Cntr=0.3,0.1

Type RM Length L Ch R = 1,8394,458,458,458
BEGIN DESCRIPTION:
Pickens Branch 14.0
END DESCRIPTION:
XS GIS Cut Line= 3
      2761226.03      6783461.00      2760926.00      6783461.00
      2760526.03      6783810.98
#Sta/Elev= 30
  4700.0  389.71  4741.8  385.63  4810.0  378.41  4830.0  377.67  4860.0  374.59
  4899.3  373.00  4950.0  373.11  4970.0  369.85  4980.0  364.76  4985.7  362.99
  4987.0  362.49  4994.3  362.99  4997.5  364.49  5003.3  364.49  5007.1  366.12
  5013.8  367.44  5021.4  371.56  5028.0  373.12  5035.6  373.74  5056.5  372.79
  5085.0  374.04  5170.4  372.66  5283.3  372.69  5297.6  372.36  5311.8  370.80
  5326.0  370.83  5340.3  372.46  5375.4  371.99  5397.2  374.22  5531.5  381.62
#Mann=5,-1,0
  4700.0    0.05       0  4741.8    0.12       0  4899.3    0.05       0
  4985.7    0.04       0  4994.3    0.05       0
Bank Sta=4985.7,4994.3
Exp/Cntr=0.3,0.1

Type RM Length L Ch R = 1,7936,447,447,447
BEGIN DESCRIPTION:
Pickens Branch 13.0
END DESCRIPTION:
XS GIS Cut Line= 3
      2761226.03      6782910.99      2760826.00      6783061.00
      2760426.04      6783160.99
#Sta/Elev= 30
  4573.2  389.27  4583.0  388.74  4588.4  387.23  4594.6  387.78  4618.6  385.67
  4626.6  378.64  4643.5  372.79  4658.7  370.69  4679.4  370.02  4723.4  369.18
  4899.9  367.99  4924.8  369.23  4930.1  370.57  4968.4  370.93  4985.3  364.92
  4990.6  364.05  4993.5  361.71  4994.7  361.21  5002.1  361.71  5010.7  364.40
  5023.6  365.73  5031.4  369.17  5041.7  371.29  5247.8  369.03  5289.0  369.75
  5307.1  368.14  5330.3  368.14  5389.5  376.59  5394.7  376.48  5412.7  379.74
#Mann=5,-1,0
  4573.2    0.05       0  4679.4    0.12       0  4723.4    0.05       0
  4993.5    0.04       0  5002.1    0.05       0
Bank Sta=4993.5,5002.1
Exp/Cntr=0.3,0.1

Type RM Length L Ch R = 1,7489,482,482,482
BEGIN DESCRIPTION:
Pickens Branch 12.0
END DESCRIPTION:
XS GIS Cut Line= 3
      2761187.51      6782484.84      2760676.00      6782661.00
      2760276.01      6782711.00
#Sta/Elev= 30
  4459.0  392.30  4521.4  385.74  4677.5  373.40  4771.1  370.85  4788.5  368.49
  4802.4  367.70  4828.3  369.81  4890.7  366.16  4958.5  368.32  4968.3  362.70
  4978.8  363.48  4980.0  360.82  4981.3  360.32  4988.7  360.82  4997.4  363.26
  5010.1  362.93  5020.2  368.55  5090.7  368.42  5123.4  365.06  5131.0  365.96
  5161.2  366.85  5181.4  368.75  5251.9  372.56  5312.4  378.81  5331.2  380.06
  5350.0  382.15  5360.3  383.78  5365.3  383.47  5372.9  384.80  5403.1  387.67
#Mann=5,-1,0
  4459.0    0.05       0  4980.0    0.04       0  4988.7    0.05       0
  5331.2    0.12       0  5350.0    0.05       0
Bank Sta=4980,4988.7
Exp/Cntr=0.3,0.1

Type RM Length L Ch R = 1,7007,467,467,467
BEGIN DESCRIPTION:
Pickens Branch 11.0
END DESCRIPTION:
XS GIS Cut Line= 3
      2760975.99      6782011.01      2760576.00      6782211.00
      2760226.00      6782610.99
#Sta/Elev= 30
  4552.2  386.66  4598.0  382.87  4708.7  373.56  4722.7  371.43  4739.5  366.74
  4764.3  364.82  4784.2  364.30  4834.5  367.53  4954.7  367.53  4963.1  361.69
  4968.7  361.02  4972.6  359.58  4973.9  359.08  4981.4  359.58  5006.5  360.27
  5020.8  363.53  5027.4  367.16  5127.1  366.07  5162.2  366.75  5176.4  365.65
  5219.1  366.79  5225.8  364.42  5240.0  362.62  5268.5  367.56  5290.3  367.84
  5353.9  370.92  5438.4  376.97  5460.2  379.57  5481.1  379.88  5530.9  384.84
#Mann=5,-1,0
  4552.2    0.05       0  4598.0    0.12       0  4764.3    0.05       0
  4972.6    0.04       0  4981.4    0.05       0
Bank Sta=4972.6,4981.4
Exp/Cntr=0.3,0.1

Type RM Length L Ch R = 1,6540,466,466,466
BEGIN DESCRIPTION:
Pickens Branch 10.0
END DESCRIPTION:
XS GIS Cut Line= 3
      2760926.01      6781661.00      2760526.00      6781761.00
      2760075.97      6782311.04
#Sta/Elev= 30
  4587.7  390.58  4618.6  386.33  4639.2  384.40  4647.0  382.79  4729.4  375.39
  4811.9  369.61  4886.6  365.99  4982.0  364.49  4989.7  361.08  4997.4  359.45
  5017.2  358.13  5018.5  357.63  5026.0  358.13  5028.0  361.25  5035.9  361.68
  5042.4  364.37  5050.3  364.97  5085.4  364.92  5091.9  364.26  5099.8  364.77
  5106.3  363.90  5135.0  363.35  5155.8  364.95  5198.9  363.85  5227.6  361.82
  5241.9  361.83  5297.9  366.29  5476.6  368.68  5625.2  378.94  5710.7  382.60
#Mann=3,-1,0
  4587.7    0.05       0  5017.2    0.04       0  5026.0    0.05       0
Bank Sta=5017.2,5026
Exp/Cntr=0.3,0.1