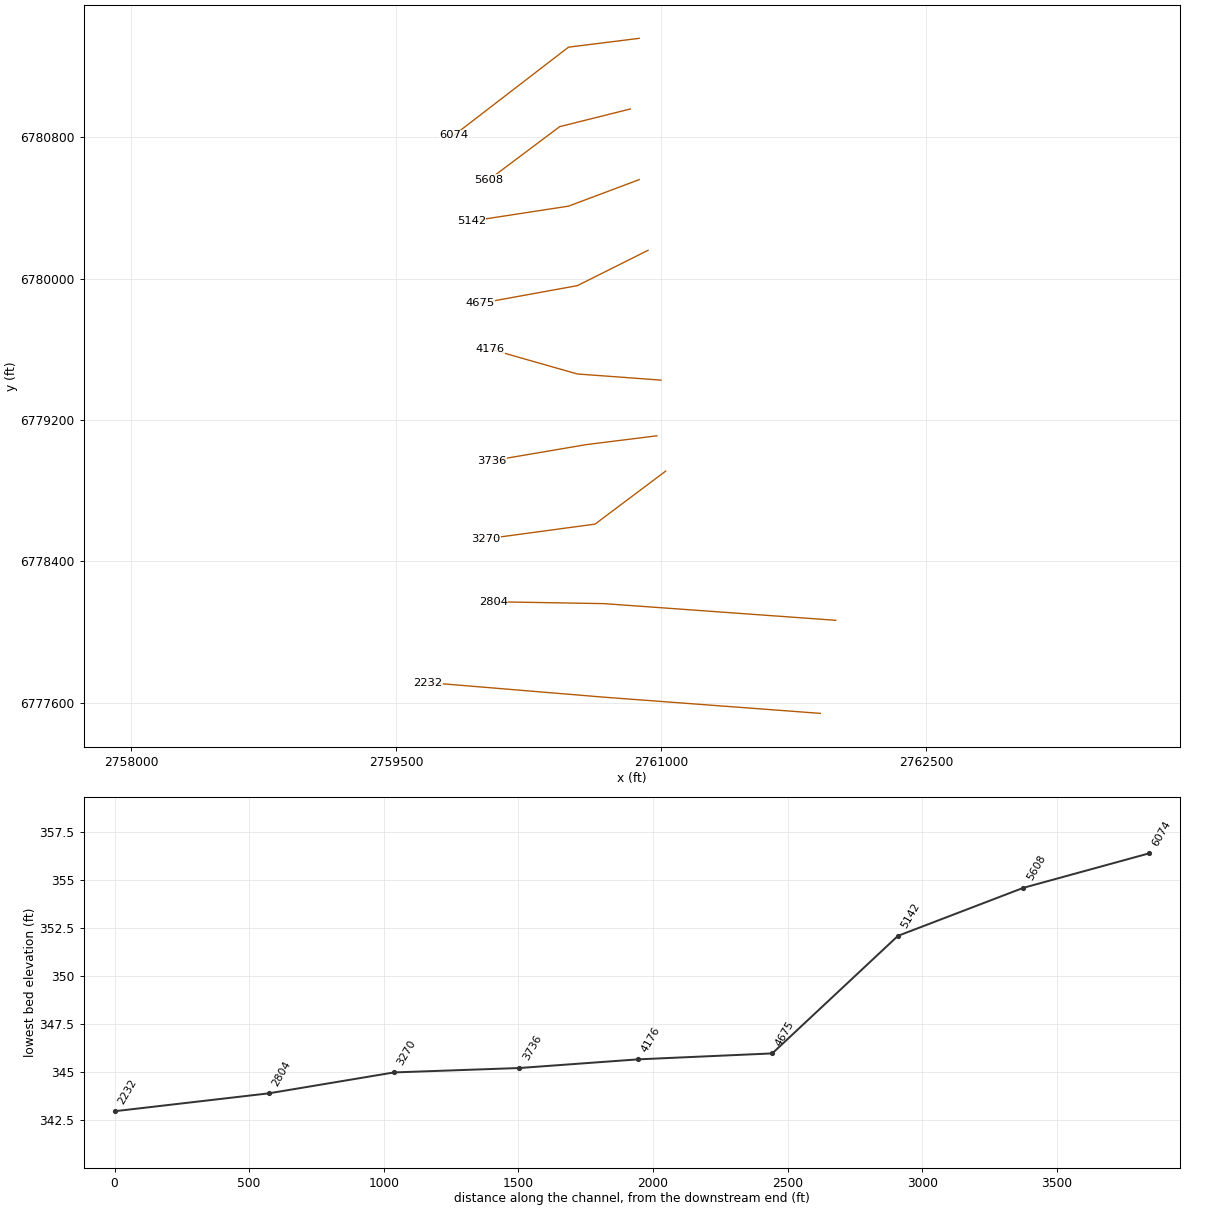
HEC-RAS study Pickens Branch.prj: Pickens Branch Base Level Engineering

--- Pickens Branch.g01 (geometry) --- (continued)

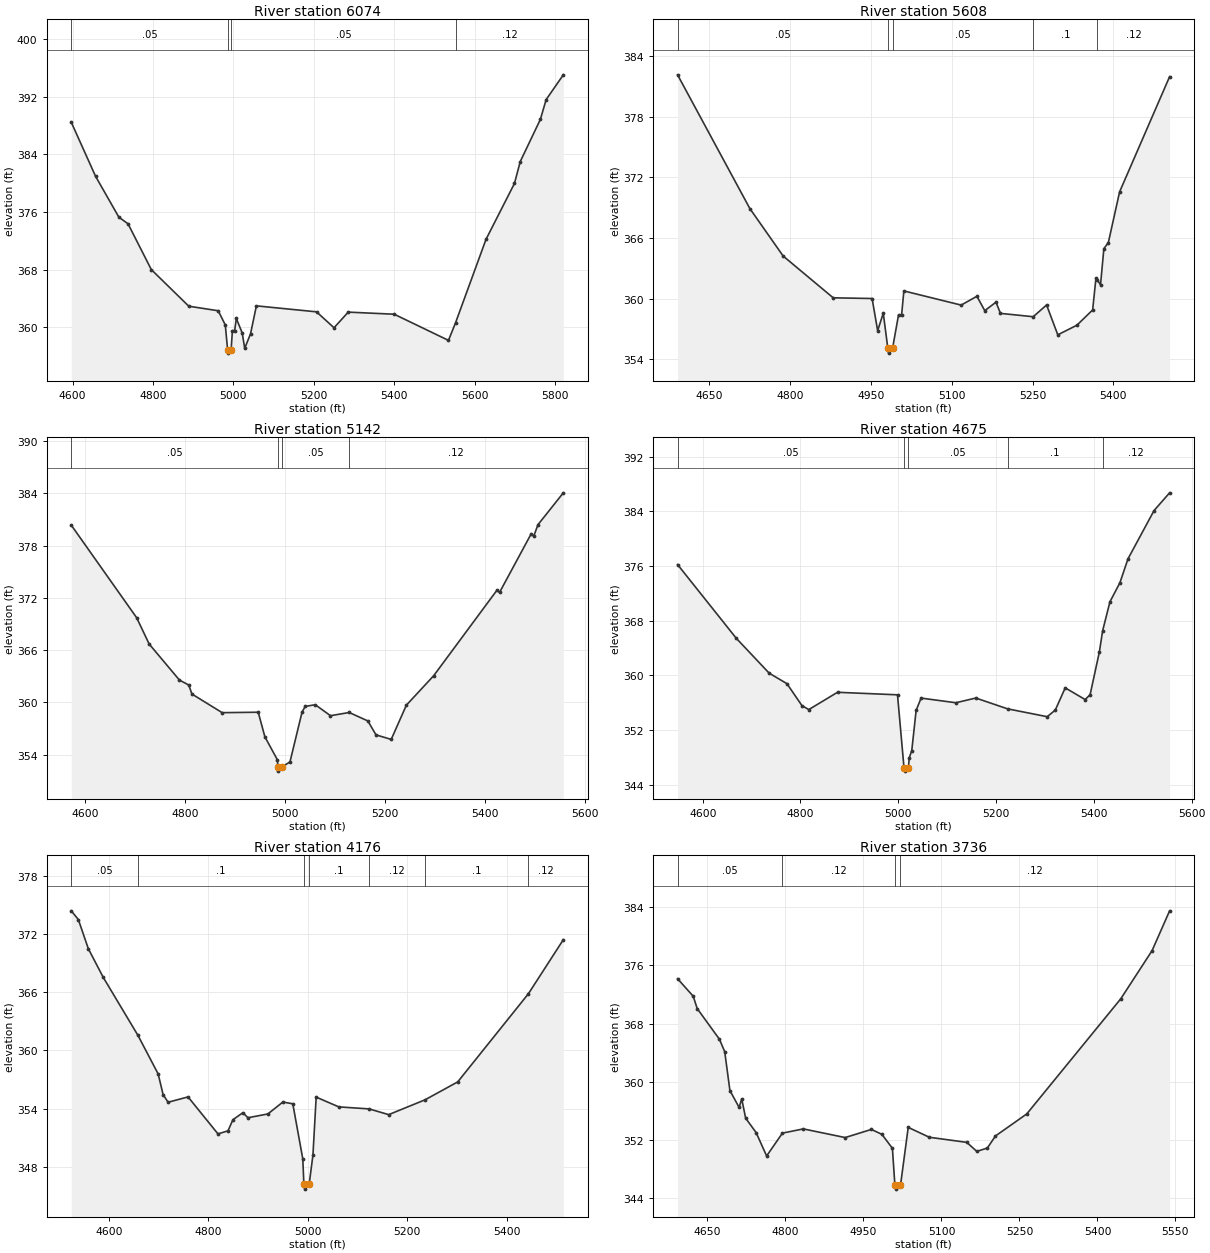
Type RM Length L Ch R = 1,6074,466,466,466
BEGIN DESCRIPTION:
Pickens Branch 9.0
END DESCRIPTION:
XS GIS Cut Line= 3
      2760875.98      6781361.00      2760476.00      6781311.00
      2759825.96      6780810.97
#Sta/Elev= 30
  4596.9  388.44  4657.3  380.94  4715.3  375.26  4738.0  374.35  4795.9  367.99
  4889.1  362.91  4962.2  362.28  4979.8  360.31  4985.5  356.90  4986.8  356.40
  4994.3  356.90  4997.5  359.52  5003.1  359.52  5007.2  361.21  5021.8  359.21
  5028.1  357.07  5042.6  359.09  5057.1  362.96  5206.6  362.13  5250.1  359.92
  5285.4  362.09  5399.6  361.80  5534.6  358.17  5552.2  360.61  5628.0  372.20
  5698.6  379.94  5713.1  382.99  5763.0  388.83  5777.5  391.59  5820.1  395.02
#Mann=4,-1,0
  4596.9    0.05       0  4985.5    0.04       0  4994.3    0.05       0
  5552.2    0.12       0
Bank Sta=4985.5,4994.3
Exp/Cntr=0.3,0.1

Type RM Length L Ch R = 1,5608,466,466,466
BEGIN DESCRIPTION:
Pickens Branch 8.0
END DESCRIPTION:
XS GIS Cut Line= 3
      2760825.97      6780960.99      2760426.00      6780861.00
      2760025.98      6780560.99
#Sta/Elev= 30
  4591.9  382.13  4725.9  368.91  4787.7  364.21  4880.5  360.08  4952.6  360.01
  4962.9  356.83  4973.3  358.56  4981.7  355.11  4983.0  354.61  4990.6  355.11
  5001.6  358.39  5007.3  358.39  5011.5  360.76  5117.7  359.36  5146.9  360.23
  5161.5  358.81  5182.3  359.65  5190.6  358.54  5251.3  358.21  5276.1  359.37
  5296.9  356.42  5332.3  357.37  5361.5  358.88  5367.7  362.06  5370.4  361.84
  5376.1  361.36  5382.3  364.94  5390.6  365.54  5411.5  370.56  5504.2  381.95
#Mann=5,-1,0
  4591.9    0.05       0  4981.7    0.04       0  4990.6    0.05       0
  5251.3     0.1       0  5370.4    0.12       0
Bank Sta=4981.7,4990.6
Exp/Cntr=0.3,0.1

Type RM Length L Ch R = 1,5142,467,467,467
BEGIN DESCRIPTION:
Pickens Branch 7.0
END DESCRIPTION:
XS GIS Cut Line= 3
      2760876.00      6780561.00      2760476.00      6780411.00
      2759925.85      6780326.50
#Sta/Elev= 30
  4572.8  380.34  4703.6  369.71  4728.5  366.70  4789.1  362.56  4807.8  361.99
  4814.0  360.96  4874.5  358.82  4946.6  358.87  4959.9  356.05  4984.9  353.41
  4985.8  352.61  4987.1  352.11  4994.7  352.61  5010.1  353.17  5034.2  358.88
  5040.5  359.54  5060.7  359.73  5091.1  358.47  5128.5  358.84  5165.8  357.87
  5182.1  356.27  5212.5  355.75  5242.8  359.68  5297.4  363.06  5424.0  372.88
  5429.1  372.62  5492.4  379.35  5497.4  379.06  5505.9  380.39  5556.6  384.05
#Mann=4,-1,0
  4572.8    0.05       0  4985.8    0.04       0  4994.7    0.05       0
  5128.5    0.12       0
Bank Sta=4985.8,4994.7
Exp/Cntr=0.3,0.1

Type RM Length L Ch R = 1,4675,499,499,499
BEGIN DESCRIPTION:
Pickens Branch 6.0
END DESCRIPTION:
XS GIS Cut Line= 3
      2760926.04      6780161.02      2760526.00      6779961.00
      2759975.98      6779861.00
#Sta/Elev= 30
  4548.6  376.20  4668.8  365.41  4735.9  360.32  4772.3  358.78  4803.0  355.57
  4817.0  354.99  4875.7  357.52  4998.4  357.15  5011.7  346.49  5013.0  345.99
  5020.6  346.49  5022.5  347.95  5027.6  349.00  5036.5  354.88  5046.7  356.67
  5117.8  355.99  5158.5  356.68  5223.5  355.10  5304.6  353.95  5321.1  354.92
  5341.4  358.17  5382.1  356.46  5392.3  357.16  5411.3  363.44  5418.0  366.54
  5432.9  370.76  5453.2  373.53  5469.8  377.04  5523.1  384.10  5554.9  386.69
#Mann=5,-1,0
  4548.6    0.05       0  5011.7    0.04       0  5020.6    0.05       0
  5223.5     0.1       0  5418.0    0.12       0
Bank Sta=5011.7,5020.6
Exp/Cntr=0.3,0.1

Type RM Length L Ch R = 1,4176,440,440,440
BEGIN DESCRIPTION:
Pickens Branch 5.0
END DESCRIPTION:
XS GIS Cut Line= 3
      2761000.21      6779426.18      2760526.00      6779461.00
      2760031.83      6779601.72
#Sta/Elev= 30
  4524.5  374.41  4538.7  373.51  4558.8  370.50  4588.9  367.53  4658.6  361.55
  4699.2  357.57  4709.2  355.43  4719.2  354.65  4759.3  355.20  4819.5  351.38
  4839.6  351.70  4849.6  352.85  4869.6  353.57  4879.7  353.05  4919.8  353.44
  4949.9  354.67  4969.9  354.49  4990.0  348.80  4992.2  346.18  4993.6  345.68
  5002.8  346.18  5010.4  349.19  5016.9  355.18  5062.4  354.17  5123.5  353.96
  5162.7  353.37  5235.8  354.90  5301.5  356.75  5443.6  365.85  5513.8  371.43
#Mann=7,-1,0
  4524.5    0.05       0  4658.6     0.1       0  4992.2    0.07       0
  5002.8     0.1       0  5123.5    0.12       0  5235.8     0.1       0
  5443.6    0.12       0
Bank Sta=4992.2,5002.8
Exp/Cntr=0.3,0.1

Type RM Length L Ch R = 1,3736,466,466,466
BEGIN DESCRIPTION:
Pickens Branch 4.0
END DESCRIPTION:
XS GIS Cut Line= 3
      2760975.95      6779110.99      2760576.00      6779061.00
      2760040.46      6778969.89
#Sta/Elev= 30
  4592.5  374.16  4622.7  371.74  4630.2  370.06  4673.1  365.83  4683.2  364.12
  4693.2  358.78  4710.9  356.46  4715.9  357.63  4723.5  354.98  4743.6  353.00
  4763.8  349.79  4794.2  352.93  4834.3  353.51  4914.9  352.32  4965.3  353.44
  4985.5  352.76  5005.7  350.84  5010.5  345.73  5012.0  345.23  5021.2  345.73
  5036.1  353.72  5076.7  352.36  5148.7  351.66  5168.0  350.42  5188.3  350.88
  5203.9  352.54  5264.1  355.57  5444.9  371.40  5505.1  378.02  5538.8  383.49
#Mann=4,-1,0
  4592.5    0.05       0  4794.2    0.12       0  5010.5    0.07       0
  5021.2    0.12       0
Bank Sta=5010.5,5021.2
Exp/Cntr=0.3,0.1

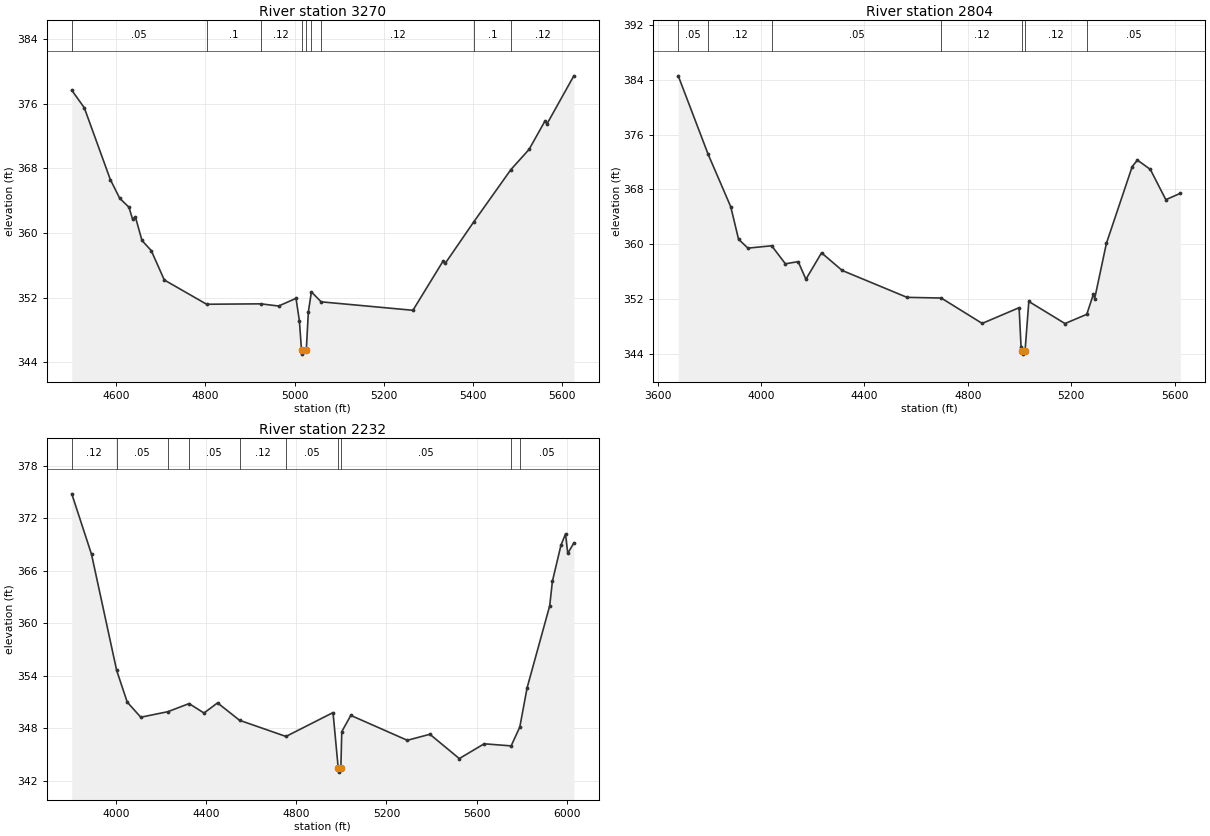
Type RM Length L Ch R = 1,3270,466,466,466
BEGIN DESCRIPTION:
Pickens Branch 3.0
END DESCRIPTION:
XS GIS Cut Line= 3
      2761025.98      6778910.99      2760626.00      6778611.00
      2760006.50      6778527.36
#Sta/Elev= 30
  4500.5  377.70  4528.6  375.52  4586.9  366.63  4607.8  364.32  4628.6  363.20
  4636.9  361.70  4643.2  361.98  4657.8  359.08  4678.6  357.83  4707.8  354.19
  4802.7  351.18  4924.2  351.23  4964.0  350.96  5003.0  351.91  5010.6  349.12
  5015.3  345.50  5016.8  345.00  5026.0  345.50  5030.7  350.24  5037.5  352.71
  5059.3  351.48  5265.0  350.43  5332.6  356.53  5337.7  356.27  5401.0  361.36
  5484.6  367.87  5525.2  370.36  5560.8  373.87  5565.8  373.56  5625.6  379.48
#Mann=9,-1,0
  4500.5    0.05       0  4802.7     0.1       0  4924.2    0.12       0
  5015.3    0.07       0  5026.0    0.12       0  5037.5    0.05       0
  5059.3    0.12       0  5401.0     0.1       0  5484.6    0.12       0
Bank Sta=5015.3,5026
Exp/Cntr=0.3,0.1

Type RM Length L Ch R = 1,2804,572,572,572
BEGIN DESCRIPTION:
Pickens Branch 2.0
END DESCRIPTION:
XS GIS Cut Line= 3
      2761988.68      6778066.58      2760676.00      6778161.00
      2760050.06      6778171.62
#Sta/Elev= 30
  3679.6  384.60  3795.4  373.12  3882.8  365.45  3912.9  360.71  3949.1  359.41
  4041.1  359.75  4094.0  357.12  4143.5  357.43  4173.5  354.86  4233.9  358.72
  4313.9  356.14  4564.6  352.21  4697.0  352.11  4855.3  348.40  4998.2  350.70
  5005.7  344.95  5010.1  344.41  5011.6  343.91  5021.2  344.41  5035.7  351.61
  5175.7  348.38  5259.9  349.73  5285.5  352.67  5290.5  352.04  5335.7  360.09
  5435.7  371.34  5455.7  372.28  5505.7  370.92  5565.7  366.49  5621.7  367.42
#Mann=7,-1,0
  3679.6    0.05       0  3795.4    0.12       0  4041.1    0.05       0
  4697.0    0.12       0  5010.1    0.07       0  5021.2    0.12       0
  5259.9    0.05       0
Bank Sta=5010.1,5021.2
Exp/Cntr=0.3,0.1

Type RM Length L Ch R = 1,2232,0,0,0
BEGIN DESCRIPTION:
Pickens Branch 1.0
END DESCRIPTION:
XS GIS Cut Line= 3
      2761901.48      6777539.70      2760679.17      6777631.19
      2759679.14      6777714.12
#Sta/Elev= 30
  3802.9  374.81  3890.5  367.90  4002.2  354.62  4049.1  350.99  4109.2  349.26
  4229.3  349.89  4323.7  350.82  4390.0  349.74  4450.2  350.90  4547.8  348.91
  4753.9  347.06  4962.9  349.79  4985.8  343.48  4987.4  342.98  4997.7  343.48
  5001.7  347.61  5041.8  349.47  5292.7  346.62  5393.0  347.31  5523.5  344.53
  5633.9  346.22  5753.7  345.98  5792.2  348.14  5824.5  352.62  5924.9  362.00
  5936.9  364.81  5975.0  368.94  5995.1  370.22  6005.1  368.00  6032.1  369.19
#Mann=10,-1,0
  3802.9    0.12       0  4002.2    0.05       0  4229.3    0.12       0
  4323.7    0.05       0  4547.8    0.12       0  4753.9    0.05       0
  4985.8    0.04       0  4997.7    0.05       0  5753.7    0.12       0
  5792.2    0.05       0
Bank Sta=4985.8,4997.7
Exp/Cntr=0.3,0.1

Chan Stop Cuts=-1