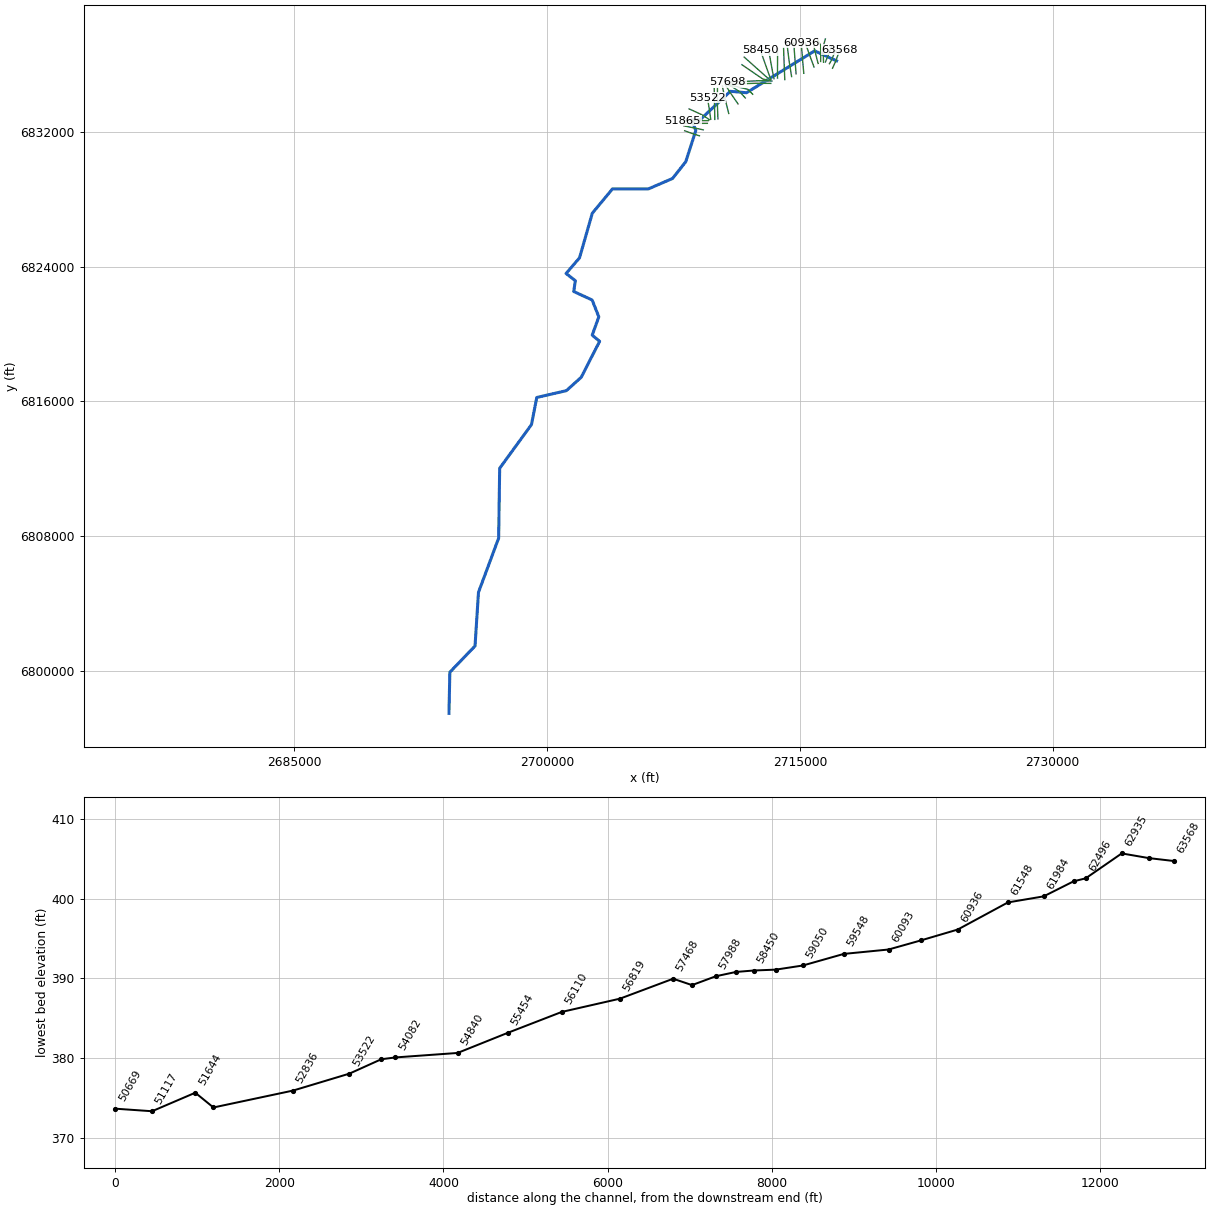
--- Prairie Creek.prj (project) ---

Proj Title=Prairie Creek Base Level Engineering
Current Plan=p01
Default Exp/Contr=0.3,0.1
English Units
Geom File=g01
Flow File=f01
Plan File=p01
BEGIN DESCRIPTION:
Prairie Creek
END DESCRIPTION:

--- Prairie Creek.p01 (plan) ---

Plan Title=Multiple Run
Short Identifier=Multiple
Geom File=g01
Flow File=f01
Subcritical Flow
K Sum by GR= 0
Std Step Tol= 0.01
Critical Tol= 0.01
Num of Std Step Trials= 20
Max Error Tol= 0.3
Flow Tol Ratio= 0.001
Split Flow NTrial= 30
Split Flow Tol= 0.02
Split Flow Ratio= 0.02
Log Output Level= 0
Friction Slope Method= 1
Unsteady Friction Slope Method= 2
Unsteady Bridges Friction Slope Method= 1
Parabolic Critical Depth
Global Vel Dist=  1 , 1 , 1
Global Log Level= 0
CheckData=True
Encroach Param= -1, 0, 0, 0
BEGIN DESCRIPTION:
Multiple Run
END DESCRIPTION:

--- Prairie Creek.f01 (steady flow) ---

Flow Title=Multiple
Number of Profiles=7
Profile Names=10-year,25-year,50-year,1pct_min,100-year,1pct_plu,500-year
River Rch & RM= Prairie Creek,Reach-1,63568
     651     874    1055     631    1259    2513    1793
River Rch & RM= Prairie Creek,Reach-1,60487
     780    1056    1281     769    1535    3063    2206
River Rch & RM= Prairie Creek,Reach-1,59050
     958    1303    1585     954    1904    3799    2748
River Rch & RM= Prairie Creek,Reach-1,55454
    1072    1454    1763    1057    2109    4209    3020
River Rch & RM= Prairie Creek,Reach-1,47344
    1452    2000    2453    1485    2962    5911    4325
River Rch & RM= Prairie Creek,Reach-1,45731
    1593    2203    2708    1643    3278    6541    4809
River Rch & RM= Prairie Creek,Reach-1,42817
    1756    2435    2998    1821    3634    7250    5343
River Rch & RM= Prairie Creek,Reach-1,40719
    1796    2485    3055    1852    3696    7375    5415
River Rch & RM= Prairie Creek,Reach-1,31958
    2309    3224    3989    2432    4852    9682    7188
River Rch & RM= Prairie Creek,Reach-1,22159
    2447    3424    4241    2588    5164   10304    7665
River Rch & RM= Prairie Creek,Reach-1,21201
    2453    3428    4243    2587    5162   10300    7649
River Rch & RM= Prairie Creek,Reach-1,18495
    2682    3761    4666    2851    5689   11351    8466
River Rch & RM= Prairie Creek,Reach-1,17956
    2668    3737    4632    2828    5643   11259    8382
River Rch & RM= Prairie Creek,Reach-1,16082
    2800    3929    4877    2981    5948   11868    8856
River Rch & RM= Prairie Creek,Reach-1,15448
    2843    3986    4945    3021    6027   12026    8962
River Rch & RM= Prairie Creek,Reach-1,12827
    2863    4014    4979    3041    6068   12108    9021
River Rch & RM= Prairie Creek,Reach-1,11691
    2890    4051    5023    3067    6119   12210    9090
River Rch & RM= Prairie Creek,Reach-1,10111
    2880    4033    4998    3050    6086   12143    9031
River Rch & RM= Prairie Creek,Reach-1,9082
    3018    4230    5246    3203    6391   12752    9492
River Rch & RM= Prairie Creek,Reach-1,7755
    3020    4228    5237    3194    6373   12716    9445
River Rch & RM= Prairie Creek,Reach-1,5045
    2989    4170    5154    3136    6257   12485    9228
Boundary for River Rch & Prof#=Prairie Creek,Reach-1,1
Up Type=0
Dn Type=3
Dn Slope=0.005
Boundary for River Rch & Prof#=Prairie Creek,Reach-1,2
Up Type=0
Dn Type=3
Dn Slope=0.005
Boundary for River Rch & Prof#=Prairie Creek,Reach-1,3
Up Type=0
Dn Type=3
Dn Slope=0.005
Boundary for River Rch & Prof#=Prairie Creek,Reach-1,4
Up Type=0
Dn Type=3
Dn Slope=0.005
Boundary for River Rch & Prof#=Prairie Creek,Reach-1,5
Up Type=0
Dn Type=3
Dn Slope=0.005
Boundary for River Rch & Prof#=Prairie Creek,Reach-1,6
Up Type=0
Dn Type=3
Dn Slope=0.005
Boundary for River Rch & Prof#=Prairie Creek,Reach-1,7
Up Type=0
Dn Type=3
Dn Slope=0.005

--- Prairie Creek.g01 (geometry) ---

Geom Title=Existing Conditions

River Reach=Prairie Creek,Reach-1
Reach XY= 30
      2717176.00      6836211.00      2715881.26      6836808.91
      2711832.75      6834320.10      2710873.53      6834405.55
      2709089.76      6832724.24      2708586.94      6832721.44
      2708825.02      6832071.27      2708223.91      6830216.26
      2707442.71      6829227.56      2706016.35      6828612.36
      2703877.98      6828607.96      2702681.52      6827163.44
      2701922.63      6824512.22      2701125.71      6823583.77
      2701672.86      6823159.36      2701581.04      6822515.93
      2702672.73      6822009.64      2703068.51      6821011.03
      2702676.55      6819921.63      2703118.51      6819557.38
      2702022.77      6817419.01      2701143.15      6816627.28
      2699386.63      6816221.12      2699070.94      6814608.75
      2697185.15      6812017.73      2697124.62      6807870.66
      2695927.36      6804651.35      2695722.46      6801462.46
      2694228.06      6799905.15      2694176.00      6797461.00

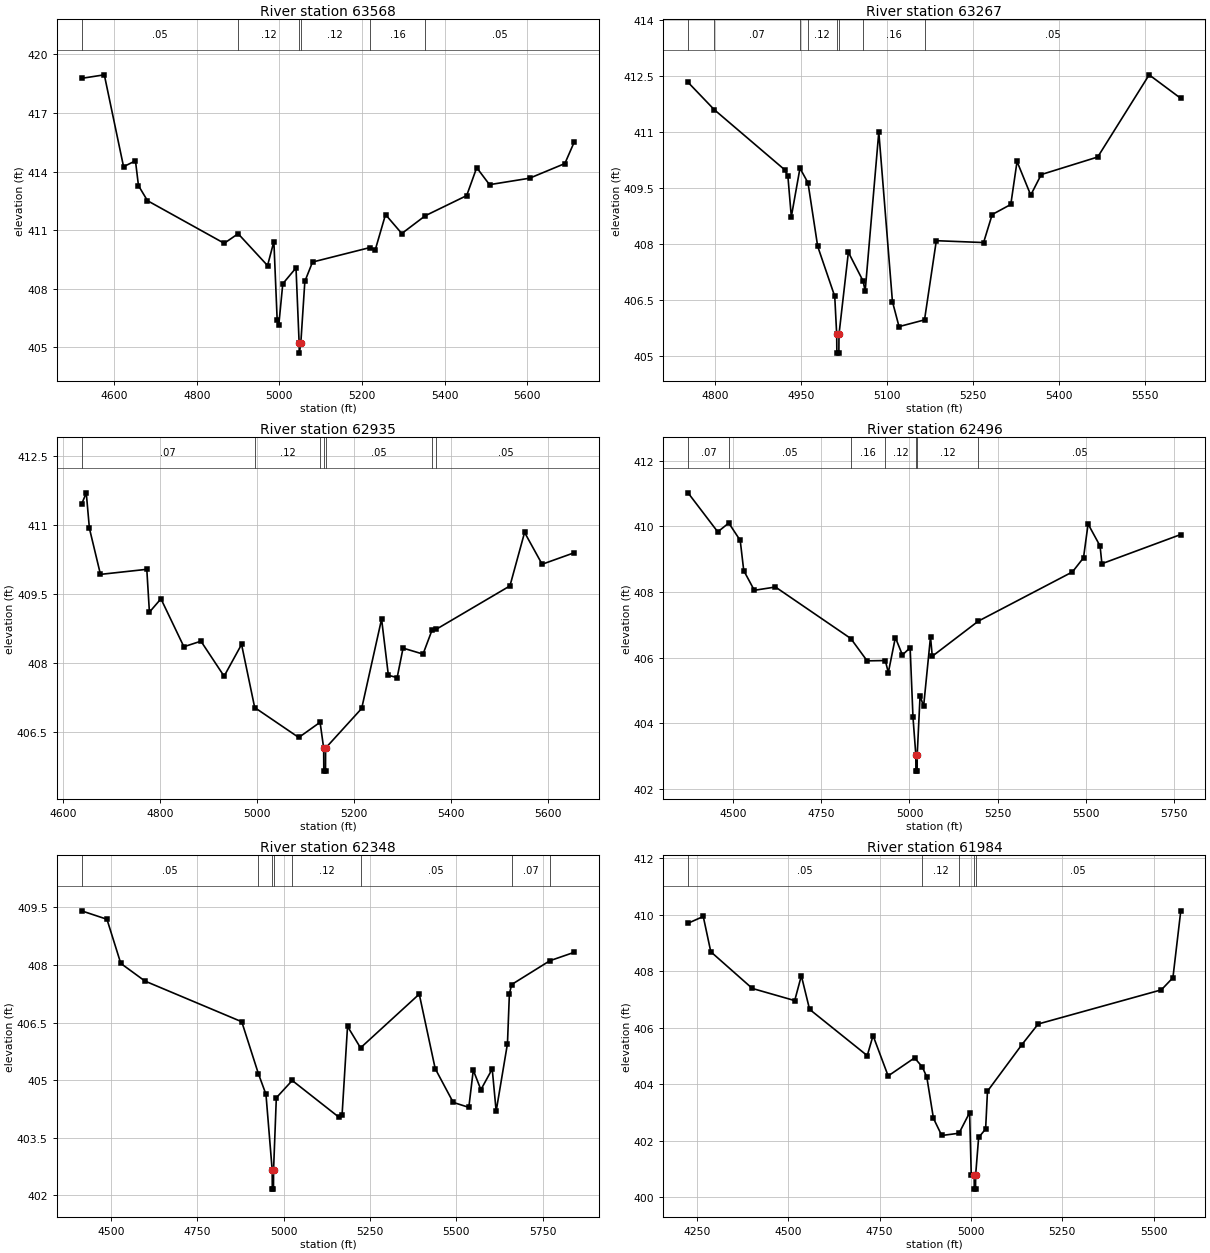
Type RM Length L Ch R = 1,63568,301,301,301
BEGIN DESCRIPTION:
Prairie Creek63568.221
END DESCRIPTION:
XS GIS Cut Line= 3
      2716939.12      6835774.91      2717132.15      6836213.29
      2717381.03      6836882.51
#Sta/Elev= 30
  4521.0  418.77  4576.1  418.95  4622.7  414.25  4651.5  414.55  4658.8  413.28
  4680.6  412.51  4866.4  410.33  4900.1  410.82  4971.3  409.19  4986.6  410.42
  4994.6  406.41  4998.6  406.17  5008.2  408.26  5040.2  409.07  5047.8  405.21
  5048.1  404.71  5051.8  405.21  5061.6  408.38  5080.2  409.37  5218.9  410.11
  5232.3  410.01  5256.9  411.80  5296.3  410.83  5353.2  411.74  5453.4  412.77
  5477.7  414.20  5508.7  413.33  5605.7  413.66  5691.1  414.41  5714.0  415.52
#Mann=6,-1,0
  4521.0    0.05       0  4900.1    0.12       0  5047.8    0.07       0
  5051.8    0.12       0  5218.9    0.16       0  5353.2    0.05       0
Bank Sta=5047.8,5051.8
Exp/Cntr=0.3,0.1

Type RM Length L Ch R = 1,63267,332,332,332
BEGIN DESCRIPTION:
Prairie Creek63267
END DESCRIPTION:
XS GIS Cut Line= 3
      2716755.12      6836044.14      2716876.52      6836258.20
      2717113.21      6836824.75
#Sta/Elev= 30
  4752.7  412.32  4798.3  411.59  4921.3  409.98  4927.0  409.81  4933.0  408.72
  4948.1  410.02  4962.1  409.63  4979.0  407.93  5008.8  406.59  5012.2  405.57
  5012.5  405.07  5016.0  405.07  5016.2  405.57  5032.6  407.77  5058.3  407.00
  5061.9  406.73  5085.7  410.99  5109.5  406.45  5121.0  405.78  5165.5  405.96
  5186.1  408.08  5268.6  408.03  5283.6  408.78  5316.1  409.05  5327.0  410.20
  5350.9  409.30  5369.2  409.85  5467.8  410.32  5557.6  412.52  5612.8  411.89
#Mann=8,-1,0
  4752.7    0.05       0  4798.3    0.07       0  4948.1    0.16       0
  4962.1    0.12       0  5012.2    0.07       0  5016.2    0.12       0
  5058.3    0.16       0  5165.5    0.05       0
Bank Sta=5012.2,5016.2
Exp/Cntr=0.3,0.1

Type RM Length L Ch R = 1,62935,439,439,439
BEGIN DESCRIPTION:
Prairie Creek62934.95
END DESCRIPTION:
XS GIS Cut Line= 3
      2716517.68      6836146.02      2716656.86      6836481.72
      2716886.64      6837093.17
#Sta/Elev= 30
  4638.5  411.45  4648.2  411.70  4654.7  410.93  4677.5  409.93  4773.1  410.04
  4778.5  409.11  4802.3  409.40  4849.6  408.36  4884.8  408.48  4932.6  407.72
  4968.6  408.41  4995.7  407.04  5086.6  406.39  5130.6  406.72  5138.0  406.16
  5138.3  405.66  5141.8  405.66  5142.0  406.16  5216.4  407.02  5257.5  408.96
  5271.5  407.74  5289.6  407.69  5301.8  408.33  5343.0  408.20  5361.9  408.73
  5370.5  408.74  5522.3  409.68  5552.5  410.84  5588.7  410.15  5655.1  410.40
#Mann=7,-1,0
  4638.5    0.07       0  4995.7    0.12       0  5130.6    0.05       0
  5138.0    0.07       0  5142.0    0.05       0  5361.9    0.12       0
  5370.5    0.05       0
Bank Sta=5138,5142
Exp/Cntr=0.3,0.1

Type RM Length L Ch R = 1,62496,148,148,148
BEGIN DESCRIPTION:
Prairie Creek62495.75
END DESCRIPTION:
XS GIS Cut Line= 4
      2716403.38      6836132.96      2716385.91      6836762.94
      2716420.88      6837189.69      2716513.02      6837516.66
#Sta/Elev= 30
  4371.6  411.02  4456.0  409.83  4487.2  410.10  4519.7  409.57  4529.7  408.65
  4559.7  408.05  4619.7  408.15  4833.5  406.58  4879.8  405.90  4931.4  405.91
  4939.9  405.54  4959.9  406.61  4979.9  406.08  5001.8  406.30  5009.9  404.18
  5017.9  403.04  5018.2  402.54  5021.7  402.54  5021.9  403.04  5030.0  404.84
  5040.0  404.51  5059.6  406.63  5064.6  406.04  5195.2  407.11  5462.3  408.61
  5493.7  409.04  5506.7  410.07  5540.7  409.40  5545.9  408.86  5769.7  409.75
#Mann=7,-1,0
  4371.6    0.07       0  4487.2    0.05       0  4833.5    0.16       0
  4931.4    0.12       0  5017.9    0.07       0  5021.9    0.12       0
  5195.2    0.05       0
Bank Sta=5017.9,5021.9
Exp/Cntr=0.3,0.1

Type RM Length L Ch R = 1,62348,364,364,364
BEGIN DESCRIPTION:
Prairie Creek62348.46
END DESCRIPTION:
XS GIS Cut Line= 4
      2716231.92      6836177.52      2716238.82      6836769.94
      2716221.91      6837154.13      2716012.95      6837551.06
#Sta/Elev= 30
  4415.6  409.41  4489.1  409.19  4529.1  408.04  4599.1  407.58  4879.1  406.52
  4927.1  405.17  4949.1  404.63  4967.1  402.66  4967.4  402.16  4970.9  402.16
  4971.1  402.66  4979.1  404.54  5025.1  404.99  5159.3  404.04  5169.3  404.09
  5185.1  406.40  5222.7  405.84  5392.6  407.24  5438.7  405.30  5490.8  404.42
  5536.0  404.29  5548.9  405.26  5570.9  404.75  5603.7  405.29  5615.1  404.19
  5647.8  405.95  5653.4  407.25  5659.9  407.49  5770.5  408.11  5841.2  408.33
#Mann=8,-1,0
  4415.6    0.05       0  4927.1    0.16       0  4967.1    0.07       0
  4971.1    0.16       0  5025.1    0.12       0  5222.7    0.05       0
  5659.9    0.07       0  5770.5    0.05       0
Bank Sta=4967.1,4971.1
Exp/Cntr=0.3,0.1

Type RM Length L Ch R = 1,61984,436,436,436
BEGIN DESCRIPTION:
Prairie Creek61983.9
END DESCRIPTION:
XS GIS Cut Line= 3
      2716082.92      6836060.62      2715889.22      6836814.70
      2715770.79      6837372.00
#Sta/Elev= 30
  4225.7  409.70  4267.4  409.94  4288.0  408.69  4401.6  407.39  4517.6  406.96
  4535.8  407.84  4558.3  406.65  4716.1  405.01  4732.0  405.72  4773.3  404.29
  4845.6  404.93  4866.7  404.61  4879.1  404.25  4897.2  402.79  4919.9  402.18
  4967.2  402.26  4996.2  402.99  5000.7  400.79  5008.7  400.78  5008.9  400.28
  5012.4  400.28  5012.7  400.78  5020.9  402.11  5040.0  402.41  5045.1  403.75
  5139.3  405.40  5183.8  406.13  5520.8  407.34  5552.5  407.77  5574.0  410.14
#Mann=5,-1,0
  4225.7    0.05       0  4866.7    0.12       0  4967.2    0.05       0
  5008.7    0.05       0  5012.7    0.05       0
Bank Sta=5008.7,5012.7
Exp/Cntr=0.3,0.1

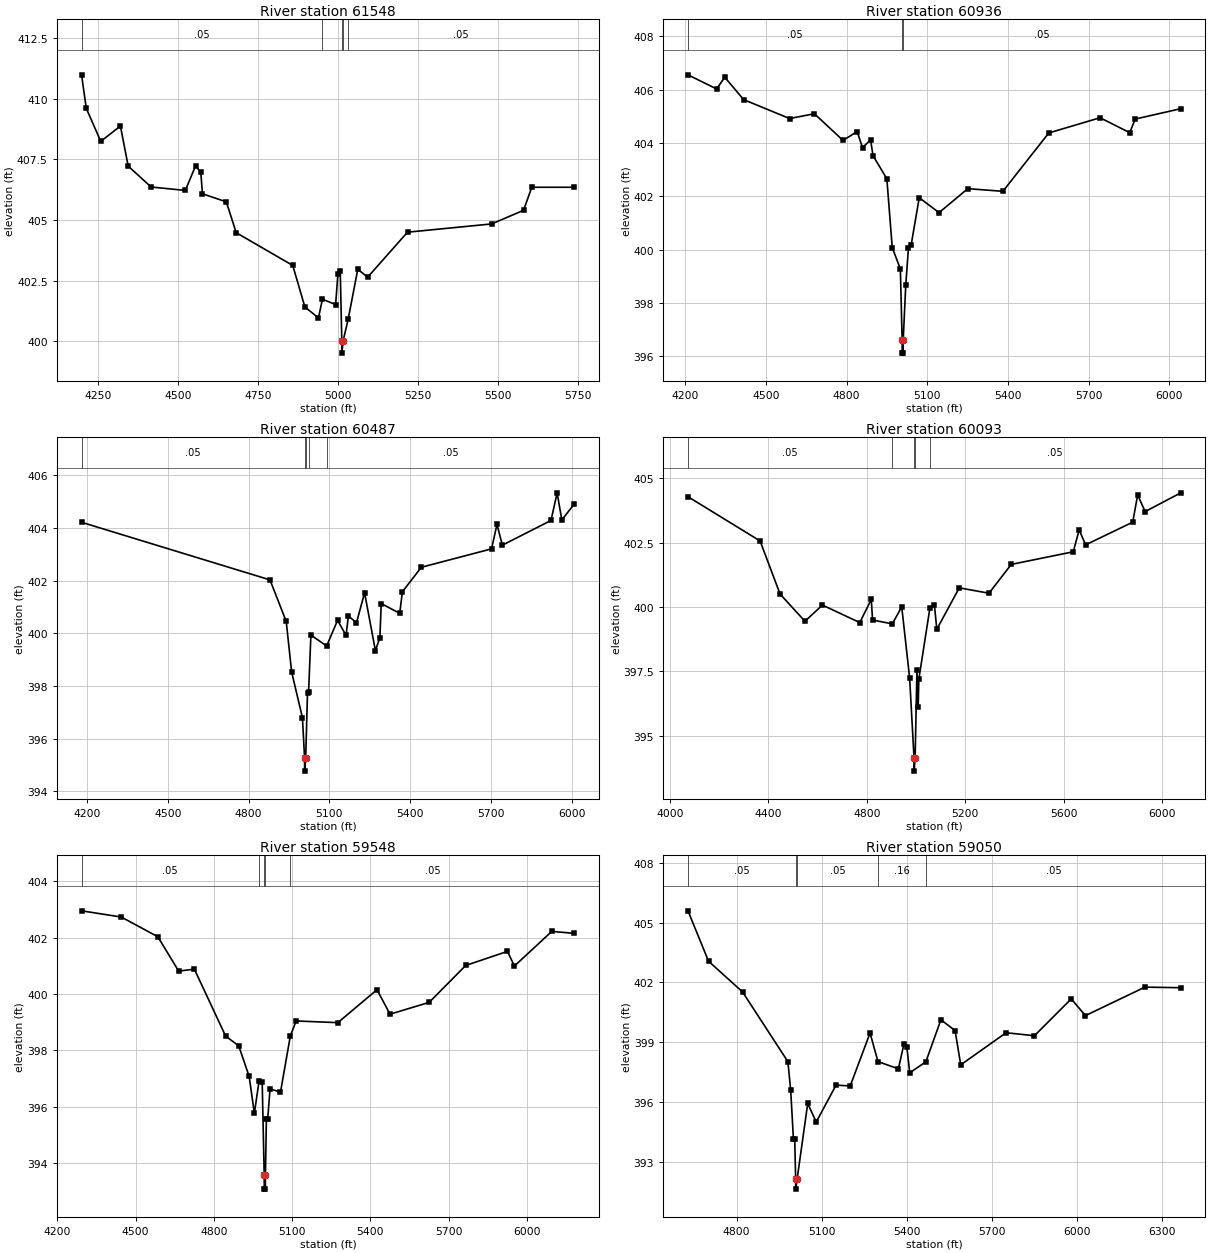
Type RM Length L Ch R = 1,61548,612,612,612
BEGIN DESCRIPTION:
Prairie Creek61548.34
END DESCRIPTION:
XS GIS Cut Line= 3
      2715841.00      6835847.26      2715559.09      6836604.47
      2715318.40      6837295.05
#Sta/Elev= 30
  4199.7  410.98  4214.4  409.60  4259.7  408.24  4321.1  408.87  4345.4  407.22
  4417.1  406.36  4523.8  406.22  4555.8  407.23  4572.1  406.97  4577.4  406.08
  4651.9  405.75  4682.7  404.48  4859.4  403.13  4897.3  401.42  4939.7  400.97
  4952.0  401.74  4993.3  401.52  5000.4  402.78  5007.7  402.89  5012.6  400.02
  5012.8  399.52  5016.6  400.02  5032.7  400.93  5062.4  402.97  5093.5  402.65
  5217.8  404.50  5480.6  404.84  5580.2  405.40  5606.0  406.35  5739.0  406.35
#Mann=5,-1,0
  4199.7    0.05       0  4952.0    0.12       0  5012.6    0.07       0
  5016.6    0.12       0  5032.7    0.05       0
Bank Sta=5012.6,5016.6
Exp/Cntr=0.3,0.1

Type RM Length L Ch R = 1,60936,449,449,449
BEGIN DESCRIPTION:
Prairie Creek60935.94
END DESCRIPTION:
XS GIS Cut Line= 3
      2715232.49      6835474.77      2715161.21      6836273.20
      2715080.26      6837300.01
#Sta/Elev= 30
  4210.7  406.56  4317.3  406.03  4347.5  406.47  4417.7  405.63  4588.4  404.92
  4680.6  405.10  4787.0  404.10  4839.4  404.43  4859.5  403.83  4889.6  404.12
  4898.4  403.53  4949.9  402.66  4969.9  400.08  5000.1  399.28  5006.7  396.62
  5006.9  396.12  5010.4  396.12  5010.7  396.62  5020.1  398.66  5030.2  400.07
  5040.2  400.18  5070.3  401.95  5143.9  401.39  5250.8  402.29  5381.2  402.19
  5551.8  404.38  5742.4  404.95  5852.7  404.39  5872.8  404.90  6042.3  405.29
#Mann=3,-1,0
  4210.7    0.05       0  5006.7    0.05       0  5010.7    0.05       0
Bank Sta=5006.7,5010.7
Exp/Cntr=0.3,0.1

Type RM Length L Ch R = 1,60487,394,394,394
BEGIN DESCRIPTION:
Prairie Creek60486.73
END DESCRIPTION:
XS GIS Cut Line= 3
      2714774.80      6835443.44      2714711.39      6836283.62
      2714635.93      6837267.46
#Sta/Elev= 30
  4180.1  404.22  4879.6  402.03  4939.8  400.45  4959.9  398.53  5000.0  396.79
  5007.9  395.26  5008.2  394.76  5012.1  395.26  5018.8  397.74  5022.8  397.76
  5031.4  399.93  5089.8  399.52  5130.4  400.49  5162.0  399.92  5170.5  400.66
  5200.6  400.40  5230.7  401.54  5270.8  399.34  5287.5  399.84  5292.5  401.13
  5361.0  400.76  5371.1  401.58  5441.3  402.51  5702.0  403.21  5722.1  404.14
  5742.2  403.35  5922.7  404.29  5945.4  405.34  5962.8  404.31  6009.4  404.92
#Mann=5,-1,0
  4180.1    0.05       0  5007.9    0.05       0  5012.1    0.05       0
  5022.8    0.12       0  5089.8    0.05       0
Bank Sta=5007.9,5012.1
Exp/Cntr=0.3,0.1

Type RM Length L Ch R = 1,60093,545,545,545
BEGIN DESCRIPTION:
Prairie Creek60092.82
END DESCRIPTION:
XS GIS Cut Line= 3
      2714509.66      6835281.47      2714360.51      6836208.01
      2714230.41      6837264.87
#Sta/Elev= 30
  4073.0  404.28  4366.3  402.56  4447.3  400.50  4548.6  399.44  4619.5  400.07
  4771.4  399.39  4818.3  400.29  4823.4  399.49  4903.7  399.34  4942.0  400.00
  4974.0  397.25  4992.1  394.12  4992.4  393.62  4996.4  394.12  5003.8  397.53
  5008.9  396.13  5011.5  397.19  5056.2  399.94  5074.9  400.06  5084.6  399.13
  5175.9  400.74  5296.6  400.53  5387.3  401.65  5639.2  402.14  5663.3  402.99
  5689.5  402.41  5881.0  403.29  5901.1  404.35  5931.3  403.70  6076.3  404.43
#Mann=5,-1,0
  4073.0    0.05       0  4903.7    0.12       0  4992.1    0.07       0
  4996.4    0.12       0  5056.2    0.05       0
Bank Sta=4992.1,4996.4
Exp/Cntr=0.3,0.1

Type RM Length L Ch R = 1,59548,498,498,498
BEGIN DESCRIPTION:
Prairie Creek59548.45
END DESCRIPTION:
XS GIS Cut Line= 3
      2714105.73      6835098.83      2714074.72      6835808.13
      2714032.92      6836987.51
#Sta/Elev= 30
  4292.5  402.95  4444.8  402.73  4585.0  402.03  4665.0  400.81  4725.1  400.88
  4845.2  398.50  4895.2  398.16  4935.3  397.07  4955.3  395.76  4973.1  396.90
  4985.3  396.87  4993.0  393.57  4993.3  393.07  4997.3  393.07  4997.7  393.57
  5001.4  395.56  5006.4  395.56  5015.4  396.63  5055.4  396.51  5093.1  398.50
  5115.4  399.04  5275.5  398.98  5425.6  400.15  5475.6  399.28  5625.7  399.70
  5765.8  401.01  5925.9  401.51  5952.7  400.99  6096.0  402.22  6182.6  402.15
#Mann=5,-1,0
  4292.5    0.05       0  4973.1    0.12       0  4993.0    0.07       0
  4997.7    0.12       0  5093.1    0.05       0
Bank Sta=4993,4997.7
Exp/Cntr=0.3,0.1

Type RM Length L Ch R = 1,59050,331,331,331
BEGIN DESCRIPTION:
Prairie Creek59050.07
END DESCRIPTION:
XS GIS Cut Line= 3
      2713673.90      6835188.45      2713672.59      6835565.09
      2713677.96      6836927.53
#Sta/Elev= 30
  4628.1  405.59  4700.7  403.06  4820.7  401.52  4980.7  398.02  4990.7  396.58
  5000.2  394.15  5004.8  394.15  5008.1  392.12  5008.5  391.62  5013.3  392.12
  5050.7  395.92  5080.7  394.99  5150.7  396.84  5200.7  396.80  5270.7  399.46
  5298.7  398.02  5370.7  397.66  5390.7  398.93  5400.7  398.73  5410.7  397.46
  5467.6  398.01  5520.7  400.12  5570.7  399.58  5590.7  397.86  5750.7  399.47
  5850.7  399.32  5980.7  401.17  6030.7  400.33  6240.7  401.76  6367.2  401.73
#Mann=5,-1,0
  4628.1    0.05       0  5008.1    0.05       0  5013.3    0.05       0
  5298.7    0.16       0  5467.6    0.05       0
Bank Sta=5008.1,5013.3
Exp/Cntr=0.3,0.1

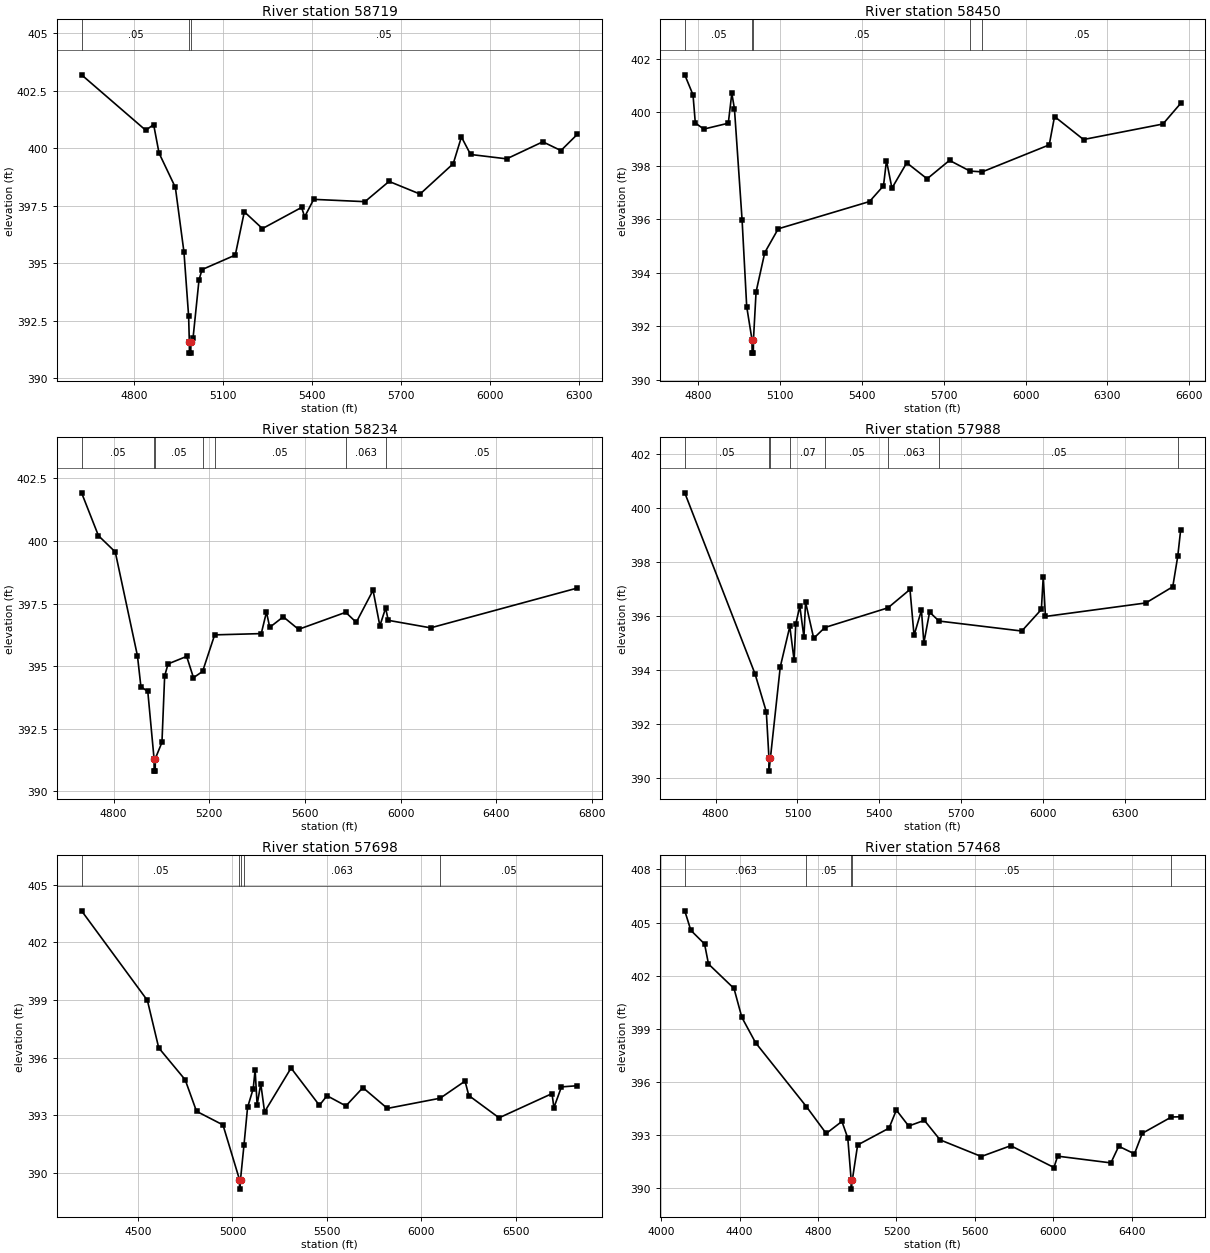
Type RM Length L Ch R = 1,58719,269,269,269
BEGIN DESCRIPTION:
Prairie Creek58719.31
END DESCRIPTION:
XS GIS Cut Line= 3
      2713465.34      6835153.32      2713382.86      6835545.45
      2713155.78      6836795.79
#Sta/Elev= 30
  4622.2  403.19  4838.6  400.78  4865.1  401.03  4883.3  399.79  4938.3  398.30
  4967.3  395.49  4983.0  392.71  4985.4  391.60  4985.8  391.10  4990.3  391.10
  4990.7  391.60  4997.9  391.75  5018.1  394.29  5028.4  394.73  5140.3  395.36
  5170.8  397.24  5231.8  396.51  5363.9  397.43  5374.1  397.02  5404.6  397.78
  5577.4  397.68  5658.7  398.56  5763.1  398.01  5875.0  399.33  5902.6  400.49
  5933.5  399.73  6055.1  399.54  6177.0  400.28  6238.0  399.90  6293.7  400.61
#Mann=3,-1,0
  4622.2    0.05       0  4985.4    0.05       0  4990.7    0.05       0
Bank Sta=4985.4,4990.7
Exp/Cntr=0.3,0.1

Type RM Length L Ch R = 1,58450,216,216,216
BEGIN DESCRIPTION:
Prairie Creek58450.35
END DESCRIPTION:
XS GIS Cut Line= 3
      2713293.10      6835136.39      2713181.35      6835363.31
      2712659.04      6836836.19
#Sta/Elev= 30
  4752.3  401.40  4782.5  400.65  4790.9  399.60  4821.9  399.37  4911.7  399.59
  4924.6  400.71  4934.2  400.13  4962.2  395.97  4979.1  392.73  4998.5  391.49
  4998.9  390.99  5003.4  390.99  5003.8  391.49  5013.4  393.28  5045.2  394.75
  5094.5  395.64  5428.8  396.66  5480.0  397.25  5490.9  398.19  5510.9  397.16
  5565.1  398.11  5639.7  397.51  5721.7  398.20  5796.6  397.80  5841.5  397.77
  6086.9  398.78  6106.3  399.84  6212.4  398.98  6503.2  399.56  6568.0  400.33
#Mann=5,-1,0
  4752.3    0.05       0  4998.5    0.05       0  5003.8    0.05       0
  5796.6    0.07       0  5841.5    0.05       0
Bank Sta=4998.5,5003.8
Exp/Cntr=0.3,0.1

Type RM Length L Ch R = 1,58234,246,246,246
BEGIN DESCRIPTION:
Prairie Creek58234.41
END DESCRIPTION:
XS GIS Cut Line= 3
      2713254.21      6835070.57      2712992.23      6835281.04
      2711695.69      6836436.73
#Sta/Elev= 30
  4666.2  401.92  4736.6  400.21  4807.0  399.56  4899.8  395.41  4914.2  394.18
  4943.0  393.99  4969.1  391.31  4969.5  390.81  4974.0  390.81  4974.4  391.31
  5002.2  391.96  5013.5  394.61  5027.7  395.09  5105.5  395.39  5133.9  394.54
  5172.1  394.79  5222.5  396.25  5417.3  396.30  5439.1  397.16  5452.7  396.55
  5509.3  396.97  5573.2  396.47  5770.4  397.15  5814.4  396.75  5884.7  398.03
  5913.1  396.61  5937.2  397.32  5948.3  396.83  6125.5  396.53  6739.1  398.12
#Mann=7,-1,0
  4666.2    0.05       0  4969.1    0.05       0  4974.4    0.05       0
  5172.1    0.07       0  5222.5    0.05       0  5770.4   0.063       0
  5937.2    0.05       0
Bank Sta=4969.1,4974.4
Exp/Cntr=0.3,0.1

Type RM Length L Ch R = 1,57988,290,290,290
BEGIN DESCRIPTION:
Mapping XS fe6308a3
END DESCRIPTION:
XS GIS Cut Line= 3
      2713106.31      6835063.49      2712795.99      6835138.63
      2711560.90      6835984.74
#Sta/Elev= 30
  4687.1  400.58  4944.6  393.87  4985.8  392.47  4995.4  390.77  4995.9  390.27
  5001.0  390.77  5036.9  394.13  5071.9  395.63  5087.7  394.37  5093.7  395.72
  5108.6  396.38  5123.6  395.23  5129.6  396.53  5159.4  395.19  5200.2  395.59
  5431.6  396.32  5512.1  397.00  5527.0  395.30  5554.1  396.23  5562.9  395.02
  5583.9  396.16  5618.4  395.83  5921.7  395.46  5993.4  396.26  6000.3  397.48
  6008.3  396.00  6376.0  396.50  6474.7  397.10  6493.0  398.23  6503.5  399.19
#Mann=8,-1,0
  4687.1    0.05       0  4995.4    0.05       0  5001.0    0.05       0
  5071.9    0.07       0  5200.2    0.05       0  5431.6   0.063       0
  5618.4    0.05       0  6493.0   0.063       0
Bank Sta=4995.4,5001
Exp/Cntr=0.3,0.1

Type RM Length L Ch R = 1,57698,230,230,230
BEGIN DESCRIPTION:
Prairie Creek57698.1
END DESCRIPTION:
XS GIS Cut Line= 4
      2713344.22      6835015.16      2712541.61      6835031.36
      2711722.57      6834995.26      2710721.49      6834955.01
#Sta/Elev= 30
  4201.5  403.64  4549.8  398.98  4609.8  396.51  4749.8  394.85  4809.8  393.21
  4949.9  392.50  5037.1  389.66  5037.6  389.16  5042.7  389.66  5061.3  391.48
  5080.0  393.41  5110.0  394.39  5120.0  395.37  5130.5  393.55  5150.0  394.64
  5170.0  393.18  5310.2  395.46  5460.3  393.52  5500.4  394.02  5600.5  393.49
  5690.5  394.44  5819.9  393.36  6099.3  393.89  6231.0  394.78  6251.0  394.03
  6411.2  392.87  6691.4  394.13  6701.4  393.40  6741.4  394.48  6826.0  394.54
#Mann=5,-1,0
  4201.5    0.05       0  5037.1    0.05       0  5042.7    0.05       0
  5061.3   0.063       0  6099.3    0.05       0
Bank Sta=5037.1,5042.7
Exp/Cntr=0.3,0.1

Type RM Length L Ch R = 1,57468,649,649,649
BEGIN DESCRIPTION:
Prairie Creek57468.36
END DESCRIPTION:
XS GIS Cut Line= 4
      2713276.92      6834875.07      2712389.28      6834882.40
      2711373.30      6834848.71      2710750.94      6834820.60
#Sta/Elev= 30
  4120.9  405.66  4151.8  404.56  4221.8  403.79  4241.8  402.66  4371.8  401.28
  4411.8  399.65  4481.8  398.22  4741.2  394.61  4841.8  393.10  4921.8  393.78
  4951.8  392.84  4969.0  390.46  4969.5  389.96  4974.6  390.46  5001.9  392.45
  5161.9  393.40  5199.3  394.42  5262.0  393.52  5342.0  393.84  5422.1  392.74
  5632.2  391.80  5782.3  392.41  6002.4  391.18  6021.3  391.82  6292.7  391.44
  6332.7  392.38  6412.8  391.95  6452.8  393.11  6601.4  394.03  6648.1  394.04
#Mann=5,-1,0
  4120.9   0.063       0  4741.2    0.05       0  4969.0    0.05       0
  4974.6    0.05       0  6601.4   0.063       0
Bank Sta=4969,4974.6
Exp/Cntr=0.3,0.1

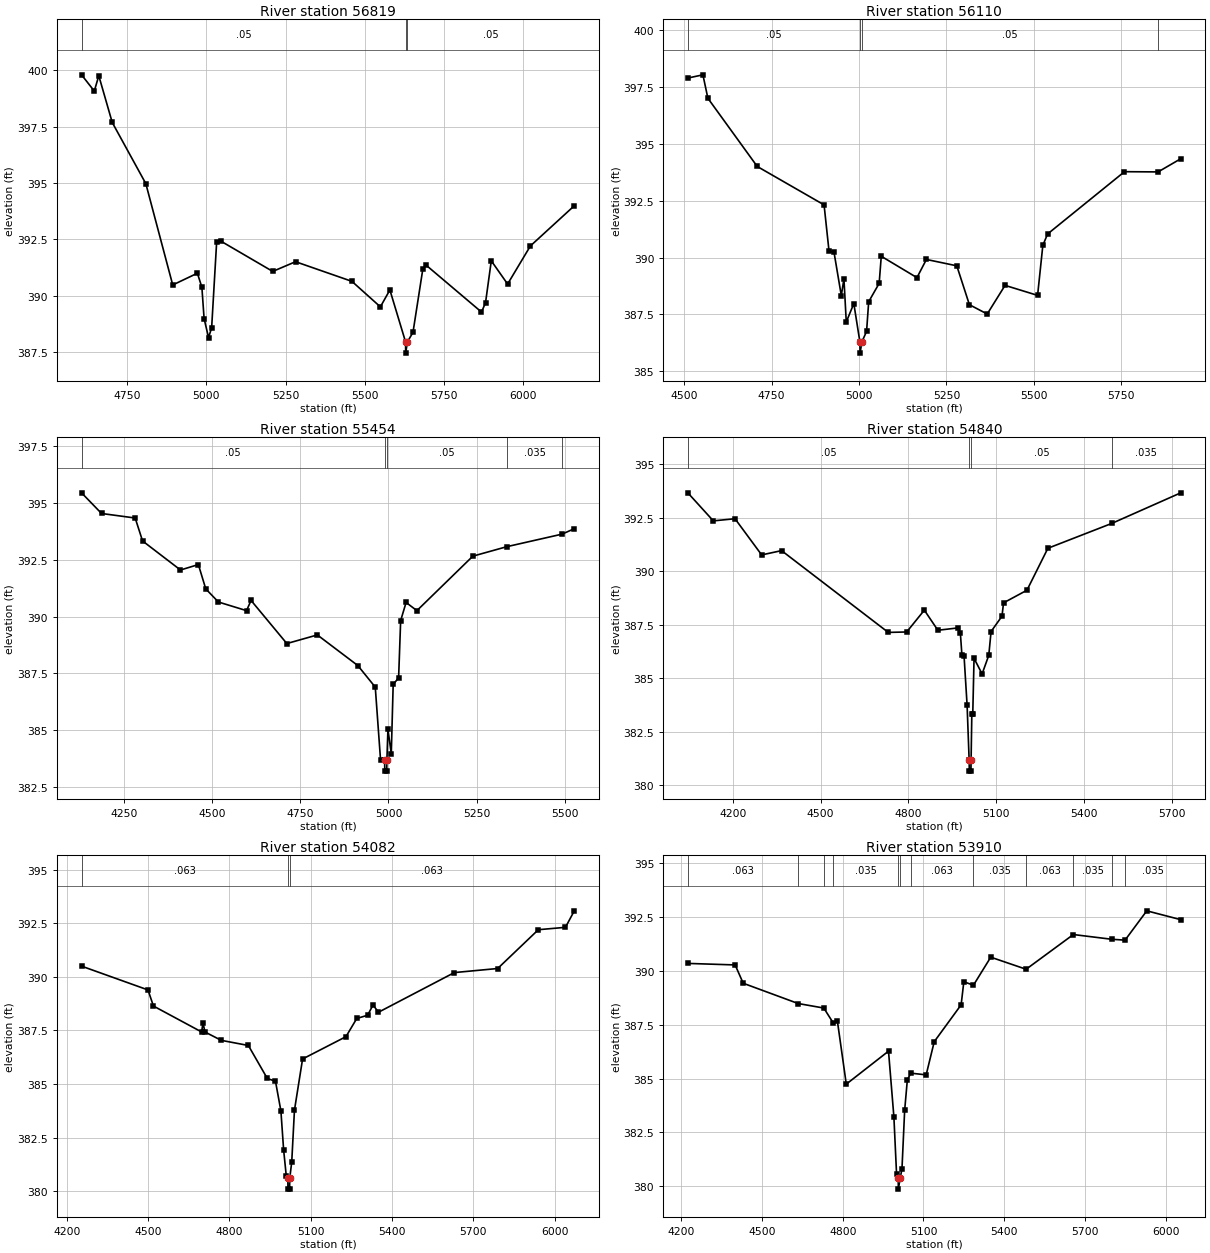
Type RM Length L Ch R = 1,56819,709,709,709
BEGIN DESCRIPTION:
Mapping XS 7407bad1
END DESCRIPTION:
XS GIS Cut Line= 3
      2712201.43      6834229.58      2711915.61      6834520.86
      2710801.50      6834793.20
#Sta/Elev= 30
  4606.1  399.79  4646.3  399.07  4660.5  399.75  4702.9  397.68  4808.9  394.97
  4893.8  390.48  4971.6  391.00  4985.8  390.38  4992.8  388.99  5006.9  388.15
  5016.6  388.58  5032.5  392.40  5044.7  392.43  5209.4  391.08  5281.4  391.51
  5459.3  390.64  5549.1  389.51  5579.1  390.26  5628.5  387.96  5629.0  387.46
  5634.4  387.96  5652.0  388.38  5682.9  391.17  5693.2  391.36  5868.2  389.28
  5880.9  389.69  5899.1  391.55  5950.6  390.52  6022.6  392.21  6161.1  393.99
#Mann=3,-1,0
  4606.1    0.05       0  5628.5    0.05       0  5634.4    0.05       0
Bank Sta=5628.5,5634.4
Exp/Cntr=0.3,0.1

Type RM Length L Ch R = 1,56110,656,656,656
BEGIN DESCRIPTION:
Prairie Creek56110.24
END DESCRIPTION:
XS GIS Cut Line= 4
      2711763.42      6834008.56      2711428.84      6834374.94
      2710994.60      6834666.32      2710639.60      6834828.98
#Sta/Elev= 30
  4510.8  397.90  4553.4  398.04  4567.6  397.01  4708.8  394.01  4900.0  392.32
  4914.2  390.28  4928.4  390.24  4949.3  388.33  4956.8  389.07  4963.5  387.17
  4985.1  387.98  5002.4  386.30  5002.9  385.80  5008.4  386.30  5021.6  386.76
  5027.6  388.06  5057.6  388.87  5063.6  390.06  5165.7  389.12  5192.7  389.92
  5279.7  389.64  5315.7  387.93  5366.7  387.52  5417.7  388.78  5510.8  388.34
  5525.8  390.54  5539.4  391.04  5759.4  393.78  5855.5  393.77  5920.4  394.35
#Mann=4,-1,0
  4510.8    0.05       0  5002.4    0.05       0  5008.4    0.05       0
  5855.5   0.063       0
Bank Sta=5002.4,5008.4
Exp/Cntr=0.3,0.1

Type RM Length L Ch R = 1,55454,614,614,614
BEGIN DESCRIPTION:
Prairie Creek55453.5
END DESCRIPTION:
XS GIS Cut Line= 3
      2711330.72      6833655.75      2710833.73      6834376.90
      2710560.03      6834821.01
#Sta/Elev= 30
  4129.5  395.45  4186.2  394.54  4281.6  394.34  4302.5  393.33  4410.1  392.05
  4460.8  392.29  4481.7  391.22  4517.6  390.64  4597.4  390.26  4610.2  390.71
  4711.7  388.81  4798.2  389.19  4913.1  387.84  4962.5  386.89  4977.4  383.70
  4989.0  383.69  4989.5  383.19  4995.0  383.19  4995.5  383.69  4998.4  385.03
  5007.9  383.96  5013.3  387.01  5028.7  387.30  5034.5  389.82  5049.9  390.62
  5080.6  390.26  5239.2  392.66  5336.2  393.08  5492.2  393.63  5527.0  393.87
#Mann=5,-1,0
  4129.5    0.05       0  4989.0    0.05       0  4995.5    0.05       0
  5336.2   0.035       0  5492.2   0.063       0
Bank Sta=4989,4995.5
Exp/Cntr=0.3,0.1

Type RM Length L Ch R = 1,54840,758,758,758
BEGIN DESCRIPTION:
Prairie Creek54839.6
END DESCRIPTION:
XS GIS Cut Line= 3
      2710779.50      6833087.26      2710541.99      6834027.33
      2710398.19      6834725.37
#Sta/Elev= 30
  4047.3  393.65  4133.7  392.35  4207.7  392.45  4298.7  390.76  4366.7  390.96
  4731.0  387.14  4793.8  387.16  4854.1  388.18  4900.3  387.24  4969.1  387.35
  4977.2  387.09  4982.4  386.08  4989.7  386.04  5000.1  383.74  5007.1  381.16
  5007.6  380.66  5013.2  380.66  5013.7  381.16  5016.2  383.31  5019.4  383.31
  5023.8  385.93  5051.3  385.20  5074.1  386.07  5081.9  387.18  5119.3  387.90
  5124.4  388.52  5204.4  389.11  5275.9  391.07  5493.8  392.23  5729.6  393.66
#Mann=4,-1,0
  4047.3    0.05       0  5007.1    0.05       0  5013.7    0.05       0
  5493.8   0.035       0
Bank Sta=5007.1,5013.7
Exp/Cntr=0.3,0.1

Type RM Length L Ch R = 1,54082,172,172,172
BEGIN DESCRIPTION:
Prairie Creek54082.16
END DESCRIPTION:
XS GIS Cut Line= 3
      2710138.86      6832766.02      2710108.06      6833534.24
      2710110.50      6834583.70
#Sta/Elev= 30
  4254.2  390.50  4499.4  389.39  4519.4  388.64  4697.3  387.43  4702.3  387.86
  4709.5  387.43  4769.6  387.04  4869.7  386.80  4939.7  385.26  4969.8  385.13
  4989.8  383.75  4999.8  381.94  5009.8  380.69  5015.4  380.60  5015.9  380.10
  5021.9  380.10  5022.4  380.60  5029.8  381.37  5039.8  383.78  5069.8  386.17
  5229.8  387.21  5269.8  388.06  5309.8  388.21  5329.8  388.69  5349.8  388.35
  5629.8  390.20  5789.8  390.39  5939.8  392.20  6039.8  392.31  6072.5  393.08
#Mann=3,-1,0
  4254.2   0.063       0  5015.4   0.063       0  5022.4   0.063       0
Bank Sta=5015.4,5022.4
Exp/Cntr=0.3,0.1

Type RM Length L Ch R = 1,53910,388,388,388
BEGIN DESCRIPTION:
Prairie Creek53909.84
END DESCRIPTION:
XS GIS Cut Line= 3
      2709954.41      6832735.81      2709936.36      6833525.12
      2709916.92      6834567.42
#Sta/Elev= 30
  4224.6  390.34  4399.8  390.27  4429.8  389.42  4634.0  388.48  4729.5  388.27
  4765.4  387.56  4779.9  387.67  4813.0  384.74  4970.0  386.27  4990.0  383.22
  5000.0  380.55  5006.1  380.37  5006.6  379.87  5013.1  380.37  5020.0  380.80
  5030.0  383.52  5040.0  384.94  5052.9  385.25  5110.0  385.17  5140.0  386.71
  5240.0  388.42  5250.0  389.49  5285.8  389.33  5350.1  390.63  5481.6  390.07
  5657.2  391.68  5800.4  391.46  5849.4  391.42  5930.2  392.78  6056.6  392.37
#Mann=12,-1,0
  4224.6   0.063       0  4634.0   0.035       0  4729.5   0.063       0
  4765.4   0.035       0  5006.1   0.035       0  5013.1   0.035       0
  5052.9   0.063       0  5285.8   0.035       0  5481.6   0.063       0
  5657.2   0.035       0  5800.4   0.063       0  5849.4   0.035       0
Bank Sta=5006.1,5013.1
Exp/Cntr=0.3,0.1

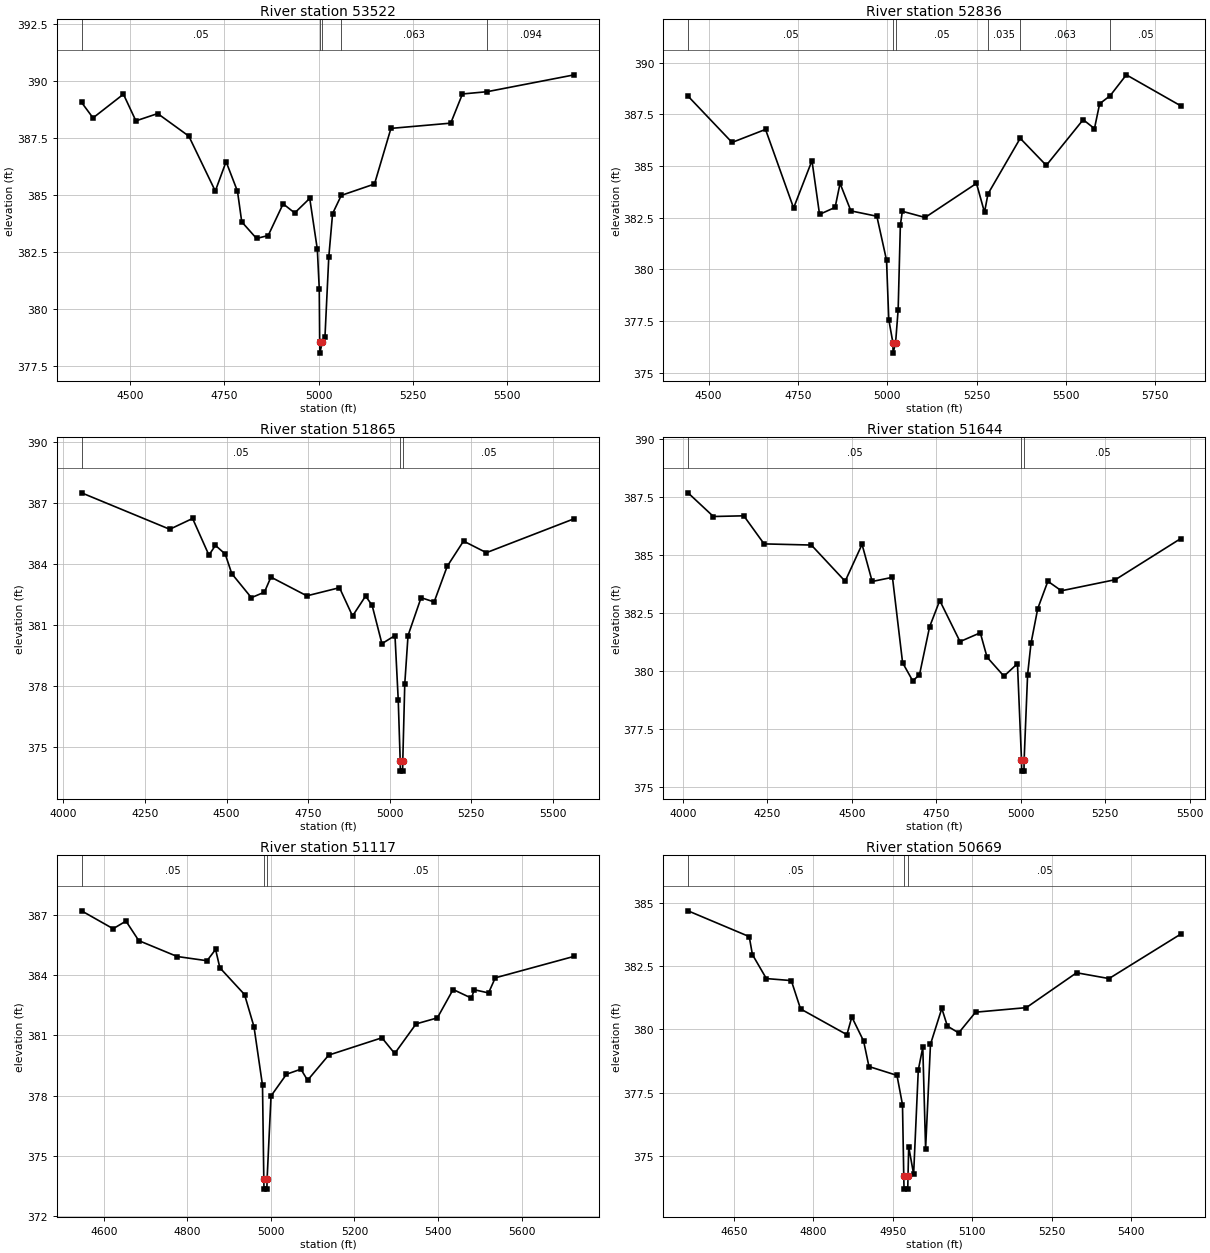
Type RM Length L Ch R = 1,53522,686,686,686
BEGIN DESCRIPTION:
Prairie Creek53521.9
END DESCRIPTION:
XS GIS Cut Line= 3
      2709711.32      6832740.82      2709619.67      6833375.19
      2709512.75      6834035.13
#Sta/Elev= 30
  4370.2  389.07  4400.7  388.39  4481.5  389.43  4514.6  388.26  4572.5  388.58
  4655.3  387.59  4725.6  385.18  4754.3  386.47  4784.6  385.17  4795.9  383.83
  4835.2  383.10  4866.2  383.23  4905.9  384.62  4936.6  384.22  4976.6  384.86
  4996.8  382.62  5001.9  380.89  5003.0  378.57  5003.5  378.07  5010.1  378.57
  5017.0  378.76  5027.2  382.28  5037.3  384.19  5060.4  384.99  5148.7  385.49
  5192.4  387.93  5351.3  388.16  5382.4  389.44  5448.1  389.54  5679.7  390.28
#Mann=5,-1,0
  4370.2    0.05       0  5003.0    0.05       0  5010.1    0.05       0
  5060.4   0.063       0  5448.1   0.094       0
Bank Sta=5003,5010.1
Exp/Cntr=0.3,0.1

Type RM Length L Ch R = 1,52836,971,971,971
BEGIN DESCRIPTION:
Prairie Creek52835.95
END DESCRIPTION:
XS GIS Cut Line= 3
      2709642.02      6832717.65      2709168.54      6833022.86
      2708426.11      6833360.93
#Sta/Elev= 30
  4442.6  388.38  4565.8  386.14  4659.5  386.77  4738.1  382.97  4789.5  385.26
  4810.7  382.66  4854.3  383.00  4868.1  384.16  4898.4  382.83  4971.1  382.57
  4998.1  380.45  5004.5  377.57  5016.0  376.45  5016.5  375.95  5023.5  376.45
  5030.7  378.05  5036.9  382.14  5042.4  382.81  5106.1  382.51  5249.9  384.16
  5272.4  382.76  5282.1  383.65  5372.3  386.34  5445.3  385.03  5548.5  387.24
  5580.1  386.81  5594.6  388.01  5624.0  388.40  5669.3  389.41  5821.7  387.91
#Mann=6,-1,0
  4442.6    0.05       0  5016.0    0.05       0  5023.5    0.05       0
  5282.1   0.035       0  5372.3   0.063       0  5624.0    0.05       0
Bank Sta=5016,5023.5
Exp/Cntr=0.3,0.1

Type RM Length L Ch R = 1,51865,221,221,221
BEGIN DESCRIPTION:
Prairie Creek51864.89
END DESCRIPTION:
XS GIS Cut Line= 3
      2709566.17      6832663.94      2708618.48      6832659.61
      2708056.65      6832651.12
#Sta/Elev= 30
  4055.8  387.50  4326.0  385.71  4396.0  386.24  4446.0  384.44  4466.0  384.92
  4496.0  384.49  4516.0  383.53  4576.0  382.35  4616.0  382.62  4636.0  383.36
  4746.0  382.44  4846.0  382.84  4886.0  381.45  4926.0  382.43  4946.0  381.97
  4976.0  380.09  5016.0  380.49  5026.0  377.32  5032.0  374.33  5032.5  373.83
  5039.4  373.83  5039.9  374.33  5046.0  378.12  5056.0  380.49  5096.0  382.35
  5136.0  382.14  5176.0  383.89  5226.0  385.13  5296.0  384.56  5565.4  386.23
#Mann=3,-1,0
  4055.8    0.05       0  5032.0    0.05       0  5039.9    0.05       0
Bank Sta=5032,5039.9
Exp/Cntr=0.3,0.1

Type RM Length L Ch R = 1,51644,527,527,527
BEGIN DESCRIPTION:
Prairie Creek51643.94
END DESCRIPTION:
XS GIS Cut Line= 3
      2709511.07      6832502.50      2708519.33      6832497.16
      2708052.63      6832503.83
#Sta/Elev= 30
  4015.3  387.67  4090.4  386.65  4180.4  386.68  4240.4  385.47  4380.4  385.42
  4480.4  383.86  4530.4  385.45  4560.4  383.85  4620.4  384.03  4650.4  380.35
  4680.4  379.57  4700.4  379.83  4730.4  381.90  4760.4  383.03  4820.4  381.26
  4880.4  381.64  4900.4  380.59  4950.4  379.77  4990.4  380.31  5002.3  376.18
  5002.8  375.68  5009.7  375.68  5010.2  376.18  5020.4  379.83  5030.4  381.18
  5050.4  382.68  5080.4  383.86  5120.4  383.45  5280.4  383.93  5473.8  385.70
#Mann=3,-1,0
  4015.3    0.05       0  5002.3    0.05       0  5010.2    0.05       0
Bank Sta=5002.3,5010.2
Exp/Cntr=0.3,0.1

Type RM Length L Ch R = 1,51117,448,448,448
BEGIN DESCRIPTION:
Prairie Creek51117.39
END DESCRIPTION:
XS GIS Cut Line= 3
      2709270.04      6832116.01      2708819.77      6832209.62
      2708114.84      6832353.72
#Sta/Elev= 30
  4546.9  387.19  4622.5  386.30  4653.2  386.68  4683.8  385.71  4775.7  384.92
  4847.2  384.71  4867.7  385.27  4877.9  384.36  4937.0  383.03  4959.6  381.43
  4980.0  378.52  4983.1  373.86  4983.6  373.36  4990.5  373.36  4991.0  373.86
  5000.4  377.99  5037.4  379.07  5071.9  379.32  5087.9  378.77  5138.4  380.02
  5265.8  380.88  5296.4  380.10  5347.5  381.57  5398.5  381.87  5436.2  383.28
  5480.2  382.85  5486.6  383.27  5521.0  383.11  5537.1  383.86  5726.3  384.93
#Mann=3,-1,0
  4546.9    0.05       0  4983.1    0.05       0  4991.0    0.05       0
Bank Sta=4983.1,4991
Exp/Cntr=0.3,0.1

Type RM Length L Ch R = 1,50669,292,292,292
BEGIN DESCRIPTION:
Prairie Creek50668.81
END DESCRIPTION:
XS GIS Cut Line= 3
      2709041.78      6831761.28      2708624.35      6831893.76
      2708162.02      6832061.60
#Sta/Elev= 30
  4563.8  384.69  4679.3  383.67  4685.3  382.96  4711.6  382.01  4758.7  381.93
  4776.1  380.81  4863.6  379.79  4872.9  380.49  4895.1  379.54  4905.2  378.53
  4958.1  378.18  4968.5  377.02  4970.9  374.18  4971.4  373.68  4978.4  373.68
  4978.9  374.18  4980.2  375.36  4989.5  374.27  4998.3  378.39  5006.8  379.29
  5012.1  375.28  5021.3  379.41  5042.7  380.83  5053.2  380.13  5074.5  379.86
  5106.4  380.68  5202.1  380.86  5297.0  382.24  5358.2  382.01  5493.6  383.77
#Mann=3,-1,0
  4563.8    0.05       0  4970.9    0.05       0  4978.9    0.05       0
Bank Sta=4970.9,4978.9
Exp/Cntr=0.3,0.1