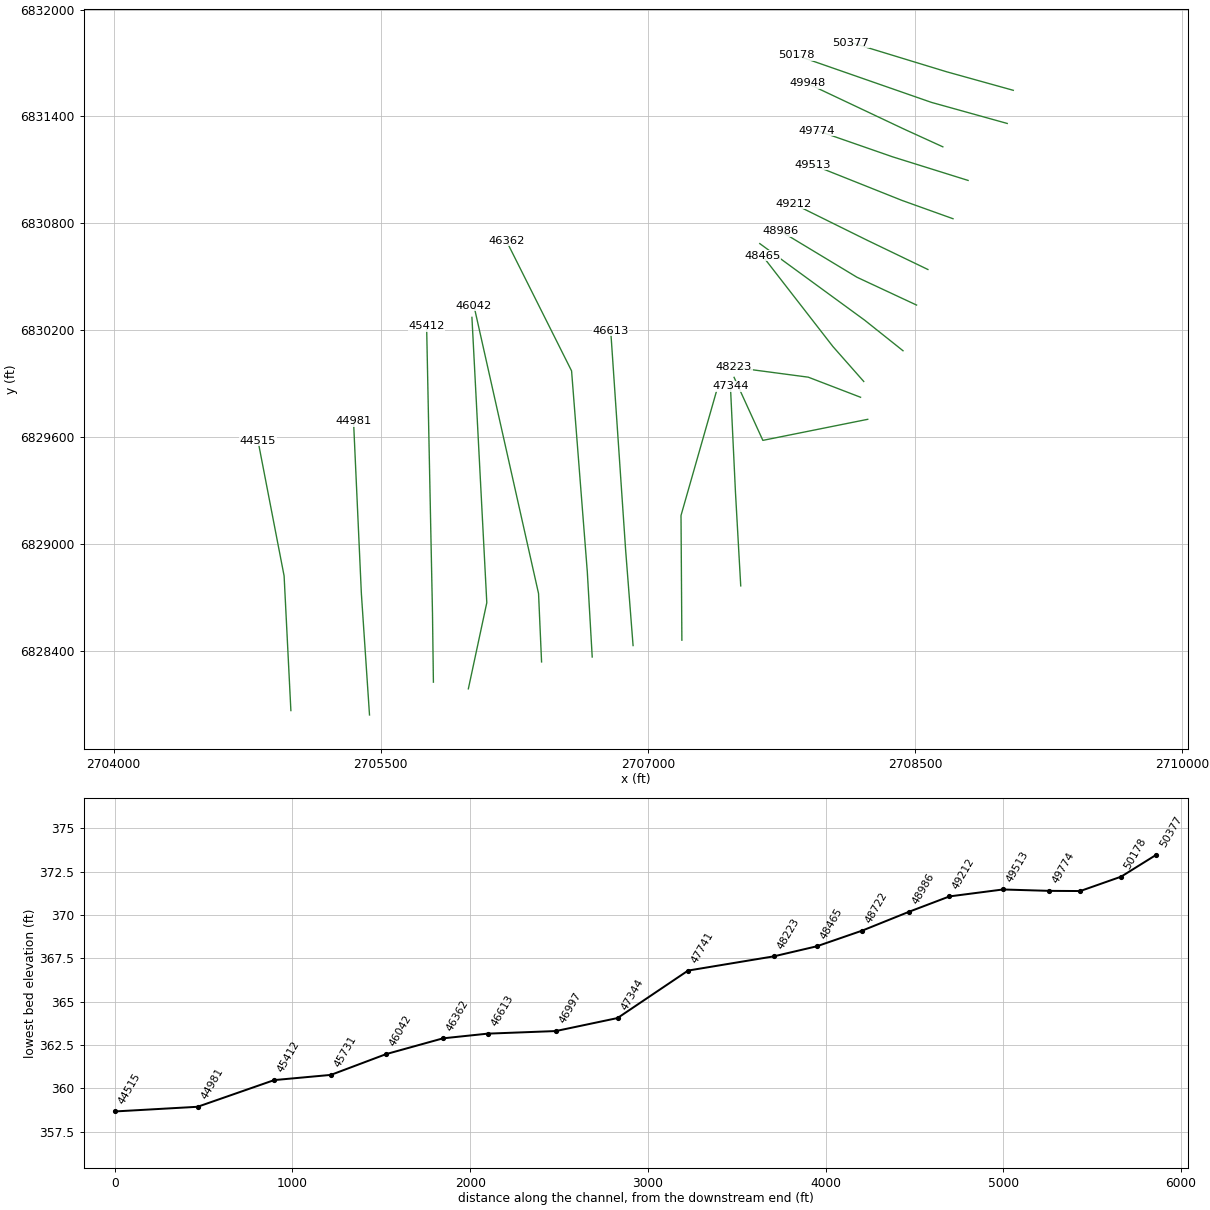
HEC-RAS study Prairie Creek.prj: Prairie Creek Base Level Engineering

--- Prairie Creek.g01 (geometry) --- (continued)

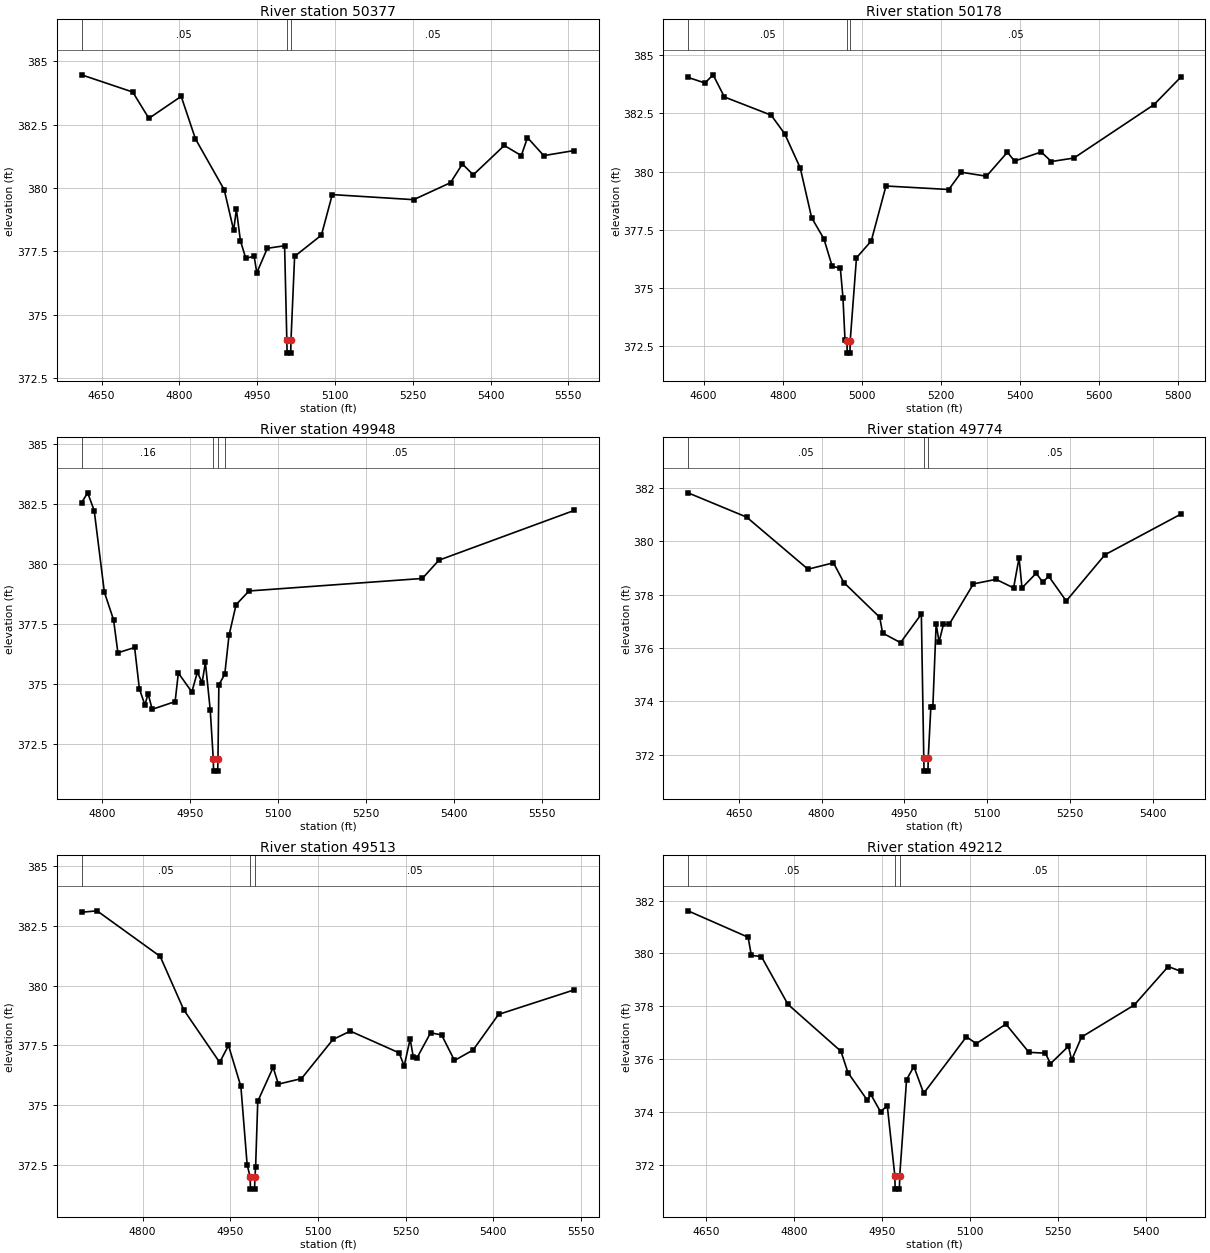
Type RM Length L Ch R = 1,50377,199,199,199
BEGIN DESCRIPTION:
Prairie Creek50376.97
END DESCRIPTION:
XS GIS Cut Line= 3
      2709051.09      6831546.76      2708676.92      6831650.79
      2708139.64      6831814.72
#Sta/Elev= 30
  4611.5  384.47  4710.2  383.79  4741.3  382.75  4803.6  383.62  4831.1  381.94
  4886.6  379.93  4904.8  378.33  4910.0  379.16  4917.8  377.92  4928.2  377.22
  4944.2  377.31  4949.4  376.65  4969.7  377.62  5003.0  377.72  5007.3  373.98
  5007.8  373.48  5014.8  373.48  5015.3  373.98  5022.3  377.30  5074.0  378.14
  5094.9  379.74  5251.8  379.54  5322.9  380.21  5345.8  380.95  5366.8  380.52
  5426.6  381.68  5459.4  381.28  5471.3  381.99  5502.7  381.28  5561.6  381.48
#Mann=3,-1,0
  4611.5    0.05       0  5007.3    0.05       0  5015.3    0.05       0
Bank Sta=5007.3,5015.3
Exp/Cntr=0.3,0.1

Type RM Length L Ch R = 1,50178,230,230,230
BEGIN DESCRIPTION:
Prairie Creek50177.8
END DESCRIPTION:
XS GIS Cut Line= 3
      2709017.15      6831360.68      2708591.20      6831479.12
      2707831.96      6831743.61
#Sta/Elev= 30
  4560.6  384.04  4603.3  383.80  4624.1  384.15  4652.6  383.20  4770.8  382.42
  4805.1  381.62  4844.5  380.15  4873.2  378.02  4904.3  377.11  4925.1  375.94
  4945.8  375.85  4952.4  374.59  4957.6  372.77  4962.6  372.71  4963.1  372.21
  4970.1  372.21  4970.6  372.71  4986.6  376.30  5023.9  377.02  5061.2  379.38
  5220.0  379.23  5251.8  379.97  5315.3  379.80  5368.3  380.83  5386.3  380.45
  5453.7  380.84  5479.5  380.43  5536.4  380.58  5738.9  382.87  5806.7  384.05
#Mann=3,-1,0
  4560.6    0.05       0  4962.6    0.05       0  4970.6    0.05       0
Bank Sta=4962.6,4970.6
Exp/Cntr=0.3,0.1

Type RM Length L Ch R = 1,49948,174,174,174
BEGIN DESCRIPTION:
Prairie Creek49948.03
END DESCRIPTION:
XS GIS Cut Line= 3
      2708655.65      6831229.50      2708438.88      6831328.44
      2707894.38      6831585.70
#Sta/Elev= 30
  4764.9  382.54  4775.3  382.95  4786.5  382.21  4803.8  378.82  4819.5  377.67
  4826.9  376.30  4855.4  376.52  4863.5  374.81  4872.9  374.13  4878.4  374.60
  4885.4  373.95  4924.5  374.27  4930.0  375.46  4953.0  374.67  4962.4  375.49
  4970.6  375.06  4976.1  375.90  4984.4  373.92  4989.6  371.88  4990.1  371.38
  4997.1  371.38  4997.6  371.88  4999.1  374.97  5009.2  375.41  5016.4  377.02
  5028.5  378.30  5050.6  378.87  5346.2  379.39  5374.5  380.15  5605.4  382.22
#Mann=4,-1,0
  4764.9    0.16       0  4989.6    0.07       0  4997.6    0.16       0
  5009.2    0.05       0
Bank Sta=4989.6,4997.6
Exp/Cntr=0.3,0.1

Type RM Length L Ch R = 1,49774,261,261,261
BEGIN DESCRIPTION:
Prairie Creek49773.63
END DESCRIPTION:
XS GIS Cut Line= 3
      2708797.38      6831040.83      2708374.13      6831173.15
      2707950.01      6831320.70
#Sta/Elev= 30
  4558.0  381.81  4664.2  380.90  4775.3  378.95  4821.4  379.19  4840.3  378.45
  4905.2  377.15  4910.4  376.56  4942.9  376.20  4980.6  377.27  4985.0  371.89
  4985.5  371.39  4992.6  371.39  4993.1  371.89  4997.8  373.78  5001.4  373.78
  5007.4  376.90  5012.7  376.23  5020.6  376.88  5031.2  376.89  5074.9  378.40
  5115.9  378.57  5147.7  378.25  5157.6  379.38  5162.9  378.25  5188.7  378.80
  5200.6  378.46  5211.2  378.69  5243.0  377.76  5313.1  379.49  5450.5  381.01
#Mann=3,-1,0
  4558.0    0.05       0  4985.0    0.05       0  4993.1    0.05       0
Bank Sta=4985,4993.1
Exp/Cntr=0.3,0.1

Type RM Length L Ch R = 1,49513,301,301,301
BEGIN DESCRIPTION:
Prairie Creek49513.42
END DESCRIPTION:
XS GIS Cut Line= 3
      2708712.71      6830825.86      2708426.74      6830928.45
      2707925.52      6831128.28
#Sta/Elev= 30
  4695.4  383.07  4721.9  383.13  4830.0  381.22  4870.4  378.98  4931.8  376.78
  4946.9  377.49  4968.1  375.77  4978.8  372.50  4984.0  371.97  4984.5  371.47
  4991.6  371.47  4992.1  371.97  4993.3  372.39  4997.0  375.15  5023.3  376.57
  5032.3  375.87  5071.8  376.10  5125.7  377.74  5155.4  378.09  5238.9  377.18
  5247.6  376.63  5257.8  377.76  5263.2  377.00  5269.1  376.95  5292.8  378.02
  5311.7  377.93  5333.7  376.86  5365.6  377.30  5409.1  378.79  5538.8  379.82
#Mann=3,-1,0
  4695.4    0.05       0  4984.0    0.05       0  4992.1    0.05       0
Bank Sta=4984,4992.1
Exp/Cntr=0.3,0.1

Type RM Length L Ch R = 1,49212,226,226,226
BEGIN DESCRIPTION:
Prairie Creek49212.37
END DESCRIPTION:
XS GIS Cut Line= 3
      2708571.74      6830540.78      2708228.50      6830706.13
      2707816.79      6830909.75
#Sta/Elev= 30
  4619.0  381.61  4721.5  380.61  4727.0  379.92  4744.1  379.88  4789.3  378.07
  4879.8  376.29  4891.8  375.48  4925.0  374.43  4930.6  374.66  4947.3  374.00
  4958.8  374.23  4971.7  371.57  4972.2  371.07  4979.5  371.07  4980.0  371.57
  4991.7  375.22  5004.2  375.71  5020.9  374.70  5093.8  376.84  5110.6  376.58
  5161.1  377.32  5200.4  376.25  5228.4  376.22  5237.1  375.82  5267.7  376.48
  5273.2  375.96  5290.1  376.83  5379.8  378.04  5437.9  379.50  5459.3  379.32
#Mann=3,-1,0
  4619.0    0.05       0  4971.7    0.05       0  4980.0    0.05       0
Bank Sta=4971.7,4980
Exp/Cntr=0.3,0.1

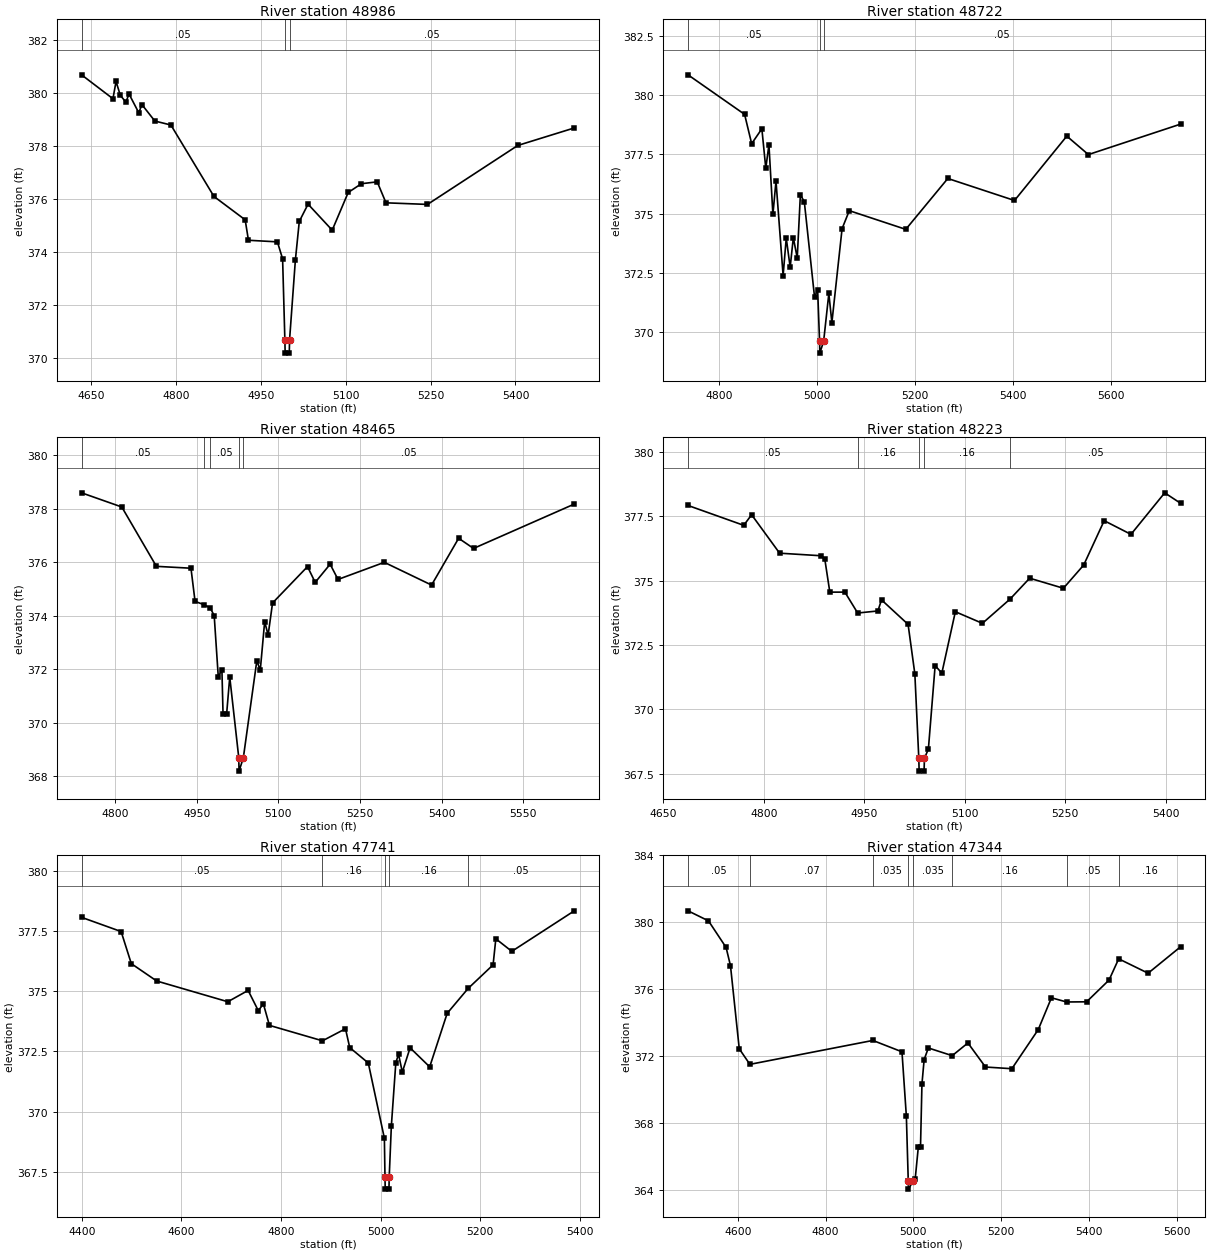
Type RM Length L Ch R = 1,48986,264,264,264
BEGIN DESCRIPTION:
Prairie Creek48986.31
END DESCRIPTION:
XS GIS Cut Line= 3
      2708508.11      6830341.04      2708173.95      6830497.04
      2707743.71      6830756.69
#Sta/Elev= 30
  4632.7  380.67  4688.2  379.77  4693.7  380.42  4701.2  379.90  4711.1  379.64
  4716.6  379.95  4733.9  379.24  4739.4  379.55  4762.3  378.93  4790.7  378.78
  4866.8  376.09  4922.0  375.21  4927.8  374.44  4979.0  374.38  4988.2  373.74
  4992.2  370.69  4992.7  370.19  5000.0  370.19  5000.5  370.69  5010.8  373.70
  5017.7  375.15  5033.2  375.80  5075.9  374.82  5104.2  376.24  5127.6  376.57
  5155.5  376.64  5171.0  375.85  5244.4  375.79  5404.0  378.01  5504.0  378.67
#Mann=3,-1,0
  4632.7    0.05       0  4992.2    0.05       0  5000.5    0.05       0
Bank Sta=4992.2,5000.5
Exp/Cntr=0.3,0.1

Type RM Length L Ch R = 1,48722,257,257,257
BEGIN DESCRIPTION:
Mapping XS 46c28997
END DESCRIPTION:
XS GIS Cut Line= 3
      2708431.89      6830084.74      2708216.39      6830256.44
      2707627.82      6830686.19
#Sta/Elev= 30
  4737.4  380.86  4852.7  379.19  4867.1  377.95  4887.9  378.58  4895.9  376.91
  4902.3  377.91  4910.4  374.96  4916.7  376.37  4931.2  372.38  4937.6  373.96
  4945.6  372.73  4952.0  373.98  4960.0  373.12  4966.4  375.79  4974.4  375.50
  4995.2  371.48  5001.6  371.77  5005.5  369.60  5006.0  369.10  5013.8  369.60
  5024.4  371.62  5030.6  370.39  5051.4  374.36  5066.1  375.12  5181.2  374.33
  5266.9  376.48  5402.8  375.55  5509.4  378.27  5553.4  377.49  5741.7  378.78
#Mann=3,-1,0
  4737.4    0.05       0  5005.5    0.05       0  5013.8    0.05       0
Bank Sta=5005.5,5013.8
Exp/Cntr=0.3,0.1

Type RM Length L Ch R = 1,48465,242,242,242
BEGIN DESCRIPTION:
Prairie Creek48497.72
END DESCRIPTION:
XS GIS Cut Line= 3
      2708211.48      6829912.17      2708038.13      6830108.63
      2707643.13      6830617.39
#Sta/Elev= 30
  4738.0  378.60  4812.0  378.07  4875.6  375.85  4939.2  375.78  4946.7  374.54
  4962.5  374.42  4974.4  374.30  4981.9  374.01  4989.4  371.72  4996.1  371.98
  4998.2  370.31  5004.7  370.31  5010.5  371.71  5027.1  368.69  5027.6  368.19
  5035.5  368.69  5060.3  372.32  5066.6  371.96  5074.7  373.78  5081.1  373.28
  5089.2  374.48  5153.5  375.84  5167.6  375.25  5195.1  375.93  5209.6  375.36
  5294.7  376.00  5381.6  375.15  5431.4  376.90  5458.8  376.52  5644.1  378.18
#Mann=5,-1,0
  4738.0    0.05       0  4962.5    0.16       0  4974.4    0.05       0
  5027.1    0.05       0  5035.5    0.05       0
Bank Sta=5027.1,5035.5
Exp/Cntr=0.3,0.1

Type RM Length L Ch R = 1,48223,482,482,482
BEGIN DESCRIPTION:
Mapping XS 16bc51e6
END DESCRIPTION:
XS GIS Cut Line= 3
      2708193.66      6829823.45      2707900.11      6829936.25
      2707482.25      6829991.66
#Sta/Elev= 30
  4686.7  377.91  4769.9  377.14  4781.7  377.55  4823.5  376.06  4885.7  375.96
  4891.0  375.83  4898.5  374.55  4921.0  374.55  4940.1  373.74  4970.3  373.82
  4975.7  374.25  5015.4  373.30  5025.5  371.38  5031.4  368.11  5031.9  367.61
  5039.3  367.61  5039.8  368.11  5045.7  368.46  5055.8  371.70  5065.8  371.41
  5086.0  373.79  5126.4  373.34  5167.7  374.28  5197.0  375.09  5247.4  374.70
  5277.7  375.60  5308.3  377.32  5348.3  376.79  5398.7  378.40  5422.7  377.99
#Mann=5,-1,0
  4686.7    0.05       0  4940.1    0.16       0  5031.4    0.07       0
  5039.8    0.16       0  5167.7    0.05       0
Bank Sta=5031.4,5039.8
Exp/Cntr=0.3,0.1

Type RM Length L Ch R = 1,47741,397,397,397
BEGIN DESCRIPTION:
Prairie Creek48117.07
END DESCRIPTION:
XS GIS Cut Line= 3
      2708233.98      6829699.69      2707645.14      6829581.42
      2707483.59      6829935.17
#Sta/Elev= 30
  4399.4  378.06  4478.9  377.47  4499.3  376.14  4550.3  375.42  4693.1  374.56
  4733.9  375.03  4754.3  374.19  4764.5  374.47  4776.7  373.58  4883.2  372.94
  4929.4  373.44  4937.9  372.66  4975.2  372.02  5007.5  368.90  5008.7  367.29
  5009.2  366.79  5016.7  366.79  5017.2  367.29  5021.5  369.41  5030.5  372.04
  5036.0  372.38  5043.5  371.64  5059.1  372.65  5098.5  371.86  5133.6  374.08
  5175.6  375.11  5225.8  376.09  5231.3  377.17  5263.4  376.65  5388.9  378.33
#Mann=5,-1,0
  4399.4    0.05       0  4883.2    0.16       0  5008.7    0.07       0
  5017.2    0.16       0  5175.6    0.05       0
Bank Sta=5008.7,5017.2
Exp/Cntr=0.3,0.1

Type RM Length L Ch R = 1,47344,347,347,347
BEGIN DESCRIPTION:
Prairie Creek47344.16
END DESCRIPTION:
XS GIS Cut Line= 3
      2707520.93      6828764.48      2707491.31      6829290.22
      2707463.06      6829885.27
#Sta/Elev= 30
  4486.8  380.69  4533.4  380.09  4573.5  378.50  4583.5  377.41  4603.5  372.44
  4627.7  371.51  4907.8  372.94  4974.1  372.26  4984.1  368.40  4988.4  364.55
  4988.9  364.05  4999.9  364.55  5004.1  364.63  5011.3  366.56  5016.3  366.56
  5019.6  370.34  5024.6  371.80  5034.2  372.49  5088.5  372.03  5124.3  372.79
  5164.3  371.35  5224.4  371.25  5284.5  373.59  5314.5  375.49  5349.0  375.24
  5394.6  375.25  5445.7  376.55  5467.7  377.82  5534.7  376.96  5609.1  378.55
#Mann=8,-1,0
  4486.8    0.05       0  4627.7    0.07       0  4907.8   0.035       0
  4988.4   0.035       0  4999.9   0.035       0  5088.5    0.16       0
  5349.0    0.05       0  5467.7    0.16       0
Bank Sta=4988.4,4999.9
Exp/Cntr=0.3,0.1

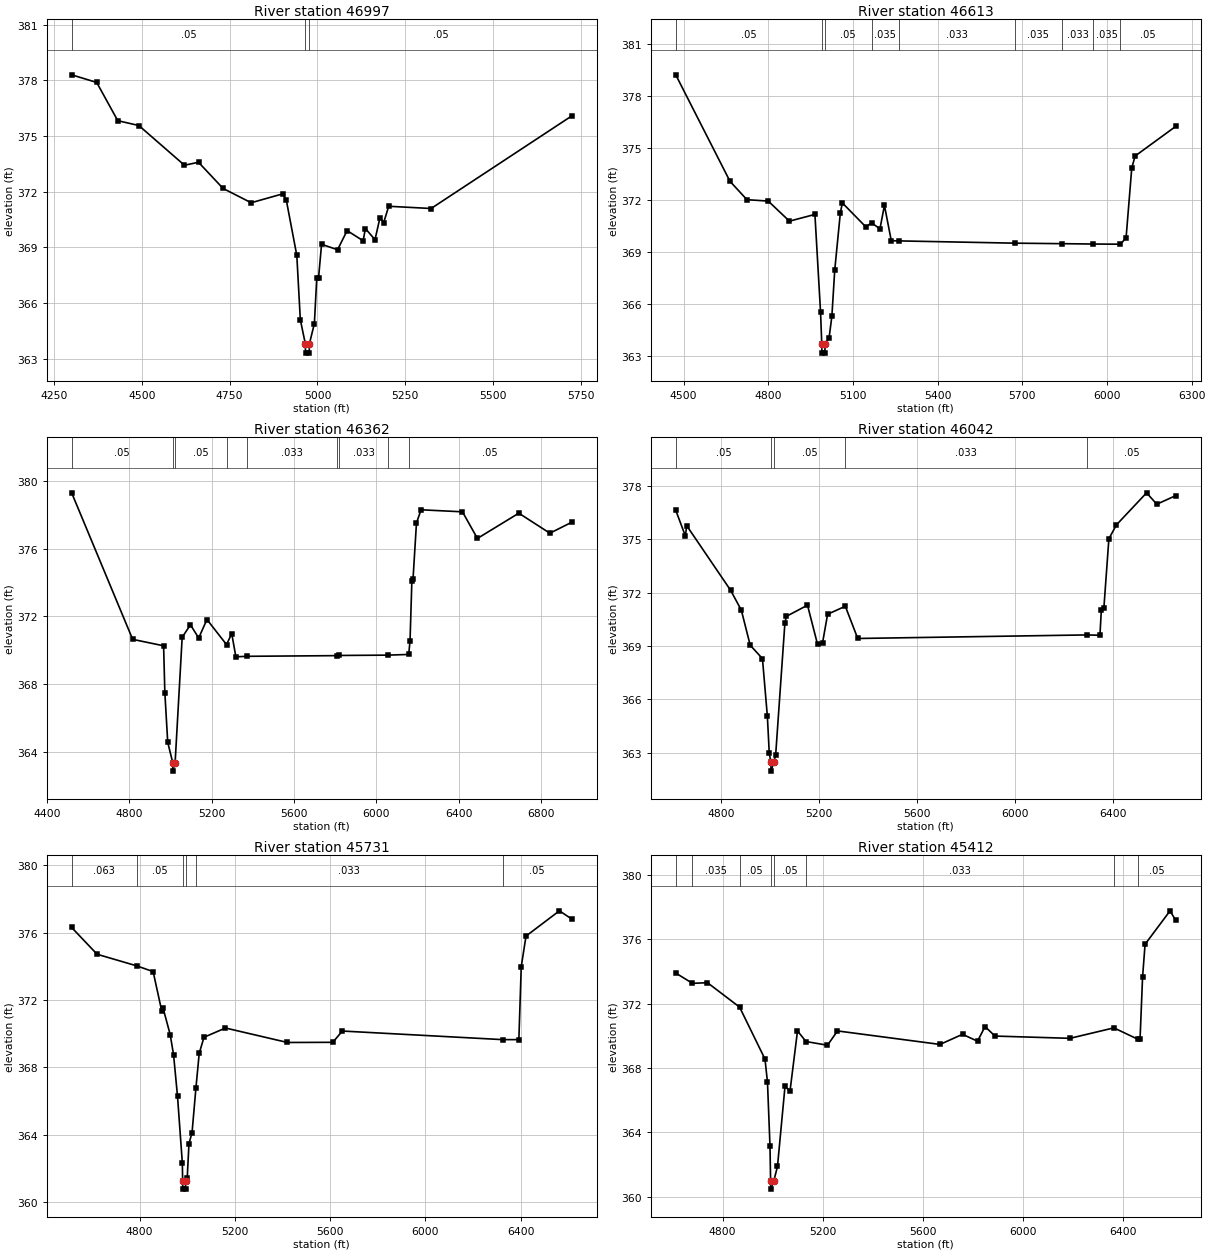
Type RM Length L Ch R = 1,46997,384,384,384
BEGIN DESCRIPTION:
Prairie Creek46965.74
END DESCRIPTION:
XS GIS Cut Line= 3
      2707190.47      6828459.70      2707185.59      6829159.79
      2707384.36      6829855.76
#Sta/Elev= 30
  4299.9  378.29  4371.2  377.88  4431.2  375.82  4491.2  375.56  4621.2  373.42
  4661.2  373.58  4731.2  372.17  4811.2  371.40  4901.2  371.88  4911.2  371.55
  4941.2  368.56  4951.2  365.10  4965.5  363.80  4966.0  363.30  4976.5  363.30
  4977.0  363.80  4991.2  364.89  4998.1  367.37  5003.2  367.37  5011.7  369.16
  5057.3  368.87  5084.5  369.90  5130.1  369.35  5136.5  370.01  5163.9  369.41
  5178.1  370.60  5188.5  370.32  5202.9  371.21  5323.7  371.09  5723.8  376.07
#Mann=3,-1,0
  4299.9    0.05       0  4965.5    0.05       0  4977.0    0.05       0
Bank Sta=4965.5,4977
Exp/Cntr=0.3,0.1

Type RM Length L Ch R = 1,46613,251,251,251
BEGIN DESCRIPTION:
Prairie Creek46612.85
END DESCRIPTION:
XS GIS Cut Line= 3
      2706916.49      6828429.42      2706874.97      6828961.87
      2706791.03      6830196.26
#Sta/Elev= 30
  4472.1  379.22  4664.3  373.07  4724.4  372.01  4799.8  371.93  4874.9  370.77
  4965.2  371.16  4985.2  365.51  4989.5  363.65  4990.0  363.15  5000.5  363.15
  5001.0  363.65  5015.3  364.02  5025.3  365.28  5035.4  367.94  5055.4  371.27
  5062.6  371.82  5145.6  370.44  5165.9  370.67  5195.7  370.33  5211.5  371.68
  5235.8  369.64  5263.9  369.63  5672.7  369.50  5841.0  369.47  5949.8  369.45
  6047.8  369.44  6067.7  369.81  6087.8  373.83  6099.6  374.53  6243.4  376.24
#Mann=9,-1,0
  4472.1    0.05       0  4989.5    0.05       0  5001.0    0.05       0
  5165.9   0.035       0  5263.9   0.033       0  5672.7   0.035       0
  5841.0   0.033       0  5949.8   0.035       0  6047.8    0.05       0
Bank Sta=4989.5,5001
Exp/Cntr=0.3,0.1

Type RM Length L Ch R = 1,46362,320,320,320
BEGIN DESCRIPTION:
Prairie Creek46219.55
END DESCRIPTION:
XS GIS Cut Line= 4
      2706687.09      6828365.19      2706659.51      6828843.90
      2706571.23      6829971.52      2706204.79      6830702.43
#Sta/Elev= 30
  4520.5  379.29  4816.8  370.65  4967.1  370.27  4973.1  367.51  4987.1  364.58
  5011.4  363.38  5011.9  362.88  5023.0  363.38  5057.3  370.77  5097.4  371.51
  5137.5  370.73  5177.6  371.82  5272.8  370.34  5298.0  370.99  5318.1  369.62
  5370.8  369.65  5807.8  369.69  5820.2  369.70  6057.1  369.72  6157.6  369.76
  6164.1  370.57  6172.9  374.07  6178.5  374.19  6195.3  377.51  6217.6  378.29
  6418.7  378.17  6491.3  376.60  6692.4  378.09  6843.2  376.91  6948.7  377.55
#Mann=9,-1,0
  4520.5    0.05       0  5011.4    0.05       0  5023.0    0.05       0
  5272.8   0.035       0  5370.8   0.033       0  5807.8   0.035       0
  5820.2   0.033       0  6057.1   0.035       0  6157.6    0.05       0
Bank Sta=5011.4,5023
Exp/Cntr=0.3,0.1

Type RM Length L Ch R = 1,46042,311,311,311
BEGIN DESCRIPTION:
Prairie Creek46042.043
END DESCRIPTION:
XS GIS Cut Line= 3
      2706402.79      6828337.52      2706385.78      6828721.54
      2706023.15      6830336.84
#Sta/Elev= 30
  4615.6  376.62  4655.1  375.17  4660.1  375.76  4839.3  372.13  4883.2  371.01
  4919.4  369.04  4969.4  368.29  4989.5  365.04  4997.2  362.97  5003.8  362.47
  5004.3  361.97  5015.5  362.47  5023.4  362.90  5060.9  370.27  5066.8  370.66
  5153.2  371.29  5194.2  369.09  5214.7  369.18  5235.2  370.78  5307.5  371.23
  5358.2  369.42  6294.2  369.62  6346.5  369.60  6352.3  371.04  6362.5  371.12
  6383.0  375.02  6413.8  375.80  6536.8  377.60  6578.5  376.96  6655.5  377.44
#Mann=5,-1,0
  4615.6    0.05       0  5003.8    0.05       0  5015.5    0.05       0
  5307.5   0.033       0  6294.2    0.05       0
Bank Sta=5003.8,5015.5
Exp/Cntr=0.3,0.1

Type RM Length L Ch R = 1,45731,319,319,319
BEGIN DESCRIPTION:
Mapping XS b5c9ac5b
END DESCRIPTION:
XS GIS Cut Line= 3
      2705991.65      6828186.58      2706095.26      6828670.32
      2706011.80      6830272.03
#Sta/Elev= 30
  4514.9  376.31  4621.7  374.72  4788.3  374.03  4856.9  373.69  4893.2  371.34
  4898.4  371.53  4928.5  369.95  4942.7  368.75  4959.2  366.29  4979.6  362.31
  4980.7  361.27  4981.2  360.77  4992.8  360.77  4993.3  361.27  5000.1  361.46
  5007.4  363.48  5020.3  364.13  5036.4  366.76  5050.4  368.84  5070.4  369.79
  5160.5  370.34  5420.9  369.48  5611.1  369.49  5651.2  370.16  6323.6  369.65
  6392.2  369.65  6402.2  373.98  6422.2  375.80  6562.4  377.30  6613.5  376.82
#Mann=6,-1,0
  4514.9   0.063       0  4788.3    0.05       0  4980.7    0.05       0
  4993.3    0.05       0  5036.4   0.033       0  6323.6    0.05       0
Bank Sta=4980.7,4993.3
Exp/Cntr=0.3,0.1

Type RM Length L Ch R = 1,45412,431,431,431
BEGIN DESCRIPTION:
Prairie Creek45411.66
END DESCRIPTION:
XS GIS Cut Line= 3
      2705795.50      6828224.08      2705790.31      6828613.62
      2705757.38      6830223.41
#Sta/Elev= 30
  4612.4  373.91  4679.3  373.27  4739.3  373.31  4867.8  371.79  4969.3  368.56
  4979.3  367.13  4989.3  363.18  4991.8  360.97  4992.3  360.47  5004.5  360.97
  5019.4  361.89  5049.4  366.86  5069.4  366.56  5099.4  370.31  5133.4  369.65
  5219.4  369.42  5259.4  370.31  5669.5  369.47  5759.5  370.10  5819.5  369.67
  5849.5  370.58  5889.5  369.99  6189.6  369.85  6364.9  370.50  6462.7  369.78
  6469.7  369.82  6479.7  373.65  6489.7  375.70  6589.7  377.78  6612.1  377.19
#Mann=8,-1,0
  4612.4   0.063       0  4679.3   0.035       0  4867.8    0.05       0
  4991.8    0.05       0  5004.5    0.05       0  5133.4   0.033       0
  6364.9   0.035       0  6462.7    0.05       0
Bank Sta=4991.8,5004.5
Exp/Cntr=0.3,0.1

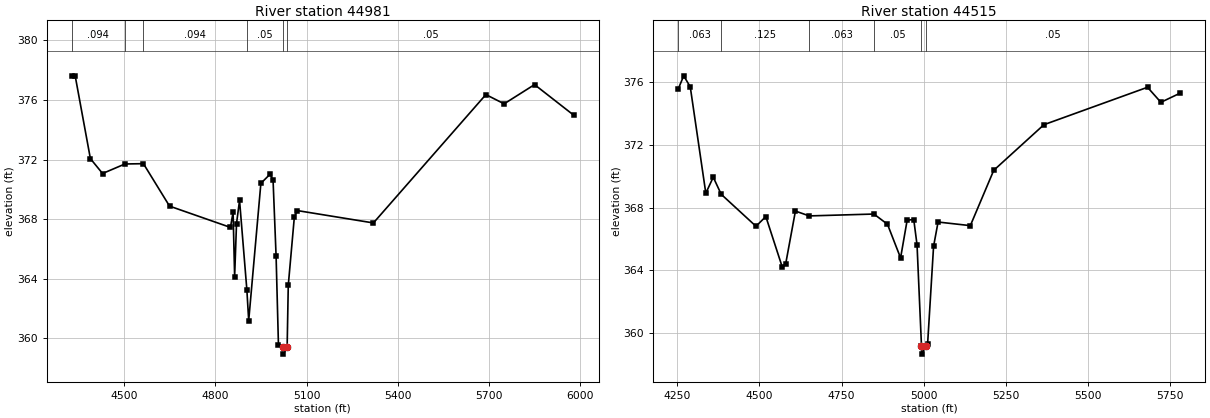
Type RM Length L Ch R = 1,44981,466,466,466
BEGIN DESCRIPTION:
Prairie Creek44980.87
END DESCRIPTION:
XS GIS Cut Line= 3
      2705436.78      6828039.79      2705391.08      6828721.44
      2705347.02      6829690.26
#Sta/Elev= 30
  4326.8  377.59  4338.0  377.62  4388.1  372.06  4428.2  371.06  4501.9  371.70
  4562.7  371.72  4648.7  368.87  4849.2  367.44  4857.9  368.46  4863.0  364.14
  4869.2  367.70  4879.2  369.25  4903.3  363.24  4909.3  361.18  4949.4  370.40
  4979.5  371.01  4989.5  370.63  4999.5  365.51  5007.3  359.52  5023.2  359.43
  5023.7  358.93  5035.9  359.43  5039.6  363.55  5059.6  368.14  5069.6  368.57
  5319.9  367.74  5690.2  376.36  5750.3  375.74  5850.4  377.03  5979.8  374.97
#Mann=6,-1,0
  4326.8   0.094       0  4501.9   0.063       0  4562.7   0.094       0
  4903.3    0.05       0  5023.2    0.05       0  5035.9    0.05       0
Bank Sta=5023.2,5035.9
Exp/Cntr=0.3,0.1

Type RM Length L Ch R = 1,44515,400,400,400
BEGIN DESCRIPTION:
Prairie Creek44514.69
END DESCRIPTION:
XS GIS Cut Line= 3
      2704995.34      6828064.45      2704957.29      6828820.41
      2704810.74      6829579.07
#Sta/Elev= 30
  4252.5  375.58  4269.1  376.42  4289.1  375.72  4336.5  368.93  4359.2  369.95
  4383.4  368.86  4489.3  366.82  4519.4  367.44  4569.5  364.21  4579.5  364.38
  4609.5  367.79  4651.6  367.48  4848.6  367.60  4889.9  366.95  4929.9  364.80
  4949.9  367.21  4970.0  367.25  4980.0  365.64  4993.6  359.16  4994.1  358.66
  5006.4  359.16  5012.3  359.33  5030.4  365.54  5044.1  367.09  5142.4  366.86
  5213.7  370.39  5366.5  373.30  5682.2  375.69  5722.9  374.73  5782.1  375.32
#Mann=6,-1,0
  4252.5   0.063       0  4383.4   0.125       0  4651.6   0.063       0
  4848.6    0.05       0  4993.6    0.05       0  5006.4    0.05       0
Bank Sta=4993.6,5006.4
Exp/Cntr=0.3,0.1