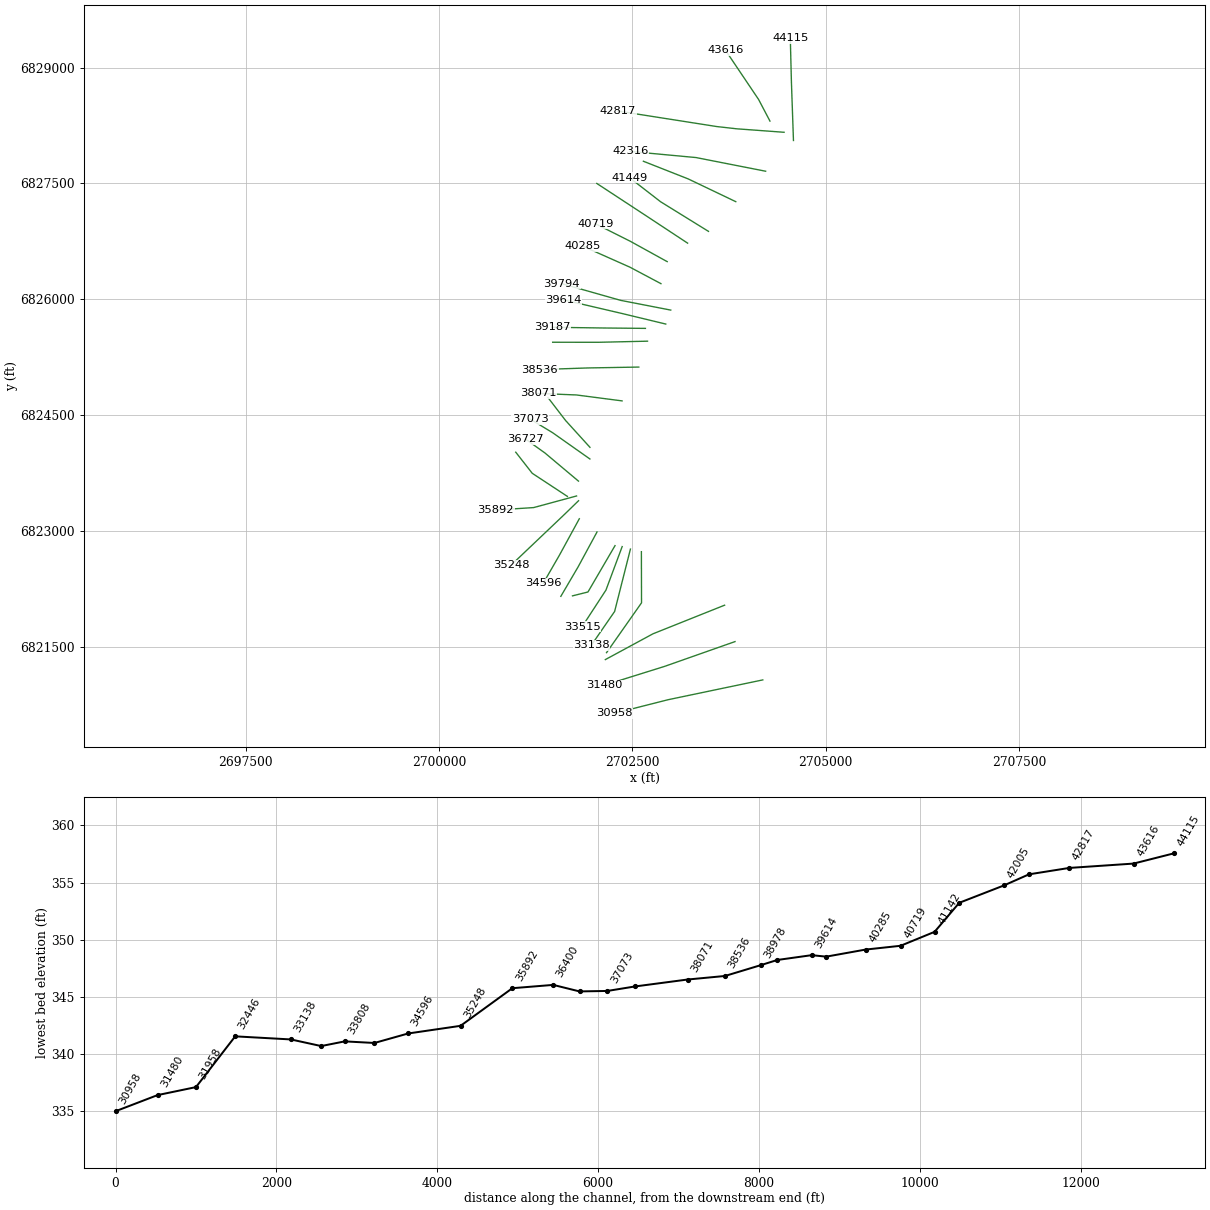
HEC-RAS study Prairie Creek.prj: Prairie Creek Base Level Engineering

--- Prairie Creek.g01 (geometry) --- (continued)

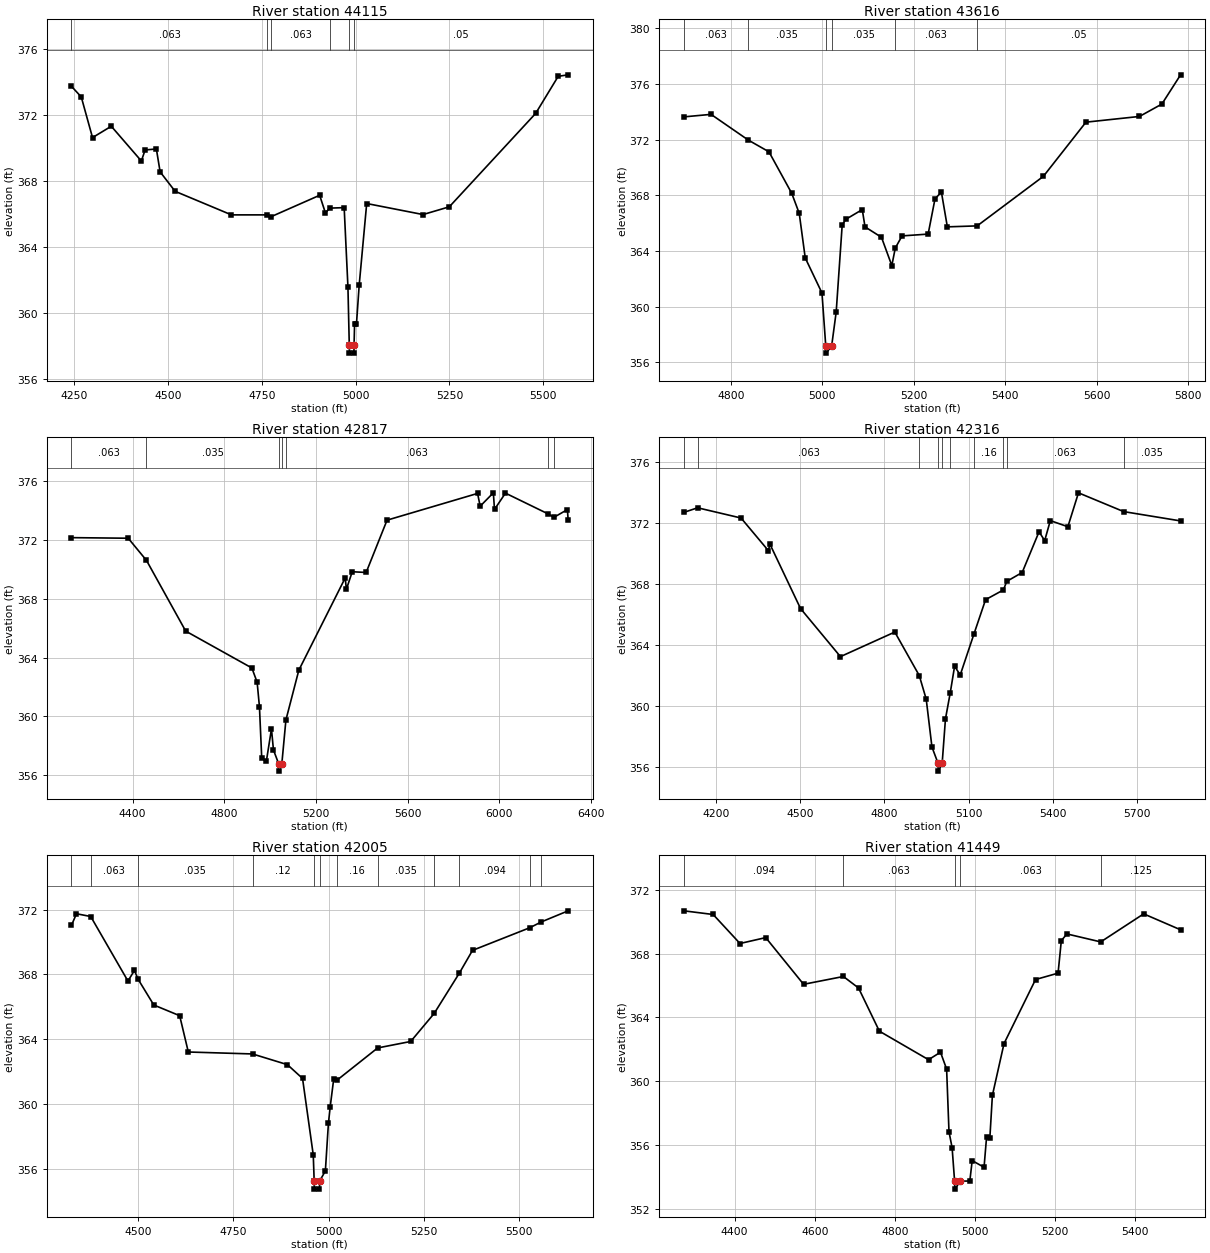
Type RM Length L Ch R = 1,44115,499,499,499
BEGIN DESCRIPTION:
Prairie Creek44085.5
END DESCRIPTION:
XS GIS Cut Line= 3
      2704584.07      6828055.06      2704557.65      6828811.40
      2704543.21      6829377.51
#Sta/Elev= 30
  4243.2  373.74  4269.2  373.10  4299.2  370.63  4349.2  371.32  4429.3  369.21
  4439.3  369.88  4469.3  369.94  4479.3  368.55  4519.3  367.37  4669.4  365.94
  4765.2  365.94  4775.9  365.84  4904.3  367.13  4919.6  366.06  4931.1  366.35
  4969.6  366.38  4979.6  361.58  4983.2  358.05  4983.7  357.55  4995.5  357.55
  4996.0  358.05  4997.3  359.30  5002.3  359.30  5009.6  361.68  5029.6  366.63
  5179.7  365.96  5249.7  366.43  5479.8  372.10  5539.8  374.35  5566.3  374.44
#Mann=6,-1,0
  4243.2   0.063       0  4765.2   0.035       0  4775.9   0.063       0
  4931.1    0.05       0  4983.2    0.05       0  4996.0    0.05       0
Bank Sta=4983.2,4996
Exp/Cntr=0.3,0.1

Type RM Length L Ch R = 1,43616,799,799,799
BEGIN DESCRIPTION:
Prairie Creek43615.76
END DESCRIPTION:
XS GIS Cut Line= 3
      2704280.04      6828306.26      2704132.58      6828586.95
      2703703.69      6829224.92
#Sta/Elev= 30
  4697.2  373.63  4756.5  373.81  4838.1  371.96  4883.1  371.12  4932.9  368.14
  4949.3  366.70  4962.4  363.50  4999.0  360.98  5007.3  357.16  5007.8  356.66
  5020.1  357.16  5030.1  359.62  5043.2  365.86  5051.1  366.27  5087.1  366.97
  5093.1  365.73  5129.1  364.98  5151.7  362.95  5159.3  364.21  5174.1  365.08
  5231.1  365.21  5246.1  367.74  5260.1  368.23  5273.1  365.73  5338.3  365.80
  5483.1  369.36  5576.1  373.25  5693.1  373.66  5742.1  374.55  5783.0  376.65
#Mann=6,-1,0
  4697.2   0.063       0  4838.1   0.035       0  5007.3   0.035       0
  5020.1   0.035       0  5159.3   0.063       0  5338.3    0.05       0
Bank Sta=5007.3,5020.1
Exp/Cntr=0.3,0.1

Type RM Length L Ch R = 1,42817,501,501,501
BEGIN DESCRIPTION:
Prairie Creek42817.24
END DESCRIPTION:
XS GIS Cut Line= 4
      2704462.62      6828161.50      2703850.24      6828206.49
      2703593.88      6828235.31      2702315.77      6828436.19
#Sta/Elev= 30
  4133.9  372.17  4381.2  372.13  4460.9  370.62  4631.9  365.81  4920.4  363.30
  4943.4  362.33  4953.5  360.66  4963.5  357.15  4983.6  356.95  5005.9  359.15
  5014.6  357.72  5037.3  356.78  5037.8  356.28  5051.1  356.78  5068.9  359.76
  5125.2  363.15  5327.5  369.43  5332.6  368.65  5358.1  369.85  5418.8  369.80
  5509.9  373.36  5904.7  375.18  5916.0  374.31  5973.5  375.22  5978.5  374.09
  6026.2  375.20  6213.0  373.78  6237.3  373.55  6296.5  374.08  6299.7  373.35
#Mann=7,-1,0
  4133.9   0.063       0  4460.9   0.035       0  5037.3   0.035       0
  5051.1   0.035       0  5068.9   0.063       0  6213.0   0.094       0
  6237.3   0.035       0
Bank Sta=5037.3,5051.1
Exp/Cntr=0.3,0.1

Type RM Length L Ch R = 1,42316,311,311,311
BEGIN DESCRIPTION:
Prairie Creek42315.51
END DESCRIPTION:
XS GIS Cut Line= 3
      2704224.18      6827657.36      2703323.75      6827834.35
      2702473.29      6827913.53
#Sta/Elev= 30
  4084.6  372.67  4133.4  372.97  4288.3  372.30  4386.0  370.16  4391.1  370.60
  4500.6  366.37  4643.0  363.22  4836.9  364.83  4924.2  361.98  4949.0  360.43
  4969.4  357.30  4991.4  356.22  4991.9  355.72  5005.8  356.22  5017.6  359.14
  5034.5  360.83  5050.2  362.59  5070.3  362.02  5119.4  364.71  5160.7  366.95
  5224.4  367.59  5236.2  368.15  5291.3  368.73  5351.5  371.40  5371.6  370.82
  5391.7  372.13  5454.3  371.73  5492.1  373.95  5653.4  372.72  5856.4  372.11
#Mann=10,-1,0
  4084.6   0.125       0  4133.4   0.063       0  4924.2    0.16       0
  4991.4    0.07       0  5005.8    0.16       0  5034.5   0.035       0
  5119.4    0.16       0  5224.4   0.035       0  5236.2   0.063       0
  5653.4   0.035       0
Bank Sta=4991.4,5005.8
Exp/Cntr=0.3,0.1

Type RM Length L Ch R = 1,42005,556,556,556
BEGIN DESCRIPTION:
Prairie Creek42004.85
END DESCRIPTION:
XS GIS Cut Line= 3
      2703837.81      6827263.47      2703222.68      6827557.80
      2702642.78      6827786.53
#Sta/Elev= 30
  4324.4  371.03  4337.5  371.74  4374.9  371.57  4472.7  367.59  4489.8  368.24
  4499.4  367.70  4540.7  366.11  4608.7  365.45  4631.4  363.21  4800.1  363.09
  4891.8  362.43  4931.6  361.58  4959.8  356.86  4962.2  355.25  4962.7  354.75
  4976.1  354.75  4976.6  355.25  4991.6  355.87  4999.6  358.80  5004.2  359.81
  5013.5  361.54  5021.6  361.46  5129.0  363.46  5215.9  363.86  5277.6  365.59
  5343.8  368.08  5378.3  369.48  5529.2  370.88  5558.6  371.23  5629.7  371.92
#Mann=12,-1,0
  4324.4   0.094       0  4374.9   0.063       0  4499.4   0.035       0
  4800.1    0.12       0  4962.2    0.07       0  4976.6    0.12       0
  5021.6    0.16       0  5129.0   0.035       0  5277.6   0.063       0
  5343.8   0.094       0  5529.2   0.125       0  5558.6   0.094       0
Bank Sta=4962.2,4976.6
Exp/Cntr=0.3,0.1

Type RM Length L Ch R = 1,41449,307,307,307
BEGIN DESCRIPTION:
Prairie Creek41449.25
END DESCRIPTION:
XS GIS Cut Line= 3
      2703484.96      6826878.84      2702865.65      6827262.24
      2702461.79      6827575.18
#Sta/Elev= 30
  4273.7  370.69  4346.6  370.46  4413.6  368.64  4477.8  369.01  4572.3  366.08
  4671.6  366.57  4709.4  365.85  4761.4  363.14  4884.1  361.35  4913.9  361.82
  4929.2  360.76  4935.1  356.83  4942.9  355.83  4949.1  353.73  4949.6  353.23
  4963.6  353.73  4987.1  353.74  4993.0  355.02  5022.6  354.60  5028.9  356.50
  5037.1  356.45  5043.4  359.11  5072.4  362.36  5151.1  366.38  5207.3  366.78
  5215.4  368.82  5229.4  369.24  5313.7  368.74  5420.9  370.50  5513.0  369.50
#Mann=5,-1,0
  4273.7   0.094       0  4671.6   0.063       0  4949.1   0.063       0
  4963.6   0.063       0  5313.7   0.125       0
Bank Sta=4949.1,4963.6
Exp/Cntr=0.3,0.1

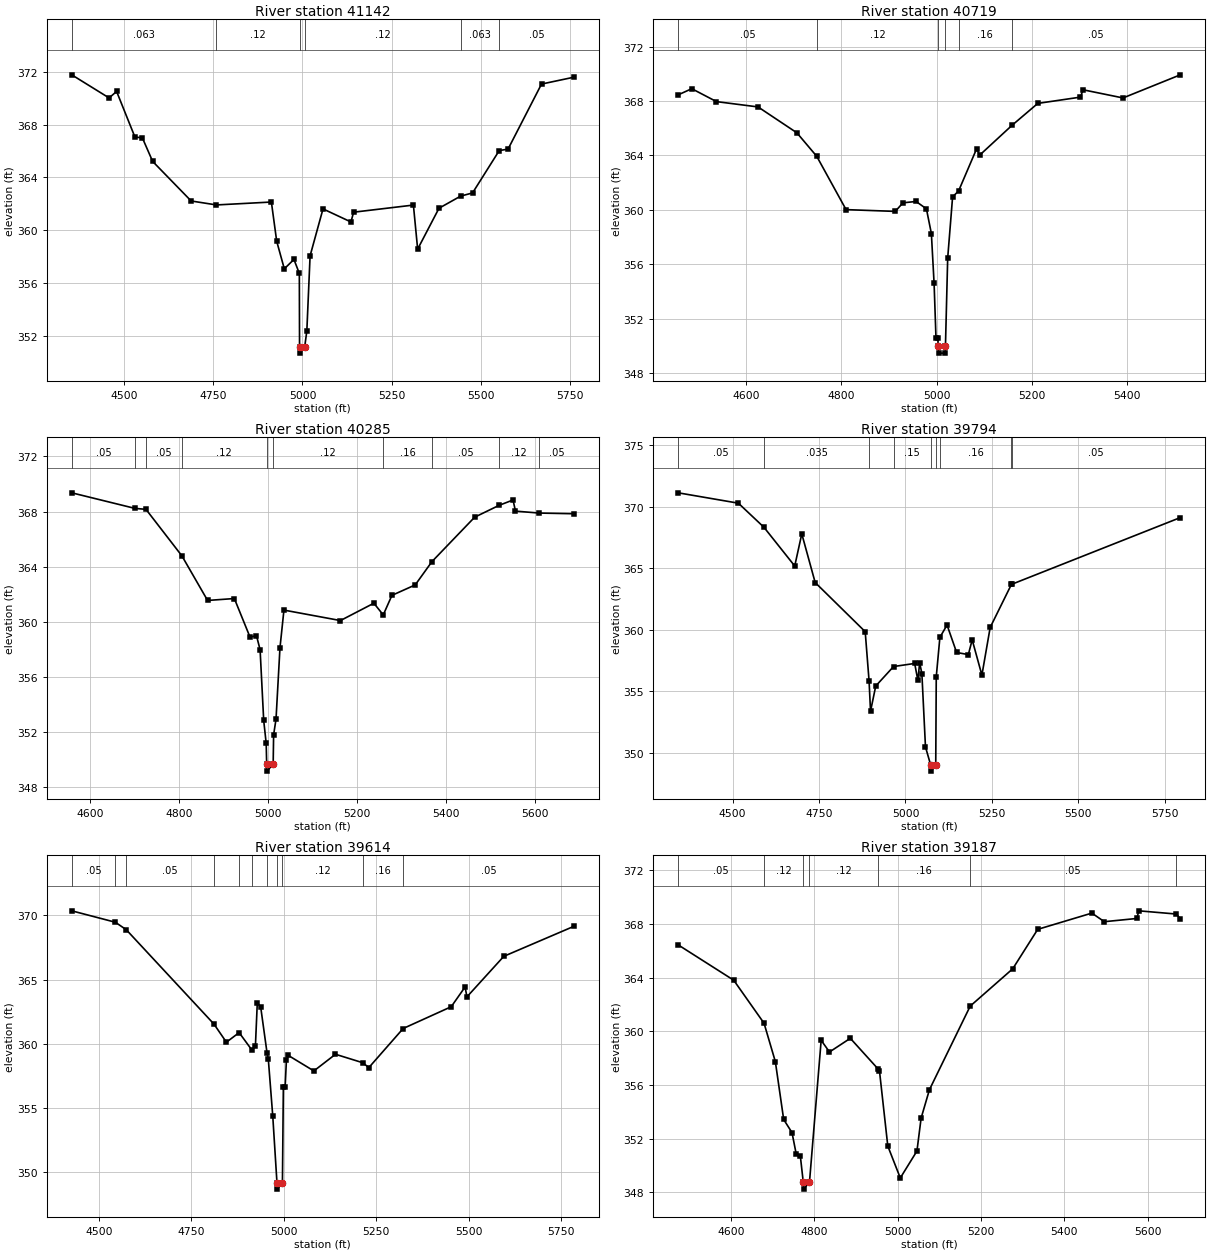
Type RM Length L Ch R = 1,41142,423,423,423
BEGIN DESCRIPTION:
Prairie Creek41141.77
END DESCRIPTION:
XS GIS Cut Line= 3
      2703215.10      6826726.36      2702672.01      6827084.68
      2702040.28      6827499.32
#Sta/Elev= 30
  4353.9  371.78  4458.4  370.03  4479.5  370.52  4530.7  367.07  4551.7  367.00
  4580.4  365.22  4688.3  362.22  4759.2  361.92  4913.0  362.14  4927.9  359.17
  4949.2  357.08  4976.2  357.79  4991.3  356.73  4991.9  351.19  4992.4  350.69
  5006.4  351.19  5012.3  352.36  5021.4  358.06  5057.6  361.62  5135.9  360.63
  5143.3  361.37  5310.8  361.91  5322.7  358.57  5382.5  361.67  5443.2  362.59
  5476.5  362.83  5551.2  366.04  5575.9  366.15  5669.6  371.08  5760.2  371.60
#Mann=6,-1,0
  4353.9   0.063       0  4759.2    0.12       0  4991.9    0.07       0
  5006.4    0.12       0  5443.2   0.063       0  5551.2    0.05       0
Bank Sta=4991.9,5006.4
Exp/Cntr=0.3,0.1

Type RM Length L Ch R = 1,40719,434,434,434
BEGIN DESCRIPTION:
Prairie Creek40719.32
END DESCRIPTION:
XS GIS Cut Line= 3
      2702950.91      6826487.08      2702474.70      6826749.89
      2702020.40      6826978.29
#Sta/Elev= 30
  4458.6  368.46  4487.0  368.91  4538.8  367.96  4625.9  367.57  4707.2  365.67
  4748.9  363.94  4810.4  360.02  4913.5  359.89  4929.6  360.52  4957.1  360.62
  4978.8  360.08  4989.2  358.26  4994.9  354.59  4998.9  350.56  5002.5  350.56
  5004.1  349.97  5004.6  349.47  5018.2  349.47  5018.7  349.97  5023.4  356.46
  5033.7  360.96  5046.2  361.39  5084.0  364.49  5090.6  364.03  5158.3  366.22
  5212.3  367.83  5301.6  368.29  5307.2  368.83  5390.9  368.23  5511.0  369.93
#Mann=6,-1,0
  4458.6    0.05       0  4748.9    0.12       0  5004.1    0.07       0
  5018.7    0.12       0  5046.2    0.16       0  5158.3    0.05       0
Bank Sta=5004.1,5018.7
Exp/Cntr=0.3,0.1

Type RM Length L Ch R = 1,40285,491,491,491
BEGIN DESCRIPTION:
Prairie Creek40285.16
END DESCRIPTION:
XS GIS Cut Line= 3
      2702869.95      6826202.08      2702472.01      6826413.88
      2701852.20      6826689.92
#Sta/Elev= 30
  4557.9  369.36  4699.9  368.23  4724.8  368.16  4805.6  364.78  4863.4  361.54
  4923.6  361.68  4958.9  358.87  4973.3  358.99  4981.5  357.96  4989.6  352.82
  4995.2  351.16  4996.3  349.64  4996.8  349.14  5010.9  349.64  5011.9  351.78
  5017.3  352.91  5026.2  358.10  5035.1  360.84  5162.2  360.08  5237.4  361.34
  5258.5  360.49  5278.0  361.91  5330.4  362.67  5368.0  364.36  5464.1  367.59
  5519.0  368.45  5550.4  368.84  5555.9  368.03  5609.2  367.89  5687.2  367.84
#Mann=10,-1,0
  4557.9    0.05       0  4699.9   0.035       0  4724.8    0.05       0
  4805.6    0.12       0  4996.3    0.07       0  5010.9    0.12       0
  5258.5    0.16       0  5368.0    0.05       0  5519.0    0.12       0
  5609.2    0.05       0
Bank Sta=4996.3,5010.9
Exp/Cntr=0.3,0.1

Type RM Length L Ch R = 1,39794,180,180,180
BEGIN DESCRIPTION:
Prairie Creek39793.69
END DESCRIPTION:
XS GIS Cut Line= 3
      2702996.76      6825859.90      2702350.17      6825985.54
      2701586.97      6826202.05
#Sta/Elev= 30
  4342.9  371.11  4516.8  370.27  4590.9  368.31  4679.8  365.17  4700.2  367.78
  4738.9  363.83  4883.6  359.84  4894.8  355.84  4899.0  353.38  4914.1  355.43
  4965.6  357.01  5026.7  357.26  5035.9  355.89  5041.1  357.32  5047.5  356.44
  5057.9  350.49  5072.9  349.02  5073.4  348.52  5087.6  349.02  5089.1  356.18
  5099.6  359.38  5120.3  360.38  5148.0  358.15  5181.9  357.98  5193.0  359.18
  5221.1  356.31  5245.0  360.18  5306.5  363.68  5306.8  363.68  5794.9  369.10
#Mann=9,-1,0
  4342.9    0.05       0  4590.9   0.035       0  4894.8    0.16       0
  4965.6    0.15       0  5072.9    0.07       0  5087.6    0.15       0
  5099.6    0.16       0  5306.5    0.12       0  5306.8    0.05       0
Bank Sta=5072.9,5087.6
Exp/Cntr=0.3,0.1

Type RM Length L Ch R = 1,39614,427,427,427
BEGIN DESCRIPTION:
Prairie Creek39614.29
END DESCRIPTION:
XS GIS Cut Line= 3
      2702932.46      6825679.22      2702371.68      6825814.58
      2701611.54      6825992.20
#Sta/Elev= 30
  4427.2  370.36  4545.0  369.47  4574.4  368.89  4811.8  361.52  4845.3  360.11
  4879.7  360.86  4914.2  359.50  4923.7  359.80  4928.8  363.17  4937.9  362.88
  4955.1  359.29  4958.5  358.83  4970.7  354.32  4982.0  349.15  4982.5  348.65
  4996.8  349.15  4999.3  356.62  5004.1  356.62  5007.5  358.69  5012.7  359.08
  5081.8  357.87  5140.2  359.17  5214.0  358.51  5230.4  358.13  5323.2  361.18
  5453.2  362.88  5490.6  364.42  5495.7  363.65  5595.3  366.81  5784.7  369.15
#Mann=11,-1,0
  4427.2    0.05       0  4545.0   0.035       0  4574.4    0.05       0
  4811.8    0.16       0  4879.7   0.035       0  4914.2    0.16       0
  4955.1    0.12       0  4982.0    0.07       0  4996.8    0.12       0
  5214.0    0.16       0  5323.2    0.05       0
Bank Sta=4982,4996.8
Exp/Cntr=0.3,0.1

Type RM Length L Ch R = 1,39187,209,209,209
BEGIN DESCRIPTION:
Prairie Creek39187.42
END DESCRIPTION:
XS GIS Cut Line= 3
      2702669.17      6825623.12      2702128.16      6825628.19
      2701463.65      6825637.41
#Sta/Elev= 30
  4473.1  366.43  4606.3  363.80  4679.2  360.59  4706.3  357.73  4726.3  353.42
  4746.3  352.44  4756.3  350.86  4766.3  350.69  4773.4  348.73  4773.9  348.23
  4788.2  348.73  4816.3  359.32  4836.3  358.45  4886.3  359.47  4953.4  357.17
  4956.3  357.05  4976.3  351.44  5006.3  349.06  5046.3  351.07  5056.3  353.52
  5076.3  355.64  5174.2  361.87  5276.3  364.65  5336.3  367.59  5466.3  368.80
  5496.3  368.16  5574.2  368.40  5579.2  368.97  5669.3  368.73  5678.7  368.37
#Mann=7,-1,0
  4473.1    0.05       0  4679.2    0.12       0  4773.4    0.07       0
  4788.2    0.12       0  4953.4    0.16       0  5174.2    0.05       0
  5669.3   0.063       0
Bank Sta=4773.4,4788.2
Exp/Cntr=0.3,0.1

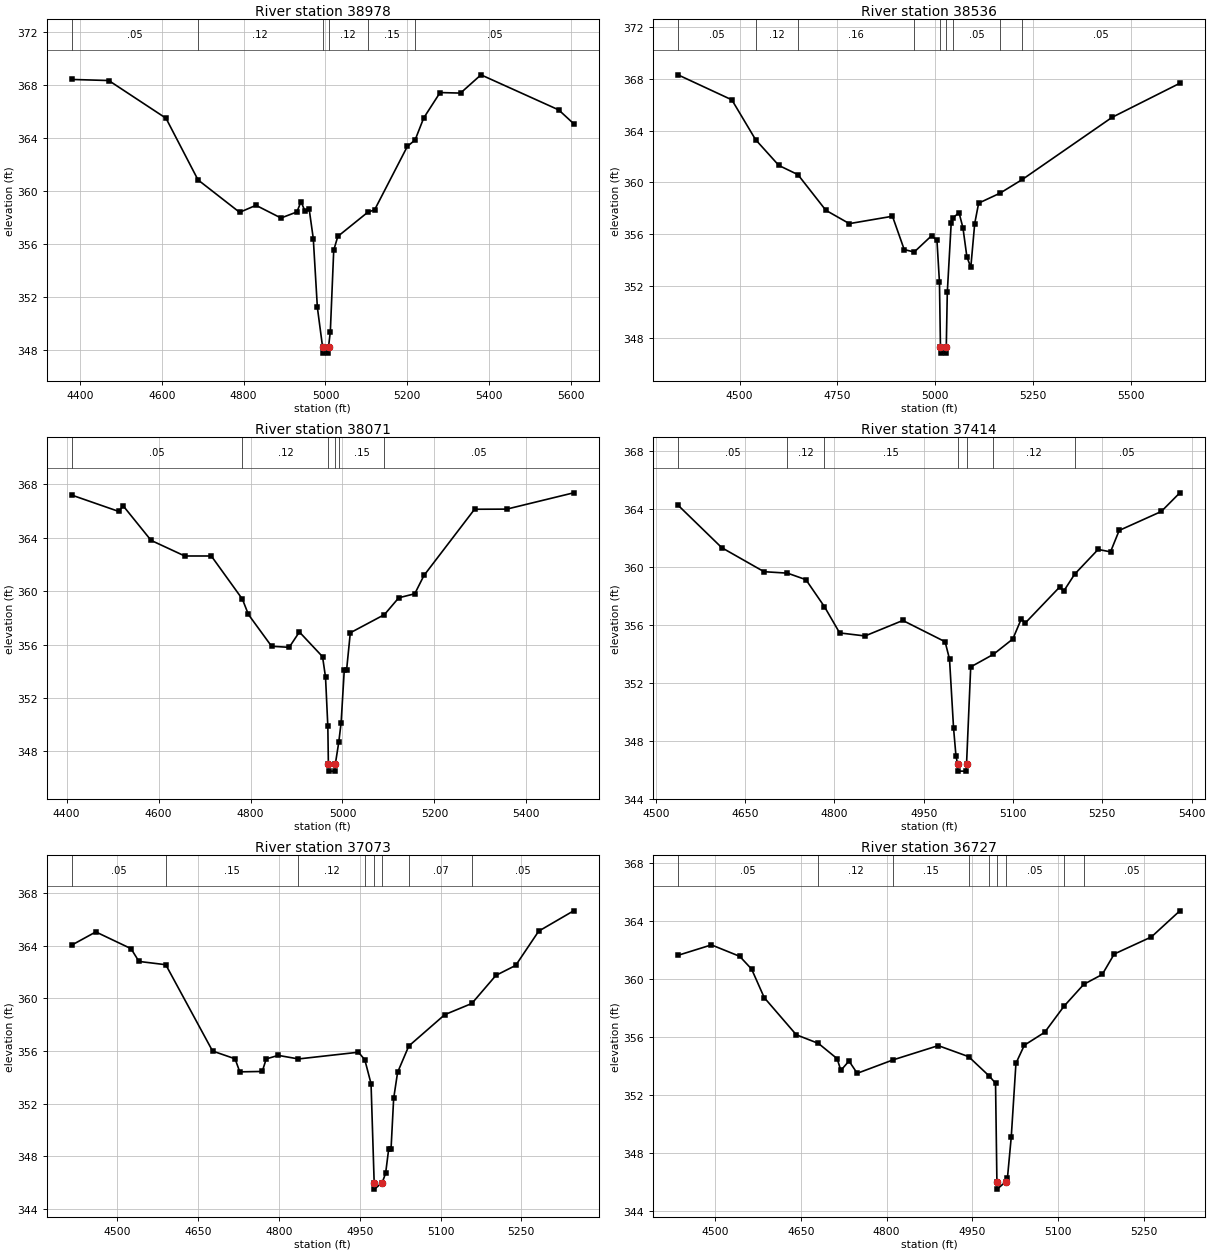
Type RM Length L Ch R = 1,38978,442,442,442
BEGIN DESCRIPTION:
Prairie Creek38977.65
END DESCRIPTION:
XS GIS Cut Line= 3
      2702696.33      6825457.49      2702067.67      6825443.26
      2701469.50      6825443.55
#Sta/Elev= 30
  4379.7  368.45  4470.1  368.37  4610.1  365.52  4688.4  360.86  4790.1  358.41
  4830.1  358.94  4891.3  357.98  4930.2  358.44  4940.2  359.22  4950.2  358.48
  4960.2  358.64  4970.2  356.43  4980.2  351.22  4992.8  348.27  4993.3  347.77
  5007.1  347.77  5007.6  348.27  5011.9  349.40  5020.2  355.55  5030.2  356.59
  5103.6  358.42  5120.2  358.60  5200.2  363.39  5219.2  363.88  5240.2  365.54
  5280.2  367.46  5330.2  367.42  5380.2  368.80  5570.2  366.15  5606.7  365.11
#Mann=6,-1,0
  4379.7    0.05       0  4688.4    0.12       0  4992.8    0.07       0
  5007.6    0.12       0  5103.6    0.15       0  5219.2    0.05       0
Bank Sta=4992.8,5007.6
Exp/Cntr=0.3,0.1

Type RM Length L Ch R = 1,38536,465,465,465
BEGIN DESCRIPTION:
Prairie Creek38536.33
END DESCRIPTION:
XS GIS Cut Line= 3
      2702583.48      6825122.44      2701922.34      6825110.94
      2701302.63      6825090.00
#Sta/Elev= 30
  4342.8  368.30  4480.3  366.37  4540.9  363.30  4600.3  361.31  4649.0  360.60
  4720.3  357.85  4780.3  356.82  4890.4  357.39  4920.4  354.82  4945.9  354.63
  4990.4  355.89  5004.0  355.53  5010.4  352.28  5012.9  347.33  5013.4  346.83
  5027.3  346.83  5027.8  347.33  5030.4  351.52  5040.4  356.89  5044.8  357.27
  5060.4  357.66  5070.4  356.49  5080.4  354.26  5090.4  353.45  5100.4  356.83
  5110.4  358.40  5165.0  359.17  5222.1  360.23  5451.1  365.02  5624.1  367.65
#Mann=9,-1,0
  4342.8    0.05       0  4540.9    0.12       0  4649.0    0.16       0
  4945.9    0.15       0  5012.9    0.07       0  5027.8    0.15       0
  5044.8    0.05       0  5165.0    0.15       0  5222.1    0.05       0
Bank Sta=5012.9,5027.8
Exp/Cntr=0.3,0.1

Type RM Length L Ch R = 1,38071,657,657,657
BEGIN DESCRIPTION:
Prairie Creek38071.48
END DESCRIPTION:
XS GIS Cut Line= 3
      2702367.06      6824684.60      2701777.40      6824761.31
      2701280.63      6824781.23
#Sta/Elev= 30
  4411.1  367.19  4513.0  365.97  4523.1  366.38  4583.6  363.80  4656.9  362.63
  4714.7  362.63  4782.3  359.40  4795.4  358.25  4845.8  355.87  4884.1  355.79
  4906.3  356.94  4956.7  355.09  4963.2  353.55  4968.2  349.87  4969.4  347.02
  4969.9  346.52  4983.9  346.52  4984.4  347.02  4992.0  348.69  4997.1  350.15
  5003.9  354.06  5008.9  354.06  5017.1  356.88  5091.3  358.24  5122.5  359.50
  5157.3  359.80  5177.3  361.17  5287.4  366.13  5357.4  366.14  5502.9  367.36
#Mann=6,-1,0
  4411.1    0.05       0  4782.3    0.12       0  4969.4    0.07       0
  4984.4    0.12       0  4992.0    0.15       0  5091.3    0.05       0
Bank Sta=4969.4,4984.4
Exp/Cntr=0.3,0.1

Type RM Length L Ch R = 1,37414,341,341,341
BEGIN DESCRIPTION:
Prairie Creek37413.58
END DESCRIPTION:
XS GIS Cut Line= 3
      2701952.05      6824083.36      2701635.52      6824432.08
      2701409.22      6824727.14
#Sta/Elev= 30
  4537.4  364.29  4610.9  361.35  4681.9  359.69  4721.3  359.59  4752.2  359.14
  4783.4  357.27  4808.9  355.46  4851.5  355.25  4915.0  356.32  4986.0  354.85
  4993.4  353.65  5000.2  348.88  5004.3  346.93  5007.0  346.41  5007.5  345.91
  5021.5  345.91  5022.0  346.41  5029.0  353.11  5067.1  353.98  5099.7  355.04
  5114.2  356.45  5120.5  356.14  5178.6  358.64  5184.9  358.33  5203.6  359.52
  5243.0  361.23  5263.8  361.06  5278.3  362.54  5349.0  363.85  5380.2  365.14
#Mann=7,-1,0
  4537.4    0.05       0  4721.3    0.12       0  4783.4    0.15       0
  5007.0    0.07       0  5022.0    0.15       0  5067.1    0.12       0
  5203.6    0.05       0
Bank Sta=5007,5022
Exp/Cntr=0.3,0.1

Type RM Length L Ch R = 1,37073,346,346,346
BEGIN DESCRIPTION:
Prairie Creek37073.3
END DESCRIPTION:
XS GIS Cut Line= 3
      2701951.04      6823932.68      2701469.37      6824272.46
      2701176.58      6824450.26
#Sta/Elev= 30
  4415.1  364.04  4459.8  365.04  4525.1  363.77  4539.9  362.80  4589.7  362.55
  4676.6  356.00  4718.4  355.41  4727.1  354.42  4768.9  354.45  4776.2  355.40
  4798.5  355.67  4836.1  355.40  4947.5  355.91  4959.3  355.34  4970.9  353.52
  4976.7  346.02  4977.2  345.52  4991.7  346.02  4998.0  346.73  5003.6  348.54
  5008.0  348.54  5012.9  352.40  5020.2  354.38  5041.0  356.38  5107.8  358.76
  5158.1  359.61  5202.8  361.74  5239.6  362.50  5282.3  365.10  5347.1  366.64
#Mann=8,-1,0
  4415.1    0.05       0  4589.7    0.15       0  4836.1    0.12       0
  4959.3    0.15       0  4976.7    0.07       0  4991.7    0.15       0
  5041.0    0.07       0  5158.1    0.05       0
Bank Sta=4976.7,4991.7
Exp/Cntr=0.3,0.1

Type RM Length L Ch R = 1,36727,327,327,327
BEGIN DESCRIPTION:
Prairie Creek36726.57
END DESCRIPTION:
XS GIS Cut Line= 3
      2701803.23      6823646.16      2701369.47      6824010.44
      2701116.22      6824191.77
#Sta/Elev= 30
  4435.0  361.61  4493.5  362.33  4543.0  361.54  4563.8  360.66  4585.9  358.69
  4641.9  356.13  4680.8  355.53  4713.4  354.48  4719.9  353.67  4734.2  354.32
  4748.5  353.47  4811.5  354.40  4890.3  355.38  4943.4  354.62  4979.5  353.28
  4990.5  352.79  4992.9  345.98  4993.4  345.48  5008.0  345.98  5011.4  346.28
  5018.0  349.08  5026.2  354.16  5040.9  355.41  5076.5  356.30  5110.3  358.10
  5144.9  359.61  5177.2  360.29  5198.1  361.70  5263.2  362.88  5312.9  364.68
#Mann=9,-1,0
  4435.0    0.05       0  4680.8    0.12       0  4811.5    0.15       0
  4943.4   0.035       0  4979.5    0.05       0  4992.9    0.05       0
  5008.0    0.05       0  5110.3   0.035       0  5144.9    0.05       0
Bank Sta=4992.9,5008
Exp/Cntr=0.3,0.1

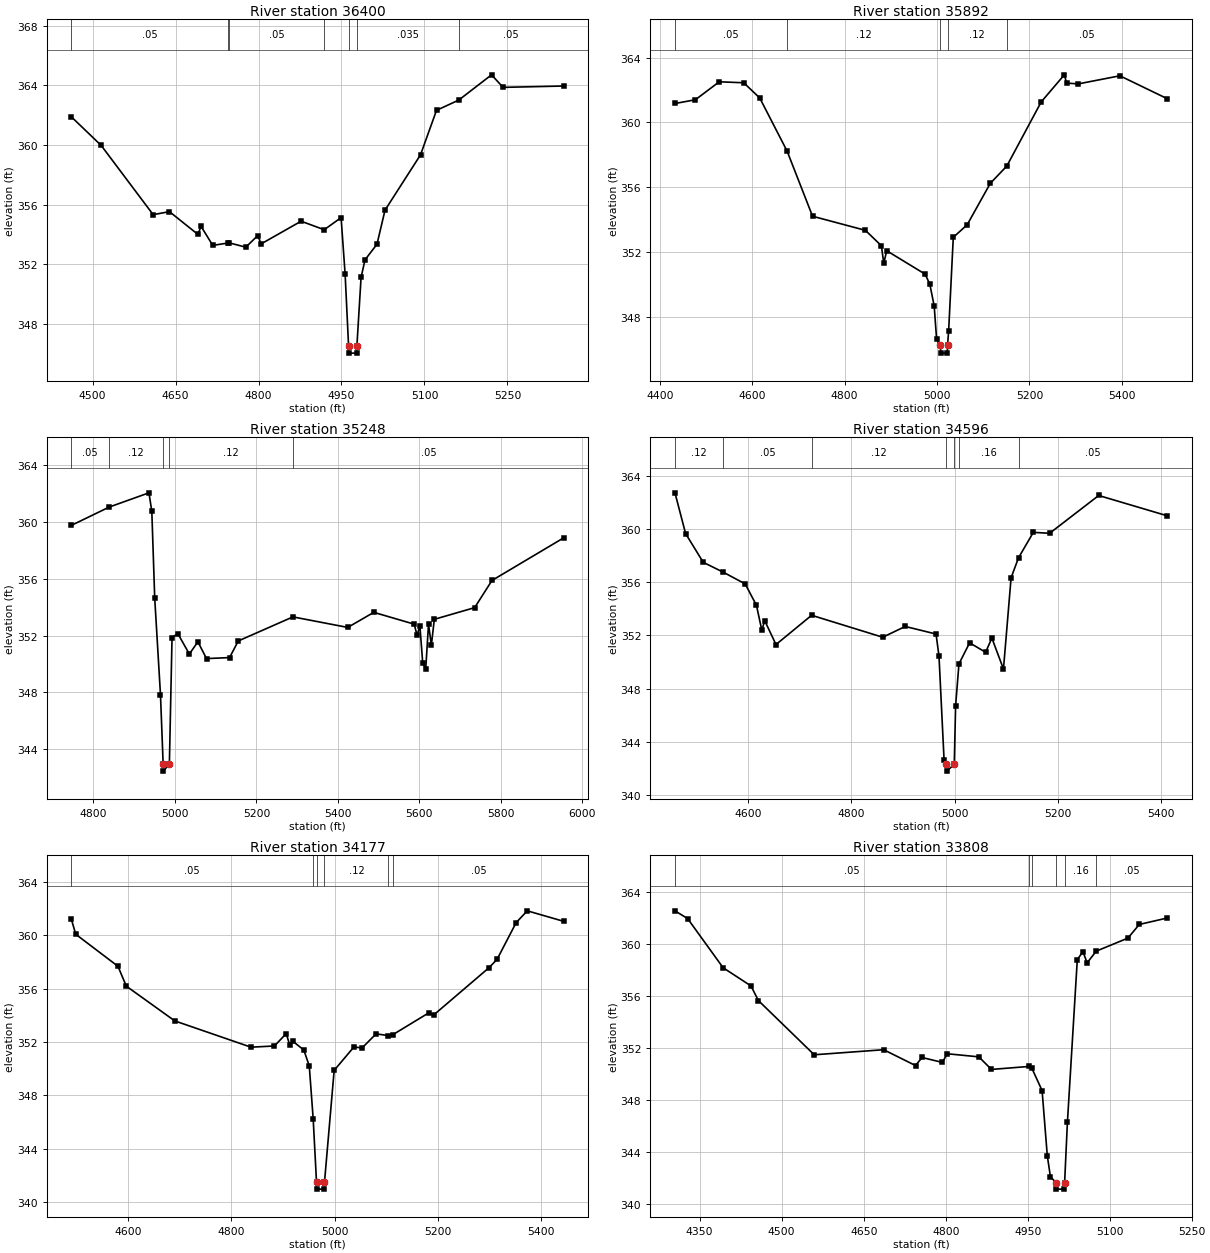
Type RM Length L Ch R = 1,36400,508,508,508
BEGIN DESCRIPTION:
Prairie Creek36400.26
END DESCRIPTION:
XS GIS Cut Line= 3
      2701659.62      6823448.64      2701205.32      6823747.49
      2700991.91      6824020.62
#Sta/Elev= 30
  4461.5  361.89  4515.5  359.97  4609.5  355.33  4639.0  355.53  4690.3  354.01
  4696.2  354.54  4717.3  353.27  4745.1  353.43  4746.9  353.44  4777.0  353.15
  4798.7  353.93  4804.7  353.37  4877.0  354.89  4918.8  354.32  4949.3  355.13
  4956.6  351.33  4962.8  346.55  4963.3  346.05  4977.4  346.05  4977.9  346.55
  4985.4  351.12  4992.5  352.30  5014.2  353.35  5028.7  355.63  5092.9  359.34
  5121.8  362.32  5162.1  363.01  5221.3  364.70  5242.1  363.86  5351.9  363.95
#Mann=7,-1,0
  4461.5    0.05       0  4745.1    0.12       0  4746.9    0.05       0
  4918.8   0.035       0  4962.8   0.035       0  4977.9   0.035       0
  5162.1    0.05       0
Bank Sta=4962.8,4977.9
Exp/Cntr=0.3,0.1

Type RM Length L Ch R = 1,35892,644,644,644
BEGIN DESCRIPTION:
Prairie Creek35891.82
END DESCRIPTION:
XS GIS Cut Line= 3
      2701778.52      6823453.92      2701224.17      6823303.72
      2700733.24      6823271.85
#Sta/Elev= 30
  4432.6  361.17  4476.7  361.40  4528.5  362.51  4581.5  362.45  4616.2  361.51
  4675.4  358.23  4730.5  354.21  4844.9  353.34  4879.5  352.39  4884.7  351.31
  4891.1  352.08  4974.0  350.64  4984.3  350.03  4993.9  348.66  4999.0  346.64
  5007.5  346.26  5008.0  345.76  5022.3  345.76  5022.8  346.26  5025.1  347.11
  5035.2  352.91  5065.2  353.68  5115.3  356.24  5151.1  357.31  5225.6  361.27
  5275.6  362.94  5280.6  362.43  5305.7  362.38  5395.9  362.88  5498.9  361.46
#Mann=5,-1,0
  4432.6    0.05       0  4675.4    0.12       0  5007.5    0.07       0
  5022.8    0.12       0  5151.1    0.05       0
Bank Sta=5007.5,5022.8
Exp/Cntr=0.3,0.1

Type RM Length L Ch R = 1,35248,652,652,652
BEGIN DESCRIPTION:
Prairie Creek35248.13
END DESCRIPTION:
XS GIS Cut Line= 3
      2701804.22      6823392.18      2701620.83      6823213.98
      2700930.61      6822557.17
#Sta/Elev= 30
  4745.8  359.74  4838.9  361.03  4936.4  362.03  4943.4  360.73  4950.5  354.64
  4964.7  347.82  4971.2  342.97  4971.7  342.47  4986.5  342.97  4993.0  351.86
  5007.3  352.13  5035.5  350.70  5056.5  351.56  5077.6  350.38  5134.2  350.45
  5155.6  351.62  5289.7  353.31  5424.2  352.57  5488.1  353.63  5587.2  352.80
  5594.1  352.04  5601.3  352.65  5608.2  350.06  5615.5  349.64  5622.4  352.80
  5629.4  351.32  5636.6  353.14  5735.6  353.96  5778.1  355.87  5954.3  358.87
#Mann=5,-1,0
  4745.8    0.05       0  4838.9    0.12       0  4971.2    0.07       0
  4986.5    0.12       0  5289.7    0.05       0
Bank Sta=4971.2,4986.5
Exp/Cntr=0.3,0.1

Type RM Length L Ch R = 1,34596,419,419,419
BEGIN DESCRIPTION:
Prairie Creek34596
END DESCRIPTION:
XS GIS Cut Line= 3
      2701814.26      6823159.07      2701556.01      6822685.70
      2701348.32      6822325.52
#Sta/Elev= 30
  4457.7  362.71  4478.3  359.65  4512.5  357.49  4551.1  356.75  4593.8  355.87
  4615.7  354.26  4626.1  352.39  4631.8  353.10  4653.6  351.31  4722.7  353.51
  4860.6  351.86  4904.2  352.67  4964.0  352.10  4969.7  350.43  4979.5  342.67
  4983.9  342.30  4984.4  341.80  4999.3  342.30  5001.9  346.71  5008.4  349.86
  5029.1  351.44  5060.1  350.73  5072.2  351.80  5094.7  349.47  5109.5  356.33
  5123.9  357.83  5152.6  359.74  5184.2  359.67  5279.4  362.51  5412.7  360.98
#Mann=7,-1,0
  4457.7    0.12       0  4551.1    0.05       0  4722.7    0.12       0
  4983.9    0.07       0  4999.3    0.12       0  5008.4    0.16       0
  5123.9    0.05       0
Bank Sta=4983.9,4999.3
Exp/Cntr=0.3,0.1

Type RM Length L Ch R = 1,34177,369,369,369
BEGIN DESCRIPTION:
Prairie Creek34177.38
END DESCRIPTION:
XS GIS Cut Line= 3
      2702043.02      6822987.61      2701799.67      6822537.95
      2701575.33      6822154.77
#Sta/Elev= 30
  4489.3  361.23  4498.0  360.09  4579.8  357.69  4596.0  356.20  4690.1  353.59
  4837.9  351.62  4883.4  351.71  4906.2  352.64  4912.8  351.81  4918.5  352.08
  4940.3  351.41  4950.9  350.22  4958.5  346.25  4965.0  341.47  4965.5  340.97
  4979.9  340.97  4980.4  341.47  4999.2  349.88  5037.6  351.64  5053.3  351.56
  5080.5  352.62  5104.2  352.49  5113.1  352.56  5182.5  354.19  5192.1  354.03
  5299.5  357.58  5315.2  358.21  5352.3  360.97  5373.8  361.85  5444.6  361.06
#Mann=6,-1,0
  4489.3    0.05       0  4958.5    0.12       0  4965.0    0.07       0
  4980.4    0.12       0  5104.2    0.16       0  5113.1    0.05       0
Bank Sta=4965,4980.4
Exp/Cntr=0.3,0.1

Type RM Length L Ch R = 1,33808,293,293,293
BEGIN DESCRIPTION:
Prairie Creek33807.542
END DESCRIPTION:
XS GIS Cut Line= 3
      2702276.01      6822811.02      2701926.00      6822211.00
      2701726.00      6822161.00
#Sta/Elev= 30
  4304.8  362.57  4328.0  361.97  4392.9  358.18  4443.8  356.78  4457.4  355.65
  4559.5  351.47  4686.5  351.86  4744.8  350.64  4756.7  351.26  4794.0  350.88
  4802.6  351.55  4860.5  351.31  4883.7  350.34  4952.6  350.57  4957.6  350.43
  4976.3  348.71  4985.8  343.69  4991.6  342.05  5002.1  341.61  5002.6  341.11
  5017.0  341.11  5017.5  341.61  5022.6  346.25  5040.7  358.81  5051.0  359.42
  5058.7  358.56  5075.3  359.46  5133.4  360.47  5154.1  361.52  5205.6  362.02
#Mann=6,-1,0
  4304.8    0.05       0  4952.6    0.12       0  4957.6    0.16       0
  5002.1    0.07       0  5017.5    0.16       0  5075.3    0.05       0
Bank Sta=5002.1,5017.5
Exp/Cntr=0.3,0.1

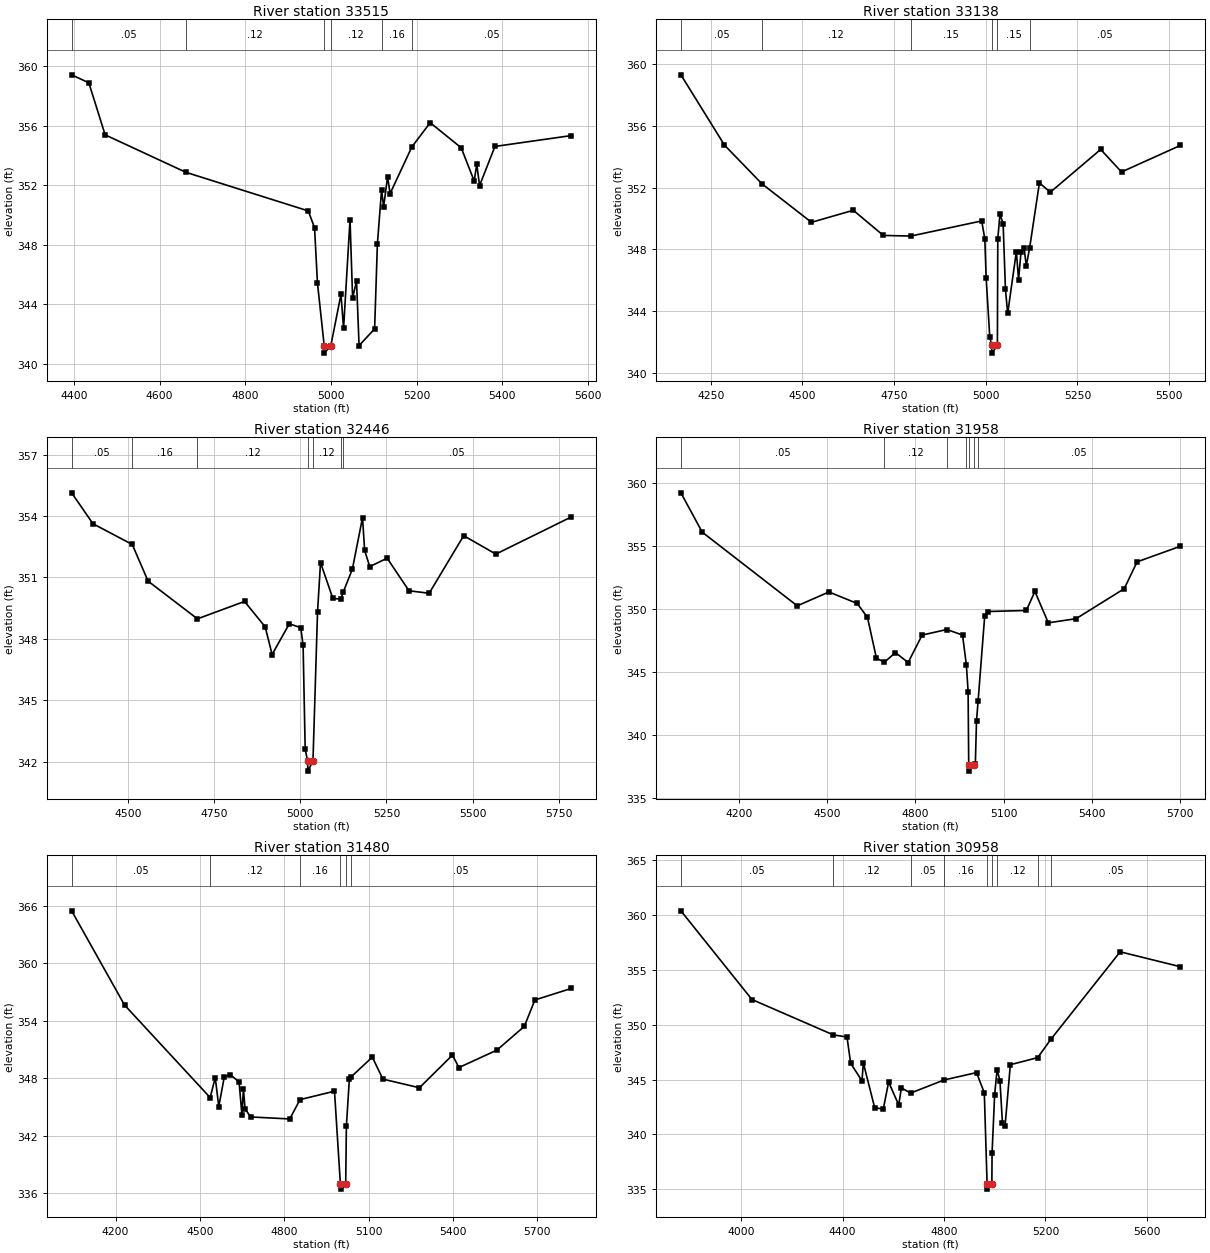
Type RM Length L Ch R = 1,33515,377,377,377
BEGIN DESCRIPTION:
Mapping XS f282cd04
END DESCRIPTION:
XS GIS Cut Line= 3
      2702368.56      6822798.68      2702158.61      6822235.42
      2701850.30      6821761.85
#Sta/Elev= 30
  4394.6  359.43  4434.8  358.89  4472.8  355.39  4661.3  352.87  4947.1  350.27
  4961.7  349.13  4968.4  345.44  4984.2  341.20  4984.7  340.70  4999.7  341.20
  5023.4  344.66  5029.4  342.36  5044.5  349.68  5050.5  344.41  5059.7  345.55
  5065.6  341.21  5101.9  342.33  5108.4  348.05  5118.1  351.67  5123.0  350.54
  5132.1  352.57  5138.1  351.44  5188.9  354.58  5231.6  356.21  5304.1  354.52
  5334.4  352.28  5340.3  353.40  5347.0  351.98  5382.8  354.61  5560.8  355.34
#Mann=6,-1,0
  4394.6    0.05       0  4661.3    0.12       0  4984.2    0.07       0
  4999.7    0.12       0  5118.1    0.16       0  5188.9    0.05       0
Bank Sta=4984.2,4999.7
Exp/Cntr=0.3,0.1

Type RM Length L Ch R = 1,33138,692,692,692
BEGIN DESCRIPTION:
Prairie Creek33138.08
END DESCRIPTION:
XS GIS Cut Line= 3
      2702475.26      6822766.18      2702270.84      6821958.86
      2701970.32      6821522.89
#Sta/Elev= 30
  4168.5  359.30  4287.3  354.75  4389.2  352.25  4524.6  349.75  4638.6  350.53
  4720.6  348.90  4795.7  348.86  4988.8  349.84  4997.3  348.68  5001.0  346.14
  5010.8  342.33  5016.1  341.78  5016.6  341.28  5031.6  341.78  5032.7  348.69
  5038.7  350.30  5047.3  349.64  5053.6  345.40  5059.7  343.85  5083.4  347.86
  5089.4  346.02  5095.9  347.80  5104.3  348.10  5110.4  346.94  5119.4  348.07
  5146.2  352.30  5176.0  351.70  5313.3  354.47  5370.1  353.01  5530.8  354.73
#Mann=6,-1,0
  4168.5    0.05       0  4389.2    0.12       0  4795.7    0.15       0
  5016.1    0.07       0  5031.6    0.15       0  5119.4    0.05       0
Bank Sta=5016.1,5031.6
Exp/Cntr=0.3,0.1

Type RM Length L Ch R = 1,32446,488,488,488
BEGIN DESCRIPTION:
Prairie Creek32446.21
END DESCRIPTION:
XS GIS Cut Line= 3
      2702617.11      6822732.98      2702618.87      6822070.64
      2702166.22      6821425.55
#Sta/Elev= 30
  4336.0  355.13  4398.0  353.62  4512.0  352.61  4558.0  350.82  4701.2  348.98
  4838.0  349.83  4898.0  348.59  4918.0  347.24  4968.0  348.74  5001.2  348.55
  5008.0  347.69  5014.1  342.61  5021.2  342.05  5021.7  341.55  5036.7  342.05
  5049.9  349.30  5058.6  351.73  5094.3  349.98  5117.4  349.94  5124.1  350.27
  5151.0  351.40  5180.6  353.92  5186.7  352.32  5201.5  351.53  5252.1  351.94
  5315.5  350.35  5374.1  350.23  5474.3  353.04  5567.6  352.14  5786.4  353.95
#Mann=7,-1,0
  4336.0    0.05       0  4512.0    0.16       0  4701.2    0.12       0
  5021.2    0.07       0  5036.7    0.12       0  5117.4    0.16       0
  5124.1    0.05       0
Bank Sta=5021.2,5036.7
Exp/Cntr=0.3,0.1

Type RM Length L Ch R = 1,31958,478,478,478
BEGIN DESCRIPTION:
Prairie Creek31957.828
END DESCRIPTION:
XS GIS Cut Line= 3
      2703693.19      6822040.20      2702767.10      6821669.85
      2702151.03      6821336.02
#Sta/Elev= 30
  4002.6  359.20  4075.0  356.08  4398.1  350.23  4505.8  351.33  4601.9  350.42
  4636.9  349.31  4667.3  346.07  4694.5  345.76  4731.9  346.52  4775.0  345.73
  4822.7  347.91  4906.5  348.35  4960.0  347.91  4973.1  345.52  4978.9  343.43
  4981.0  337.61  4981.5  337.11  4999.8  337.61  5003.5  337.70  5007.5  341.10
  5012.8  342.65  5035.4  349.44  5045.6  349.78  5176.8  349.86  5206.0  351.37
  5251.5  348.88  5346.0  349.21  5509.6  351.59  5553.3  353.72  5700.7  354.96
#Mann=7,-1,0
  4002.6    0.05       0  4694.5    0.12       0  4906.5    0.16       0
  4973.1    0.12       0  4981.0    0.07       0  4999.8    0.12       0
  5012.8    0.05       0
Bank Sta=4981,4999.8
Exp/Cntr=0.3,0.1

Type RM Length L Ch R = 1,31480,522,522,522
BEGIN DESCRIPTION:
Prairie Creek31479.84
END DESCRIPTION:
XS GIS Cut Line= 3
      2703827.69      6821568.77      2702913.34      6821246.72
      2702142.89      6821005.94
#Sta/Elev= 30
  4043.6  365.48  4231.7  355.64  4536.3  345.97  4554.3  348.06  4566.9  345.04
  4586.1  348.08  4607.3  348.38  4639.1  347.60  4649.2  344.16  4654.5  346.89
  4660.3  344.80  4680.1  343.95  4819.3  343.74  4855.9  345.76  4978.4  346.64
  4999.5  336.91  5000.0  336.41  5018.3  336.91  5020.7  342.98  5031.2  347.87
  5036.7  348.11  5112.9  350.20  5150.6  347.90  5280.5  347.00  5397.9  350.41
  5420.9  349.11  5556.0  350.93  5653.5  353.41  5691.2  356.17  5820.2  357.37
#Mann=6,-1,0
  4043.6    0.05       0  4536.3    0.12       0  4855.9    0.16       0
  4999.5    0.07       0  5018.3    0.16       0  5036.7    0.05       0
Bank Sta=4999.5,5018.3
Exp/Cntr=0.3,0.1

Type RM Length L Ch R = 1,30958,525,525,525
BEGIN DESCRIPTION:
Prairie Creek30957.65
END DESCRIPTION:
XS GIS Cut Line= 3
      2704187.29      6821072.98      2702962.77      6820816.63
      2702265.61      6820639.80
#Sta/Elev= 30
  3762.0  360.39  4042.2  352.30  4363.3  349.07  4417.2  348.88  4431.5  346.48
  4476.3  344.88  4481.5  346.52  4526.3  342.43  4560.2  342.30  4581.3  344.77
  4621.1  342.68  4631.7  344.24  4667.7  343.76  4800.3  344.96  4928.0  345.63
  4958.7  343.79  4969.7  335.50  4970.2  335.00  4988.5  335.50  4989.3  338.26
  4999.5  343.63  5009.2  345.91  5020.4  344.88  5030.4  340.99  5040.7  340.79
  5061.4  346.35  5169.4  347.00  5221.2  348.67  5494.6  356.65  5732.3  355.29
#Mann=9,-1,0
  3762.0    0.05       0  4363.3    0.12       0  4667.7    0.05       0
  4800.3    0.16       0  4969.7    0.07       0  4988.5    0.16       0
  5009.2    0.12       0  5169.4    0.16       0  5221.2    0.05       0
Bank Sta=4969.7,4988.5
Exp/Cntr=0.3,0.1