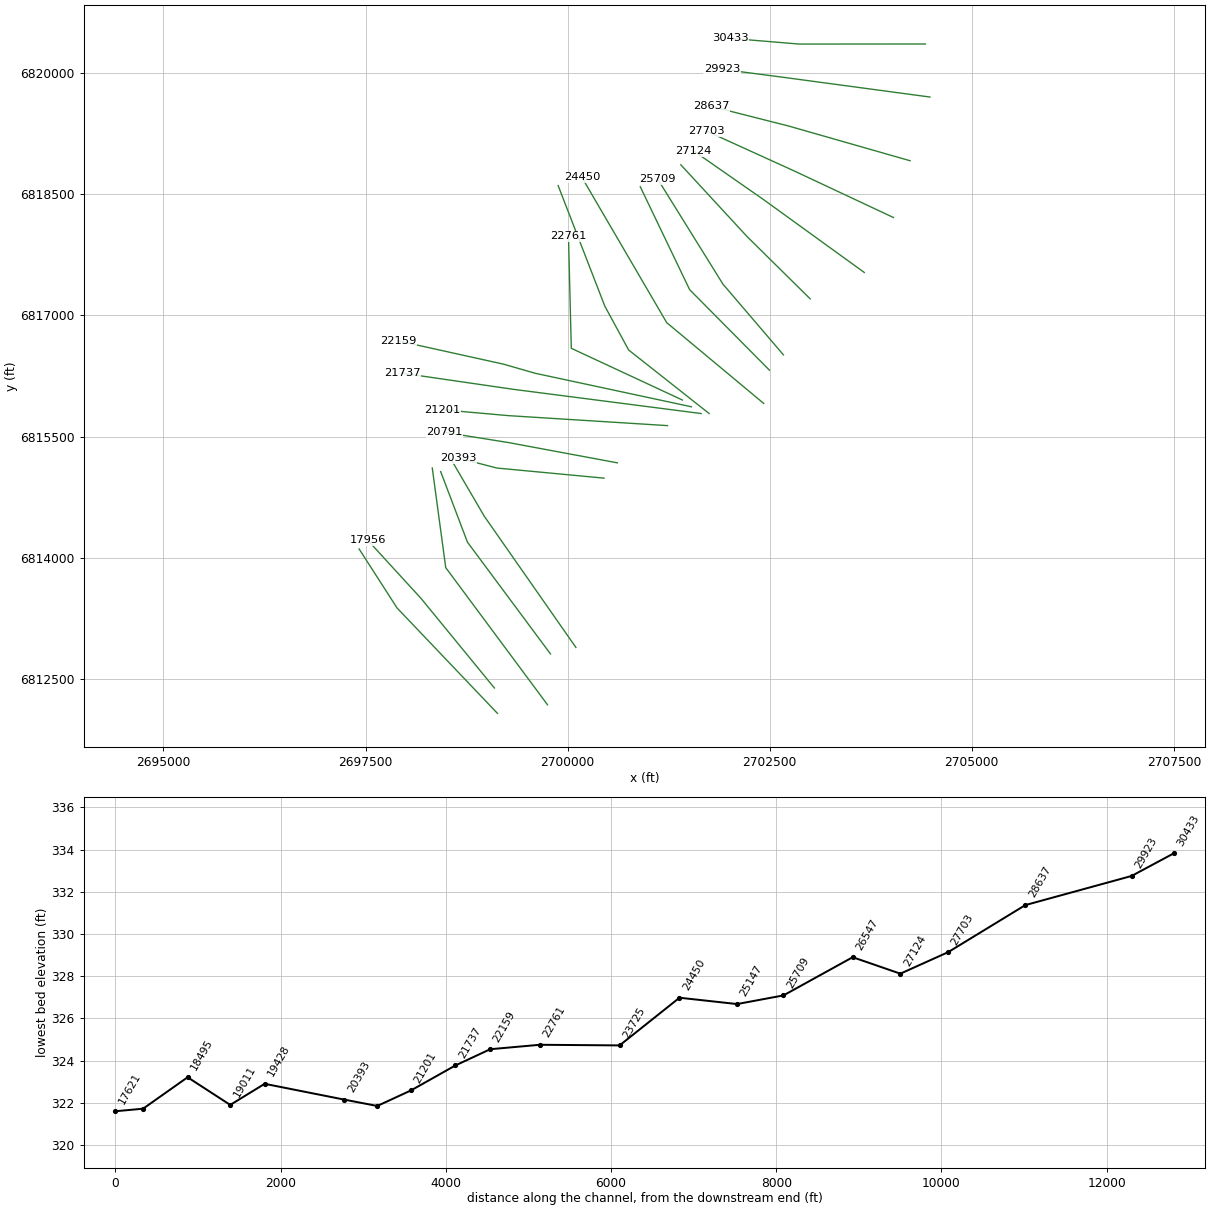
HEC-RAS study Prairie Creek.prj: Prairie Creek Base Level Engineering

--- Prairie Creek.g01 (geometry) --- (continued)

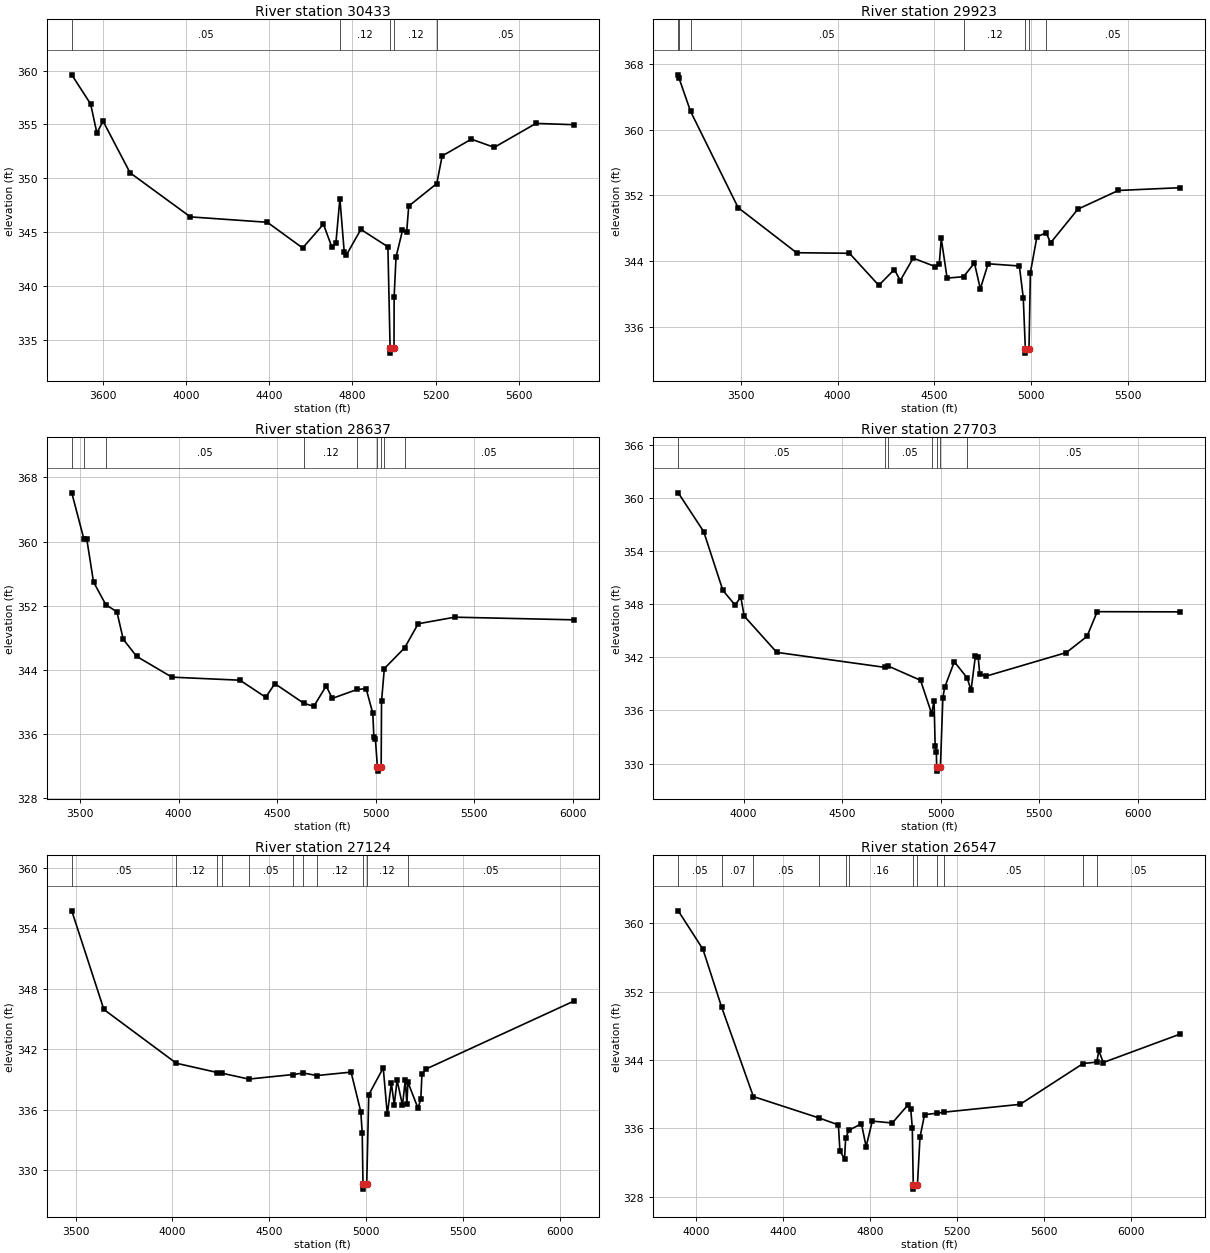
Type RM Length L Ch R = 1,30433,510,510,510
BEGIN DESCRIPTION:
Prairie Creek30433.31
END DESCRIPTION:
XS GIS Cut Line= 3
      2704426.75      6820360.60      2702862.78      6820359.78
      2702014.50      6820430.64
#Sta/Elev= 30
  3450.0  359.60  3540.7  356.90  3570.7  354.22  3600.7  355.30  3730.7  350.52
  4020.7  346.44  4390.7  345.94  4560.7  343.56  4660.7  345.77  4700.7  343.66
  4720.7  344.05  4739.8  348.14  4760.7  343.16  4770.7  342.90  4840.7  345.28
  4970.7  343.67  4981.3  334.32  4981.8  333.82  5000.1  334.32  5000.7  339.04
  5009.9  342.72  5040.8  345.18  5060.9  345.01  5070.9  347.44  5206.0  349.53
  5231.5  352.08  5372.0  353.64  5482.4  352.88  5683.1  355.10  5865.2  354.98
#Mann=5,-1,0
  3450.0    0.05       0  4739.8    0.12       0  4981.3    0.07       0
  5000.1    0.12       0  5206.0    0.05       0
Bank Sta=4981.3,5000.1
Exp/Cntr=0.3,0.1

Type RM Length L Ch R = 1,29923,1286,1286,1286
BEGIN DESCRIPTION:
Prairie Creek29922.82
END DESCRIPTION:
XS GIS Cut Line= 3
      2704482.79      6819703.81      2702678.09      6819946.91
      2701911.44      6820047.33
#Sta/Elev= 30
  3177.0  366.73  3181.5  366.30  3240.6  362.27  3486.6  350.51  3788.4  345.01
  4061.7  344.94  4213.1  341.03  4293.8  342.96  4324.1  341.61  4390.8  344.35
  4505.7  343.31  4525.9  343.69  4536.0  346.75  4566.2  341.91  4651.0  342.08
  4707.5  343.75  4737.8  340.60  4778.1  343.66  4939.6  343.39  4959.7  339.52
  4970.5  333.25  4971.0  332.75  4989.4  333.25  4996.5  342.58  5030.4  346.95
  5078.0  347.44  5101.0  346.22  5242.2  350.33  5450.9  352.61  5771.2  352.95
#Mann=7,-1,0
  3177.0    0.05       0  3181.5    0.16       0  3240.6    0.05       0
  4651.0    0.12       0  4970.5    0.07       0  4989.4    0.12       0
  5078.0    0.05       0
Bank Sta=4970.5,4989.4
Exp/Cntr=0.3,0.1

Type RM Length L Ch R = 1,28637,934,934,934
BEGIN DESCRIPTION:
Prairie Creek28637.03
END DESCRIPTION:
XS GIS Cut Line= 3
      2704236.13      6818915.46      2702732.87      6819345.50
      2701780.82      6819587.17
#Sta/Elev= 30
  3458.3  366.08  3519.8  360.31  3534.7  360.26  3568.5  354.97  3630.6  352.14
  3687.3  351.23  3719.2  347.82  3786.8  345.69  3966.1  343.09  4311.3  342.71
  4441.6  340.58  4488.1  342.28  4635.4  339.82  4685.8  339.46  4748.2  341.99
  4779.4  340.44  4905.5  341.56  4951.0  341.65  4984.8  338.56  4990.0  335.67
  4997.8  335.36  5008.1  331.87  5008.6  331.37  5027.1  331.87  5029.0  340.06
  5043.1  344.16  5145.9  346.74  5214.7  349.75  5400.4  350.57  6004.1  350.24
#Mann=9,-1,0
  3458.3    0.05       0  3519.8   0.035       0  3630.6    0.05       0
  4635.4    0.12       0  4905.5    0.16       0  5008.1    0.07       0
  5027.1    0.16       0  5043.1    0.07       0  5145.9    0.05       0
Bank Sta=5008.1,5027.1
Exp/Cntr=0.3,0.1

Type RM Length L Ch R = 1,27703,579,579,579
BEGIN DESCRIPTION:
Prairie Creek27703.31
END DESCRIPTION:
XS GIS Cut Line= 3
      2704030.86      6818212.46      2702806.51      6818787.38
      2701720.18      6819281.90
#Sta/Elev= 30
  3668.9  360.61  3798.1  356.22  3895.2  349.58  3957.8  347.91  3986.1  348.84
  4003.4  346.67  4168.6  342.57  4715.2  340.88  4731.0  341.05  4897.8  339.41
  4954.2  335.63  4966.3  337.12  4971.8  332.01  4977.9  331.35  4979.4  329.64
  4979.9  329.14  4998.5  329.64  5011.0  337.45  5019.9  338.60  5069.0  341.51
  5134.3  339.68  5153.9  338.28  5175.9  342.17  5189.8  342.09  5197.9  340.12
  5230.4  339.88  5637.4  342.55  5742.0  344.38  5793.6  347.17  6215.1  347.15
#Mann=7,-1,0
  3668.9    0.05       0  4715.2    0.07       0  4731.0    0.05       0
  4954.2    0.12       0  4979.4    0.07       0  4998.5    0.12       0
  5134.3    0.05       0
Bank Sta=4979.4,4998.5
Exp/Cntr=0.3,0.1

Type RM Length L Ch R = 1,27124,577,577,577
BEGIN DESCRIPTION:
Prairie Creek27123.55
END DESCRIPTION:
XS GIS Cut Line= 3
      2703669.89      6817532.39      2702426.46      6818432.43
      2701560.81      6819035.85
#Sta/Elev= 30
  3480.4  355.71  3646.0  345.93  4019.8  340.60  4231.3  339.68  4255.7  339.61
  4393.5  339.03  4621.9  339.48  4675.6  339.63  4745.0  339.38  4921.3  339.72
  4971.5  335.79  4978.9  333.66  4982.8  328.62  4983.3  328.12  5002.0  328.62
  5012.6  337.48  5087.3  340.14  5108.2  335.53  5129.2  338.63  5144.0  336.47
  5158.8  338.92  5186.6  336.43  5200.7  338.91  5209.4  336.54  5214.4  338.73
  5266.2  336.16  5281.0  337.02  5287.1  339.55  5308.5  340.03  6070.6  346.76
#Mann=11,-1,0
  3480.4    0.05       0  4019.8    0.12       0  4231.3    0.05       0
  4255.7    0.16       0  4393.5    0.05       0  4621.9    0.12       0
  4675.6    0.05       0  4745.0    0.12       0  4982.8    0.07       0
  5002.0    0.12       0  5214.4    0.05       0
Bank Sta=4982.8,5002
Exp/Cntr=0.3,0.1

Type RM Length L Ch R = 1,26547,838,838,838
BEGIN DESCRIPTION:
Prairie Creek26546.54
END DESCRIPTION:
XS GIS Cut Line= 3
      2703001.06      6817205.53      2702219.19      6817977.49
      2701400.39      6818865.32
#Sta/Elev= 30
  3918.2  361.43  4031.7  356.94  4117.5  350.18  4263.3  339.72  4563.6  337.23
  4654.0  336.41  4661.0  333.33  4682.3  332.45  4687.3  334.89  4702.6  335.79
  4760.0  336.54  4781.3  333.86  4809.6  336.85  4901.5  336.63  4972.2  338.70
  4986.3  338.24  4993.4  336.10  4997.9  329.40  4998.4  328.90  5017.1  329.40
  5028.8  334.97  5049.7  337.60  5108.9  337.78  5140.7  337.90  5488.7  338.81
  5778.0  343.58  5841.5  343.75  5849.9  345.11  5870.9  343.70  6224.7  347.03
#Mann=12,-1,0
  3918.2    0.05       0  4117.5    0.07       0  4263.3    0.05       0
  4563.6    0.16       0  4687.3    0.12       0  4702.6    0.16       0
  4997.9    0.07       0  5017.1    0.16       0  5108.9    0.12       0
  5140.7    0.05       0  5778.0    0.07       0  5841.5    0.05       0
Bank Sta=4997.9,5017.1
Exp/Cntr=0.3,0.1

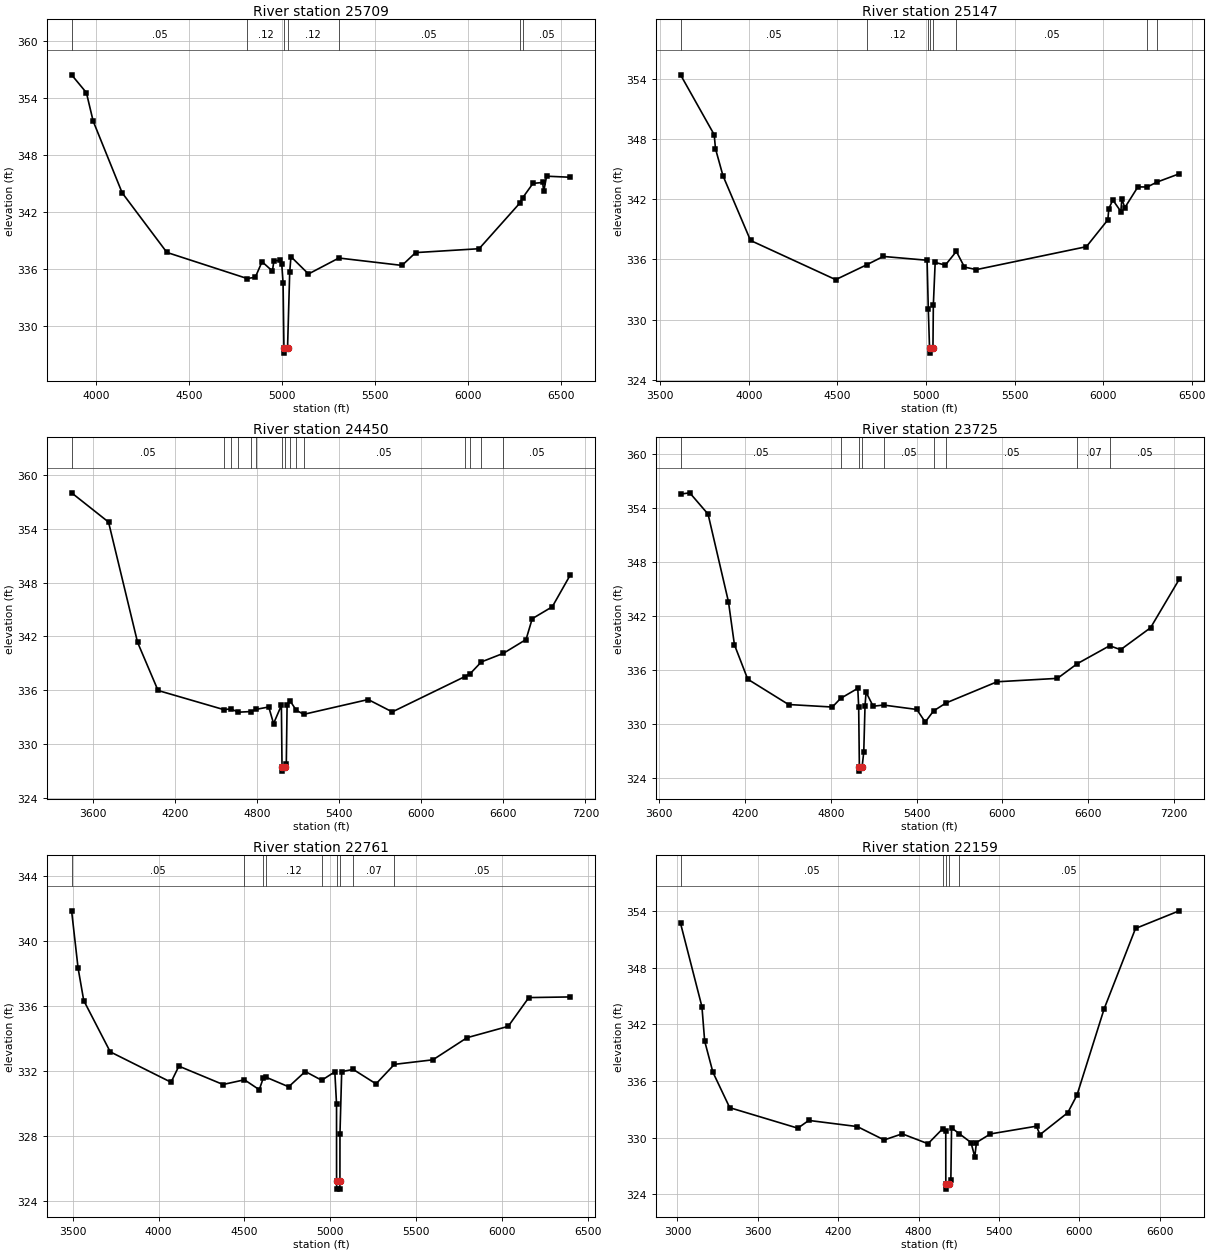
Type RM Length L Ch R = 1,25709,562,562,562
BEGIN DESCRIPTION:
Prairie Creek25708.86
END DESCRIPTION:
XS GIS Cut Line= 3
      2702669.83      6816512.24      2701920.85      6817388.87
      2701115.60      6818686.38
#Sta/Elev= 30
  3870.2  356.41  3949.7  354.53  3986.0  351.54  4141.9  343.98  4382.3  337.70
  4813.9  334.95  4857.6  335.08  4893.9  336.72  4949.8  335.73  4957.5  336.82
  4992.7  336.86  4999.7  336.52  5006.9  334.47  5011.6  327.59  5012.1  327.09
  5030.9  327.59  5042.6  335.63  5049.3  337.25  5143.4  335.43  5306.9  337.11
  5646.2  336.33  5719.4  337.68  6060.7  338.09  6278.2  342.87  6294.9  343.46
  6350.1  344.97  6402.1  345.07  6408.0  344.12  6423.3  345.73  6550.3  345.62
#Mann=7,-1,0
  3870.2    0.05       0  4813.9    0.12       0  5011.6    0.07       0
  5030.9    0.12       0  5306.9    0.05       0  6278.2    0.07       0
  6294.9    0.05       0
Bank Sta=5011.6,5030.9
Exp/Cntr=0.3,0.1

Type RM Length L Ch R = 1,25147,697,697,697
BEGIN DESCRIPTION:
Prairie Creek25147.24
END DESCRIPTION:
XS GIS Cut Line= 3
      2702496.74      6816322.95      2701509.86      6817318.88
      2700898.95      6818593.46
#Sta/Elev= 30
  3614.2  354.37  3804.3  348.41  3811.3  347.03  3853.7  344.33  4009.3  337.89
  4490.2  333.99  4664.3  335.46  4758.9  336.30  5006.3  335.92  5013.1  331.08
  5020.1  327.18  5020.6  326.68  5039.4  327.18  5041.6  331.46  5051.9  335.70
  5109.5  335.44  5171.5  336.80  5217.3  335.24  5284.8  334.99  5905.8  337.27
  6026.9  339.94  6032.5  341.05  6055.1  341.92  6100.4  340.77  6106.0  342.00
  6123.1  341.16  6196.6  343.22  6248.7  343.21  6306.3  343.71  6429.7  344.52
#Mann=8,-1,0
  3614.2    0.05       0  4664.3    0.12       0  5013.1    0.07       0
  5020.1    0.07       0  5039.4    0.07       0  5171.5    0.05       0
  6248.7    0.07       0  6306.3    0.05       0
Bank Sta=5020.1,5039.4
Exp/Cntr=0.3,0.1

Type RM Length L Ch R = 1,24450,725,725,725
BEGIN DESCRIPTION:
Prairie Creek24450.337
END DESCRIPTION:
XS GIS Cut Line= 3
      2702425.99      6815911.01      2701226.00      6816911.00
      2700176.00      6818711.00
#Sta/Elev= 30
  3442.5  358.00  3712.6  354.74  3924.8  341.34  4074.5  335.97  4556.9  333.83
  4605.6  333.92  4661.8  333.55  4754.2  333.62  4793.3  333.87  4884.1  334.13
  4919.3  332.28  4976.5  334.31  4981.2  327.48  4981.7  326.98  5000.5  327.48
  5012.4  327.77  5018.2  334.40  5040.0  334.81  5085.1  333.77  5140.0  333.31
  5611.1  334.96  5787.2  333.58  6317.2  337.51  6356.8  337.84  6438.5  339.15
  6599.6  340.11  6765.5  341.65  6810.6  343.97  6957.3  345.30  7088.4  348.83
#Mann=15,-1,0
  3442.5    0.05       0  4556.9    0.16       0  4605.6    0.05       0
  4661.8    0.12       0  4754.2    0.16       0  4793.3    0.12       0
  4981.2    0.07       0  5000.5    0.12       0  5040.0    0.05       0
  5085.1    0.07       0  5140.0    0.05       0  6317.2    0.07       0
  6356.8    0.05       0  6438.5    0.07       0  6599.6    0.05       0
Bank Sta=4981.2,5000.5
Exp/Cntr=0.3,0.1

Type RM Length L Ch R = 1,23725,964,964,964
BEGIN DESCRIPTION:
Prairie Creek23724.576
END DESCRIPTION:
XS GIS Cut Line= 4
      2701751.04      6815785.97      2700755.35      6816572.28
      2700460.49      6817114.94      2699883.08      6818607.52
#Sta/Elev= 30
  3749.3  355.54  3813.5  355.68  3941.7  353.31  4084.4  343.55  4126.0  338.78
  4219.0  334.95  4504.4  332.13  4810.6  331.85  4868.4  332.81  4988.6  333.93
  4994.9  331.88  4999.7  325.22  5000.2  324.72  5019.1  325.22  5030.4  326.85
  5039.3  332.00  5046.6  333.50  5096.2  331.94  5169.1  332.07  5401.0  331.58
  5460.4  330.18  5518.5  331.42  5606.6  332.31  5962.6  334.66  6384.9  335.04
  6523.3  336.67  6749.9  338.67  6826.5  338.23  7036.0  340.67  7236.0  346.05
#Mann=9,-1,0
  3749.3    0.05       0  4868.4    0.12       0  4999.7    0.07       0
  5019.1    0.12       0  5169.1    0.05       0  5518.5    0.07       0
  5606.6    0.05       0  6523.3    0.07       0  6749.9    0.05       0
Bank Sta=4999.7,5019.1
Exp/Cntr=0.3,0.1

Type RM Length L Ch R = 1,22761,602,602,602
BEGIN DESCRIPTION:
Mapping XS 11994f92
END DESCRIPTION:
XS GIS Cut Line= 3
      2701420.06      6815953.21      2700045.76      6816593.23
      2700010.76      6817982.17
#Sta/Elev= 30
  3492.9  341.88  3530.5  338.37  3563.6  336.36  3718.1  333.20  4072.3  331.33
  4118.0  332.32  4375.1  331.19  4500.1  331.48  4586.5  330.87  4610.5  331.61
  4628.0  331.63  4757.7  331.05  4854.7  331.99  4950.3  331.45  5026.7  331.97
  5036.7  329.99  5036.9  325.25  5037.4  324.75  5055.9  324.75  5056.4  325.25
  5056.7  328.17  5066.7  331.98  5133.6  332.12  5266.8  331.23  5373.9  332.43
  5598.4  332.71  5796.9  334.07  6037.0  334.77  6157.1  336.54  6398.3  336.58
#Mann=9,-1,0
  3492.9    0.05       0  4500.1    0.12       0  4610.5    0.16       0
  4628.0    0.12       0  4950.3    0.05       0  5036.9    0.05       0
  5056.4    0.05       0  5133.6    0.07       0  5373.9    0.05       0
Bank Sta=5036.9,5056.4
Exp/Cntr=0.3,0.1

Type RM Length L Ch R = 1,22159,422,422,422
BEGIN DESCRIPTION:
Prairie Creek22713.471
END DESCRIPTION:
XS GIS Cut Line= 4
      2701532.03      6815869.41      2699599.33      6816284.19
      2699208.56      6816396.86      2697901.04      6816685.99
#Sta/Elev= 30
  3023.3  352.70  3182.9  343.87  3203.3  340.23  3264.7  336.93  3390.4  333.17
  3898.8  331.00  3980.6  331.82  4342.6  331.17  4543.2  329.75  4678.1  330.40
  4870.6  329.35  4980.3  330.94  5003.3  330.67  5003.6  325.04  5004.1  324.54
  5024.1  325.04  5041.3  325.55  5046.5  331.03  5104.6  330.41  5191.5  329.48
  5220.0  327.97  5232.4  329.48  5336.6  330.39  5680.7  331.21  5706.3  330.31
  5914.2  332.64  5982.8  334.50  6186.3  343.67  6419.9  352.16  6745.8  354.03
#Mann=5,-1,0
  3023.3    0.05       0  4980.3    0.07       0  5003.6    0.07       0
  5024.1    0.07       0  5104.6    0.05       0
Bank Sta=5003.6,5024.1
Exp/Cntr=0.3,0.1

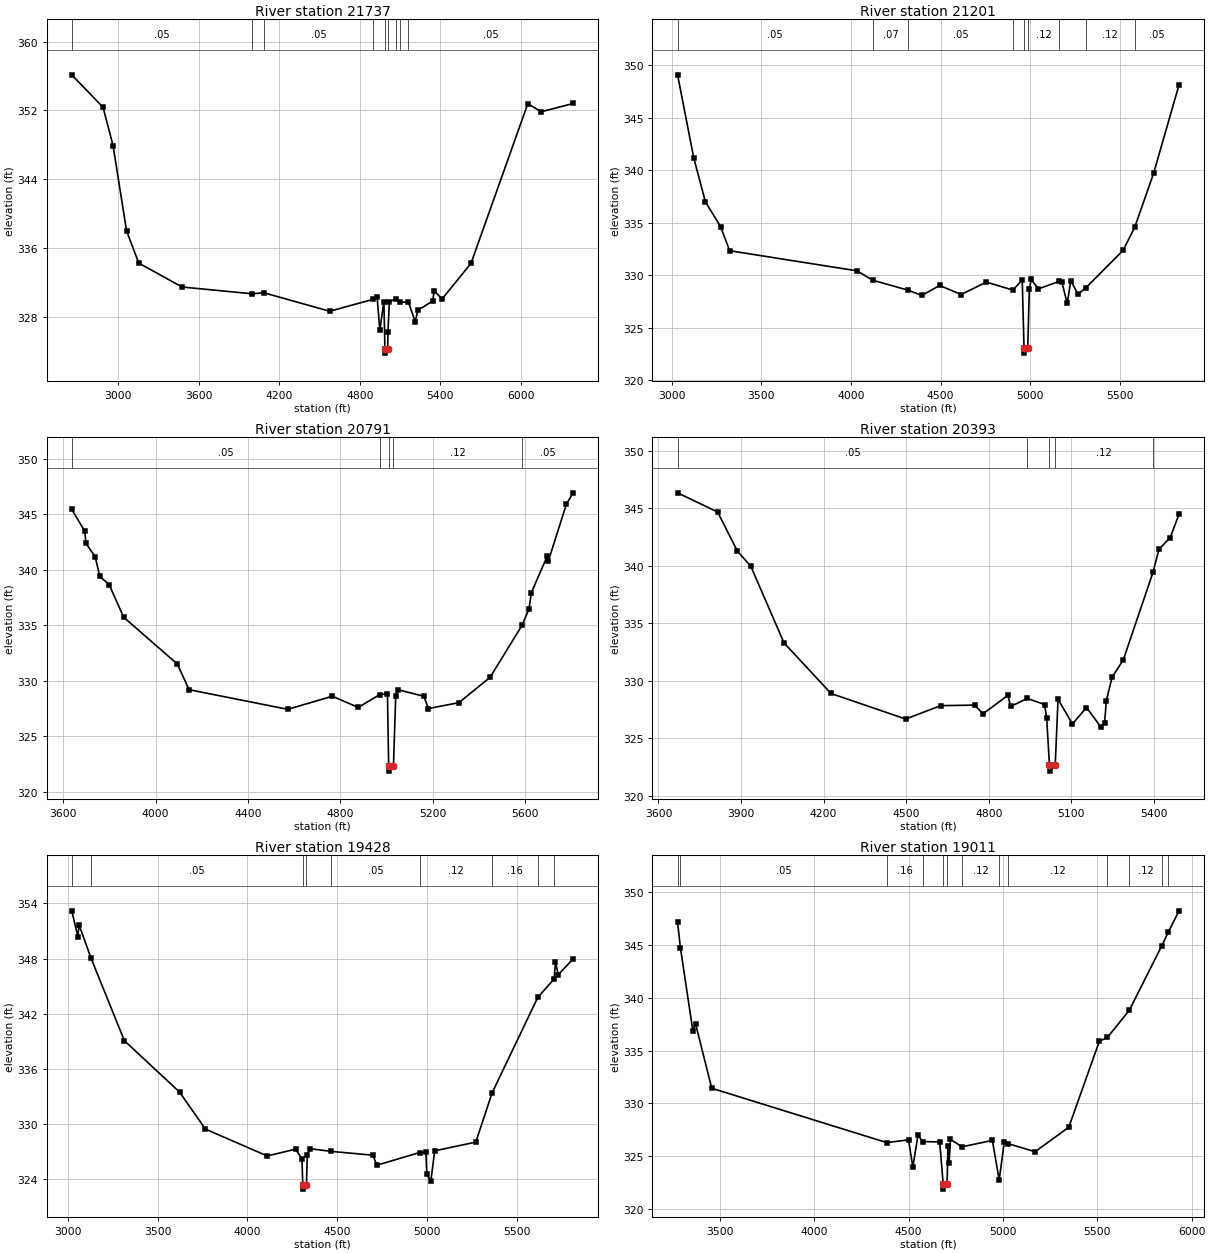
Type RM Length L Ch R = 1,21737,536,536,536
BEGIN DESCRIPTION:
Prairie Creek21737.001
END DESCRIPTION:
XS GIS Cut Line= 3
      2701651.03      6815786.00      2699325.60      6816086.00
      2697950.97      6816286.00
#Sta/Elev= 30
  2655.3  356.14  2888.5  352.36  2962.9  347.91  3063.7  337.97  3154.4  334.24
  3477.1  331.46  3999.8  330.67  4085.2  330.79  4576.1  328.64  4899.1  330.03
  4929.0  330.27  4949.2  326.44  4979.4  329.76  4987.0  324.27  4987.5  323.77
  5007.5  324.27  5009.7  326.22  5019.8  329.73  5066.9  330.08  5099.6  329.70
  5162.0  329.71  5212.6  327.41  5232.0  328.76  5342.7  329.83  5353.3  331.02
  5412.8  330.07  5628.1  334.22  6050.5  352.77  6151.6  351.85  6389.1  352.81
#Mann=9,-1,0
  2655.3    0.05       0  3999.8    0.07       0  4085.2    0.05       0
  4899.1    0.16       0  4987.0    0.07       0  5007.5    0.16       0
  5066.9    0.12       0  5099.6    0.16       0  5162.0    0.05       0
Bank Sta=4987,5007.5
Exp/Cntr=0.3,0.1

Type RM Length L Ch R = 1,21201,410,410,410
BEGIN DESCRIPTION:
Prairie Creek20964.235
END DESCRIPTION:
XS GIS Cut Line= 3
      2701235.93      6815636.25      2699272.10      6815759.56
      2698444.16      6815833.06
#Sta/Elev= 30
  3032.3  349.08  3122.4  341.18  3187.7  336.99  3272.7  334.62  3322.8  332.34
  4034.2  330.42  4121.3  329.53  4319.4  328.58  4394.9  328.08  4495.1  329.03
  4615.3  328.17  4755.6  329.35  4903.8  328.59  4956.0  329.56  4965.7  323.09
  4966.2  322.59  4986.5  323.09  4995.5  328.67  5006.1  329.60  5046.3  328.70
  5162.9  329.43  5176.8  329.38  5206.9  327.32  5227.0  329.49  5267.1  328.20
  5311.7  328.82  5518.1  332.36  5583.9  334.58  5688.8  339.69  5831.2  348.14
#Mann=9,-1,0
  3032.3    0.05       0  4121.3    0.07       0  4319.4    0.05       0
  4903.8    0.12       0  4965.7    0.07       0  4986.5    0.12       0
  5162.9    0.16       0  5311.7    0.12       0  5583.9    0.05       0
Bank Sta=4965.7,4986.5
Exp/Cntr=0.3,0.1

Type RM Length L Ch R = 1,20791,398,398,398
BEGIN DESCRIPTION:
Mapping XS ae3aae4a
END DESCRIPTION:
XS GIS Cut Line= 3
      2700615.63      6815175.45      2699273.62      6815425.73
      2698476.91      6815553.25
#Sta/Elev= 30
  3637.1  345.44  3693.7  343.46  3698.7  342.37  3738.4  341.18  3758.8  339.39
  3799.1  338.66  3861.9  335.72  4094.5  331.50  4145.3  329.19  4572.6  327.42
  4765.9  328.60  4877.8  327.59  4970.1  328.74  5004.4  328.83  5009.7  322.35
  5010.2  321.85  5030.5  322.35  5040.3  328.63  5050.5  329.18  5161.9  328.60
  5182.1  327.49  5313.8  328.02  5448.7  330.30  5587.5  334.99  5617.6  336.48
  5627.7  337.93  5696.7  341.24  5701.8  340.82  5779.6  345.92  5809.1  346.93
#Mann=5,-1,0
  3637.1    0.05       0  4970.1    0.12       0  5009.7    0.07       0
  5030.5    0.12       0  5587.5    0.05       0
Bank Sta=5009.7,5030.5
Exp/Cntr=0.3,0.1

Type RM Length L Ch R = 1,20393,965,965,965
BEGIN DESCRIPTION:
Prairie Creek20392.818
END DESCRIPTION:
XS GIS Cut Line= 3
      2700451.02      6814986.00      2699126.00      6815111.00
      2698650.21      6815234.25
#Sta/Elev= 30
  3669.4  346.34  3815.1  344.67  3886.4  341.29  3935.6  339.95  4056.1  333.30
  4226.9  328.90  4498.1  326.68  4625.7  327.84  4749.2  327.89  4779.3  327.13
  4869.7  328.74  4879.8  327.77  4940.3  328.47  5002.9  327.94  5010.6  326.80
  5020.9  322.65  5021.4  322.15  5041.7  322.65  5052.0  328.39  5104.4  326.25
  5155.3  327.68  5206.9  326.01  5221.0  326.33  5227.6  328.28  5248.2  330.29
  5289.5  331.85  5396.9  339.42  5418.9  341.44  5459.5  342.45  5491.8  344.49
#Mann=5,-1,0
  3669.4    0.05       0  4940.3    0.12       0  5020.9    0.07       0
  5041.7    0.12       0  5396.9    0.05       0
Bank Sta=5020.9,5041.7
Exp/Cntr=0.3,0.1

Type RM Length L Ch R = 1,19428,417,417,417
BEGIN DESCRIPTION:
Prairie Creek19427.921
END DESCRIPTION:
XS GIS Cut Line= 3
      2700102.63      6812890.40      2698969.92      6814513.55
      2698558.93      6815217.67
#Sta/Elev= 30
  3020.7  353.20  3055.2  350.39  3061.3  351.68  3128.3  348.04  3314.1  339.06
  3621.4  333.47  3765.3  329.44  4109.9  326.51  4267.8  327.25  4303.5  326.21
  4308.0  323.40  4308.5  322.90  4328.8  323.40  4333.2  326.62  4348.0  327.30
  4467.3  327.01  4699.6  326.59  4720.5  325.50  4958.6  326.88  4994.5  326.92
  4999.1  324.52  5021.9  323.81  5043.4  327.07  5272.4  328.02  5363.2  333.38
  5617.9  343.78  5708.7  345.78  5716.4  347.60  5732.1  346.25  5815.3  347.98
#Mann=9,-1,0
  3020.7    0.16       0  3128.3    0.05       0  4308.0    0.07       0
  4328.8    0.05       0  4467.3    0.05       0  4958.6    0.12       0
  5363.2    0.16       0  5617.9    0.12       0  5708.7    0.05       0
Bank Sta=4308,4328.8
Exp/Cntr=0.3,0.1

Type RM Length L Ch R = 1,19011,516,516,516
BEGIN DESCRIPTION:
Prairie Creek19010.53
END DESCRIPTION:
XS GIS Cut Line= 3
      2699788.36      6812809.69      2698761.11      6814193.58
      2698429.61      6815067.65
#Sta/Elev= 30
  3275.1  347.12  3290.6  344.68  3356.1  336.87  3370.7  337.51  3456.3  331.44
  4384.1  326.30  4499.4  326.56  4522.1  323.99  4549.5  327.00  4574.9  326.39
  4664.3  326.37  4683.1  322.40  4683.6  321.90  4703.9  322.40  4708.1  326.02
  4714.3  324.33  4721.4  326.62  4782.3  325.90  4943.9  326.51  4979.8  322.76
  5006.5  326.31  5025.2  326.21  5170.2  325.44  5348.8  327.75  5510.5  335.87
  5553.8  336.25  5669.5  338.81  5842.0  344.92  5877.1  346.24  5933.4  348.22
#Mann=13,-1,0
  3275.1    0.16       0  3290.6    0.05       0  4384.1    0.16       0
  4574.9    0.12       0  4683.1    0.07       0  4703.9    0.12       0
  4782.3    0.12       0  4979.8    0.16       0  5025.2    0.12       0
  5553.8    0.16       0  5669.5    0.12       0  5842.0    0.16       0
  5877.1    0.12       0
Bank Sta=4683.1,4703.9
Exp/Cntr=0.3,0.1

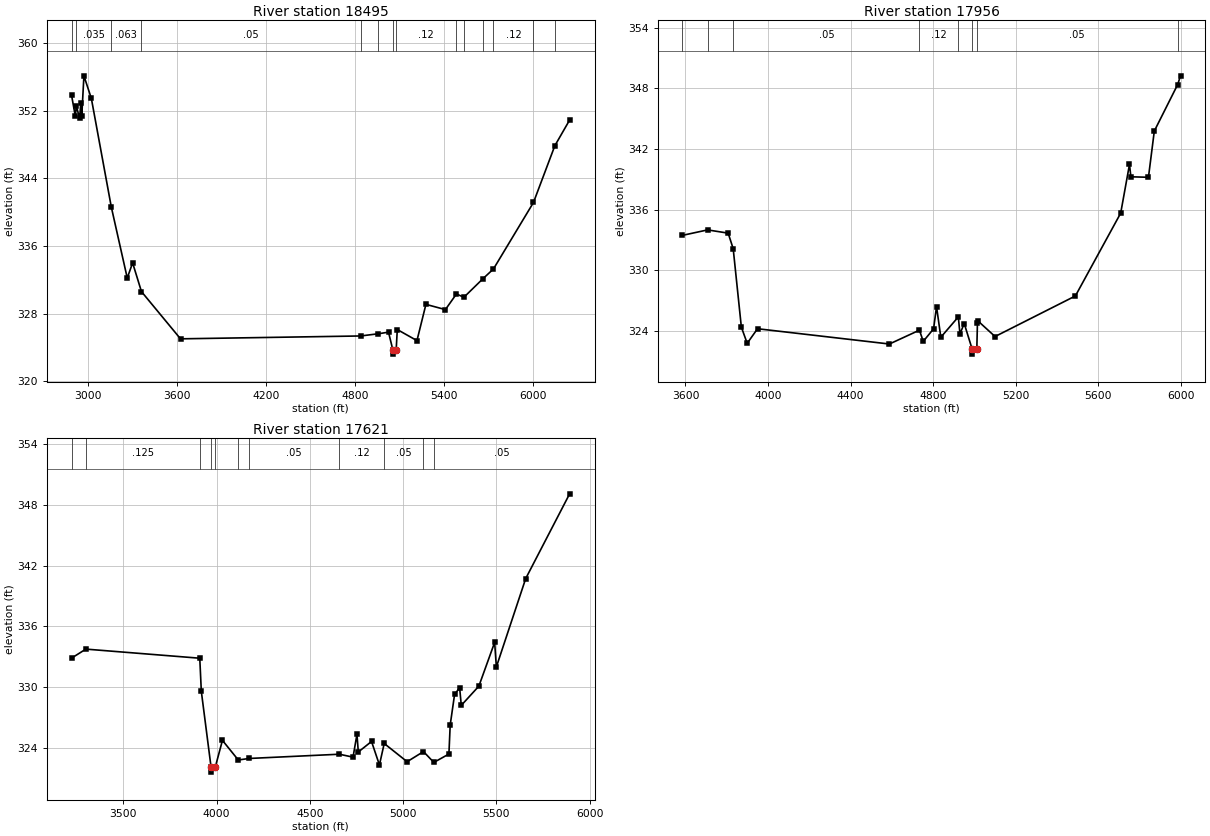
Type RM Length L Ch R = 1,18495,539,539,539
BEGIN DESCRIPTION:
Prairie Creek18494.812
END DESCRIPTION:
XS GIS Cut Line= 3
      2699751.65      6812180.43      2698492.51      6813878.04
      2698325.99      6815111.05
#Sta/Elev= 30
  2886.4  353.84  2912.0  351.34  2918.0  352.62  2940.5  351.11  2948.9  352.98
  2955.1  351.41  2969.7  356.15  3019.8  353.47  3154.2  340.63  3261.8  332.22
  3298.0  334.01  3357.6  330.61  3620.8  325.02  4835.3  325.36  4954.6  325.62
  5023.2  325.81  5052.3  323.71  5052.8  323.21  5074.8  323.71  5082.3  326.12
  5214.9  324.81  5275.4  329.10  5406.6  328.48  5481.1  330.33  5531.4  329.94
  5661.2  332.16  5730.7  333.29  6000.4  341.16  6144.6  347.88  6244.2  350.92
#Mann=14,-1,0
  2886.4   0.125       0  2918.0   0.035       0  3154.2   0.063       0
  3357.6    0.05       0  4835.3    0.16       0  4954.6    0.12       0
  5052.3    0.07       0  5074.8    0.12       0  5481.1    0.16       0
  5531.4    0.12       0  5661.2    0.16       0  5730.7    0.12       0
  6000.4    0.16       0  6144.6    0.12       0
Bank Sta=5052.3,5074.8
Exp/Cntr=0.3,0.1

Type RM Length L Ch R = 1,17956,335,335,335
BEGIN DESCRIPTION:
Prairie Creek17955.72
END DESCRIPTION:
XS GIS Cut Line= 3
      2699094.24      6812388.31      2698187.14      6813496.98
      2697525.55      6814219.86
#Sta/Elev= 30
  3585.3  333.46  3707.0  334.00  3806.7  333.68  3831.1  332.14  3870.6  324.39
  3898.9  322.79  3948.9  324.23  4587.7  322.72  4733.2  324.09  4751.6  322.98
  4801.6  324.22  4816.0  326.41  4836.8  323.39  4921.5  325.40  4929.4  323.73
  4950.2  324.74  4988.4  322.22  4988.9  321.72  5011.1  322.22  5014.1  324.82
  5017.1  324.99  5099.4  323.46  5488.5  327.47  5708.0  335.66  5750.6  340.48
  5757.3  339.25  5842.4  339.20  5870.8  343.77  5984.0  348.37  5997.7  349.23
#Mann=8,-1,0
  3585.3   0.125       0  3707.0   0.094       0  3831.1    0.05       0
  4733.2    0.12       0  4921.5    0.05       0  4988.4    0.05       0
  5011.1    0.05       0  5984.0    0.16       0
Bank Sta=4988.4,5011.1
Exp/Cntr=0.3,0.1

Type RM Length L Ch R = 1,17621,730,730,730
BEGIN DESCRIPTION:
Prairie Creek17621.023
END DESCRIPTION:
XS GIS Cut Line= 3
      2699132.31      6812073.99      2697889.85      6813379.46
      2697420.80      6814109.80
#Sta/Elev= 30
  3222.7  332.87  3299.4  333.76  3910.0  332.86  3918.3  329.59  3970.5  322.10
  3971.0  321.60  3993.2  322.10  4031.5  324.74  4116.4  322.80  4174.4  322.95
  4658.4  323.37  4731.7  323.08  4752.7  325.34  4760.0  323.59  4830.8  324.63
  4873.2  322.31  4898.8  324.43  5021.7  322.63  5109.4  323.63  5164.9  322.56
  5245.7  323.39  5252.6  326.26  5276.1  329.28  5303.2  329.94  5312.0  328.20
  5406.3  330.10  5490.8  334.42  5500.1  332.00  5657.3  340.73  5892.9  349.11
#Mann=11,-1,0
  3222.7   0.094       0  3299.4   0.125       0  3910.0    0.05       0
  3970.5    0.05       0  3993.2    0.05       0  4116.4    0.16       0
  4174.4    0.05       0  4658.4    0.12       0  4898.8    0.05       0
  5109.4    0.12       0  5164.9    0.05       0
Bank Sta=3970.5,3993.2
Exp/Cntr=0.3,0.1