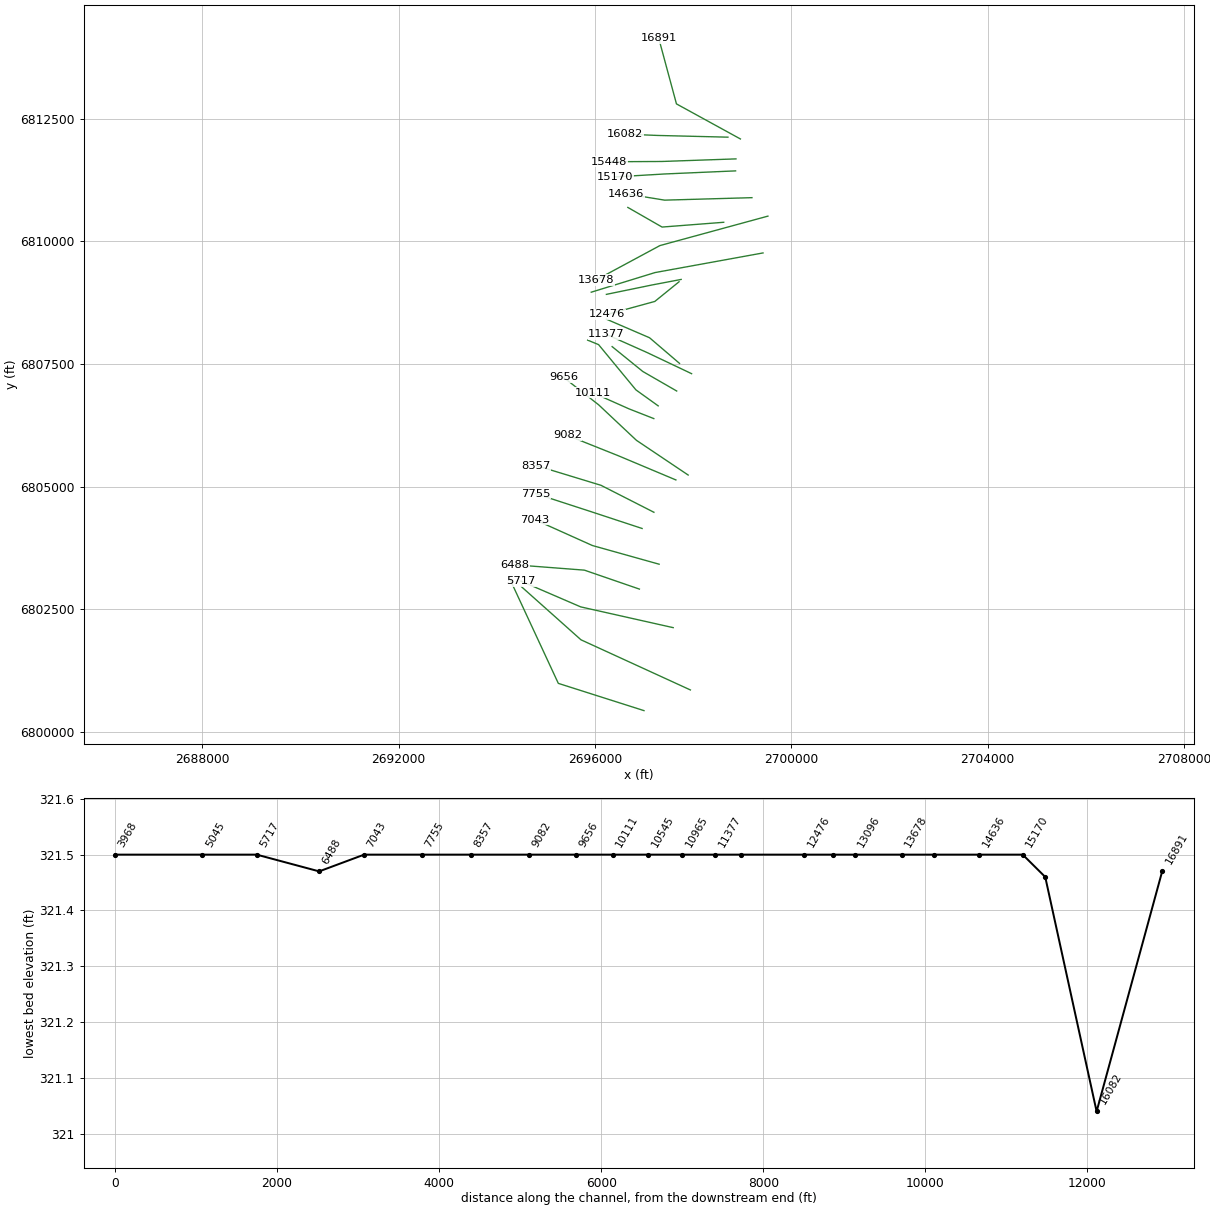
HEC-RAS study Prairie Creek.prj: Prairie Creek Base Level Engineering

--- Prairie Creek.g01 (geometry) --- (continued)

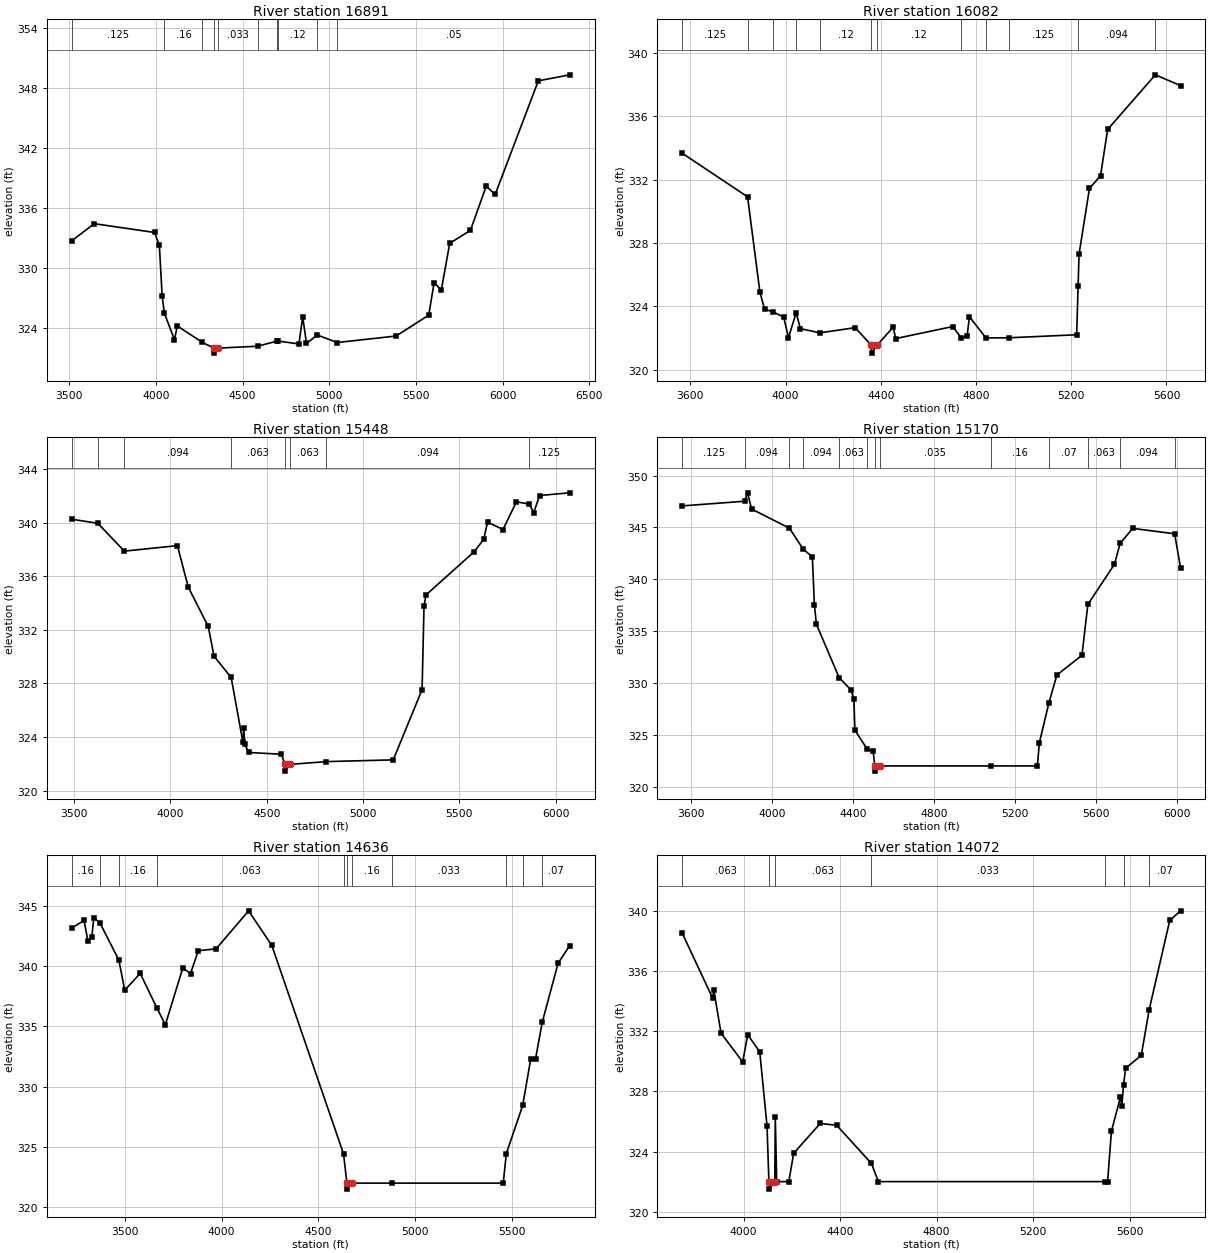
Type RM Length L Ch R = 1,16891,809,809,809
BEGIN DESCRIPTION:
Prairie Creek16891.252
END DESCRIPTION:
XS GIS Cut Line= 3
      2698965.61      6812083.05      2697662.44      6812797.76
      2697301.00      6814136.01
#Sta/Elev= 30
  3513.7  332.69  3644.5  334.41  3992.3  333.53  4019.9  332.23  4036.0  327.17
  4048.9  325.46  4107.1  322.80  4123.2  324.19  4268.1  322.54  4334.5  321.97
  4335.0  321.47  4357.2  321.97  4587.3  322.16  4697.5  322.67  4701.2  322.68
  4824.6  322.39  4846.4  325.10  4868.2  322.44  4930.5  323.28  5045.3  322.53
  5385.2  323.18  5573.1  325.27  5604.1  328.51  5645.6  327.77  5694.0  332.44
  5813.7  333.75  5904.5  338.16  5956.3  337.33  6204.9  348.69  6386.2  349.29
#Mann=10,-1,0
  3513.7   0.125       0  4048.9    0.16       0  4268.1   0.033       0
  4334.5   0.035       0  4357.2   0.033       0  4587.3    0.16       0
  4697.5    0.05       0  4701.2    0.12       0  4930.5   0.035       0
  5045.3    0.05       0
Bank Sta=4334.5,4357.2
Exp/Cntr=0.3,0.1

Type RM Length L Ch R = 1,16082,634,634,634
BEGIN DESCRIPTION:
Prairie Creek16082.46
END DESCRIPTION:
XS GIS Cut Line= 3
      2698711.56      6812119.73      2697272.84      6812154.92
      2696620.25      6812181.77
#Sta/Elev= 30
  3566.7  333.67  3840.7  330.92  3892.4  324.91  3912.4  323.81  3945.9  323.66
  3992.4  323.32  4012.4  322.02  4045.0  323.59  4062.4  322.59  4144.1  322.32
  4292.5  322.65  4360.7  321.54  4361.2  321.04  4384.3  321.54  4452.5  322.68
  4462.5  321.96  4702.6  322.72  4738.4  322.00  4762.6  322.11  4772.6  323.34
  4841.9  322.00  4937.7  322.01  5222.9  322.20  5228.9  325.26  5232.9  327.30
  5276.6  331.45  5323.0  332.25  5353.0  335.18  5553.4  338.63  5659.0  337.95
#Mann=12,-1,0
  3566.7   0.125       0  3840.7   0.094       0  3945.9    0.12       0
  4045.0    0.16       0  4144.1    0.12       0  4360.7    0.07       0
  4384.3    0.12       0  4738.4   0.063       0  4841.9   0.094       0
  4937.7   0.125       0  5228.9   0.094       0  5553.4    0.05       0
Bank Sta=4360.7,4384.3
Exp/Cntr=0.3,0.1

Type RM Length L Ch R = 1,15448,278,278,278
BEGIN DESCRIPTION:
Prairie Creek15448.071
END DESCRIPTION:
XS GIS Cut Line= 3
      2698875.37      6811677.17      2697362.79      6811624.38
      2696289.20      6811619.02
#Sta/Elev= 30
  3486.5  340.25  3622.7  339.95  3760.6  337.87  4036.2  338.28  4092.4  335.19
  4196.3  332.25  4226.3  330.03  4315.3  328.45  4375.8  323.65  4380.8  324.69
  4386.4  323.45  4406.4  322.85  4576.5  322.72  4594.6  321.96  4595.1  321.46
  4618.5  321.96  4810.1  322.17  5156.8  322.30  5306.8  327.54  5316.8  333.78
  5326.8  334.60  5576.8  337.82  5626.8  338.75  5646.8  340.04  5726.8  339.48
  5796.8  341.55  5863.0  341.38  5886.8  340.75  5916.8  342.02  6073.6  342.22
#Mann=8,-1,0
  3486.5   0.094       0  3622.7   0.125       0  3760.6   0.094       0
  4315.3   0.063       0  4594.6    0.07       0  4618.5   0.063       0
  4810.1   0.094       0  5863.0   0.125       0
Bank Sta=4594.6,4618.5
Exp/Cntr=0.3,0.1

Type RM Length L Ch R = 1,15170,534,534,534
BEGIN DESCRIPTION:
Prairie Creek15169.718
END DESCRIPTION:
XS GIS Cut Line= 3
      2698867.64      6811432.82      2697426.00      6811370.09
      2696410.07      6811310.08
#Sta/Elev= 30
  3557.0  347.08  3865.0  347.53  3878.9  348.34  3899.0  346.78  4086.1  344.93
  4154.5  342.89  4199.2  342.17  4209.3  337.55  4219.3  335.66  4331.6  330.51
  4389.4  329.35  4404.2  328.50  4409.4  325.45  4471.3  323.59  4499.5  323.41
  4507.4  322.00  4507.9  321.50  4531.6  322.00  5081.5  322.00  5310.5  322.00
  5320.6  324.25  5367.2  328.05  5407.1  330.77  5530.9  332.67  5560.1  337.58
  5691.2  341.44  5719.5  343.46  5781.4  344.91  5988.8  344.39  6017.7  341.12
#Mann=13,-1,0
  3557.0   0.125       0  3865.0   0.094       0  4086.1   0.063       0
  4154.5   0.094       0  4331.6   0.063       0  4471.3   0.035       0
  4507.4   0.035       0  4531.6   0.035       0  5081.5    0.16       0
  5367.2    0.07       0  5560.1   0.063       0  5719.5   0.094       0
  5988.8   0.063       0
Bank Sta=4507.4,4531.6
Exp/Cntr=0.3,0.1

Type RM Length L Ch R = 1,14636,564,564,564
BEGIN DESCRIPTION:
Prairie Creek14636.39
END DESCRIPTION:
XS GIS Cut Line= 3
      2699200.59      6810887.14      2697421.73      6810836.62
      2696636.65      6810964.45
#Sta/Elev= 30
  3224.7  343.14  3289.3  343.78  3309.3  342.05  3329.3  342.38  3339.3  343.99
  3370.3  343.61  3469.2  340.49  3499.4  338.00  3579.4  339.39  3667.1  336.48
  3709.5  335.13  3799.5  339.84  3839.5  339.38  3879.6  341.27  3971.9  341.43
  4139.7  344.58  4259.7  341.71  4630.5  324.42  4647.8  322.00  4648.3  321.50
  4672.0  322.00  4883.0  322.00  5455.9  322.00  5471.8  324.45  5556.5  328.44
  5597.7  332.26  5622.9  332.30  5657.2  335.32  5739.6  340.24  5799.7  341.70
#Mann=11,-1,0
  3224.7    0.16       0  3370.3   0.035       0  3469.2    0.16       0
  3667.1   0.063       0  4630.5    0.16       0  4647.8   0.033       0
  4672.0    0.16       0  4883.0   0.033       0  5471.8    0.07       0
  5556.5   0.063       0  5657.2    0.07       0
Bank Sta=4647.8,4672
Exp/Cntr=0.3,0.1

Type RM Length L Ch R = 1,14072,394,394,394
BEGIN DESCRIPTION:
Prairie Creek14072.21
END DESCRIPTION:
XS GIS Cut Line= 3
      2698625.78      6810385.73      2697369.36      6810288.21
      2696672.25      6810688.17
#Sta/Elev= 30
  3746.4  338.50  3871.8  334.20  3876.9  334.73  3906.7  331.87  3996.6  329.95
  4017.0  331.77  4067.1  330.63  4097.2  325.71  4105.1  322.00  4105.6  321.50
  4129.5  322.00  4131.5  326.30  4137.3  322.00  4187.5  322.00  4207.6  323.88
  4317.9  325.87  4386.1  325.74  4529.8  323.21  4558.6  322.00  5495.5  322.00
  5508.2  322.00  5524.1  325.35  5561.4  327.61  5567.2  327.04  5574.2  328.41
  5583.0  329.54  5647.8  330.39  5680.4  333.42  5765.7  339.36  5810.3  340.00
#Mann=7,-1,0
  3746.4   0.063       0  4105.1   0.033       0  4129.5   0.063       0
  4529.8   0.033       0  5495.5    0.07       0  5574.2   0.063       0
  5680.4    0.07       0
Bank Sta=4105.1,4129.5
Exp/Cntr=0.3,0.1

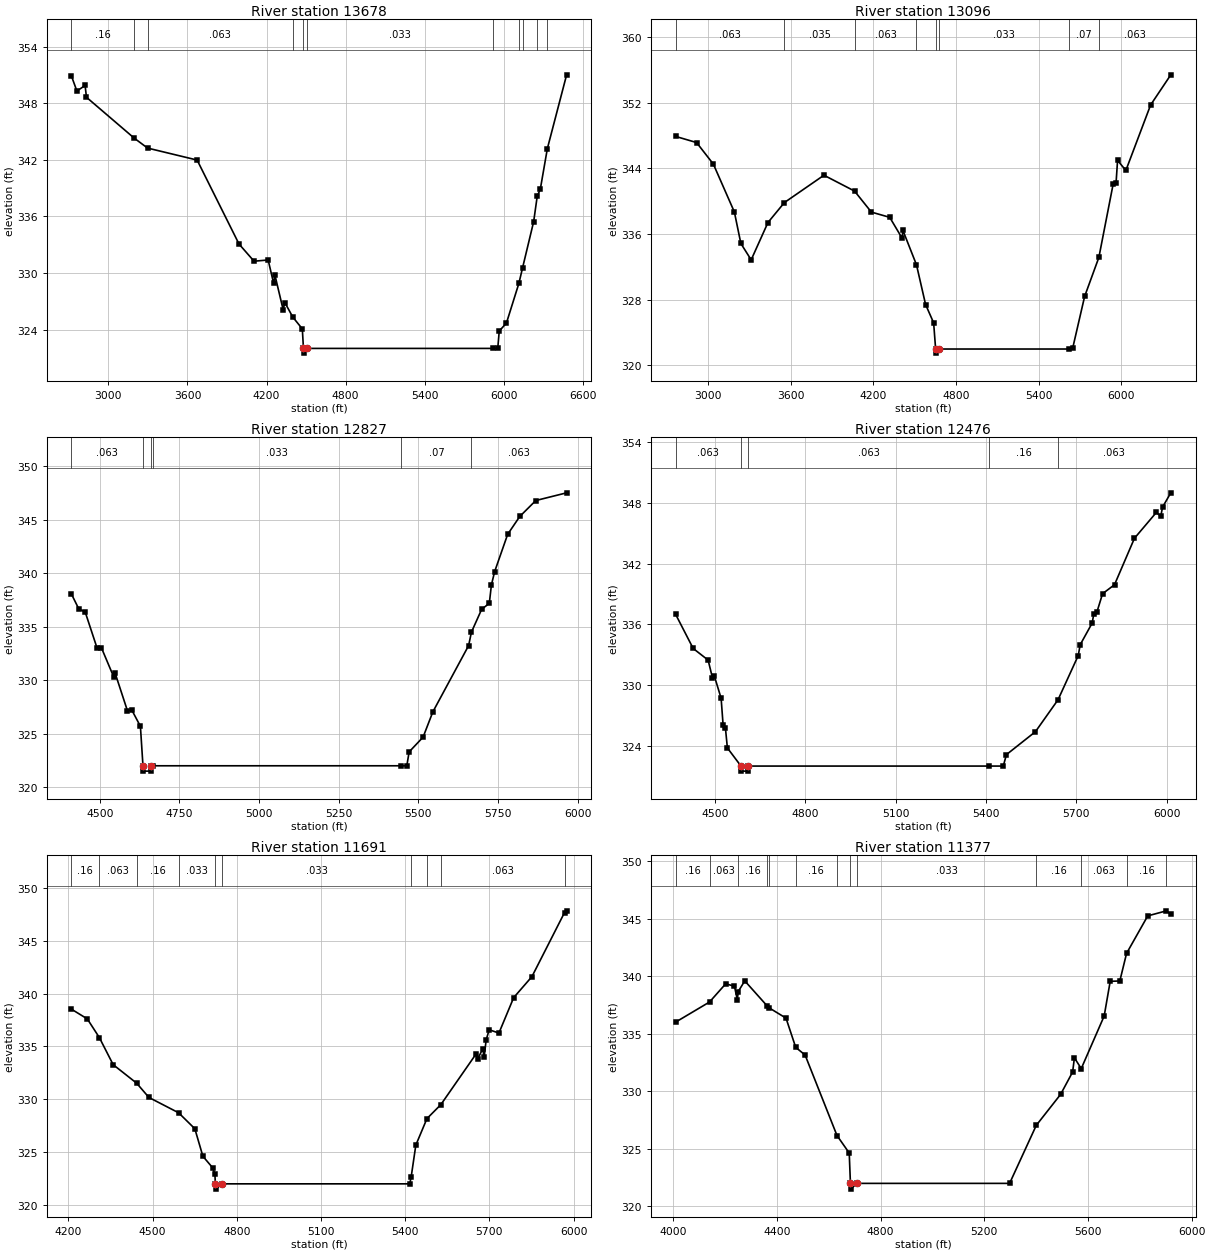
Type RM Length L Ch R = 1,13678,582,582,582
BEGIN DESCRIPTION:
Prairie Creek13678.369
END DESCRIPTION:
XS GIS Cut Line= 3
      2699526.04      6810511.01      2697326.00      6809911.00
      2696025.97      6809210.99
#Sta/Elev= 30
  2719.7  350.90  2761.2  349.30  2823.4  349.89  2833.8  348.64  3195.5  344.31
  3297.4  343.25  3673.3  341.98  3991.2  333.07  4105.2  331.25  4212.3  331.38
  4253.8  328.89  4264.2  329.74  4326.3  326.09  4338.4  326.87  4399.4  325.32
  4471.5  324.07  4480.0  322.00  4480.5  321.50  4504.4  322.00  5920.5  322.00
  5954.1  322.00  5965.5  323.85  6019.8  324.68  6114.2  328.89  6142.5  330.55
  6226.7  335.46  6253.5  338.13  6277.0  338.89  6330.4  343.19  6476.6  351.02
#Mann=11,-1,0
  2719.7    0.16       0  3195.5    0.12       0  3297.4   0.063       0
  4399.4   0.033       0  4480.0   0.033       0  4504.4   0.033       0
  5920.5    0.16       0  6114.2    0.07       0  6142.5   0.063       0
  6253.5    0.16       0  6330.4   0.063       0
Bank Sta=4480,4504.4
Exp/Cntr=0.3,0.1

Type RM Length L Ch R = 1,13096,269,269,269
BEGIN DESCRIPTION:
Prairie Creek13096.053
END DESCRIPTION:
XS GIS Cut Line= 3
      2699425.99      6809761.00      2697226.00      6809361.00
      2695926.00      6808961.00
#Sta/Elev= 30
  2763.9  347.90  2916.3  347.15  3038.3  344.52  3190.8  338.69  3237.8  334.86
  3312.7  332.86  3434.7  337.41  3554.0  339.84  3841.3  343.17  4063.5  341.24
  4185.6  338.68  4319.0  338.04  4409.2  335.49  4414.3  336.47  4513.2  332.26
  4579.4  327.42  4637.9  325.19  4652.3  322.00  4652.8  321.50  4676.7  322.00
  5619.5  322.00  5648.6  322.17  5734.3  328.40  5837.8  333.16  5941.6  342.10
  5962.5  342.19  5973.6  344.98  6033.8  343.75  6213.6  351.73  6360.1  355.40
#Mann=8,-1,0
  2763.9   0.063       0  3554.0   0.035       0  4063.5   0.063       0
  4513.2   0.033       0  4652.3   0.033       0  4676.7   0.033       0
  5619.5    0.07       0  5837.8   0.063       0
Bank Sta=4652.3,4676.7
Exp/Cntr=0.3,0.1

Type RM Length L Ch R = 1,12827,351,351,351
BEGIN DESCRIPTION:
Prairie Creek12826.77
END DESCRIPTION:
XS GIS Cut Line= 3
      2697758.68      6809221.19      2697170.07      6809109.25
      2696234.82      6808916.83
#Sta/Elev= 30
  4411.3  338.06  4434.2  336.68  4454.7  336.36  4491.5  333.03  4505.6  333.02
  4543.7  330.33  4548.8  330.63  4587.1  327.14  4601.0  327.20  4627.8  325.69
  4635.8  322.00  4636.3  321.50  4660.0  321.50  4660.5  322.00  4666.6  322.00
  5446.5  322.00  5463.8  322.00  5471.1  323.30  5514.9  324.68  5545.5  327.04
  5657.8  333.24  5666.5  334.49  5698.7  336.63  5722.7  337.19  5729.3  338.91
  5739.5  340.16  5780.3  343.64  5818.3  345.31  5868.6  346.80  5965.3  347.52
#Mann=6,-1,0
  4411.3   0.063       0  4635.8   0.033       0  4660.5   0.063       0
  4666.6   0.033       0  5446.5    0.07       0  5666.5   0.063       0
Bank Sta=4635.8,4660.5
Exp/Cntr=0.3,0.1

Type RM Length L Ch R = 1,12476,785,785,785
BEGIN DESCRIPTION:
Prairie Creek12476.13
END DESCRIPTION:
XS GIS Cut Line= 3
      2697715.60      6809173.44      2697221.75      6808772.72
      2696249.68      6808507.05
#Sta/Elev= 30
  4369.5  337.00  4427.9  333.62  4477.5  332.47  4491.9  330.71  4498.3  330.88
  4520.6  328.70  4527.1  326.10  4535.0  325.73  4541.4  323.79  4586.6  322.00
  4587.1  321.50  4610.8  321.50  4611.3  322.00  5409.7  322.00  5457.2  322.00
  5467.6  323.13  5564.0  325.40  5638.9  328.55  5706.0  332.92  5712.5  333.99
  5752.2  336.13  5757.8  337.06  5768.2  337.24  5786.7  339.03  5826.4  339.92
  5892.6  344.51  5965.2  347.06  5980.0  346.70  5985.9  347.59  6013.2  349.00
#Mann=5,-1,0
  4369.5   0.063       0  4586.6   0.033       0  4611.3   0.063       0
  5409.7    0.16       0  5638.9   0.063       0
Bank Sta=4586.6,4611.3
Exp/Cntr=0.3,0.1

Type RM Length L Ch R = 1,11691,314,314,314
BEGIN DESCRIPTION:
Prairie Creek11690.74
END DESCRIPTION:
XS GIS Cut Line= 3
      2697725.23      6807510.38      2697114.85      6808032.60
      2696232.82      6808412.85
#Sta/Elev= 30
  4211.2  338.52  4267.7  337.60  4310.5  335.84  4359.9  333.27  4443.5  331.52
  4487.2  330.17  4593.0  328.72  4650.8  327.21  4679.4  324.61  4714.5  323.51
  4722.2  322.93  4723.9  322.00  4724.4  321.50  4749.0  322.00  5416.2  322.00
  5421.3  322.65  5437.9  325.66  5477.5  328.17  5527.0  329.49  5652.4  334.28
  5657.9  333.79  5675.9  334.75  5681.4  334.00  5688.4  335.62  5699.3  336.57
  5733.9  336.26  5786.4  339.61  5851.5  341.60  5967.6  347.66  5975.0  347.82
#Mann=10,-1,0
  4211.2    0.16       0  4310.5   0.063       0  4443.5    0.16       0
  4593.0   0.033       0  4723.9   0.033       0  4749.0   0.033       0
  5421.3    0.16       0  5477.5   0.033       0  5527.0   0.063       0
  5967.6    0.16       0
Bank Sta=4723.9,4749
Exp/Cntr=0.3,0.1

Type RM Length L Ch R = 1,11377,412,412,412
BEGIN DESCRIPTION:
Prairie Creek11377.398
END DESCRIPTION:
XS GIS Cut Line= 3
      2697971.09      6807301.17      2697068.17      6807729.75
      2696236.42      6808100.71
#Sta/Elev= 30
  4009.3  336.02  4140.1  337.77  4202.4  339.35  4236.3  339.15  4247.4  337.96
  4250.9  338.68  4276.1  339.61  4361.7  337.45  4368.9  337.28  4435.2  336.37
  4472.6  333.83  4508.9  333.16  4631.9  326.16  4679.1  324.64  4683.7  322.00
  4684.2  321.50  4708.8  322.00  5297.7  322.00  5400.7  327.05  5494.5  329.74
  5540.9  331.69  5547.7  332.92  5574.1  331.98  5662.5  336.55  5685.8  339.57
  5722.9  339.60  5748.9  342.00  5830.6  345.26  5902.7  345.70  5919.5  345.40
#Mann=13,-1,0
  4009.3    0.16       0  4140.1   0.063       0  4250.9    0.16       0
  4361.7    0.07       0  4368.9   0.063       0  4472.6    0.16       0
  4631.9   0.033       0  4683.7   0.033       0  4708.8   0.033       0
  5400.7    0.16       0  5574.1   0.063       0  5748.9    0.16       0
  5902.7   0.063       0
Bank Sta=4683.7,4708.8
Exp/Cntr=0.3,0.1

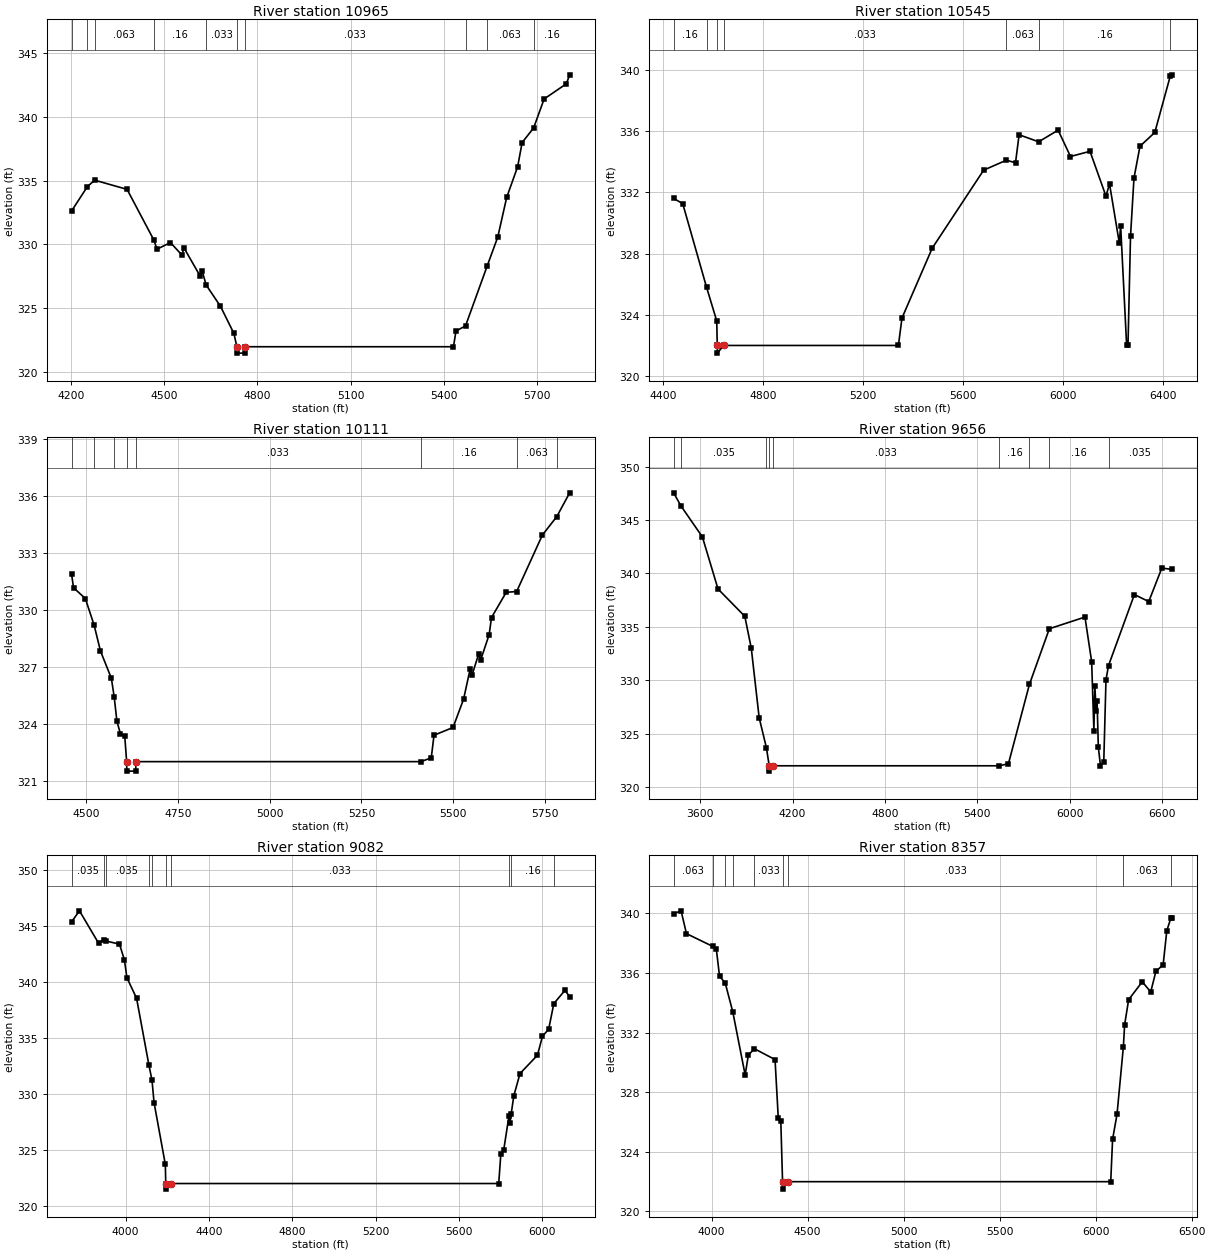
Type RM Length L Ch R = 1,10965,420,420,420
BEGIN DESCRIPTION:
Prairie Creek10964.959
END DESCRIPTION:
XS GIS Cut Line= 3
      2697667.31      6806947.97      2696976.66      6807345.73
      2696352.25      6807852.21
#Sta/Elev= 30
  4203.0  332.62  4253.7  334.52  4277.1  335.03  4381.4  334.31  4467.4  330.35
  4477.6  329.63  4520.8  330.15  4558.1  329.16  4563.9  329.75  4617.0  327.50
  4622.8  327.91  4635.6  326.83  4681.7  325.16  4724.8  323.04  4734.3  322.00
  4734.8  321.50  4759.0  321.50  4759.5  322.00  5430.6  322.00  5438.6  323.23
  5469.3  323.63  5538.5  328.29  5572.9  330.58  5601.6  333.68  5636.8  336.08
  5651.2  337.97  5688.3  339.12  5721.9  341.38  5793.4  342.57  5804.0  343.27
#Mann=10,-1,0
  4203.0   0.063       0  4253.7    0.07       0  4277.1   0.063       0
  4467.4    0.16       0  4635.6   0.033       0  4734.3   0.033       0
  4759.5   0.033       0  5469.3    0.16       0  5538.5   0.063       0
  5688.3    0.16       0
Bank Sta=4734.3,4759.5
Exp/Cntr=0.3,0.1

Type RM Length L Ch R = 1,10545,434,434,434
BEGIN DESCRIPTION:
Mapping XS 384b5334
END DESCRIPTION:
XS GIS Cut Line= 4
      2697290.59      6806644.87      2696836.83      6806970.66
      2696075.88      6807893.03      2695853.25      6807984.15
#Sta/Elev= 30
  4441.4  331.59  4477.7  331.26  4573.0  325.81  4614.0  323.60  4616.1  322.00
  4616.6  321.50  4641.3  322.00  5341.6  322.00  5355.9  323.79  5477.1  328.35
  5683.0  333.44  5774.2  334.09  5810.6  333.92  5825.0  335.75  5903.3  335.29
  5981.3  336.05  6030.8  334.33  6109.0  334.67  6172.8  331.75  6187.2  332.54
  6226.3  328.69  6231.7  329.81  6255.7  322.00  6261.1  322.00  6271.3  329.14
  6285.1  332.92  6309.1  335.00  6368.5  335.90  6430.6  339.59  6436.3  339.66
#Mann=7,-1,0
  4441.4    0.16       0  4573.0   0.033       0  4616.1   0.033       0
  4641.3   0.033       0  5774.2   0.063       0  5903.3    0.16       0
  6430.6   0.063       0
Bank Sta=4616.1,4641.3
Exp/Cntr=0.3,0.1

Type RM Length L Ch R = 1,10111,455,455,455
BEGIN DESCRIPTION:
Prairie Creek10111.094
END DESCRIPTION:
XS GIS Cut Line= 3
      2697201.00      6806386.00      2696695.63      6806584.21
      2695951.43      6806915.61
#Sta/Elev= 30
  4459.9  331.87  4465.3  331.16  4497.5  330.59  4521.5  329.18  4538.6  327.83
  4568.4  326.39  4576.2  325.39  4583.4  324.14  4592.8  323.48  4604.9  323.33
  4610.0  322.00  4610.5  321.50  4634.8  321.50  4635.3  322.00  5412.1  322.00
  5440.2  322.20  5447.7  323.39  5499.6  323.80  5528.3  325.29  5546.1  326.87
  5551.6  326.58  5569.3  327.66  5574.8  327.35  5598.0  328.69  5604.4  329.59
  5644.5  330.92  5672.9  330.96  5742.9  333.93  5782.4  334.91  5817.4  336.16
#Mann=8,-1,0
  4459.9   0.063       0  4521.5    0.16       0  4576.2   0.033       0
  4610.0   0.033       0  4635.3   0.033       0  5412.1    0.16       0
  5672.9   0.063       0  5782.4    0.16       0
Bank Sta=4610,4635.3
Exp/Cntr=0.3,0.1

Type RM Length L Ch R = 1,9656,574,574,574
BEGIN DESCRIPTION:
Prairie Creek9655.606
END DESCRIPTION:
XS GIS Cut Line= 4
      2697901.02      6805235.99      2696846.77      6805943.40
      2696076.14      6806667.29      2695361.49      6807226.44
#Sta/Elev= 30
  3427.7  347.55  3474.8  346.33  3614.4  343.42  3715.8  338.55  3889.8  335.99
  3931.9  333.00  3982.9  326.51  4030.0  323.69  4048.3  322.00  4048.8  321.50
  4073.6  322.00  5543.6  322.00  5601.8  322.20  5738.0  329.62  5867.3  334.83
  6098.6  335.92  6142.0  331.75  6156.5  325.29  6162.8  329.47  6170.9  327.15
  6177.3  328.05  6185.4  323.76  6199.2  322.00  6220.7  322.37  6235.1  330.05
  6251.5  331.38  6419.6  338.03  6512.7  337.37  6597.8  340.51  6662.0  340.38
#Mann=9,-1,0
  3427.7   0.063       0  3474.8   0.035       0  4030.0   0.033       0
  4048.3   0.033       0  4073.6   0.033       0  5543.6    0.16       0
  5738.0   0.063       0  5867.3    0.16       0  6251.5   0.035       0
Bank Sta=4048.3,4073.6
Exp/Cntr=0.3,0.1

Type RM Length L Ch R = 1,9082,725,725,725
BEGIN DESCRIPTION:
Prairie Creek9082.273
END DESCRIPTION:
XS GIS Cut Line= 3
      2697650.96      6805136.02      2696489.97      6805624.07
      2695439.24      6806044.17
#Sta/Elev= 30
  3740.6  345.36  3778.5  346.34  3870.2  343.45  3894.8  343.77  3904.3  343.65
  3970.6  343.37  3994.3  341.96  4006.3  340.37  4052.7  338.53  4111.7  332.59
  4126.7  331.22  4136.5  329.23  4190.7  323.70  4192.7  322.00  4193.2  321.50
  4219.3  322.00  5791.1  322.00  5801.2  324.63  5815.3  325.02  5840.4  328.04
  5845.0  327.43  5850.5  328.17  5863.8  329.85  5893.4  331.82  5976.9  333.45
  6001.2  335.15  6030.8  335.77  6055.6  338.06  6108.9  339.24  6131.6  338.68
#Mann=10,-1,0
  3740.6   0.035       0  3894.8   0.063       0  3904.3   0.035       0
  4111.7    0.16       0  4126.7   0.033       0  4192.7   0.033       0
  4219.3   0.033       0  5840.4    0.07       0  5850.5    0.16       0
  6055.6    0.07       0
Bank Sta=4192.7,4219.3
Exp/Cntr=0.3,0.1

Type RM Length L Ch R = 1,8357,602,602,602
BEGIN DESCRIPTION:
Prairie Creek8357.13
END DESCRIPTION:
XS GIS Cut Line= 3
      2697203.30      6804477.19      2696124.79      6805026.62
      2694801.37      6805429.92
#Sta/Elev= 30
  3802.3  339.98  3841.1  340.17  3869.0  338.64  4005.1  337.79  4024.7  337.59
  4041.3  335.78  4070.7  335.34  4110.3  333.39  4174.7  329.16  4191.3  330.49
  4222.7  330.92  4330.4  330.19  4347.0  326.30  4360.4  326.05  4369.5  322.00
  4370.0  321.50  4396.2  322.00  6078.5  322.00  6088.2  324.84  6111.3  326.52
  6144.4  331.05  6150.9  332.53  6171.8  334.21  6242.7  335.41  6286.8  334.73
  6313.6  336.10  6351.6  336.56  6370.5  338.83  6392.2  339.71  6396.2  339.71
#Mann=9,-1,0
  3802.3   0.063       0  4005.1   0.035       0  4070.7   0.063       0
  4110.3   0.094       0  4222.7   0.033       0  4369.5   0.033       0
  4396.2   0.033       0  6144.4   0.063       0  6392.2    0.16       0
Bank Sta=4369.5,4396.2
Exp/Cntr=0.3,0.1

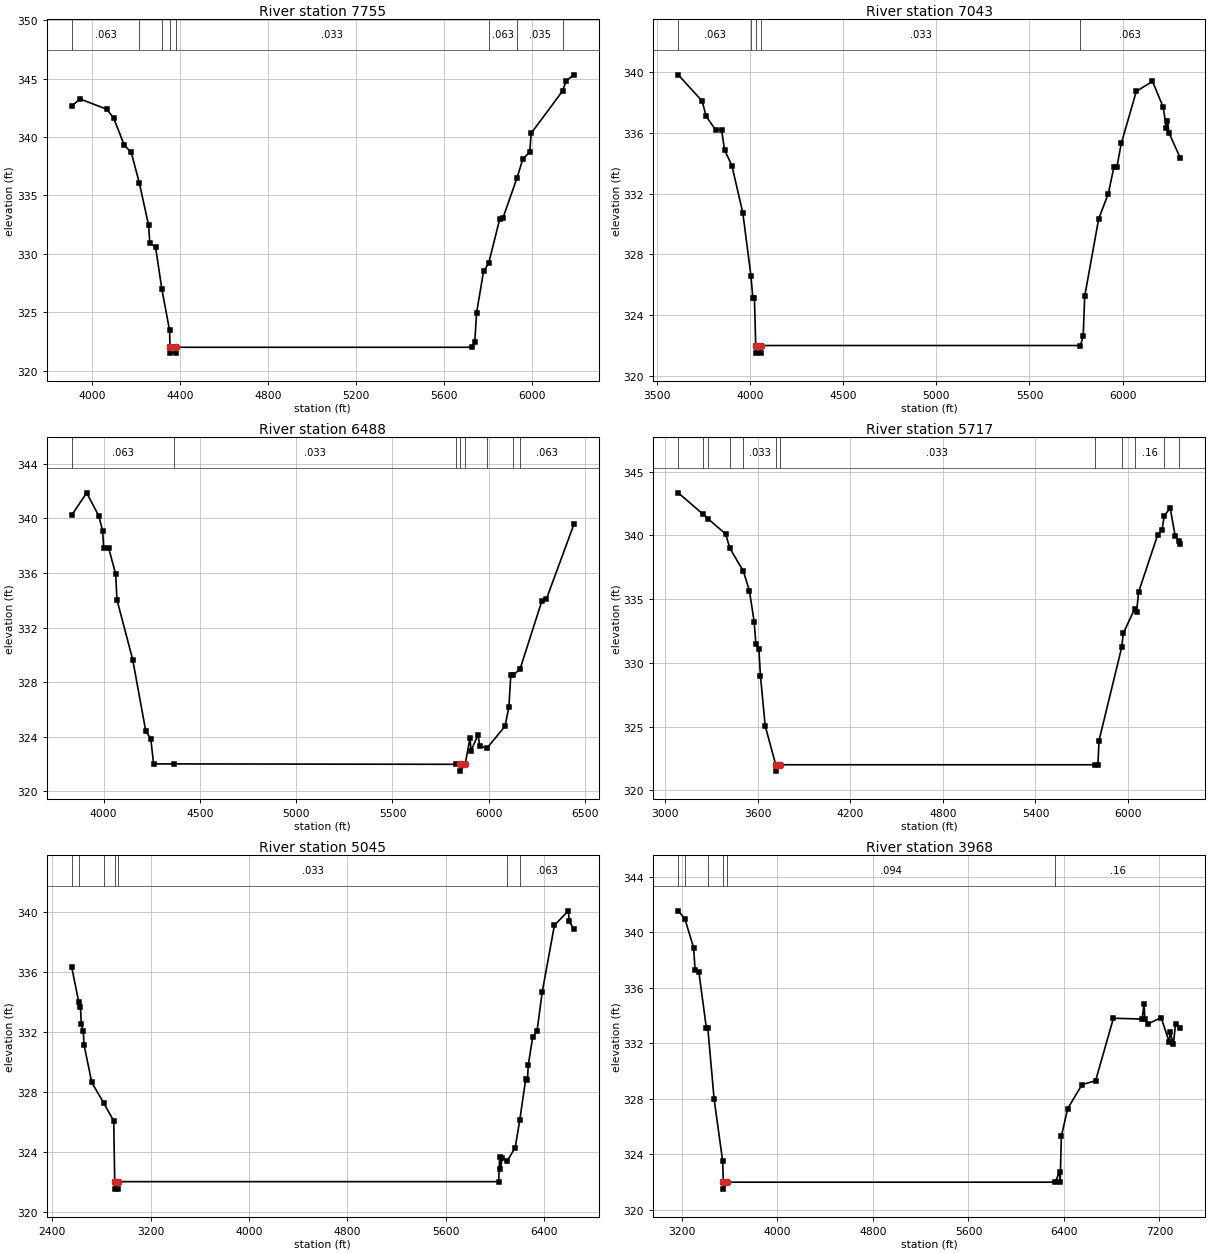
Type RM Length L Ch R = 1,7755,712,712,712
BEGIN DESCRIPTION:
Prairie Creek7755.09
END DESCRIPTION:
XS GIS Cut Line= 3
      2696962.58      6804147.07      2695916.19      6804491.60
      2694796.05      6804856.08
#Sta/Elev= 30
  3908.4  342.67  3946.9  343.25  4066.4  342.38  4098.2  341.64  4146.9  339.29
  4178.5  338.68  4215.0  336.07  4257.1  332.46  4262.8  330.91  4288.9  330.58
  4317.3  326.99  4352.4  323.46  4354.5  322.00  4355.0  321.50  4381.0  321.50
  4381.5  322.00  5725.3  322.00  5738.2  322.42  5746.4  324.95  5777.9  328.49
  5801.0  329.18  5851.5  332.98  5865.9  333.06  5930.3  336.52  5956.5  338.12
  5988.2  338.72  5993.7  340.30  6136.5  343.93  6153.3  344.81  6188.0  345.32
#Mann=8,-1,0
  3908.4   0.063       0  4215.0    0.16       0  4317.3   0.033       0
  4354.5   0.033       0  4381.5   0.033       0  5801.0   0.063       0
  5930.3   0.035       0  6136.5   0.063       0
Bank Sta=4354.5,4381.5
Exp/Cntr=0.3,0.1

Type RM Length L Ch R = 1,7043,555,555,555
BEGIN DESCRIPTION:
Prairie Creek7042.79
END DESCRIPTION:
XS GIS Cut Line= 3
      2697309.77      6803418.89      2695950.09      6803799.66
      2694780.56      6804325.27
#Sta/Elev= 30
  3615.3  339.82  3743.8  338.09  3764.6  337.10  3816.5  336.18  3847.7  336.22
  3863.7  334.88  3903.0  333.85  3961.9  330.73  4005.4  326.59  4015.8  325.12
  4024.2  325.11  4031.1  322.00  4031.6  321.50  4057.7  321.50  4058.2  322.00
  5773.2  322.00  5788.3  322.61  5796.4  325.24  5871.3  330.33  5923.1  332.00
  5952.7  333.72  5969.5  333.78  5992.6  335.30  6073.3  338.73  6160.2  339.39
  6217.5  337.70  6235.2  336.29  6240.7  336.81  6248.7  336.00  6309.5  334.34
#Mann=5,-1,0
  3615.3   0.063       0  4005.4   0.033       0  4031.1   0.033       0
  4058.2   0.033       0  5773.2   0.063       0
Bank Sta=4031.1,4058.2
Exp/Cntr=0.3,0.1

Type RM Length L Ch R = 1,6488,771,771,771
BEGIN DESCRIPTION:
Prairie Creek6487.93
END DESCRIPTION:
XS GIS Cut Line= 3
      2696907.58      6802911.96      2695786.69      6803298.12
      2694369.81      6803406.99
#Sta/Elev= 30
  3835.1  340.25  3912.5  341.88  3974.9  340.20  3995.4  339.09  4000.9  337.82
  4026.8  337.82  4063.3  335.91  4069.5  334.05  4151.6  329.64  4219.4  324.39
  4245.3  323.85  4259.8  322.00  4364.3  322.00  5830.1  321.97  5850.3  321.97
  5850.8  321.47  5877.4  321.97  5902.8  323.91  5907.8  322.97  5944.0  324.12
  5954.1  323.29  5991.8  323.17  6084.5  324.77  6104.5  326.17  6114.5  328.55
  6128.4  328.51  6163.0  328.98  6275.0  333.92  6299.2  334.09  6441.7  339.56
#Mann=8,-1,0
  3835.1   0.063       0  4364.3   0.033       0  5830.1    0.16       0
  5850.3   0.033       0  5877.4    0.16       0  5991.8   0.033       0
  6128.4    0.16       0  6163.0   0.063       0
Bank Sta=5850.3,5877.4
Exp/Cntr=0.3,0.1

Type RM Length L Ch R = 1,5717,672,672,672
BEGIN DESCRIPTION:
Prairie Creek5716.6
END DESCRIPTION:
XS GIS Cut Line= 3
      2697596.25      6802126.50      2695711.54      6802549.62
      2694495.67      6803074.38
#Sta/Elev= 30
  3083.2  343.33  3244.5  341.65  3274.9  341.31  3390.9  340.10  3418.3  338.97
  3505.4  337.19  3544.7  335.65  3575.4  333.23  3586.9  331.45  3606.1  331.07
  3616.4  328.97  3647.1  325.05  3715.5  322.00  3716.0  321.50  3742.8  322.00
  5784.1  322.00  5805.0  322.00  5811.9  323.90  5958.8  331.20  5969.3  332.31
  6043.9  334.25  6055.6  334.01  6068.7  335.55  6191.7  340.01  6220.7  340.42
  6234.6  341.52  6273.4  342.14  6306.1  339.92  6331.0  339.54  6339.1  339.33
#Mann=12,-1,0
  3083.2   0.063       0  3244.5    0.16       0  3274.9   0.063       0
  3418.3    0.16       0  3505.4   0.033       0  3715.5   0.033       0
  3742.8   0.033       0  5784.1    0.16       0  5958.8   0.063       0
  6043.9    0.16       0  6234.6   0.063       0  6331.0    0.16       0
Bank Sta=3715.5,3742.8
Exp/Cntr=0.3,0.1

Type RM Length L Ch R = 1,5045,1077,1077,1077
BEGIN DESCRIPTION:
Prairie Creek5044.97
END DESCRIPTION:
XS GIS Cut Line= 3
      2697946.47      6800857.22      2695717.39      6801878.70
      2694498.08      6802966.20
#Sta/Elev= 30
  2557.5  336.31  2613.8  334.02  2628.1  333.67  2635.0  332.53  2651.1  332.04
  2657.0  331.16  2720.1  328.63  2818.6  327.23  2899.0  326.06  2907.1  322.00
  2907.6  321.50  2934.4  321.50  2934.9  322.00  6031.7  322.00  6039.2  323.66
  6045.9  322.83  6060.1  323.55  6102.6  323.40  6166.3  324.28  6203.9  326.15
  6251.6  328.86  6265.8  328.79  6272.5  329.81  6308.4  331.64  6343.6  332.07
  6386.2  334.68  6485.3  339.13  6598.6  340.09  6605.9  339.39  6643.3  338.87
#Mann=7,-1,0
  2557.5   0.035       0  2613.8   0.063       0  2818.6   0.033       0
  2907.1   0.033       0  2934.9   0.033       0  6102.6    0.16       0
  6203.9   0.063       0
Bank Sta=2907.1,2934.9
Exp/Cntr=0.3,0.1

Type RM Length L Ch R = 1,3968,0,0,0
BEGIN DESCRIPTION:
Prairie Creek3968.454
END DESCRIPTION:
XS GIS Cut Line= 3
      2697000.95      6800436.01      2695255.62      6800991.16
      2694255.08      6803144.79
#Sta/Elev= 30
  3168.5  341.53  3223.9  340.96  3297.4  338.87  3310.1  337.24  3341.6  337.11
  3404.6  333.07  3416.0  333.11  3469.1  327.98  3541.0  323.50  3546.6  322.00
  3547.1  321.50  3574.5  322.00  6327.6  322.00  6362.7  322.76  6368.2  322.01
  6378.1  325.30  6431.4  327.30  6551.4  329.02  6664.8  329.30  6814.2  333.80
  7054.2  333.74  7071.6  334.81  7077.1  333.73  7100.0  333.37  7214.4  333.85
  7282.3  332.06  7288.6  332.79  7317.0  331.97  7334.4  333.37  7374.7  333.08
#Mann=6,-1,0
  3168.5   0.094       0  3223.9   0.063       0  3416.0   0.094       0
  3546.6   0.033       0  3574.5   0.094       0  6327.6    0.16       0
Bank Sta=3546.6,3574.5
Exp/Cntr=0.3,0.1

Chan Stop Cuts=-1