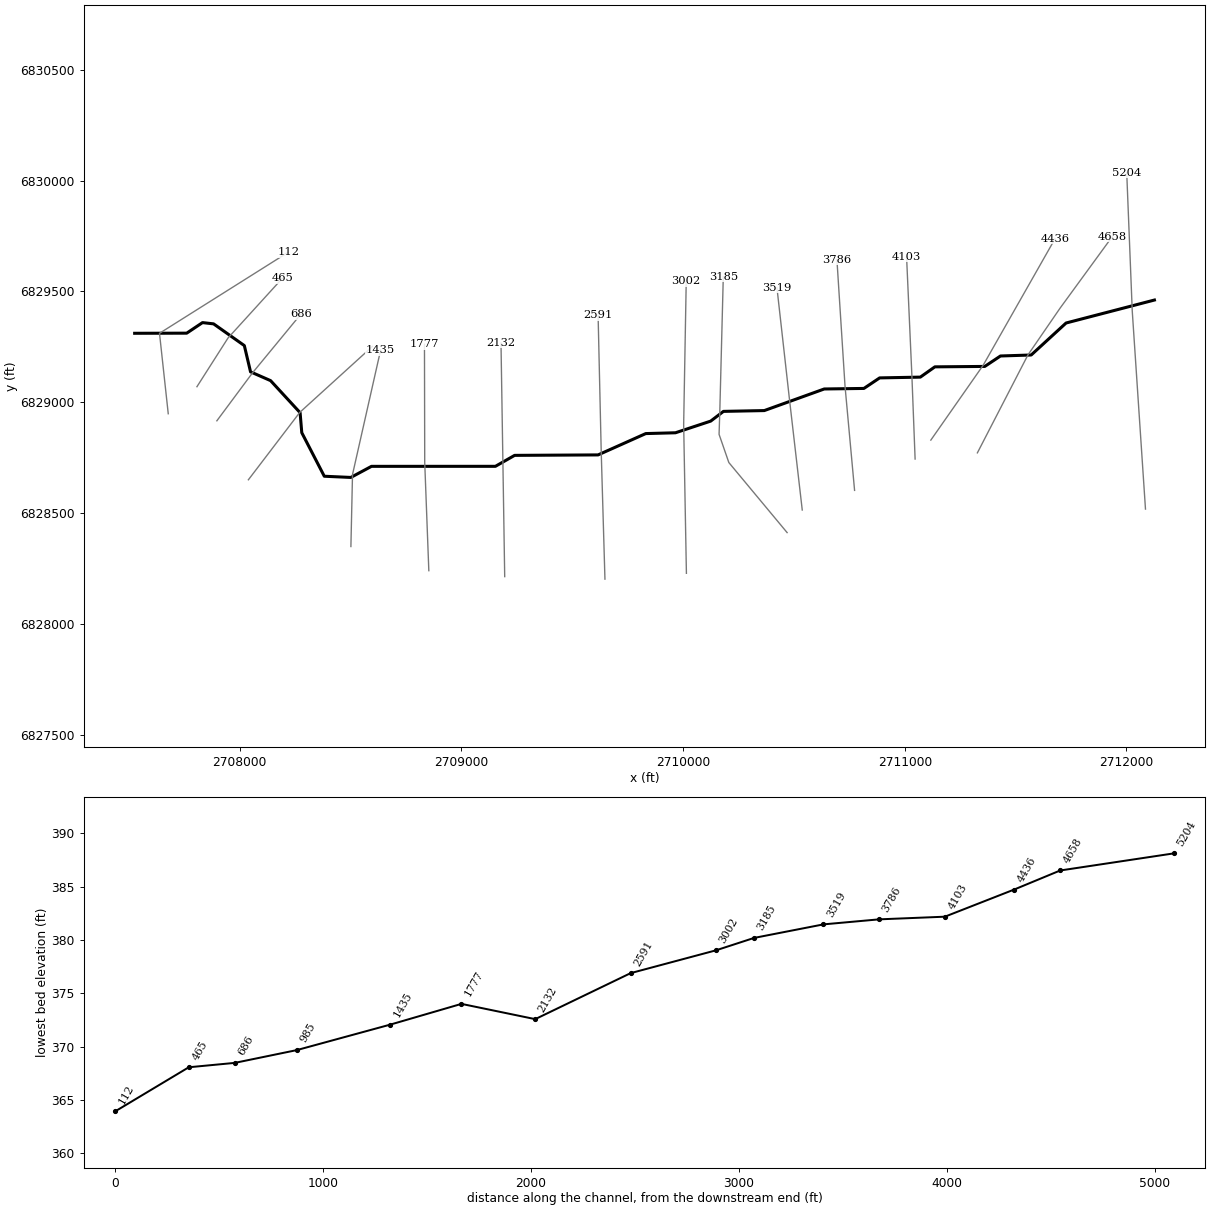
--- Prairie Creek Trib A.prj (project) ---

Proj Title=Prairie Creek Trib A Base Level Engineering
Current Plan=p01
Default Exp/Contr=0.3,0.1
English Units
Geom File=g01
Flow File=f01
Plan File=p01
BEGIN DESCRIPTION:
Prairie Creek Trib A
END DESCRIPTION:

--- Prairie Creek Trib A.p01 (plan) ---

Plan Title=Multiple Run
Short Identifier=Multiple
Geom File=g01
Flow File=f01
Subcritical Flow
K Sum by GR= 0
Std Step Tol= 0.01
Critical Tol= 0.01
Num of Std Step Trials= 20
Max Error Tol= 0.3
Flow Tol Ratio= 0.001
Split Flow NTrial= 30
Split Flow Tol= 0.02
Split Flow Ratio= 0.02
Log Output Level= 0
Friction Slope Method= 1
Unsteady Friction Slope Method= 2
Unsteady Bridges Friction Slope Method= 1
Parabolic Critical Depth
Global Vel Dist=  1 , 1 , 1
Global Log Level= 0
CheckData=True
Encroach Param= -1, 0, 0, 0
BEGIN DESCRIPTION:
Multiple Run
END DESCRIPTION:

--- Prairie Creek Trib A.f01 (steady flow) ---

Flow Title=Multiple
Number of Profiles=7
Profile Names=10-year,25-year,50-year,1pct_min,100-year,1pct_plu,500-year
River Rch & RM= Prairie Creek Tr,Reach-1,5204
     381     494     582     341     680    1356     926
River Rch & RM= Prairie Creek Tr,Reach-1,4658
     604     805     966     575    1148    2291    1619
River Rch & RM= Prairie Creek Tr,Reach-1,3002
     729     982    1186     711    1418    2829    2024
Boundary for River Rch & Prof#=Prairie Creek Tr,Reach-1,1
Up Type=0
Dn Type=3
Dn Slope=0.005
Boundary for River Rch & Prof#=Prairie Creek Tr,Reach-1,2
Up Type=0
Dn Type=3
Dn Slope=0.005
Boundary for River Rch & Prof#=Prairie Creek Tr,Reach-1,3
Up Type=0
Dn Type=3
Dn Slope=0.005
Boundary for River Rch & Prof#=Prairie Creek Tr,Reach-1,4
Up Type=0
Dn Type=3
Dn Slope=0.005
Boundary for River Rch & Prof#=Prairie Creek Tr,Reach-1,5
Up Type=0
Dn Type=3
Dn Slope=0.005
Boundary for River Rch & Prof#=Prairie Creek Tr,Reach-1,6
Up Type=0
Dn Type=3
Dn Slope=0.005
Boundary for River Rch & Prof#=Prairie Creek Tr,Reach-1,7
Up Type=0
Dn Type=3
Dn Slope=0.005

--- Prairie Creek Trib A.g01 (geometry) ---

Geom Title=Existing Conditions

River Reach=Prairie Creek Tr,Reach-1
Reach XY= 30
      2712126.00      6829461.00      2711727.50      6829357.39
      2711570.14      6829213.07      2711431.53      6829208.61
      2711360.78      6829161.52      2711135.66      6829159.62
      2711070.06      6829113.26      2710886.51      6829109.78
      2710815.49      6829062.22      2710636.51      6829059.78
      2710366.34      6828962.38      2710181.94      6828958.74
      2710124.40      6828914.86      2709965.49      6828862.23
      2709831.53      6828858.61      2709616.34      6828762.38
      2709239.92      6828760.32      2709153.31      6828710.91
      2708594.27      6828710.79      2708501.05      6828660.76
      2708381.41      6828666.16      2708279.85      6828862.65
      2708272.34      6828952.81      2708139.22      6829097.37
      2708048.73      6829137.12      2708020.74      6829255.53
      2707882.05      6829353.50      2707832.13      6829359.22
      2707760.79      6829311.54      2707526.00      6829311.00

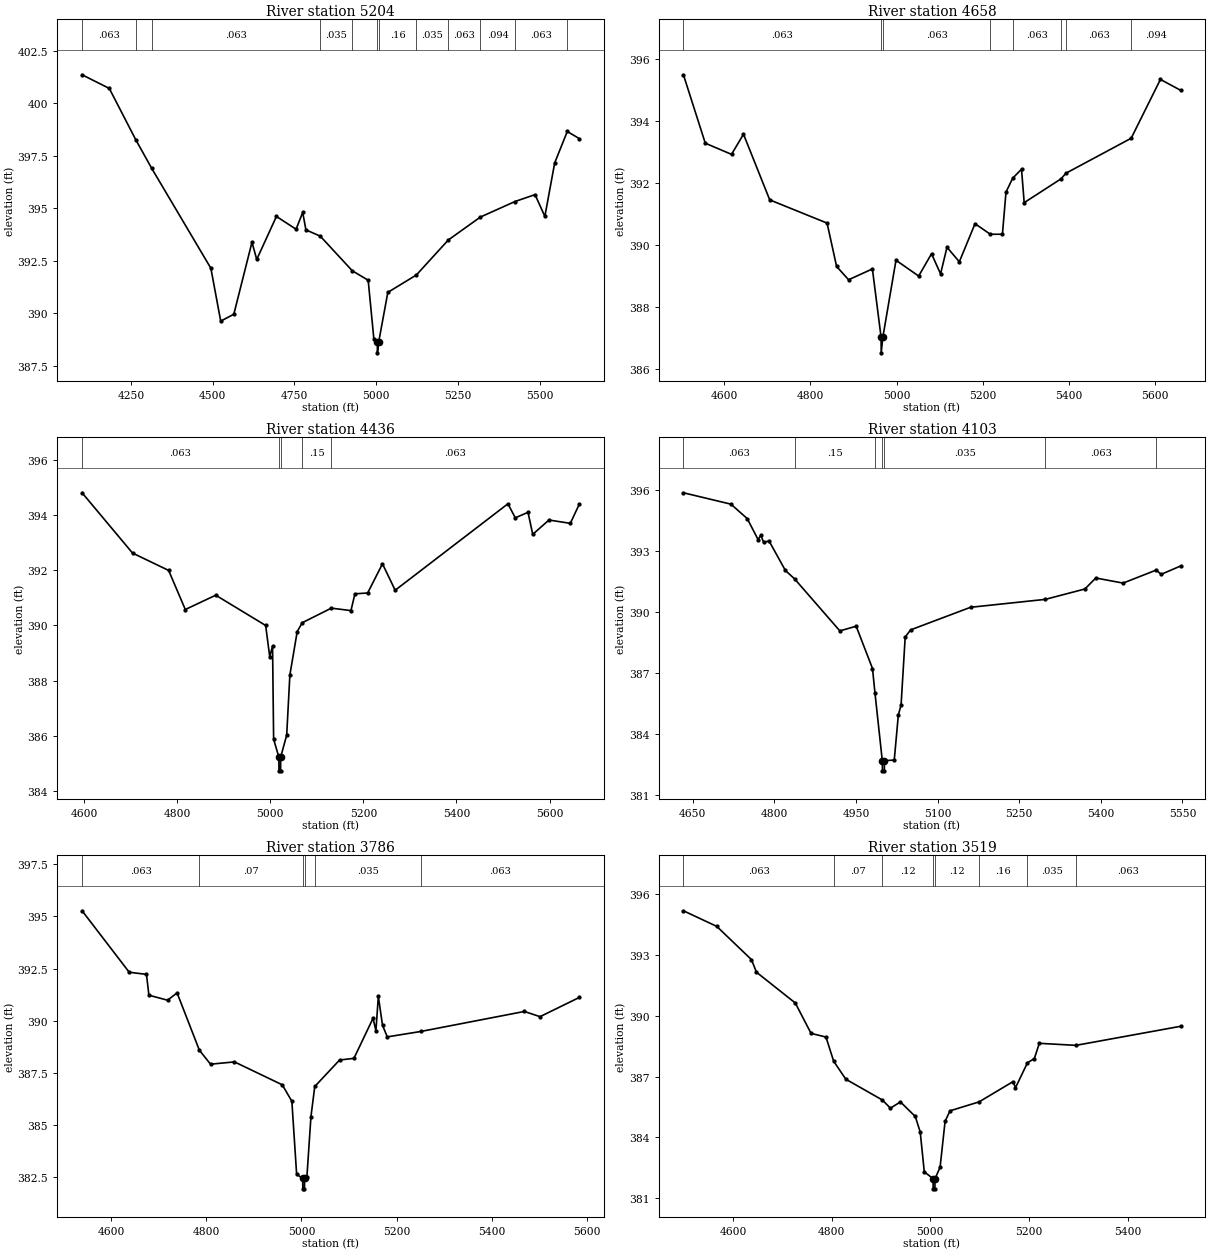
Type RM Length L Ch R = 1,5204,546,546,546
BEGIN DESCRIPTION:
Prairie Creek Trib A5203.766
END DESCRIPTION:
XS GIS Cut Line= 3
      2712085.65      6828517.96      2712026.00      6829411.00
      2712001.00      6830035.97
#Sta/Elev= 30
  4100.7  401.36  4183.9  400.71  4264.7  398.27  4313.3  396.91  4494.6  392.14
  4524.7  389.62  4564.8  389.95  4620.3  393.38  4634.9  392.56  4695.1  394.61
  4755.2  394.00  4775.5  394.80  4785.3  393.97  4829.2  393.67  4927.2  392.02
  4975.7  391.57  4993.2  388.76  5003.7  388.61  5004.0  388.11  5007.7  388.61
  5035.8  390.99  5123.1  391.82  5221.0  393.49  5318.9  394.58  5424.7  395.32
  5486.1  395.65  5516.1  394.61  5546.2  397.16  5584.7  398.66  5621.2  398.32
#Mann=12,-1,0
  4100.7   0.063       0  4264.7   0.094       0  4313.3   0.063       0
  4829.2   0.035       0  4927.2    0.16       0  5003.7    0.07       0
  5007.7    0.16       0  5123.1   0.035       0  5221.0   0.063       0
  5318.9   0.094       0  5424.7   0.063       0  5584.7   0.094       0
Bank Sta=5003.7,5007.7
Exp/Cntr=0.3,0.1

Type RM Length L Ch R = 1,4658,222,222,222
BEGIN DESCRIPTION:
Prairie Creek Trib A4657.53
END DESCRIPTION:
XS GIS Cut Line= 4
      2711327.41      6828771.64      2711555.36      6829213.27
      2711700.42      6829424.40      2711936.02      6829747.22
#Sta/Elev= 30
  4505.7  395.49  4556.4  393.28  4617.2  392.92  4645.0  393.57  4705.8  391.45
  4838.8  390.70  4860.9  389.30  4888.7  388.87  4943.9  389.22  4964.1  387.01
  4964.3  386.51  4968.1  387.01  4998.6  389.50  5051.2  388.99  5081.0  389.71
  5102.0  389.06  5116.9  389.92  5145.5  389.45  5181.9  390.68  5217.3  390.34
  5245.4  390.34  5253.7  391.70  5269.2  392.15  5289.7  392.44  5295.9  391.36
  5381.4  392.13  5392.6  392.31  5544.0  393.44  5611.8  395.34  5658.5  394.99
#Mann=8,-1,0
  4505.7   0.063       0  4964.1   0.063       0  4968.1   0.063       0
  5217.3   0.035       0  5269.2   0.063       0  5381.4    0.16       0
  5392.6   0.063       0  5544.0   0.094       0
Bank Sta=4964.1,4968.1
Exp/Cntr=0.3,0.1

Type RM Length L Ch R = 1,4436,333,333,333
BEGIN DESCRIPTION:
Prairie Creek Trib A4436.44
END DESCRIPTION:
XS GIS Cut Line= 3
      2711117.44      6828829.21      2711353.62      6829167.08
      2711677.64      6829737.55
#Sta/Elev= 30
  4595.5  394.82  4703.9  392.63  4781.5  392.00  4817.3  390.58  4882.7  391.10
  4990.0  390.00  4998.7  388.87  5004.8  389.25  5007.1  385.87  5018.3  385.22
  5018.6  384.72  5022.1  384.72  5022.3  385.22  5035.2  386.02  5042.0  388.20
  5057.8  389.78  5068.6  390.10  5131.1  390.63  5173.3  390.54  5181.8  391.15
  5209.2  391.18  5241.0  392.24  5268.3  391.28  5510.6  394.42  5526.4  393.91
  5553.8  394.11  5563.9  393.31  5598.8  393.83  5644.7  393.71  5663.8  394.40
#Mann=5,-1,0
  4595.5   0.063       0  5018.3   0.063       0  5022.3   0.063       0
  5068.6    0.15       0  5131.1   0.063       0
Bank Sta=5018.3,5022.3
Exp/Cntr=0.3,0.1

Type RM Length L Ch R = 1,4103,317,317,317
BEGIN DESCRIPTION:
Prairie Creek Trib A4103.43
END DESCRIPTION:
XS GIS Cut Line= 3
      2711046.48      6828743.75      2711032.05      6829117.46
      2711007.95      6829656.63
#Sta/Elev= 30
  4632.9  395.85  4720.2  395.29  4750.2  394.58  4770.1  393.55  4775.1  393.76
  4780.3  393.42  4790.3  393.48  4820.3  392.03  4837.1  391.62  4920.4  389.06
  4950.4  389.29  4980.4  387.21  4984.9  386.02  4998.4  382.68  4998.7  382.18
  5002.2  382.18  5002.4  382.68  5020.4  382.71  5027.9  384.93  5032.9  385.41
  5040.5  388.76  5050.5  389.11  5160.6  390.22  5298.0  390.61  5370.8  391.12
  5390.8  391.66  5440.9  391.41  5501.9  392.05  5510.9  391.84  5546.6  392.25
#Mann=7,-1,0
  4632.9   0.063       0  4837.1    0.15       0  4984.9   0.035       0
  4998.4   0.035       0  5002.4   0.035       0  5298.0   0.063       0
  5501.9   0.094       0
Bank Sta=4998.4,5002.4
Exp/Cntr=0.3,0.1

Type RM Length L Ch R = 1,3786,267,267,267
BEGIN DESCRIPTION:
Prairie Creek Trib A3786.38
END DESCRIPTION:
XS GIS Cut Line= 3
      2710773.44      6828602.38      2710730.35      6829072.45
      2710693.77      6829643.14
#Sta/Elev= 30
  4539.5  395.27  4638.5  392.32  4674.7  392.22  4679.8  391.22  4718.9  390.98
  4739.0  391.33  4785.8  388.58  4809.2  387.91  4859.5  388.02  4959.9  386.92
  4980.0  386.13  4990.0  382.63  5002.7  382.43  5003.0  381.93  5006.5  381.93
  5006.7  382.43  5011.5  382.48  5020.1  385.40  5028.1  386.84  5080.2  388.11
  5110.3  388.19  5150.4  390.11  5156.5  389.52  5161.6  391.16  5170.4  389.77
  5180.4  389.22  5250.8  389.48  5468.2  390.44  5501.1  390.19  5583.4  391.11
#Mann=6,-1,0
  4539.5   0.063       0  4785.8    0.07       0  5002.7    0.07       0
  5006.7    0.07       0  5028.1   0.035       0  5250.8   0.063       0
Bank Sta=5002.7,5006.7
Exp/Cntr=0.3,0.1

Type RM Length L Ch R = 1,3519,334,334,334
BEGIN DESCRIPTION:
Prairie Creek Trib A3518.79
END DESCRIPTION:
XS GIS Cut Line= 3
      2710537.40      6828513.84      2710478.75      6829021.67
      2710423.36      6829515.67
#Sta/Elev= 30
  4499.3  395.18  4566.9  394.41  4637.3  392.77  4647.4  392.15  4726.2  390.63
  4758.2  389.13  4788.4  388.95  4804.0  387.76  4828.6  386.87  4902.3  385.85
  4919.2  385.44  4939.4  385.75  4969.6  385.03  4979.6  384.26  4987.8  382.30
  5005.6  381.96  5005.9  381.46  5009.4  381.46  5009.6  381.96  5019.9  382.53
  5030.0  384.79  5040.0  385.31  5098.9  385.75  5167.8  386.75  5172.8  386.45
  5197.1  387.68  5211.1  387.89  5221.1  388.64  5295.4  388.54  5507.6  389.48
#Mann=8,-1,0
  4499.3   0.063       0  4804.0    0.07       0  4902.3    0.12       0
  5005.6    0.07       0  5009.6    0.12       0  5098.9    0.16       0
  5197.1   0.035       0  5295.4   0.063       0
Bank Sta=5005.6,5009.6
Exp/Cntr=0.3,0.1

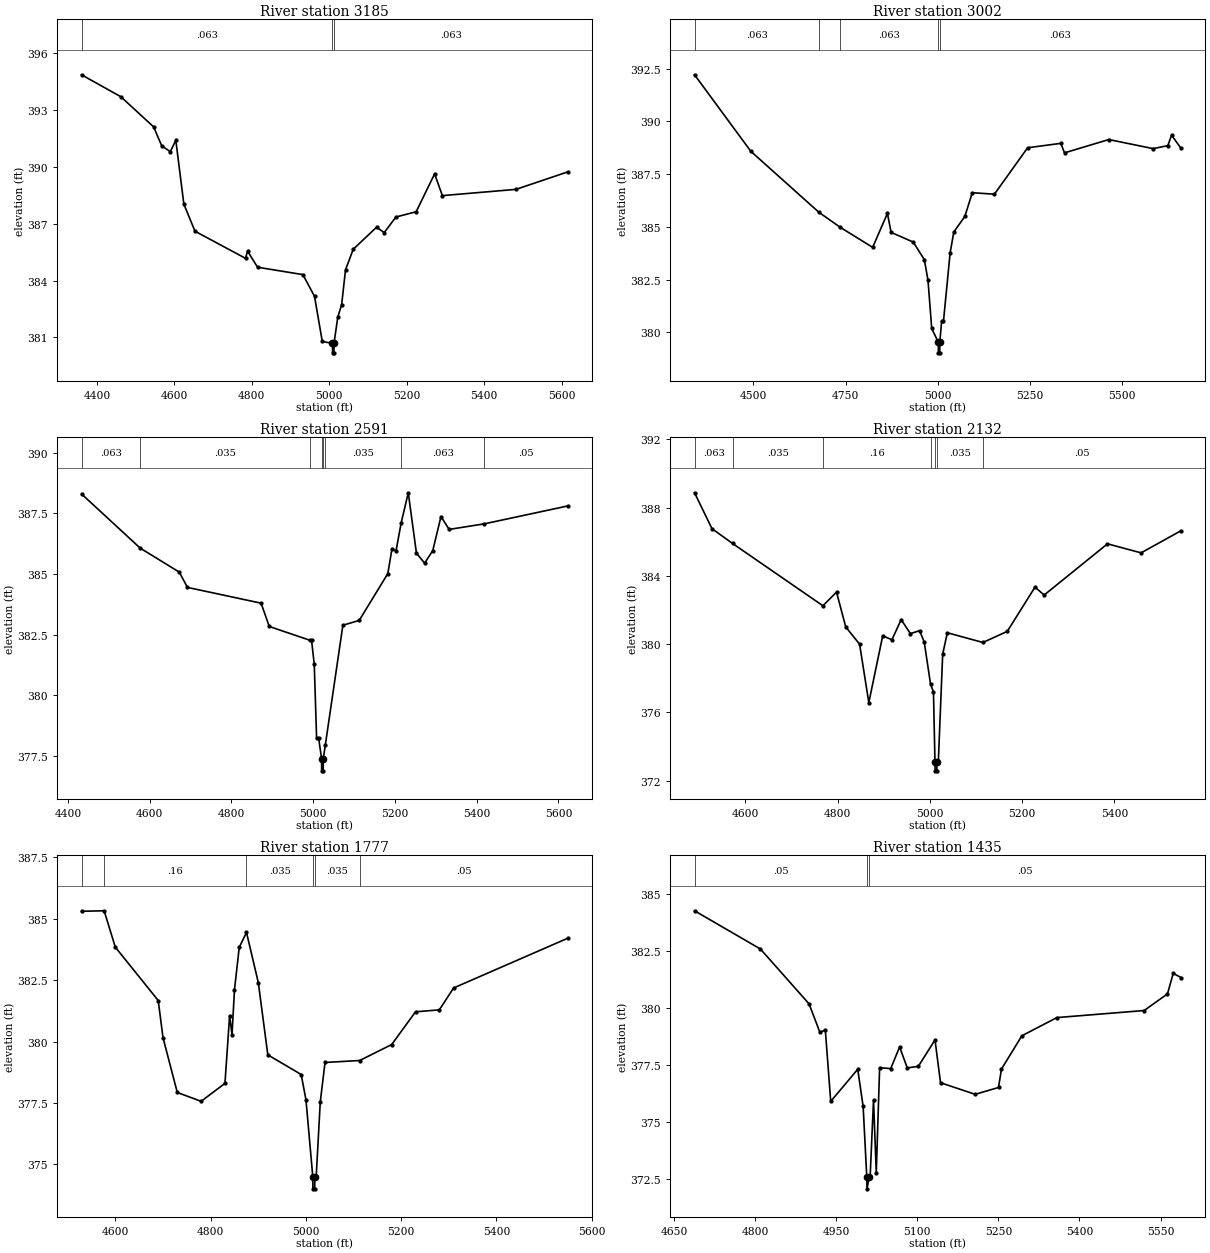
Type RM Length L Ch R = 1,3185,183,183,183
BEGIN DESCRIPTION:
Prairie Creek Trib A3185.01
END DESCRIPTION:
XS GIS Cut Line= 5
      2710469.17      6828411.90      2710206.25      6828727.96
      2710162.20      6828855.11      2710165.62      6828962.55
      2710181.21      6829565.57
#Sta/Elev= 30
  4360.2  394.87  4461.7  393.71  4546.3  392.12  4567.2  391.12  4589.3  390.81
  4603.6  391.41  4624.4  388.04  4653.1  386.61  4783.6  385.18  4788.9  385.56
  4814.7  384.71  4931.8  384.32  4961.8  383.17  4981.8  380.79  5008.1  380.69
  5008.4  380.19  5011.9  380.19  5012.1  380.69  5021.8  382.07  5031.8  382.73
  5041.8  384.57  5061.8  385.66  5121.9  386.82  5141.9  386.54  5171.9  387.36
  5224.3  387.64  5271.9  389.64  5291.9  388.49  5482.0  388.82  5616.6  389.75
#Mann=3,-1,0
  4360.2   0.063       0  5008.1   0.063       0  5012.1   0.063       0
Bank Sta=5008.1,5012.1
Exp/Cntr=0.3,0.1

Type RM Length L Ch R = 1,3002,411,411,411
BEGIN DESCRIPTION:
Prairie Creek Trib A3001.98
END DESCRIPTION:
XS GIS Cut Line= 3
      2710014.88      6828228.33      2710002.46      6828899.94
      2710014.07      6829546.91
#Sta/Elev= 30
  4340.6  392.21  4493.3  388.58  4677.8  385.69  4735.5  384.98  4823.4  384.03
  4863.4  385.64  4873.4  384.74  4933.4  384.28  4963.4  383.45  4973.4  382.47
  4983.4  380.19  5001.3  379.53  5001.6  379.03  5005.2  379.03  5005.4  379.53
  5010.4  380.54  5015.4  380.54  5033.4  383.77  5043.4  384.76  5073.4  385.50
  5093.4  386.62  5153.4  386.55  5243.4  388.75  5333.4  388.96  5343.4  388.51
  5463.5  389.14  5583.5  388.71  5623.5  388.85  5633.5  389.35  5659.4  388.72
#Mann=5,-1,0
  4340.6   0.063       0  4677.8   0.035       0  4735.5   0.063       0
  5001.3   0.063       0  5005.4   0.063       0
Bank Sta=5001.3,5005.4
Exp/Cntr=0.3,0.1

Type RM Length L Ch R = 1,2591,459,459,459
BEGIN DESCRIPTION:
Prairie Creek Trib A2590.68
END DESCRIPTION:
XS GIS Cut Line= 3
      2709647.40      6828201.99      2709630.57      6828777.43
      2709616.52      6829391.89
#Sta/Elev= 30
  4433.4  388.30  4576.8  386.07  4672.5  385.08  4692.5  384.45  4872.6  383.80
  4892.6  382.84  4992.4  382.27  4996.0  382.28  5002.7  381.28  5008.4  378.24
  5013.4  378.24  5020.6  377.39  5020.8  376.89  5024.5  376.89  5024.8  377.39
  5029.9  377.97  5072.7  382.89  5112.7  383.09  5182.7  385.02  5192.7  386.03
  5202.7  385.95  5215.3  387.11  5232.7  388.35  5252.7  385.86  5272.7  385.45
  5292.7  385.97  5312.7  387.37  5332.7  386.84  5418.9  387.07  5623.7  387.81
#Mann=8,-1,0
  4433.4   0.063       0  4576.8   0.035       0  4992.4   0.063       0
  5020.6   0.063       0  5024.8   0.063       0  5029.9   0.035       0
  5215.3   0.063       0  5418.9    0.05       0
Bank Sta=5020.6,5024.8
Exp/Cntr=0.3,0.1

Type RM Length L Ch R = 1,2132,355,355,355
BEGIN DESCRIPTION:
Prairie Creek Trib A2132.48
END DESCRIPTION:
XS GIS Cut Line= 3
      2709195.24      6828213.30      2709186.95      6828736.99
      2709178.49      6829267.67
#Sta/Elev= 30
  4490.1  388.87  4527.8  386.77  4572.5  385.90  4768.3  382.25  4797.8  383.05
  4817.8  381.01  4847.8  380.00  4867.8  376.58  4897.9  380.49  4917.9  380.26
  4937.9  381.44  4957.9  380.62  4977.9  380.79  4987.9  380.13  5001.7  377.64
  5007.9  377.21  5011.2  373.08  5011.5  372.58  5015.2  372.58  5015.5  373.08
  5018.4  373.08  5027.9  379.41  5037.9  380.67  5115.1  380.10  5167.9  380.75
  5227.9  383.34  5247.9  382.88  5385.1  385.88  5457.9  385.35  5544.6  386.65
#Mann=7,-1,0
  4490.1   0.063       0  4572.5   0.035       0  4768.3    0.16       0
  5001.7   0.035       0  5011.2    0.07       0  5015.5   0.035       0
  5115.1    0.05       0
Bank Sta=5011.2,5015.5
Exp/Cntr=0.3,0.1

Type RM Length L Ch R = 1,1777,342,342,342
BEGIN DESCRIPTION:
Prairie Creek Trib A1777.43
END DESCRIPTION:
XS GIS Cut Line= 3
      2708852.95      6828240.14      2708834.44      6828728.94
      2708833.30      6829261.39
#Sta/Elev= 30
  4528.8  385.30  4576.2  385.32  4599.7  383.84  4689.8  381.67  4699.8  380.16
  4729.8  377.93  4779.8  377.57  4829.9  378.30  4839.7  381.06  4844.7  380.28
  4849.9  382.11  4859.9  383.83  4875.1  384.44  4899.9  382.40  4919.9  379.46
  4990.0  378.66  5000.0  377.63  5014.3  374.51  5014.6  374.01  5018.4  374.01
  5018.6  374.51  5021.5  374.51  5030.0  377.54  5040.0  379.15  5112.8  379.23
  5180.0  379.88  5230.0  381.21  5280.0  381.29  5310.0  382.18  5550.4  384.21
#Mann=6,-1,0
  4528.8   0.063       0  4576.2    0.16       0  4875.1   0.035       0
  5014.3   0.035       0  5018.6   0.035       0  5112.8    0.05       0
Bank Sta=5014.3,5018.6
Exp/Cntr=0.3,0.1

Type RM Length L Ch R = 1,1435,450,450,450
BEGIN DESCRIPTION:
Prairie Creek Trib A1434.62
END DESCRIPTION:
XS GIS Cut Line= 3
      2708501.44      6828349.06      2708508.72      6828673.88
      2708635.51      6829235.24
#Sta/Elev= 30
  4687.7  384.28  4809.7  382.60  4899.7  380.19  4919.7  378.94  4929.7  379.05
  4939.7  375.91  4989.7  377.32  4999.7  375.69  5006.5  372.57  5006.8  372.07
  5010.9  372.57  5012.6  372.57  5018.9  375.97  5024.0  372.78  5030.2  377.39
  5050.7  377.35  5067.2  378.30  5081.4  377.38  5101.9  377.45  5132.7  378.61
  5142.9  376.73  5207.0  376.22  5250.2  376.52  5255.7  377.33  5293.4  378.79
  5358.2  379.59  5519.7  379.90  5562.9  380.63  5573.5  381.53  5588.1  381.35
#Mann=3,-1,0
  4687.7    0.05       0  5006.5    0.05       0  5010.9    0.05       0
Bank Sta=5006.5,5010.9
Exp/Cntr=0.3,0.1

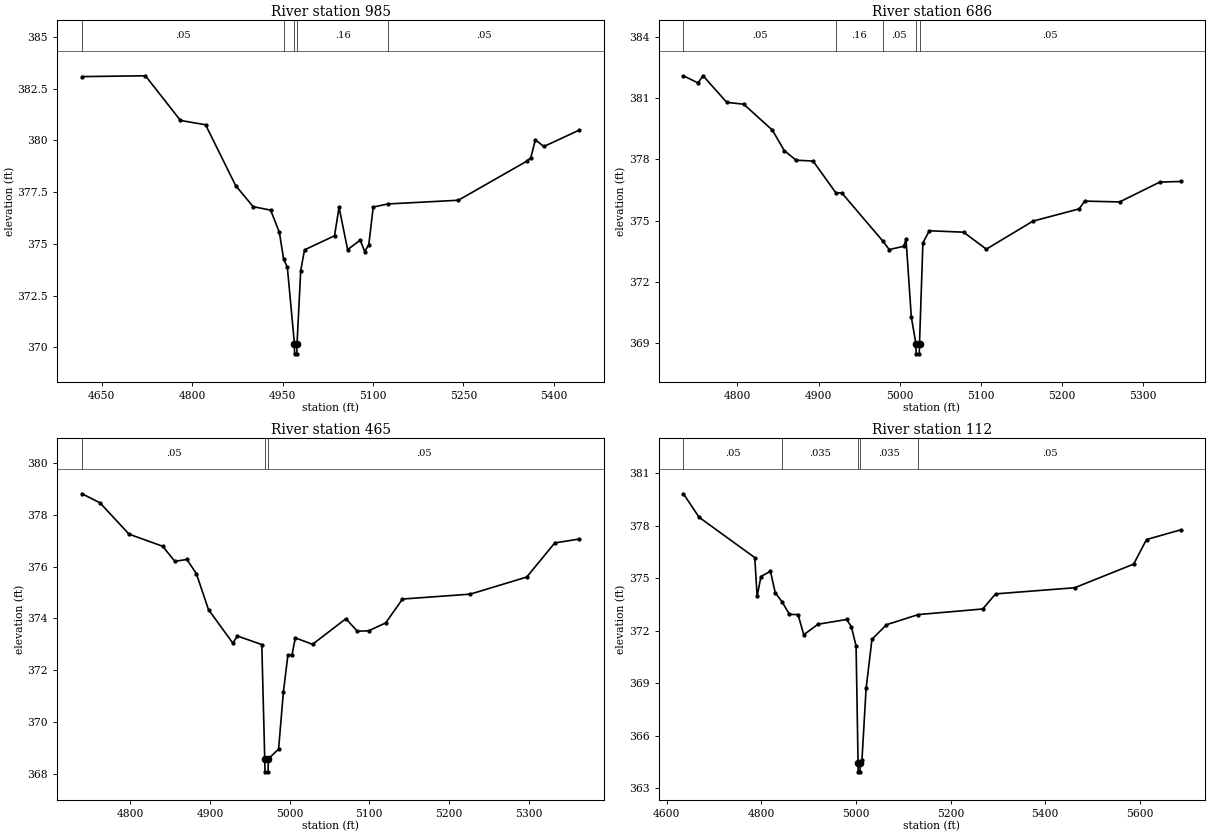
Type RM Length L Ch R = 1,985,299,299,299
BEGIN DESCRIPTION:
Prairie Creek Trib A984.96
END DESCRIPTION:
XS GIS Cut Line= 3
      2708038.99      6828650.16      2708270.87      6828954.19
      2708598.42      6829251.76
#Sta/Elev= 30
  4617.3  383.09  4722.4  383.13  4780.5  380.97  4822.2  380.76  4872.1  377.82
  4901.1  376.80  4930.2  376.63  4944.7  375.55  4951.6  374.28  4957.9  373.86
  4969.6  370.18  4969.9  369.68  4973.7  369.68  4974.0  370.18  4980.1  373.71
  4986.4  374.71  5036.2  375.39  5043.7  376.77  5057.9  374.72  5078.8  375.18
  5086.2  374.63  5093.0  374.95  5100.4  376.78  5124.8  376.93  5241.7  377.11
  5355.2  379.00  5361.9  379.17  5369.4  380.03  5383.6  379.71  5442.2  380.50
#Mann=5,-1,0
  4617.3    0.05       0  4951.6    0.16       0  4969.6    0.07       0
  4974.0    0.16       0  5124.8    0.05       0
Bank Sta=4969.6,4974
Exp/Cntr=0.3,0.1

Type RM Length L Ch R = 1,686,221,221,221
BEGIN DESCRIPTION:
Prairie Creek Trib A685.65
END DESCRIPTION:
XS GIS Cut Line= 3
      2707896.83      6828916.24      2708057.25      6829132.05
      2708275.87      6829397.51
#Sta/Elev= 30
  4733.4  382.08  4751.4  381.73  4757.6  382.08  4786.8  380.78  4807.7  380.69
  4843.1  379.42  4857.7  378.42  4872.3  377.95  4893.2  377.91  4921.2  376.36
  4928.6  376.35  4978.9  374.01  4987.1  373.58  5004.9  373.74  5007.8  374.08
  5014.3  370.29  5019.9  368.98  5020.3  368.48  5024.1  368.48  5024.4  368.98
  5028.6  373.91  5036.5  374.50  5078.7  374.43  5106.8  373.60  5164.2  374.97
  5221.2  375.57  5228.0  375.95  5271.1  375.91  5320.6  376.88  5346.2  376.91
#Mann=5,-1,0
  4733.4    0.05       0  4921.2    0.16       0  4978.9    0.05       0
  5019.9    0.05       0  5024.4    0.05       0
Bank Sta=5019.9,5024.4
Exp/Cntr=0.3,0.1

Type RM Length L Ch R = 1,465,353,353,353
BEGIN DESCRIPTION:
Prairie Creek Trib A465.18
END DESCRIPTION:
XS GIS Cut Line= 3
      2707806.99      6829070.05      2707947.11      6829289.73
      2708191.83      6829558.56
#Sta/Elev= 30
  4739.5  378.82  4762.0  378.47  4798.4  377.26  4840.7  376.79  4855.9  376.21
  4871.1  376.28  4883.0  375.73  4898.2  374.34  4928.7  373.05  4934.6  373.32
  4965.1  372.99  4968.8  368.57  4969.1  368.07  4973.0  368.07  4973.3  368.57
  4986.2  368.95  4992.2  371.15  4997.9  372.59  5003.0  372.59  5007.2  373.25
  5028.8  373.00  5070.7  373.99  5084.9  373.51  5099.1  373.52  5120.7  373.83
  5141.7  374.75  5226.8  374.94  5297.7  375.60  5332.9  376.92  5363.6  377.07
#Mann=3,-1,0
  4739.5    0.05       0  4968.8    0.05       0  4973.3    0.05       0
Bank Sta=4968.8,4973.3
Exp/Cntr=0.3,0.1

Type RM Length L Ch R = 1,112,0,0,0
BEGIN DESCRIPTION:
Prairie Creek Trib A112.06
END DESCRIPTION:
XS GIS Cut Line= 3
      2707677.52      6828948.10      2707638.06      6829310.96
      2708218.58      6829676.46
#Sta/Elev= 30
  4635.0  379.81  4668.1  378.47  4785.8  376.17  4790.8  373.96  4798.9  375.09
  4819.0  375.39  4829.0  374.17  4843.5  373.65  4859.2  372.93  4877.3  372.92
  4889.4  371.77  4919.6  372.37  4979.9  372.64  4990.0  372.23  5000.0  371.13
  5004.2  364.45  5004.5  363.95  5008.4  363.95  5008.7  364.45  5012.4  364.60
  5021.2  368.71  5033.6  371.51  5064.2  372.34  5131.4  372.92  5267.8  373.24
  5294.9  374.10  5462.1  374.45  5586.9  375.80  5614.0  377.20  5686.0  377.75
#Mann=5,-1,0
  4635.0    0.05       0  4843.5   0.035       0  5004.2   0.035       0
  5008.7   0.035       0  5131.4    0.05       0
Bank Sta=5004.2,5008.7
Exp/Cntr=0.3,0.1

Chan Stop Cuts=-1