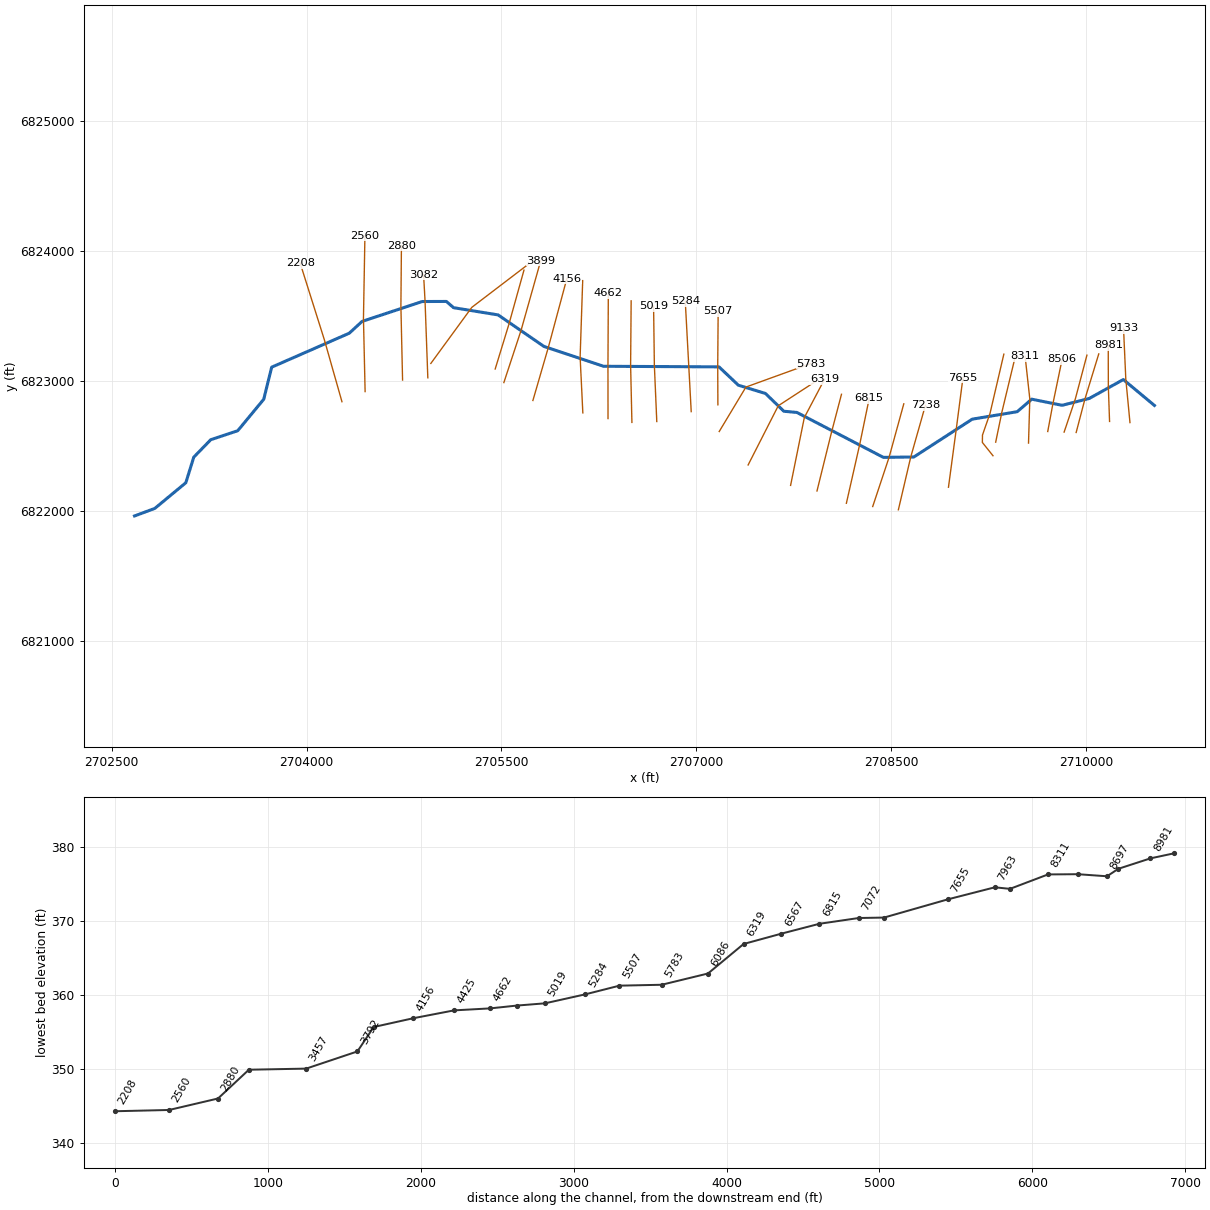
--- Prairie Creek Trib C.prj (project) ---

Proj Title=Prairie Creek Trib C Base Level Engineering
Current Plan=p01
Default Exp/Contr=0.3,0.1
English Units
Geom File=g01
Flow File=f01
Plan File=p01
BEGIN DESCRIPTION:
Prairie Creek Trib C
END DESCRIPTION:

--- Prairie Creek Trib C.p01 (plan) ---

Plan Title=Multiple Run
Short Identifier=Multiple
Geom File=g01
Flow File=f01
Subcritical Flow
K Sum by GR= 0
Std Step Tol= 0.01
Critical Tol= 0.01
Num of Std Step Trials= 20
Max Error Tol= 0.3
Flow Tol Ratio= 0.001
Split Flow NTrial= 30
Split Flow Tol= 0.02
Split Flow Ratio= 0.02
Log Output Level= 0
Friction Slope Method= 1
Unsteady Friction Slope Method= 2
Unsteady Bridges Friction Slope Method= 1
Parabolic Critical Depth
Global Vel Dist=  1 , 1 , 1
Global Log Level= 0
CheckData=True
Encroach Param= -1, 0, 0, 0
BEGIN DESCRIPTION:
Multiple Run
END DESCRIPTION:

--- Prairie Creek Trib C.f01 (steady flow) ---

Flow Title=Multiple
Number of Profiles=7
Profile Names=10-year,25-year,50-year,1pct_min,100-year,1pct_plu,500-year
River Rch & RM= Prairie Creek Tr,Reach-1,9133
     427     559     663     391     780    1556    1076
River Rch & RM= Prairie Creek Tr,Reach-1,7655
     553     734     879     522    1042    2080    1464
River Rch & RM= Prairie Creek Tr,Reach-1,5507
     637     854    1029     615    1227    2449    1744
River Rch & RM= Prairie Creek Tr,Reach-1,4425
     745    1006    1219     732    1461    2915    2096
River Rch & RM= Prairie Creek Tr,Reach-1,3082
    1103    1530    1885    1151    2296    4580    3404
River Rch & RM= Prairie Creek Tr,Reach-1,784
    1224    1707    2112    1294    2581    5150    3855
Boundary for River Rch & Prof#=Prairie Creek Tr,Reach-1,1
Up Type=0
Dn Type=3
Dn Slope=0.005
Boundary for River Rch & Prof#=Prairie Creek Tr,Reach-1,2
Up Type=0
Dn Type=3
Dn Slope=0.005
Boundary for River Rch & Prof#=Prairie Creek Tr,Reach-1,3
Up Type=0
Dn Type=3
Dn Slope=0.005
Boundary for River Rch & Prof#=Prairie Creek Tr,Reach-1,4
Up Type=0
Dn Type=3
Dn Slope=0.005
Boundary for River Rch & Prof#=Prairie Creek Tr,Reach-1,5
Up Type=0
Dn Type=3
Dn Slope=0.005
Boundary for River Rch & Prof#=Prairie Creek Tr,Reach-1,6
Up Type=0
Dn Type=3
Dn Slope=0.005
Boundary for River Rch & Prof#=Prairie Creek Tr,Reach-1,7
Up Type=0
Dn Type=3
Dn Slope=0.005

--- Prairie Creek Trib C.g01 (geometry) ---

Geom Title=Existing Conditions

River Reach=Prairie Creek Tr,Reach-1
Reach XY= 30
      2710526.00      6822811.00      2710286.70      6823010.30
      2710024.44      6822864.76      2709815.49      6822812.21
      2709581.63      6822859.26      2709470.14      6822763.07
      2709123.58      6822705.46      2708674.45      6822414.75
      2708439.91      6822411.67      2707774.41      6822757.17
      2707673.57      6822766.52      2707532.17      6822903.14
      2707323.68      6822966.79      2707174.64      6823107.71
      2706285.66      6823112.38      2705827.58      6823264.83
      2705474.50      6823507.38      2705131.37      6823563.00
      2705076.00      6823611.00      2704889.92      6823610.33
      2704427.50      6823457.38      2704328.42      6823366.54
      2703731.58      6823105.42      2703670.53      6822858.55
      2703470.39      6822616.59      2703262.70      6822547.60
      2703131.83      6822413.30      2703070.74      6822216.47
      2702832.06      6822019.13      2702676.00      6821961.00

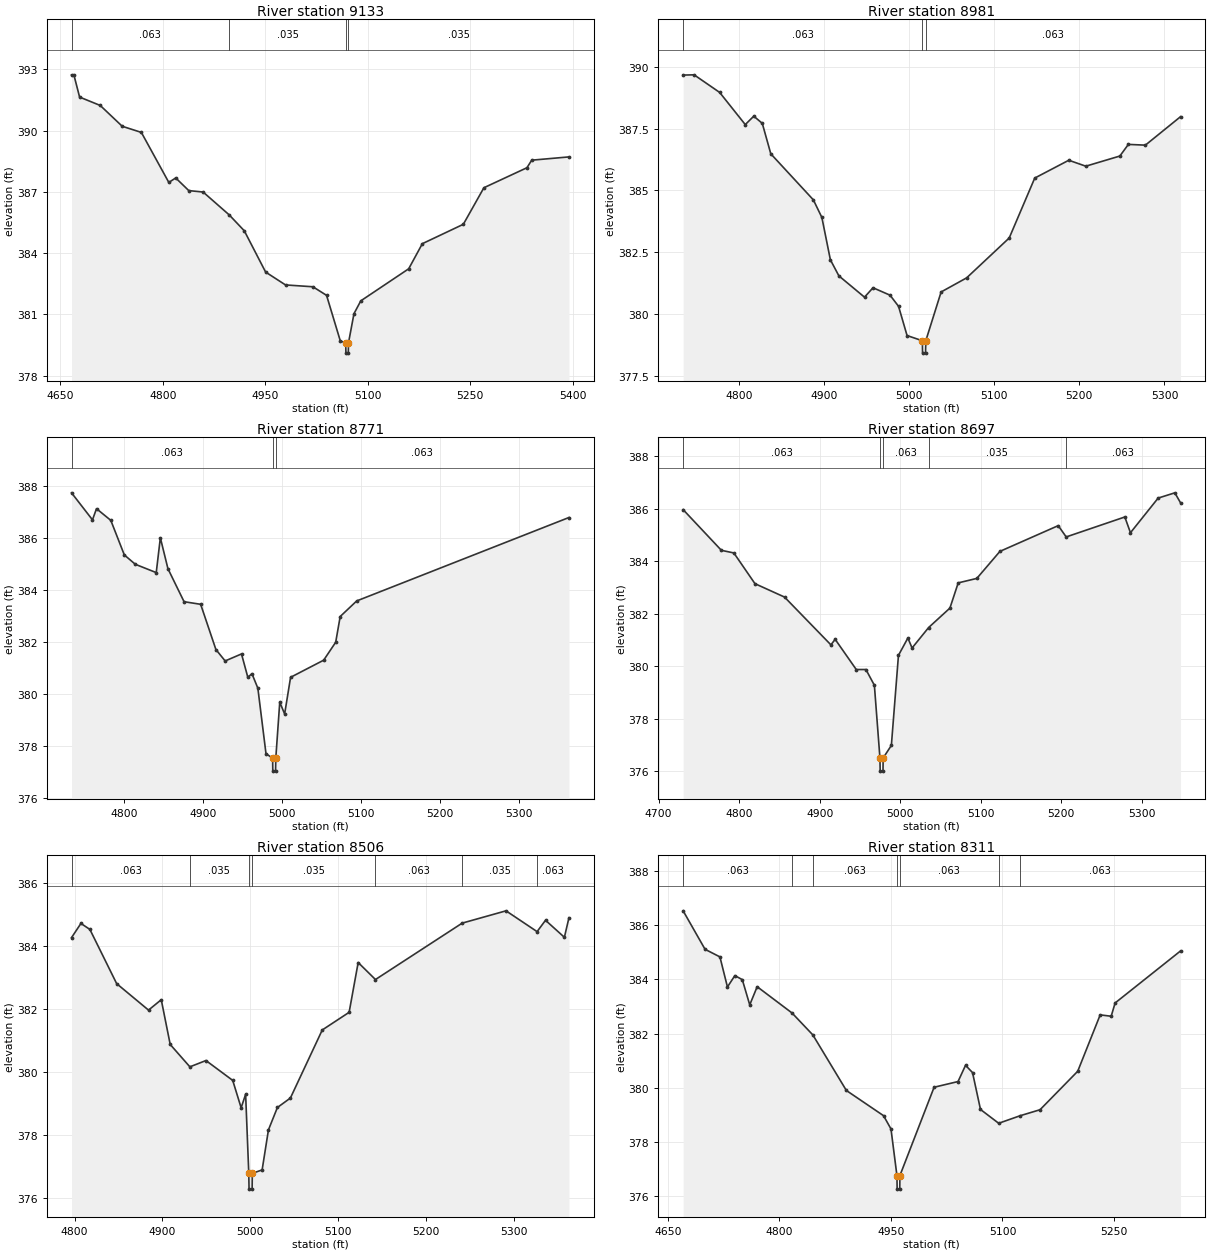
Type RM Length L Ch R = 1,9133,152,152,152
BEGIN DESCRIPTION:
Prairie Creek Trib C9133.235
END DESCRIPTION:
XS GIS Cut Line= 3
      2710337.82      6822679.24      2710305.87      6823011.41
      2710288.14      6823405.41
#Sta/Elev= 30
  4666.3  392.73  4669.7  392.73  4678.1  391.64  4708.3  391.23  4740.5  390.21
  4768.5  389.91  4808.7  387.46  4818.8  387.68  4837.9  387.06  4858.9  386.99
  4897.1  385.87  4919.2  385.09  4950.4  383.07  4979.5  382.44  5019.6  382.35
  5039.6  381.93  5059.7  379.70  5067.7  379.60  5067.9  379.10  5071.4  379.10
  5071.7  379.60  5079.7  381.03  5089.7  381.66  5159.8  383.23  5179.8  384.46
  5239.8  385.41  5269.9  387.20  5332.9  388.18  5339.9  388.55  5394.4  388.71
#Mann=4,-1,0
  4666.3   0.063       0  4897.1   0.035       0  5067.7   0.035       0
  5071.7   0.035       0
Bank Sta=5067.7,5071.7
Exp/Cntr=0.3,0.1

Type RM Length L Ch R = 1,8981,210,210,210
BEGIN DESCRIPTION:
Prairie Creek Trib C8981.34
END DESCRIPTION:
XS GIS Cut Line= 3
      2710180.72      6822688.08      2710171.24      6822958.00
      2710170.66      6823272.31
#Sta/Elev= 30
  4734.5  389.66  4747.4  389.67  4777.4  388.96  4807.5  387.66  4817.5  388.00
  4827.5  387.71  4837.5  386.48  4887.5  384.62  4897.5  383.91  4907.5  382.20
  4917.5  381.55  4947.6  380.69  4957.6  381.07  4977.6  380.77  4987.6  380.32
  4997.6  379.14  5015.6  378.93  5015.8  378.43  5019.3  378.43  5019.6  378.93
  5037.6  380.90  5067.6  381.47  5117.6  383.08  5147.6  385.50  5187.6  386.22
  5207.6  385.98  5247.6  386.39  5257.6  386.86  5277.6  386.83  5318.9  387.98
#Mann=3,-1,0
  4734.5   0.063       0  5015.6   0.063       0  5019.6   0.063       0
Bank Sta=5015.6,5019.6
Exp/Cntr=0.3,0.1

Type RM Length L Ch R = 1,8771,74,74,74
BEGIN DESCRIPTION:
Prairie Creek Trib C8771.09
END DESCRIPTION:
XS GIS Cut Line= 3
      2709923.61      6822602.96      2709991.55      6822861.67
      2710097.68      6823207.78
#Sta/Elev= 30
  4733.6  387.73  4760.1  386.69  4765.2  387.12  4783.3  386.67  4800.4  385.34
  4814.3  384.98  4840.8  384.66  4846.0  386.00  4855.6  384.81  4876.0  383.54
  4897.0  383.44  4916.3  381.70  4928.0  381.26  4948.7  381.53  4956.7  380.63
  4961.9  380.77  4969.4  380.21  4979.7  377.69  4988.1  377.52  4988.3  377.02
  4991.8  377.02  4992.1  377.52  4997.1  379.67  5003.3  379.22  5010.8  380.63
  5052.7  381.29  5067.9  381.98  5073.6  382.97  5094.5  383.57  5363.1  386.78
#Mann=3,-1,0
  4733.6   0.063       0  4988.1   0.063       0  4992.1   0.063       0
Bank Sta=4988.1,4992.1
Exp/Cntr=0.3,0.1

Type RM Length L Ch R = 1,8697,191,191,191
BEGIN DESCRIPTION:
Prairie Creek Trib C8697.08
END DESCRIPTION:
XS GIS Cut Line= 3
      2709830.92      6822606.00      2709917.67      6822862.58
      2710006.48      6823197.87
#Sta/Elev= 30
  4730.4  385.97  4777.9  384.42  4793.4  384.32  4819.6  383.15  4856.3  382.64
  4913.9  380.82  4919.2  381.03  4945.4  379.88  4957.4  379.88  4967.9  379.28
  4974.8  376.51  4975.1  376.01  4978.6  376.01  4978.8  376.51  4989.0  376.99
  4997.8  380.42  5009.5  381.08  5014.7  380.70  5035.3  381.48  5061.7  382.22
  5072.0  383.18  5095.1  383.35  5123.8  384.38  5196.2  385.36  5206.1  384.93
  5278.9  385.69  5285.9  385.09  5320.3  386.41  5341.0  386.61  5348.1  386.23
#Mann=5,-1,0
  4730.4   0.063       0  4974.8   0.063       0  4978.8   0.063       0
  5035.3   0.035       0  5206.1   0.063       0
Bank Sta=4974.8,4978.8
Exp/Cntr=0.3,0.1

Type RM Length L Ch R = 1,8506,195,195,195
BEGIN DESCRIPTION:
Prairie Creek Trib C8505.72
END DESCRIPTION:
XS GIS Cut Line= 3
      2709704.86      6822610.49      2709744.14      6822821.83
      2709815.59      6823166.14
#Sta/Elev= 30
  4796.5  384.27  4807.2  384.72  4817.4  384.53  4847.9  382.81  4884.2  381.97
  4898.7  382.30  4908.9  380.88  4931.3  380.17  4949.6  380.37  4980.1  379.74
  4989.7  378.87  4994.8  379.30  4998.4  376.79  4998.7  376.29  5002.2  376.29
  5002.4  376.79  5013.6  376.90  5020.8  378.17  5031.0  378.88  5045.8  379.18
  5082.1  381.34  5112.7  381.90  5123.0  383.48  5142.7  382.94  5241.5  384.73
  5291.4  385.12  5326.8  384.46  5336.4  384.82  5357.9  384.28  5363.1  384.90
#Mann=7,-1,0
  4796.5   0.063       0  4931.3   0.035       0  4998.4   0.035       0
  5002.4   0.035       0  5142.7   0.063       0  5241.5   0.035       0
  5326.8   0.063       0
Bank Sta=4998.4,5002.4
Exp/Cntr=0.3,0.1

Type RM Length L Ch R = 1,8311,249,249,249
BEGIN DESCRIPTION:
Prairie Creek Trib C8311.39
END DESCRIPTION:
XS GIS Cut Line= 3
      2709556.98      6822521.47      2709566.84      6822861.94
      2709530.72      6823188.44
#Sta/Elev= 30
  4670.4  386.53  4699.9  385.11  4719.9  384.83  4730.0  383.72  4740.0  384.14
  4750.0  383.99  4760.0  383.06  4770.0  383.73  4816.9  382.76  4844.9  381.95
  4890.0  379.90  4940.0  378.97  4950.0  378.48  4958.0  376.76  4958.3  376.26
  4961.8  376.26  4962.0  376.76  5008.0  380.02  5040.2  380.23  5050.3  380.83
  5059.7  380.56  5070.4  379.20  5094.9  378.69  5123.9  378.97  5150.5  379.19
  5201.2  380.61  5231.4  382.69  5246.2  382.64  5251.5  383.13  5339.5  385.05
#Mann=7,-1,0
  4670.4   0.063       0  4816.9   0.035       0  4844.9   0.063       0
  4958.0   0.063       0  4962.0   0.063       0  5094.9   0.035       0
  5123.9   0.063       0
Bank Sta=4958,4962
Exp/Cntr=0.3,0.1

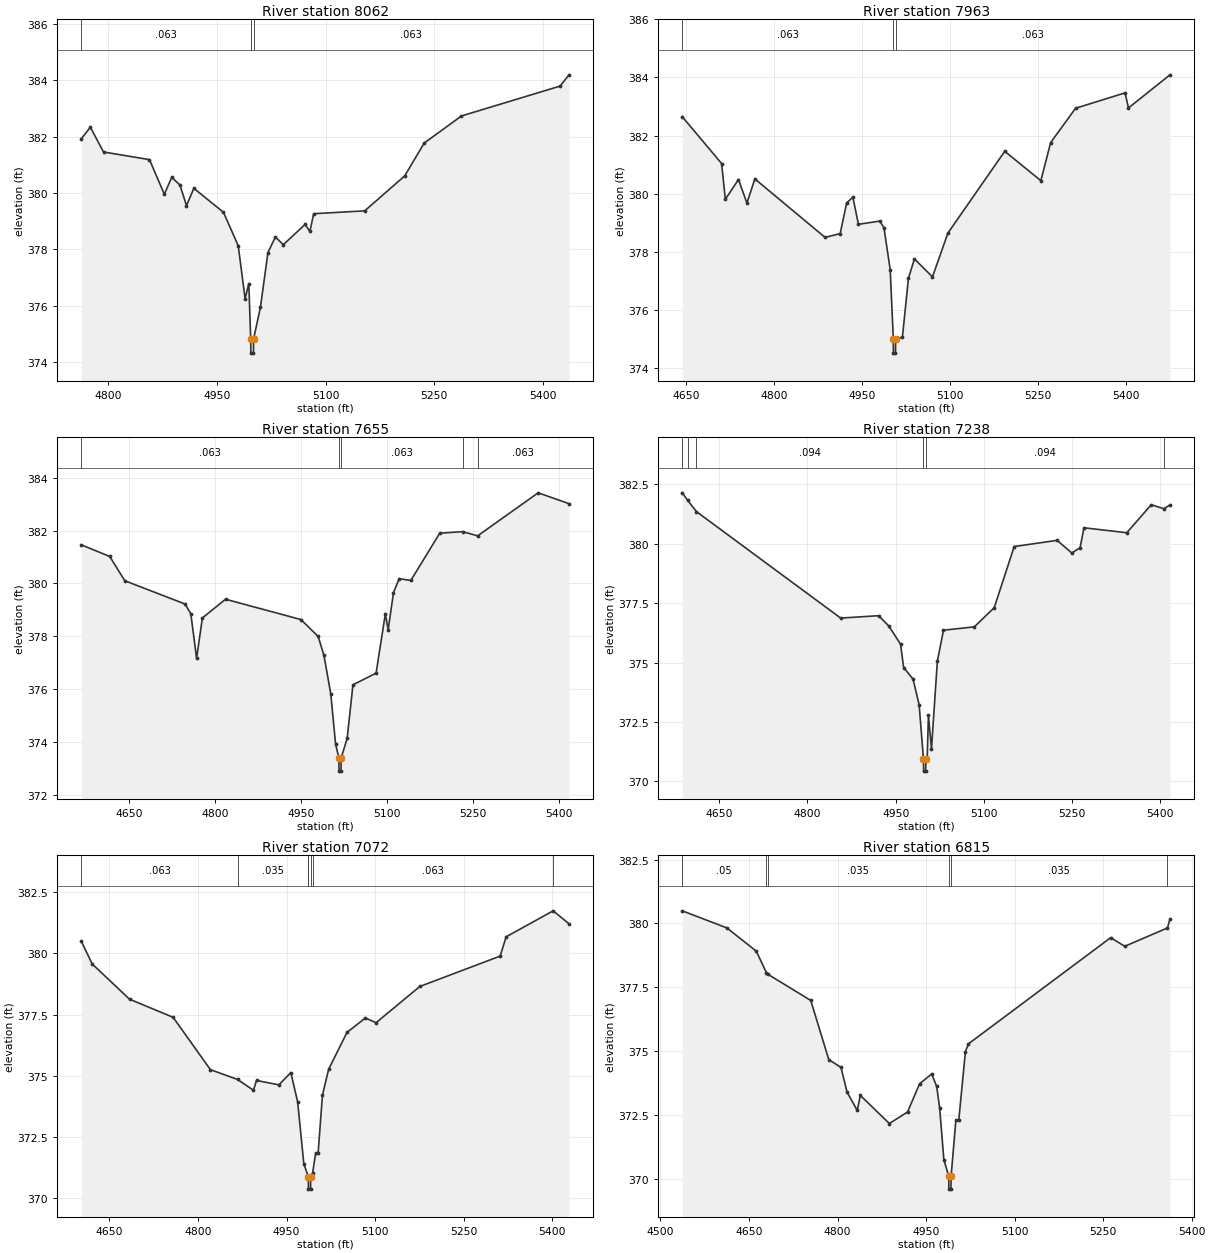
Type RM Length L Ch R = 1,8062,99,99,99
BEGIN DESCRIPTION:
Prairie Creek Trib C8062.18
END DESCRIPTION:
XS GIS Cut Line= 3
      2709304.20      6822528.71      2709352.85      6822763.62
      2709454.54      6823185.44
#Sta/Elev= 30
  4762.6  381.92  4775.1  382.33  4793.3  381.45  4856.8  381.18  4877.3  379.95
  4887.5  380.55  4898.8  380.28  4907.9  379.55  4918.1  380.16  4959.0  379.31
  4979.4  378.12  4988.9  376.24  4994.0  376.78  4996.6  374.81  4996.9  374.31
  5000.4  374.31  5000.6  374.81  5010.1  375.94  5020.4  377.88  5030.7  378.43
  5041.7  378.16  5071.8  378.88  5078.4  378.63  5083.6  379.26  5154.1  379.36
  5209.3  380.60  5236.4  381.77  5287.8  382.73  5424.0  383.79  5436.4  384.19
#Mann=3,-1,0
  4762.6   0.063       0  4996.6   0.063       0  5000.6   0.063       0
Bank Sta=4996.6,5000.6
Exp/Cntr=0.3,0.1

Type RM Length L Ch R = 1,7963,308,308,308
BEGIN DESCRIPTION:
Prairie Creek Trib C7962.72
END DESCRIPTION:
XS GIS Cut Line= 5
      2709283.46      6822424.31      2709201.73      6822526.39
      2709202.63      6822583.55      2709260.56      6822749.83
      2709367.01      6823205.55
#Sta/Elev= 30
  4643.3  382.65  4710.4  381.04  4716.8  379.81  4739.2  380.49  4753.6  379.68
  4767.2  380.51  4886.9  378.50  4912.7  378.63  4923.8  379.69  4934.4  379.88
  4943.8  378.95  4980.2  379.06  4987.4  378.83  4998.0  377.39  5003.3  375.02
  5003.5  374.52  5007.0  374.52  5007.3  375.02  5018.8  375.06  5029.1  377.09
  5039.3  377.76  5070.1  377.14  5096.5  378.65  5193.4  381.46  5255.0  380.45
  5271.7  381.76  5314.2  382.94  5398.7  383.47  5404.4  382.95  5475.3  384.09
#Mann=3,-1,0
  4643.3   0.063       0  5003.3   0.063       0  5007.3   0.063       0
Bank Sta=5003.3,5007.3
Exp/Cntr=0.3,0.1

Type RM Length L Ch R = 1,7655,417,417,417
BEGIN DESCRIPTION:
Prairie Creek Trib C7655.16
END DESCRIPTION:
XS GIS Cut Line= 3
      2708940.78      6822181.92      2708998.56      6822612.75
      2709052.36      6823024.37
#Sta/Elev= 30
  4567.4  381.46  4616.9  381.02  4643.2  380.10  4748.1  379.22  4758.2  378.85
  4768.3  377.16  4778.3  378.69  4818.7  379.40  4950.1  378.63  4980.1  377.99
  4990.2  377.27  5002.1  375.81  5010.4  373.92  5016.2  373.39  5016.4  372.89
  5019.9  372.89  5020.2  373.39  5030.6  374.13  5040.7  376.16  5081.0  376.60
  5097.1  378.84  5102.1  378.25  5111.3  379.65  5121.3  380.18  5141.5  380.11
  5191.9  381.90  5232.0  381.96  5257.9  381.80  5363.4  383.43  5417.2  383.02
#Mann=5,-1,0
  4567.4   0.063       0  5016.2   0.063       0  5020.2   0.063       0
  5232.0   0.094       0  5257.9   0.063       0
Bank Sta=5016.2,5020.2
Exp/Cntr=0.3,0.1

Type RM Length L Ch R = 1,7238,166,166,166
BEGIN DESCRIPTION:
Prairie Creek Trib C7238.34
END DESCRIPTION:
XS GIS Cut Line= 3
      2708555.23      6822008.64      2708650.33      6822414.31
      2708763.25      6822811.71
#Sta/Elev= 30
  4587.0  382.14  4596.1  381.83  4611.1  381.35  4856.5  376.87  4921.1  376.97
  4938.6  376.53  4958.4  375.77  4963.6  374.79  4979.7  374.30  4990.0  373.22
  4997.4  370.93  4997.6  370.43  5001.1  370.43  5001.4  370.93  5003.7  370.93
  5005.8  372.78  5011.0  371.37  5021.0  375.05  5031.4  376.36  5083.9  376.50
  5117.8  377.31  5151.7  379.88  5224.7  380.14  5249.7  379.61  5263.8  379.83
  5270.5  380.67  5343.3  380.46  5384.9  381.64  5406.4  381.47  5416.8  381.63
#Mann=6,-1,0
  4587.0   0.094       0  4596.1   0.063       0  4611.1   0.094       0
  4997.4    0.07       0  5001.4   0.094       0  5406.4   0.125       0
Bank Sta=4997.4,5001.4
Exp/Cntr=0.3,0.1

Type RM Length L Ch R = 1,7072,257,257,257
BEGIN DESCRIPTION:
Prairie Creek Trib C7071.97
END DESCRIPTION:
XS GIS Cut Line= 3
      2708357.69      6822033.56      2708484.24      6822413.98
      2708596.90      6822823.55
#Sta/Elev= 30
  4602.6  380.50  4621.0  379.57  4684.2  378.13  4758.0  377.39  4821.2  375.25
  4867.2  374.85  4894.0  374.41  4899.2  374.81  4937.1  374.63  4957.3  375.13
  4968.8  373.94  4979.3  371.41  4986.5  370.90  4986.9  370.87  4987.2  370.37
  4990.7  370.37  4990.9  370.87  4994.2  371.03  4999.3  371.84  5003.5  371.84
  5010.8  374.20  5021.2  375.26  5052.3  376.77  5083.4  377.36  5101.7  377.17
  5175.7  378.65  5311.6  379.89  5321.9  380.68  5401.4  381.74  5428.3  381.21
#Mann=7,-1,0
  4602.6   0.063       0  4867.2   0.035       0  4986.5   0.094       0
  4986.9   0.063       0  4990.9   0.094       0  4994.2   0.063       0
  5401.4   0.125       0
Bank Sta=4986.9,4990.9
Exp/Cntr=0.3,0.1

Type RM Length L Ch R = 1,6815,248,248,248
BEGIN DESCRIPTION:
Prairie Creek Trib C6814.75
END DESCRIPTION:
XS GIS Cut Line= 3
      2708155.06      6822058.72      2708258.55      6822515.68
      2708330.97      6822866.15
#Sta/Elev= 30
  4536.9  380.49  4612.6  379.82  4662.3  378.91  4679.4  378.07  4682.4  378.00
  4754.6  376.98  4785.2  374.66  4805.8  374.36  4816.1  373.39  4833.4  372.67
  4838.6  373.26  4887.8  372.16  4918.6  372.61  4939.1  373.72  4959.6  374.10
  4968.0  373.61  4973.1  372.75  4980.1  370.75  4988.4  370.09  4988.6  369.59
  4992.1  369.59  4992.4  370.09  5000.5  372.29  5005.4  372.29  5016.7  374.98
  5021.8  375.28  5262.8  379.44  5286.6  379.10  5359.0  379.82  5363.3  380.17
#Mann=6,-1,0
  4536.9    0.05       0  4679.4   0.063       0  4682.4   0.035       0
  4988.4   0.035       0  4992.4   0.035       0  5359.0   0.125       0
Bank Sta=4988.4,4992.4
Exp/Cntr=0.3,0.1

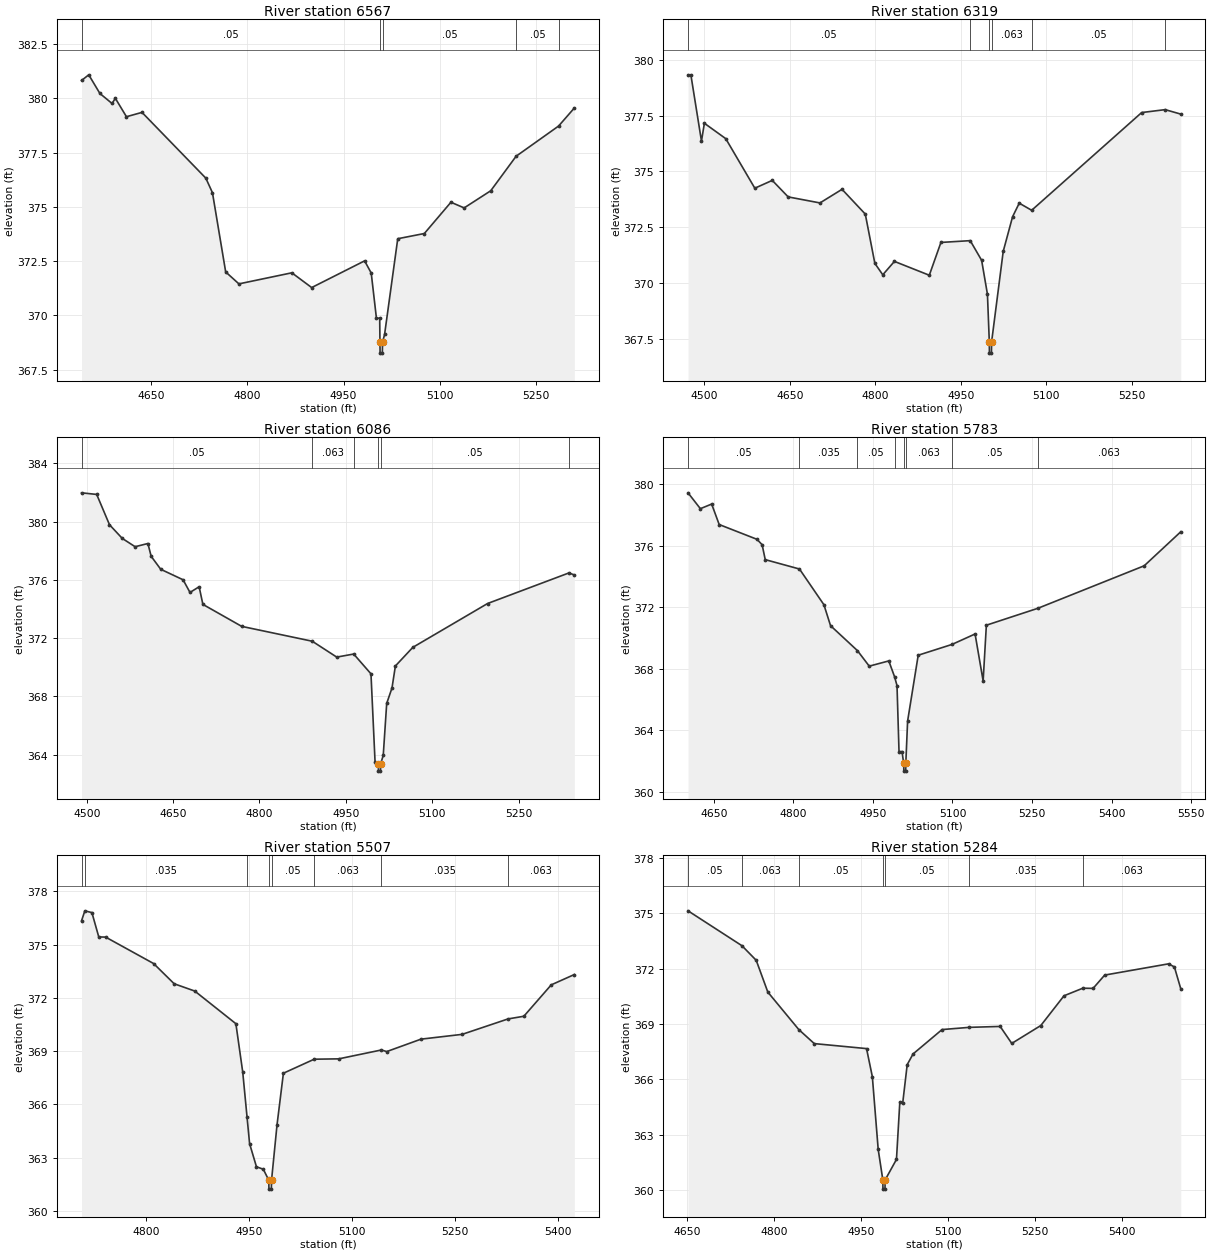
Type RM Length L Ch R = 1,6567,248,248,248
BEGIN DESCRIPTION:
Prairie Creek Trib C6567.45
END DESCRIPTION:
XS GIS Cut Line= 3
      2707928.77      6822153.20      2708039.79      6822601.61
      2708117.31      6822896.85
#Sta/Elev= 30
  4542.0  380.82  4553.2  381.08  4570.6  380.22  4589.5  379.76  4594.6  380.00
  4611.9  379.15  4636.1  379.35  4735.5  376.32  4745.8  375.65  4766.4  372.00
  4787.0  371.45  4869.4  371.96  4900.3  371.28  4982.7  372.51  4993.0  371.95
  5001.1  369.87  5006.2  369.87  5006.6  368.76  5006.8  368.26  5010.3  368.26
  5010.6  368.76  5013.8  369.12  5034.3  373.53  5075.7  373.77  5117.1  375.21
  5137.7  374.95  5179.1  375.74  5218.6  377.33  5284.7  378.72  5309.2  379.55
#Mann=5,-1,0
  4542.0    0.05       0  5006.6    0.05       0  5010.6    0.05       0
  5218.6    0.05       0  5284.7   0.035       0
Bank Sta=5006.6,5010.6
Exp/Cntr=0.3,0.1

Type RM Length L Ch R = 1,6319,233,233,233
BEGIN DESCRIPTION:
Prairie Creek Trib C6319.39
END DESCRIPTION:
XS GIS Cut Line= 3
      2707725.67      6822196.14      2707831.36      6822718.08
      2707986.33      6823011.65
#Sta/Elev= 30
  4471.4  379.33  4476.4  379.33  4495.0  376.36  4500.1  377.16  4537.6  376.47
  4588.6  374.25  4619.2  374.60  4647.1  373.86  4702.9  373.59  4741.6  374.20
  4782.4  373.09  4799.2  370.88  4813.1  370.37  4833.5  370.97  4894.7  370.35
  4915.1  371.82  4966.5  371.90  4986.5  371.02  4996.7  369.50  5000.0  367.36
  5000.2  366.86  5003.7  366.86  5004.0  367.36  5024.4  371.42  5040.8  372.97
  5052.5  373.58  5074.3  373.26  5267.3  377.64  5308.5  377.77  5335.9  377.57
#Mann=6,-1,0
  4471.4    0.05       0  4966.5   0.063       0  5000.0   0.063       0
  5004.0   0.063       0  5074.3    0.05       0  5308.5   0.063       0
Bank Sta=5000,5004
Exp/Cntr=0.3,0.1

Type RM Length L Ch R = 1,6086,303,303,303
BEGIN DESCRIPTION:
Prairie Creek Trib C6086.48
END DESCRIPTION:
XS GIS Cut Line= 3
      2707398.74      6822353.24      2707630.87      6822808.75
      2707919.60      6822996.58
#Sta/Elev= 30
  4491.0  381.98  4517.3  381.87  4539.5  379.79  4561.7  378.85  4584.0  378.28
  4606.2  378.50  4611.9  377.62  4628.5  376.73  4667.3  376.01  4679.3  375.14
  4695.2  375.53  4701.7  374.32  4769.1  372.81  4891.6  371.79  4934.1  370.70
  4963.6  370.91  4993.6  369.55  5000.7  363.49  5006.4  363.37  5006.6  362.87
  5010.1  362.87  5010.4  363.37  5014.9  363.95  5020.9  367.52  5030.1  368.58
  5036.0  370.09  5066.3  371.37  5196.1  374.38  5337.4  376.48  5346.7  376.34
#Mann=6,-1,0
  4491.0    0.05       0  4891.6   0.063       0  4963.6    0.05       0
  5006.4    0.05       0  5010.4    0.05       0  5337.4   0.063       0
Bank Sta=5006.4,5010.4
Exp/Cntr=0.3,0.1

Type RM Length L Ch R = 1,5783,276,276,276
BEGIN DESCRIPTION:
Prairie Creek Trib C5783.192
END DESCRIPTION:
XS GIS Cut Line= 3
      2707176.27      6822610.59      2707381.92      6822952.52
      2707880.92      6823133.18
#Sta/Elev= 30
  4601.0  379.43  4624.3  378.40  4645.6  378.70  4659.8  377.37  4731.1  376.41
  4740.8  376.06  4746.7  375.09  4811.3  374.48  4857.4  372.16  4869.9  370.80
  4920.6  369.18  4942.9  368.17  4979.8  368.51  4990.6  367.49  4995.3  366.91
  4999.1  362.62  5004.8  362.62  5007.9  361.85  5008.2  361.35  5011.7  361.35
  5011.9  361.85  5015.3  364.60  5035.3  368.88  5099.0  369.58  5142.6  370.26
  5157.8  367.21  5163.9  370.83  5261.2  371.93  5461.7  374.69  5530.7  376.90
#Mann=8,-1,0
  4601.0    0.05       0  4811.3   0.035       0  4920.6    0.05       0
  4990.6   0.063       0  5007.9   0.063       0  5011.9   0.063       0
  5099.0    0.05       0  5261.2   0.063       0
Bank Sta=5007.9,5011.9
Exp/Cntr=0.3,0.1

Type RM Length L Ch R = 1,5507,223,223,223
BEGIN DESCRIPTION:
Prairie Creek Trib C5506.62
END DESCRIPTION:
XS GIS Cut Line= 3
      2707166.06      6822815.94      2707164.77      6823114.60
      2707168.07      6823534.63
#Sta/Elev= 30
  4705.8  376.35  4710.6  376.91  4720.9  376.81  4730.9  375.44  4740.9  375.43
  4810.9  373.94  4840.9  372.80  4870.9  372.39  4930.9  370.55  4940.9  367.82
  4947.2  365.28  4950.9  363.79  4960.9  362.49  4970.9  362.35  4978.9  361.73
  4979.1  361.23  4982.6  361.23  4982.9  361.73  4990.9  364.85  5000.2  367.76
  5045.1  368.55  5080.9  368.57  5143.1  369.07  5150.9  368.98  5200.9  369.68
  5260.9  369.95  5327.9  370.82  5350.9  370.97  5390.9  372.74  5424.5  373.32
#Mann=8,-1,0
  4705.8    0.05       0  4710.6   0.035       0  4947.2    0.05       0
  4978.9    0.05       0  4982.9    0.05       0  5045.1   0.063       0
  5143.1   0.035       0  5327.9   0.063       0
Bank Sta=4978.9,4982.9
Exp/Cntr=0.3,0.1

Type RM Length L Ch R = 1,5284,265,265,265
BEGIN DESCRIPTION:
Prairie Creek Trib C5283.83
END DESCRIPTION:
XS GIS Cut Line= 3
      2706960.74      6822763.61      2706941.63      6823119.05
      2706914.97      6823611.98
#Sta/Elev= 30
  4652.1  375.13  4745.1  373.24  4769.7  372.45  4789.7  370.73  4843.1  368.70
  4869.8  367.94  4959.9  367.67  4969.9  366.15  4980.0  362.21  4988.0  360.56
  4988.2  360.06  4991.7  360.06  4992.0  360.56  5011.5  361.67  5017.3  364.78
  5022.3  364.73  5030.0  366.80  5040.1  367.38  5090.1  368.70  5136.9  368.82
  5190.3  368.87  5210.3  367.95  5260.4  368.92  5300.4  370.53  5332.8  370.94
  5350.5  370.93  5370.5  371.65  5480.7  372.26  5490.7  372.09  5501.7  370.91
#Mann=7,-1,0
  4652.1    0.05       0  4745.1   0.063       0  4843.1    0.05       0
  4988.0    0.05       0  4992.0    0.05       0  5136.9   0.035       0
  5332.8   0.063       0
Bank Sta=4988,4992
Exp/Cntr=0.3,0.1

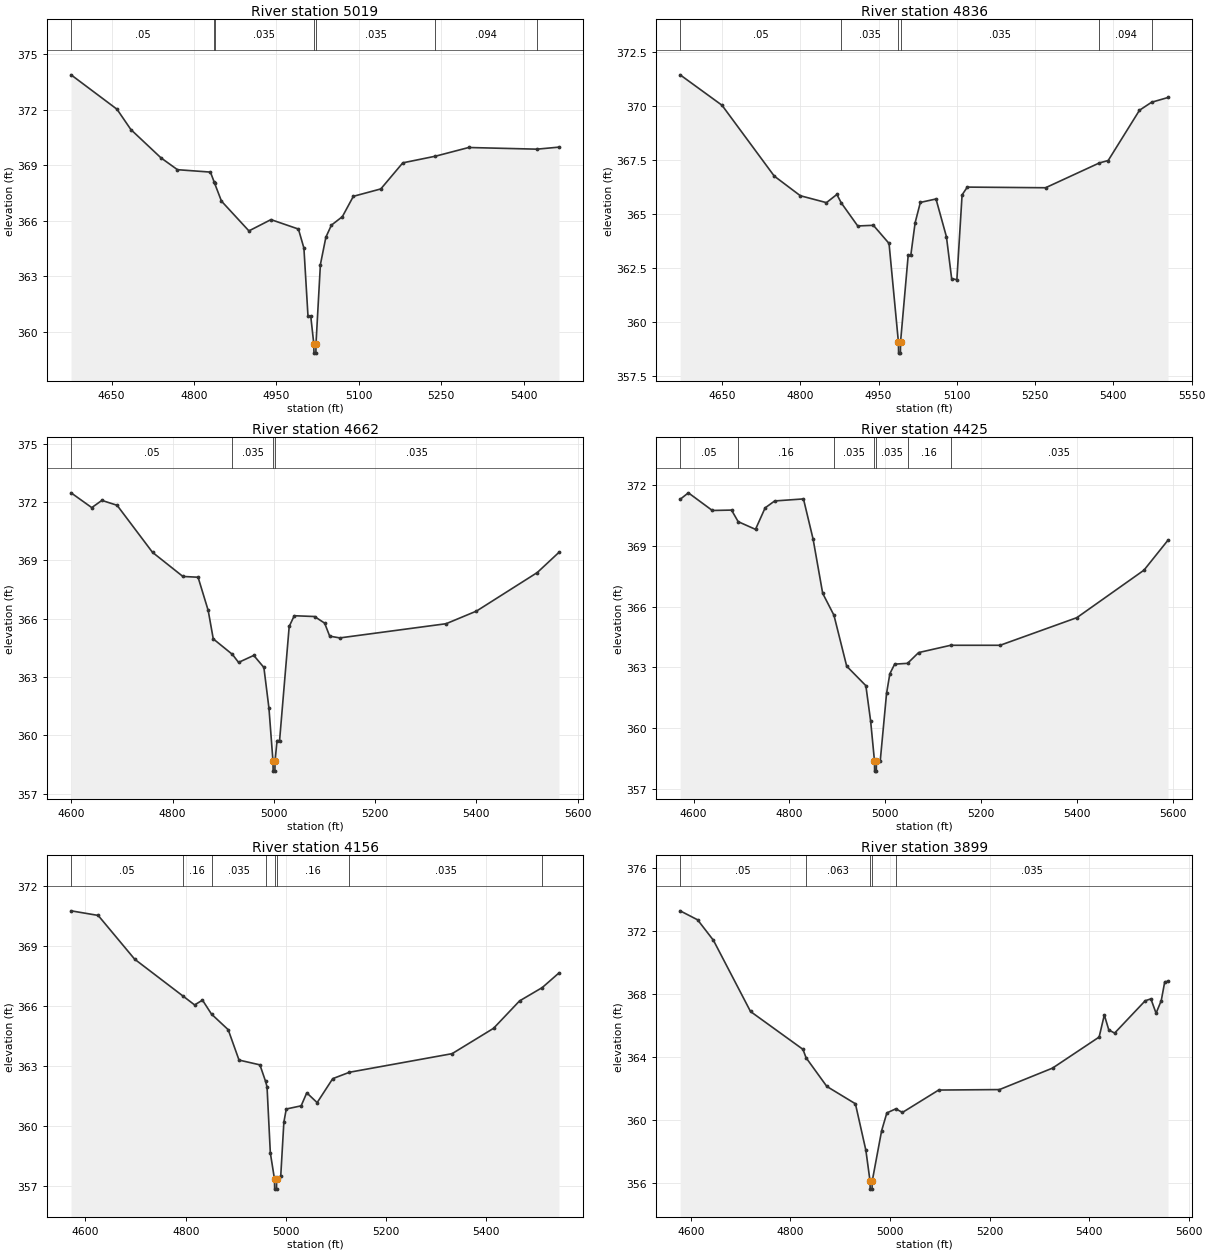
Type RM Length L Ch R = 1,5019,183,183,183
BEGIN DESCRIPTION:
Prairie Creek Trib C5019.22
END DESCRIPTION:
XS GIS Cut Line= 3
      2706695.70      6822687.49      2706677.02      6823120.82
      2706671.09      6823575.25
#Sta/Elev= 30
  4576.1  373.89  4659.7  372.03  4685.0  370.93  4739.8  369.40  4769.8  368.76
  4829.8  368.63  4836.8  368.08  4837.4  368.03  4849.9  367.06  4899.9  365.45
  4940.0  366.06  4990.0  365.55  5000.0  364.52  5007.4  360.85  5012.4  360.85
  5018.0  359.34  5018.3  358.84  5021.8  358.84  5022.0  359.34  5030.0  363.63
  5040.0  365.11  5050.0  365.76  5070.0  366.22  5090.0  367.32  5140.0  367.72
  5180.0  369.13  5239.5  369.49  5300.0  369.96  5424.2  369.87  5464.3  369.98
#Mann=7,-1,0
  4576.1    0.05       0  4836.8   0.063       0  4837.4   0.035       0
  5018.0   0.035       0  5022.0   0.035       0  5239.5   0.094       0
  5424.2   0.035       0
Bank Sta=5018,5022
Exp/Cntr=0.3,0.1

Type RM Length L Ch R = 1,4836,174,174,174
BEGIN DESCRIPTION:
Prairie Creek Trib C4836.26
END DESCRIPTION:
XS GIS Cut Line= 3
      2706504.28      6822680.69      2706494.29      6823119.43
      2706498.43      6823615.66
#Sta/Elev= 30
  4569.6  371.43  4649.9  370.02  4750.0  366.74  4800.0  365.83  4850.0  365.51
  4870.0  365.89  4878.4  365.50  4910.0  364.43  4940.0  364.46  4970.0  363.62
  4988.0  359.04  4988.3  358.54  4991.8  358.54  4992.0  359.04  5006.7  363.07
  5011.7  363.07  5020.0  364.58  5030.0  365.52  5060.0  365.68  5080.0  363.93
  5090.0  361.99  5100.0  361.94  5110.0  365.87  5120.0  366.23  5270.0  366.20
  5373.2  367.35  5390.0  367.46  5450.0  369.79  5473.2  370.16  5504.7  370.38
#Mann=6,-1,0
  4569.6    0.05       0  4878.4   0.035       0  4988.0   0.035       0
  4992.0   0.035       0  5373.2   0.094       0  5473.2   0.063       0
Bank Sta=4988,4992
Exp/Cntr=0.3,0.1

Type RM Length L Ch R = 1,4662,237,237,237
BEGIN DESCRIPTION:
Prairie Creek Trib C4661.71
END DESCRIPTION:
XS GIS Cut Line= 3
      2706320.38      6822710.06      2706319.92      6823117.88
      2706322.71      6823673.86
#Sta/Elev= 30
  4599.5  372.47  4640.4  371.71  4660.4  372.08  4690.4  371.83  4760.4  369.41
  4820.4  368.17  4850.4  368.13  4870.4  366.42  4880.4  364.96  4918.3  364.16
  4930.4  363.75  4960.4  364.11  4980.4  363.49  4990.4  361.40  4998.4  358.66
  4998.7  358.16  5002.2  358.16  5002.4  358.66  5006.4  359.73  5011.4  359.73
  5030.4  365.60  5040.4  366.15  5080.4  366.11  5100.4  365.77  5110.4  365.10
  5130.4  365.01  5340.4  365.74  5400.4  366.39  5520.4  368.37  5563.3  369.41
#Mann=4,-1,0
  4599.5    0.05       0  4918.3   0.035       0  4998.4   0.035       0
  5002.4   0.035       0
Bank Sta=4998.4,5002.4
Exp/Cntr=0.3,0.1

Type RM Length L Ch R = 1,4425,269,269,269
BEGIN DESCRIPTION:
Prairie Creek Trib C4425.42
END DESCRIPTION:
XS GIS Cut Line= 3
      2706126.52      6822753.85      2706105.71      6823184.19
      2706125.42      6823771.22
#Sta/Elev= 30
  4572.0  371.28  4589.2  371.60  4639.2  370.73  4679.3  370.75  4693.1  370.18
  4729.3  369.80  4749.4  370.86  4769.4  371.20  4829.4  371.30  4849.5  369.32
  4869.5  366.65  4893.0  365.57  4919.6  363.06  4959.6  362.10  4969.6  360.35
  4977.6  358.39  4977.9  357.89  4981.4  357.89  4981.6  358.39  4989.6  358.39
  5002.8  361.72  5009.7  362.69  5019.7  363.16  5046.6  363.20  5069.7  363.73
  5136.7  364.09  5239.8  364.09  5399.9  365.45  5540.0  367.79  5590.2  369.27
#Mann=7,-1,0
  4572.0    0.05       0  4693.1    0.16       0  4893.0   0.035       0
  4977.6   0.035       0  4981.6   0.035       0  5046.6    0.16       0
  5136.7   0.035       0
Bank Sta=4977.6,4981.6
Exp/Cntr=0.3,0.1

Type RM Length L Ch R = 1,4156,257,257,257
BEGIN DESCRIPTION:
Prairie Creek Trib C4155.62
END DESCRIPTION:
XS GIS Cut Line= 3
      2705742.21      6822849.10      2705863.18      6823265.26
      2706003.53      6823787.03
#Sta/Elev= 30
  4571.2  370.75  4625.3  370.52  4698.1  368.33  4794.8  366.48  4817.8  366.04
  4833.5  366.28  4851.5  365.58  4884.8  364.80  4906.4  363.28  4948.1  363.04
  4959.3  362.22  4962.3  361.94  4968.9  358.63  4977.2  357.32  4977.5  356.82
  4981.2  356.82  4981.5  357.32  4989.7  357.49  4995.9  360.17  5000.7  360.83
  5030.4  360.99  5041.6  361.64  5062.3  361.15  5093.4  362.35  5126.8  362.67
  5331.6  363.60  5414.4  364.87  5466.2  366.24  5511.6  366.91  5544.9  367.64
#Mann=8,-1,0
  4571.2    0.05       0  4794.8    0.16       0  4851.5   0.035       0
  4959.3    0.16       0  4977.2    0.07       0  4981.5    0.16       0
  5126.8   0.035       0  5511.6   0.063       0
Bank Sta=4977.2,4981.5
Exp/Cntr=0.3,0.1

Type RM Length L Ch R = 1,3899,107,107,107
BEGIN DESCRIPTION:
Prairie Creek Trib C3899.31
END DESCRIPTION:
XS GIS Cut Line= 3
      2705518.60      6822986.85      2705650.94      6823388.15
      2705802.28      6823924.13
#Sta/Elev= 30
  4578.8  373.28  4613.9  372.71  4645.7  371.41  4720.1  366.90  4825.4  364.50
  4831.6  363.97  4873.3  362.15  4930.7  361.05  4951.7  358.10  4960.1  356.14
  4960.3  355.64  4964.1  355.64  4964.4  356.14  4983.3  359.34  4993.8  360.47
  5011.8  360.73  5025.1  360.50  5097.8  361.92  5219.9  361.95  5326.4  363.31
  5420.0  365.28  5430.4  366.68  5439.4  365.73  5451.1  365.53  5512.5  367.58
  5523.9  367.70  5534.3  366.79  5544.7  367.59  5551.7  368.78  5558.3  368.81
#Mann=5,-1,0
  4578.8    0.05       0  4831.6   0.063       0  4960.1   0.063       0
  4964.4   0.063       0  5011.8   0.035       0
Bank Sta=4960.1,4964.4
Exp/Cntr=0.3,0.1

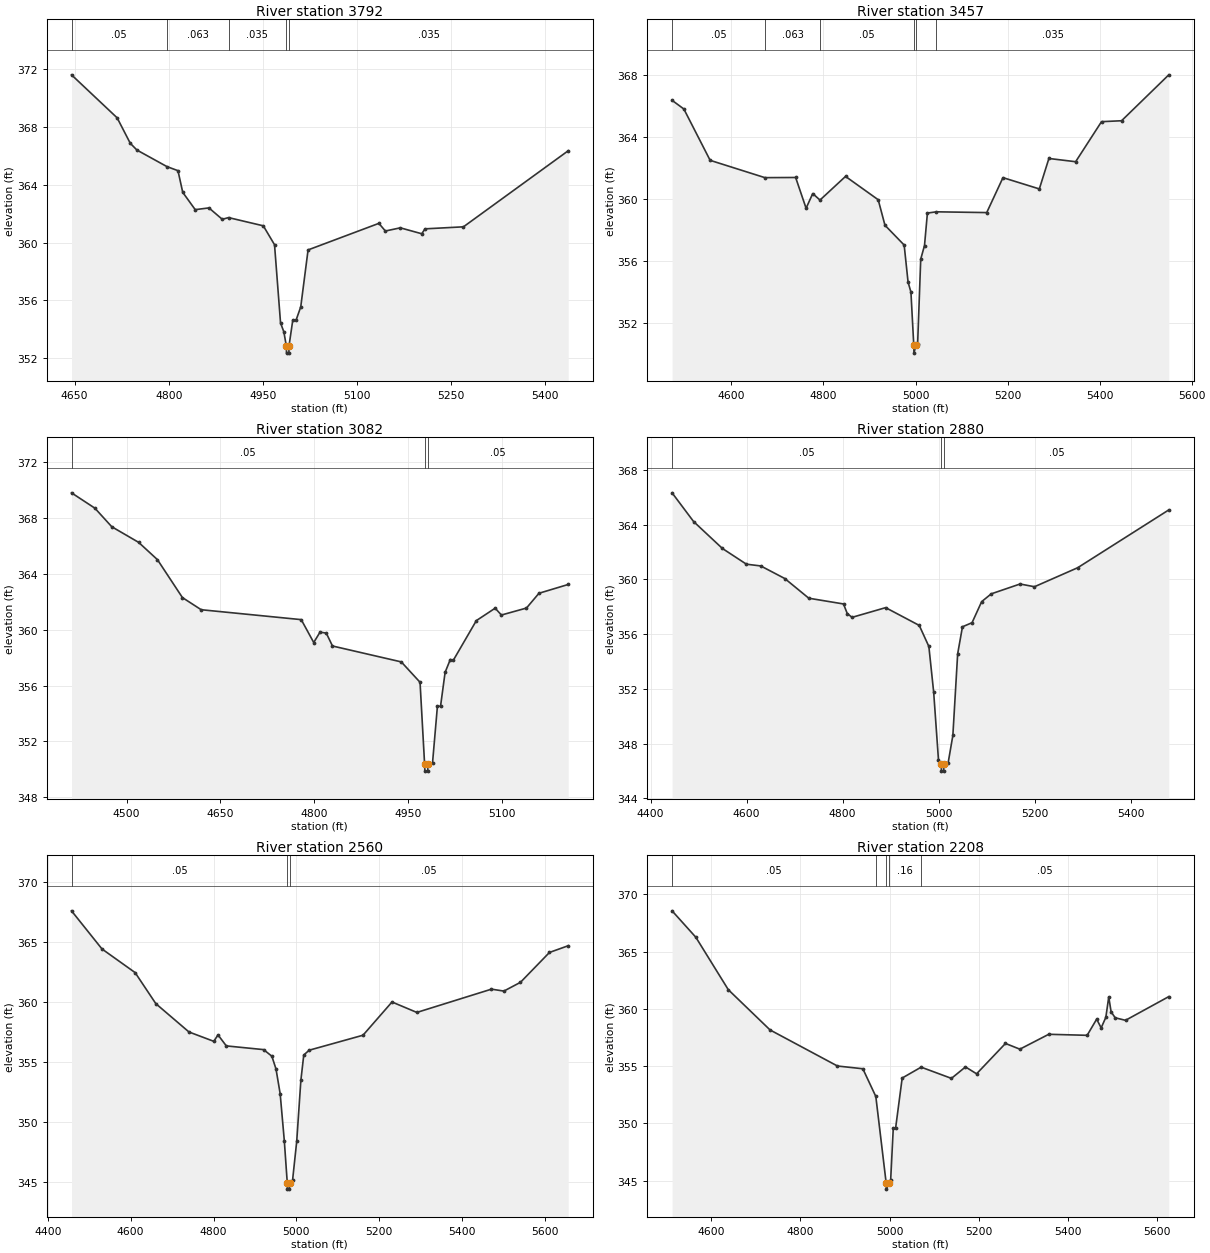
Type RM Length L Ch R = 1,3792,335,335,335
BEGIN DESCRIPTION:
Prairie Creek Trib C3791.64
END DESCRIPTION:
XS GIS Cut Line= 3
      2705451.92      6823091.40      2705556.26      6823431.46
      2705673.47      6823851.92
#Sta/Elev= 30
  4645.0  371.62  4717.8  368.64  4738.7  366.88  4749.3  366.41  4797.3  365.26
  4814.8  364.98  4822.4  363.48  4842.3  362.28  4864.2  362.40  4885.5  361.61
  4895.4  361.73  4950.9  361.16  4968.8  359.85  4978.4  354.43  4983.7  353.81
  4987.6  352.84  4987.9  352.34  4991.7  352.34  4991.9  352.84  4997.9  354.62
  5003.1  354.62  5010.6  355.54  5022.3  359.49  5135.2  361.33  5145.6  360.80
  5169.4  361.02  5203.6  360.61  5208.8  360.95  5270.1  361.09  5437.2  366.36
#Mann=5,-1,0
  4645.0    0.05       0  4797.3   0.063       0  4895.4   0.035       0
  4987.6   0.035       0  4991.9   0.035       0
Bank Sta=4987.6,4991.9
Exp/Cntr=0.3,0.1

Type RM Length L Ch R = 1,3457,375,375,375
BEGIN DESCRIPTION:
Prairie Creek Trib C3457.31
END DESCRIPTION:
XS GIS Cut Line= 3
      2704956.72      6823134.27      2705272.11      6823565.70
      2705705.53      6823895.92
#Sta/Elev= 30
  4471.0  366.37  4496.6  365.81  4553.7  362.49  4672.7  361.37  4739.5  361.38
  4762.2  359.39  4776.6  360.34  4792.4  359.92  4847.9  361.45  4918.9  359.94
  4933.6  358.29  4975.3  357.01  4983.8  354.61  4990.0  353.97  4996.2  350.52
  4996.6  350.02  5000.7  350.52  5004.5  350.58  5011.3  356.10  5019.5  356.98
  5025.8  359.08  5045.5  359.16  5154.7  359.11  5190.0  361.37  5269.0  360.64
  5289.8  362.61  5347.9  362.40  5404.1  364.99  5447.7  365.05  5550.3  368.02
#Mann=6,-1,0
  4471.0    0.05       0  4672.7   0.063       0  4792.4    0.05       0
  4996.2    0.05       0  5000.7    0.05       0  5045.5   0.035       0
Bank Sta=4996.2,5000.7
Exp/Cntr=0.3,0.1

Type RM Length L Ch R = 1,3082,202,202,202
BEGIN DESCRIPTION:
Prairie Creek Trib C3081.72
END DESCRIPTION:
XS GIS Cut Line= 3
      2704933.40      6823023.64      2704912.18      6823611.46
      2704900.72      6823817.74
#Sta/Elev= 30
  4411.8  369.82  4449.2  368.72  4476.2  367.39  4519.2  366.27  4549.3  365.03
  4589.3  362.31  4619.3  361.44  4779.4  360.73  4799.4  359.09  4809.4  359.83
  4819.4  359.77  4829.4  358.84  4939.5  357.70  4969.5  356.24  4976.8  350.37
  4977.2  349.87  4981.8  349.87  4982.2  350.37  4989.5  350.47  4997.3  354.52
  5002.3  354.52  5009.6  356.95  5017.9  357.87  5022.9  357.83  5059.6  360.66
  5089.7  361.55  5099.7  361.06  5139.8  361.56  5159.8  362.62  5206.6  363.25
#Mann=3,-1,0
  4411.8    0.05       0  4976.8    0.05       0  4982.2    0.05       0
Bank Sta=4976.8,4982.2
Exp/Cntr=0.3,0.1

Type RM Length L Ch R = 1,2880,320,320,320
BEGIN DESCRIPTION:
Prairie Creek Trib C2879.85
END DESCRIPTION:
XS GIS Cut Line= 3
      2704739.04      6823006.23      2704726.17      6823573.06
      2704730.25      6824040.76
#Sta/Elev= 30
  4444.8  366.34  4489.6  364.24  4549.6  362.27  4599.6  361.12  4629.6  360.99
  4679.6  360.07  4729.6  358.63  4801.9  358.21  4809.7  357.51  4819.7  357.23
  4889.7  357.94  4959.7  356.64  4979.7  355.10  4989.7  351.77  4999.7  346.82
  5005.5  346.48  5005.9  345.98  5010.5  345.98  5010.9  346.48  5019.7  346.55
  5029.7  348.59  5039.7  354.56  5049.7  356.54  5069.7  356.84  5089.7  358.38
  5109.7  358.95  5169.7  359.67  5199.7  359.47  5289.7  360.86  5479.5  365.09
#Mann=3,-1,0
  4444.8    0.05       0  5005.5    0.05       0  5010.9    0.05       0
Bank Sta=5005.5,5010.9
Exp/Cntr=0.3,0.1

Type RM Length L Ch R = 1,2560,352,352,352
BEGIN DESCRIPTION:
Prairie Creek Trib C2560.15
END DESCRIPTION:
XS GIS Cut Line= 3
      2704450.77      6822917.44      2704438.00      6823479.93
      2704449.27      6824116.30
#Sta/Elev= 30
  4457.2  367.63  4530.8  364.45  4610.8  362.48  4660.8  359.89  4740.8  357.53
  4800.8  356.75  4810.8  357.29  4830.9  356.37  4920.9  356.06  4940.9  355.51
  4950.9  354.44  4960.9  352.39  4970.9  348.48  4978.1  344.93  4978.6  344.43
  4983.2  344.43  4983.6  344.93  4990.9  345.18  5000.9  348.42  5010.9  353.50
  5017.9  355.61  5030.9  356.01  5160.9  357.26  5230.9  360.03  5290.9  359.16
  5471.0  361.10  5501.0  360.94  5541.0  361.67  5611.0  364.16  5656.3  364.72
#Mann=3,-1,0
  4457.2    0.05       0  4978.1    0.05       0  4983.6    0.05       0
Bank Sta=4978.1,4983.6
Exp/Cntr=0.3,0.1

Type RM Length L Ch R = 1,2208,359,359,359
BEGIN DESCRIPTION:
Prairie Creek Trib C2207.85
END DESCRIPTION:
XS GIS Cut Line= 3
      2704272.49      6822839.73      2704136.71      6823317.23
      2703950.85      6823905.54
#Sta/Elev= 30
  4512.3  368.56  4565.6  366.25  4638.4  361.67  4731.9  358.16  4883.0  355.01
  4939.9  354.77  4969.0  352.35  4992.3  344.76  4992.7  344.26  4997.8  344.76
  5002.3  345.08  5008.1  349.57  5013.3  349.57  5028.1  353.96  5070.6  354.91
  5138.5  353.93  5170.0  354.93  5194.9  354.33  5259.6  356.98  5291.9  356.48
  5356.6  357.78  5442.7  357.69  5464.0  359.10  5474.1  358.34  5484.6  359.26
  5491.1  361.04  5496.4  359.74  5505.6  359.22  5528.7  359.00  5625.7  361.07
#Mann=5,-1,0
  4512.3    0.05       0  4969.0    0.16       0  4992.3    0.07       0
  4997.8    0.16       0  5070.6    0.05       0
Bank Sta=4992.3,4997.8
Exp/Cntr=0.3,0.1