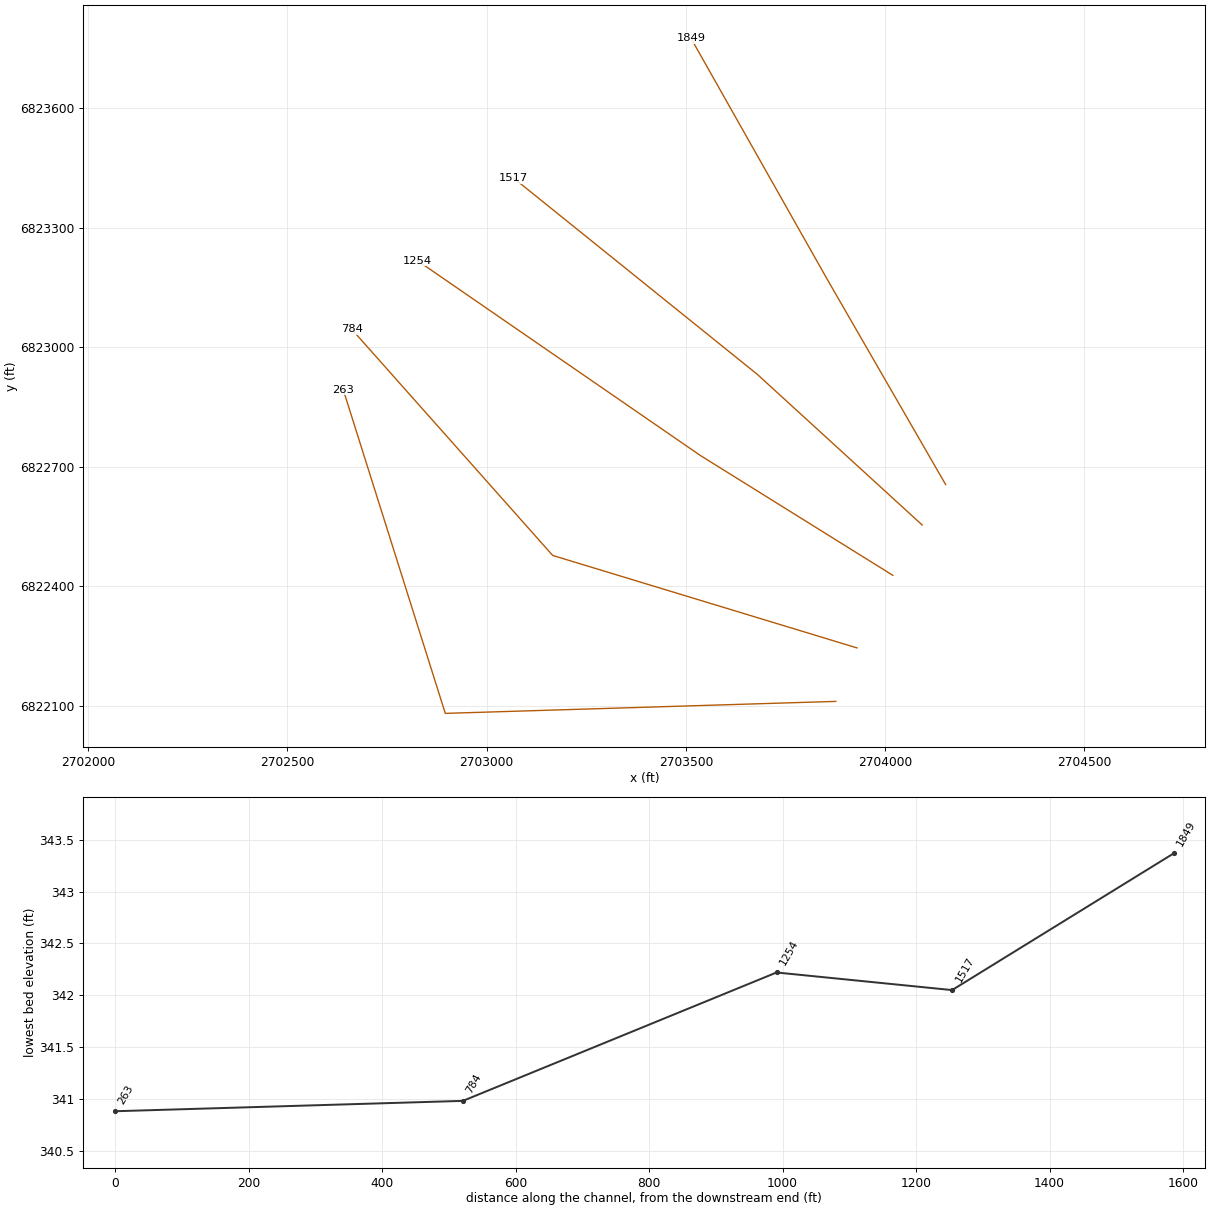
HEC-RAS study Prairie Creek Trib C.prj: Prairie Creek Trib C Base Level Engineering

--- Prairie Creek Trib C.g01 (geometry) --- (continued)

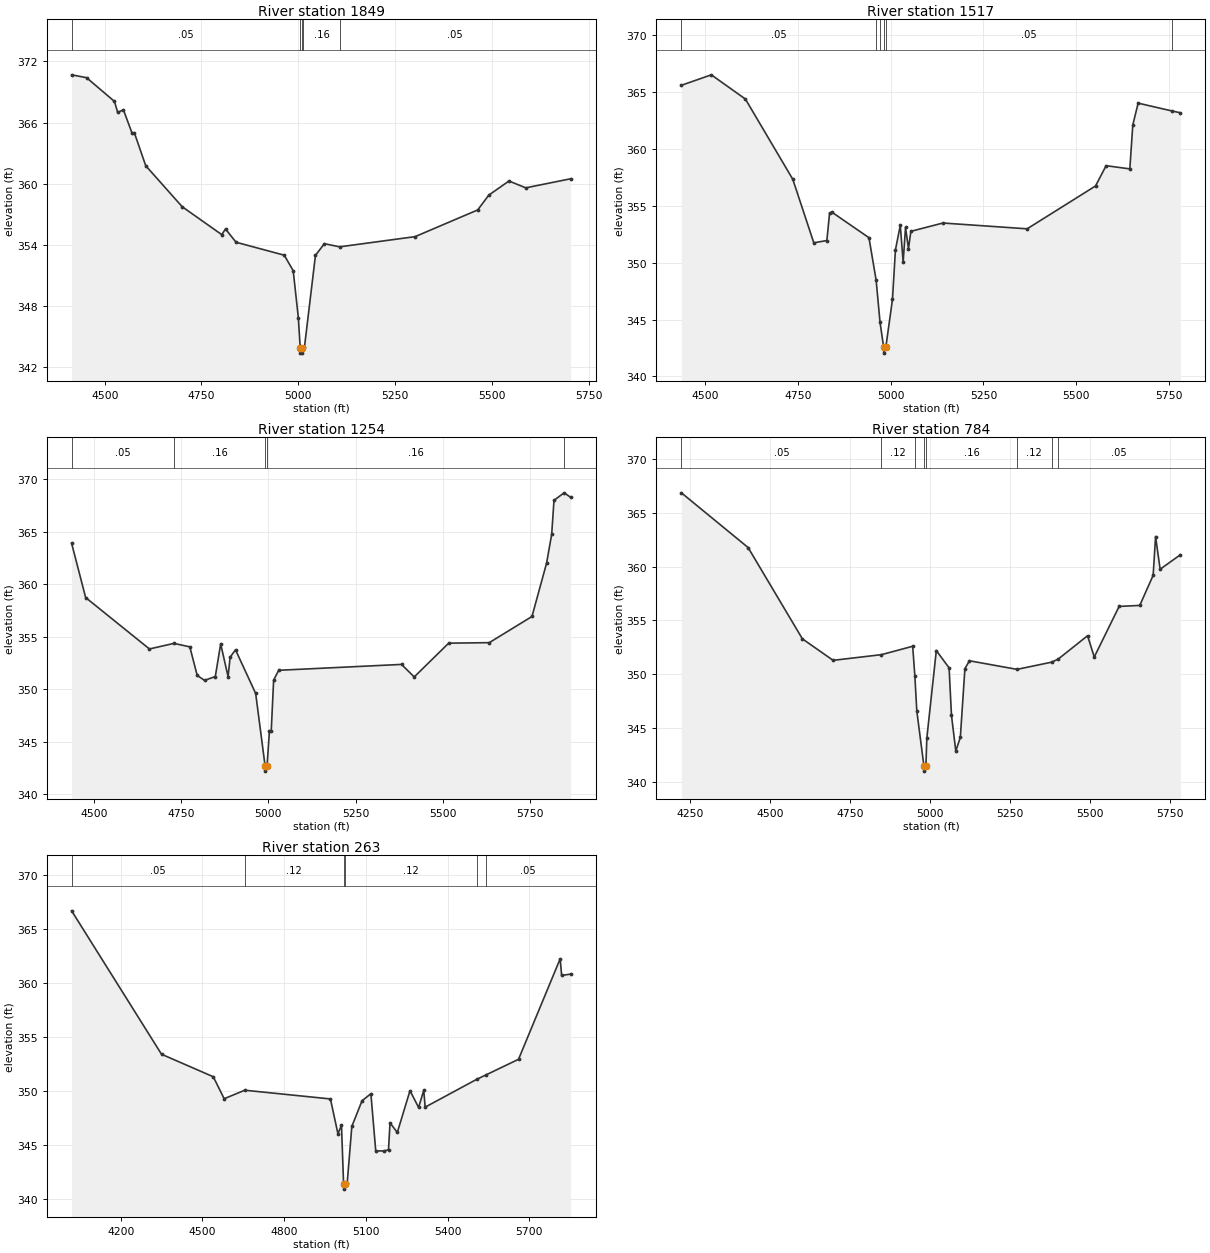
Type RM Length L Ch R = 1,1849,332,332,332
BEGIN DESCRIPTION:
Prairie Creek Trib C1849.02
END DESCRIPTION:
XS GIS Cut Line= 3
      2704151.75      6822655.14      2703853.39      6823172.27
      2703512.68      6823775.01
#Sta/Elev= 30
  4414.5  370.68  4453.1  370.40  4525.2  368.07  4533.5  366.99  4548.3  367.25
  4570.8  364.94  4576.6  364.99  4606.0  361.76  4700.1  357.74  4802.3  355.00
  4812.1  355.55  4839.4  354.25  4963.9  352.98  4987.0  351.46  5000.3  346.84
  5005.1  343.87  5005.6  343.37  5010.3  343.37  5010.7  343.87  5013.5  343.87
  5016.1  343.96  5044.5  352.96  5067.5  354.11  5106.8  353.80  5301.9  354.80
  5463.6  357.42  5492.5  358.88  5544.5  360.26  5587.8  359.59  5703.9  360.48
#Mann=5,-1,0
  4414.5    0.05       0  5005.1    0.05       0  5010.7    0.05       0
  5013.5    0.16       0  5106.8    0.05       0
Bank Sta=5005.1,5010.7
Exp/Cntr=0.3,0.1

Type RM Length L Ch R = 1,1517,263,263,263
BEGIN DESCRIPTION:
Prairie Creek Trib C1516.87
END DESCRIPTION:
XS GIS Cut Line= 3
      2704092.81      6822553.68      2703678.54      6822932.21
      2703067.70      6823424.05
#Sta/Elev= 30
  4435.6  365.60  4516.2  366.52  4608.1  364.39  4735.8  357.34  4792.5  351.75
  4827.7  351.95  4835.1  354.38  4841.9  354.43  4941.2  352.20  4960.6  348.46
  4971.0  344.78  4980.9  342.55  4981.3  342.05  4986.6  342.55  5004.6  346.77
  5012.6  351.13  5025.7  353.28  5033.4  350.05  5039.8  353.10  5047.8  351.24
  5054.2  352.76  5140.6  353.49  5367.7  352.98  5552.1  356.75  5580.5  358.53
  5644.5  358.25  5652.5  362.11  5666.9  364.03  5758.5  363.34  5781.0  363.18
#Mann=6,-1,0
  4435.6    0.05       0  4960.6    0.16       0  4971.0    0.05       0
  4980.9    0.05       0  4986.6    0.05       0  5758.5   0.033       0
Bank Sta=4980.9,4986.6
Exp/Cntr=0.3,0.1

Type RM Length L Ch R = 1,1254,470,470,470
BEGIN DESCRIPTION:
Prairie Creek Trib C1253.98
END DESCRIPTION:
XS GIS Cut Line= 3
      2704019.22      6822427.34      2703536.18      6822728.10
      2702826.65      6823216.85
#Sta/Elev= 30
  4435.9  363.89  4476.1  358.73  4659.0  353.84  4729.1  354.37  4774.7  354.04
  4795.9  351.32  4817.1  350.85  4847.8  351.22  4863.2  354.32  4884.4  351.21
  4890.3  353.06  4905.7  353.76  4963.5  349.61  4990.5  342.72  4991.0  342.22
  4996.2  342.72  5002.9  346.02  5008.1  346.02  5015.0  350.87  5029.4  351.81
  5381.6  352.37  5418.0  351.18  5516.8  354.39  5633.2  354.44  5755.6  356.93
  5797.5  362.01  5812.1  364.75  5818.7  367.98  5847.8  368.69  5866.5  368.26
#Mann=5,-1,0
  4435.9    0.05       0  4729.1    0.16       0  4990.5    0.05       0
  4996.2    0.16       0  5847.8   0.033       0
Bank Sta=4990.5,4996.2
Exp/Cntr=0.3,0.1

Type RM Length L Ch R = 1,784,521,521,521
BEGIN DESCRIPTION:
Prairie Creek Trib C783.56
END DESCRIPTION:
XS GIS Cut Line= 3
      2703929.30      6822245.19      2703165.59      6822477.26
      2702660.66      6823045.56
#Sta/Elev= 30
  4223.0  366.88  4431.2  361.79  4600.8  353.29  4696.8  351.29  4847.8  351.82
  4945.2  352.60  4952.0  349.84  4958.1  346.57  4980.2  341.48  4980.7  340.98
  4986.5  341.48  4989.4  344.06  5019.0  352.20  5058.9  350.59  5066.3  346.19
  5079.8  342.85  5094.0  344.12  5108.3  350.52  5122.5  351.25  5271.0  350.45
  5379.0  351.12  5399.3  351.40  5491.3  353.58  5512.2  351.60  5589.9  356.31
  5654.3  356.40  5696.1  359.20  5703.7  362.81  5717.9  359.77  5781.4  361.12
#Mann=8,-1,0
  4223.0    0.05       0  4847.8    0.12       0  4952.0    0.16       0
  4980.2    0.07       0  4986.5    0.16       0  5271.0    0.12       0
  5379.0    0.16       0  5399.3    0.05       0
Bank Sta=4980.2,4986.5
Exp/Cntr=0.3,0.1

Type RM Length L Ch R = 1,263,0,0,0
BEGIN DESCRIPTION:
Prairie Creek Trib C262.601
END DESCRIPTION:
XS GIS Cut Line= 3
      2703875.97      6822111.00      2702896.03      6822080.93
      2702639.76      6822893.68
#Sta/Elev= 30
  4019.6  366.71  4349.7  353.40  4539.8  351.31  4579.8  349.27  4655.4  350.06
  4970.0  349.25  4997.5  346.03  5010.6  346.80  5018.3  341.38  5018.8  340.88
  5024.7  341.38  5031.5  341.42  5048.6  346.70  5086.2  349.09  5118.6  349.73
  5136.4  344.43  5167.8  344.42  5183.3  344.54  5188.8  347.03  5215.6  346.14
  5262.2  350.02  5293.7  348.46  5312.7  350.05  5317.9  348.49  5507.1  351.07
  5540.3  351.47  5660.7  352.93  5813.7  362.26  5819.0  360.71  5852.2  360.84
#Mann=6,-1,0
  4019.6    0.05       0  4655.4    0.12       0  5018.3    0.07       0
  5024.7    0.12       0  5507.1    0.16       0  5540.3    0.05       0
Bank Sta=5018.3,5024.7
Exp/Cntr=0.3,0.1

Chan Stop Cuts=-1