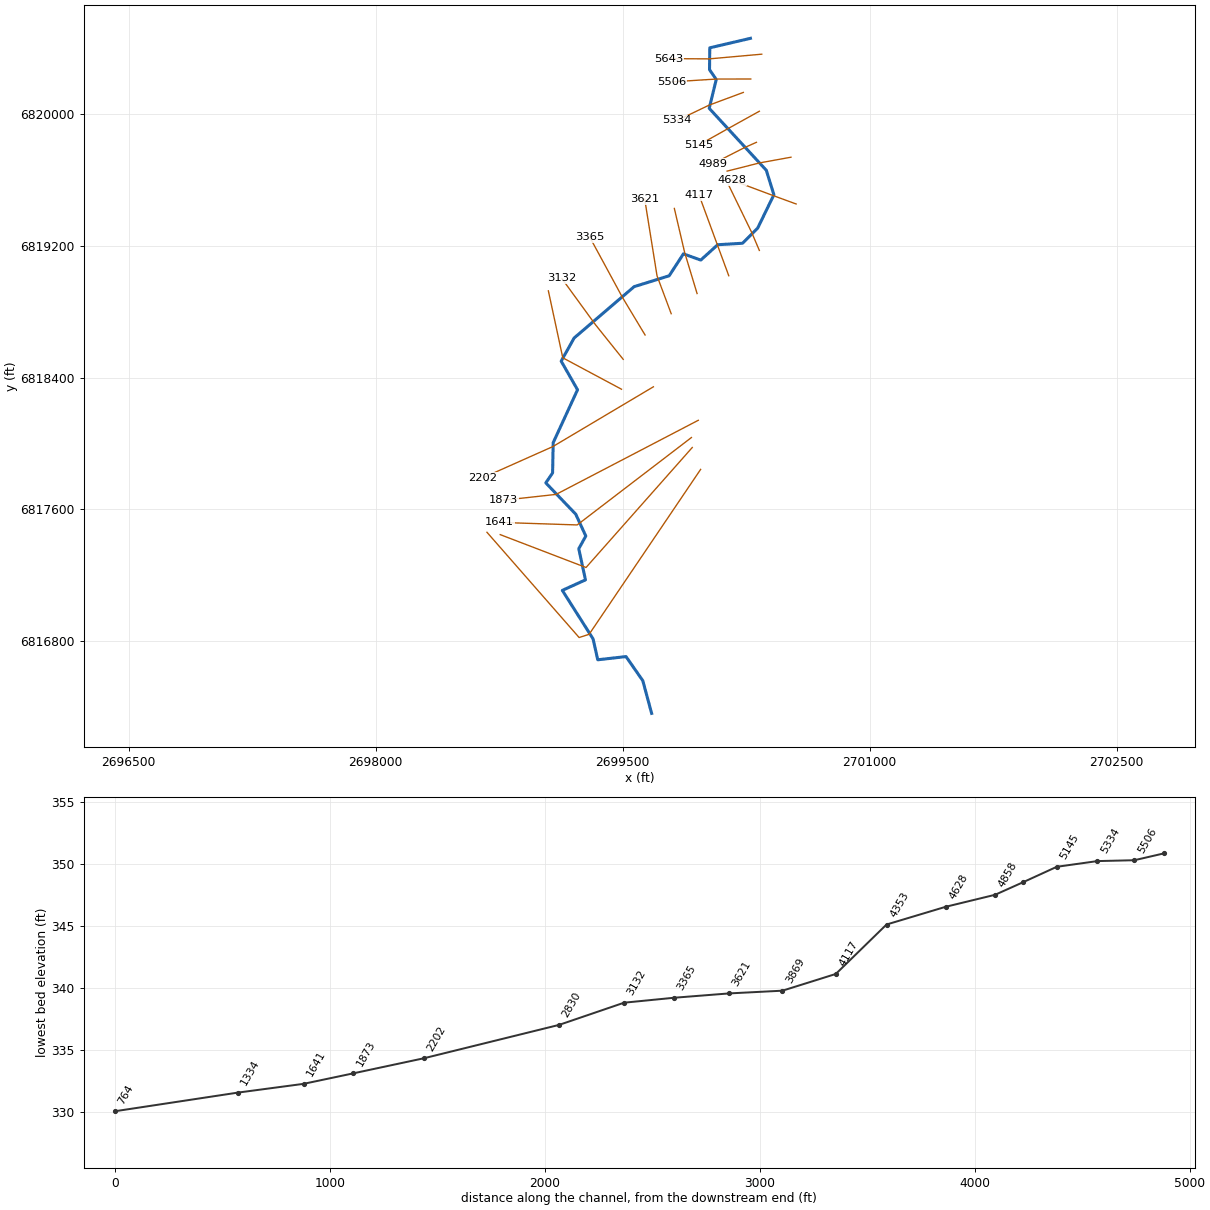
--- Prairie Creek Trib D.prj (project) ---

Proj Title=Prairie Creek Trib D Base Level Engineering
Current Plan=p01
Default Exp/Contr=0.3,0.1
English Units
Geom File=g01
Flow File=f01
Plan File=p01
BEGIN DESCRIPTION:
Prairie Creek Trib D
END DESCRIPTION:

--- Prairie Creek Trib D.p01 (plan) ---

Plan Title=Multiple Run
Short Identifier=Multiple
Geom File=g01
Flow File=f01
Subcritical Flow
K Sum by GR= 0
Std Step Tol= 0.01
Critical Tol= 0.01
Num of Std Step Trials= 20
Max Error Tol= 0.3
Flow Tol Ratio= 0.001
Split Flow NTrial= 30
Split Flow Tol= 0.02
Split Flow Ratio= 0.02
Log Output Level= 0
Friction Slope Method= 1
Unsteady Friction Slope Method= 2
Unsteady Bridges Friction Slope Method= 1
Parabolic Critical Depth
Global Vel Dist=  1 , 1 , 1
Global Log Level= 0
CheckData=True
Encroach Param= -1, 0, 0, 0
BEGIN DESCRIPTION:
Multiple Run
END DESCRIPTION:

--- Prairie Creek Trib D.f01 (steady flow) ---

Flow Title=Multiple
Number of Profiles=7
Profile Names=10-year,25-year,50-year,1pct_min,100-year,1pct_plu,500-year
River Rch & RM= Prairie Creek Tr,Reach-1,5643
     362     466     547     319     636    1269     858
River Rch & RM= Prairie Creek Tr,Reach-1,2202
     536     708     845     500     997    1990    1388
Boundary for River Rch & Prof#=Prairie Creek Tr,Reach-1,1
Up Type=0
Dn Type=3
Dn Slope=0.005
Boundary for River Rch & Prof#=Prairie Creek Tr,Reach-1,2
Up Type=0
Dn Type=3
Dn Slope=0.005
Boundary for River Rch & Prof#=Prairie Creek Tr,Reach-1,3
Up Type=0
Dn Type=3
Dn Slope=0.005
Boundary for River Rch & Prof#=Prairie Creek Tr,Reach-1,4
Up Type=0
Dn Type=3
Dn Slope=0.005
Boundary for River Rch & Prof#=Prairie Creek Tr,Reach-1,5
Up Type=0
Dn Type=3
Dn Slope=0.005
Boundary for River Rch & Prof#=Prairie Creek Tr,Reach-1,6
Up Type=0
Dn Type=3
Dn Slope=0.005
Boundary for River Rch & Prof#=Prairie Creek Tr,Reach-1,7
Up Type=0
Dn Type=3
Dn Slope=0.005

--- Prairie Creek Trib D.g01 (geometry) ---

Geom Title=Existing Conditions

River Reach=Prairie Creek Tr,Reach-1
Reach XY= 30
      2700276.00      6820461.00      2700029.06      6820403.38
      2700027.53      6820270.61      2700068.44      6820211.00
      2700025.68      6820035.89      2700372.39      6819659.50
      2700418.47      6819510.99      2700320.17      6819308.69
      2700228.46      6819216.46      2700077.47      6819207.44
      2699974.35      6819114.17      2699868.99      6819151.97
      2699782.45      6819018.75      2699569.94      6818952.86
      2699205.58      6818641.23      2699126.70      6818500.30
      2699226.09      6818326.41      2699078.24      6818005.07
      2699074.61      6817821.43      2699033.32      6817760.90
      2699215.24      6817570.68      2699276.31      6817438.16
      2699233.59      6817361.01      2699274.29      6817171.85
      2699133.75      6817107.97      2699320.46      6816813.42
      2699348.85      6816686.53      2699520.53      6816705.89
      2699622.38      6816559.50      2699676.00      6816361.00

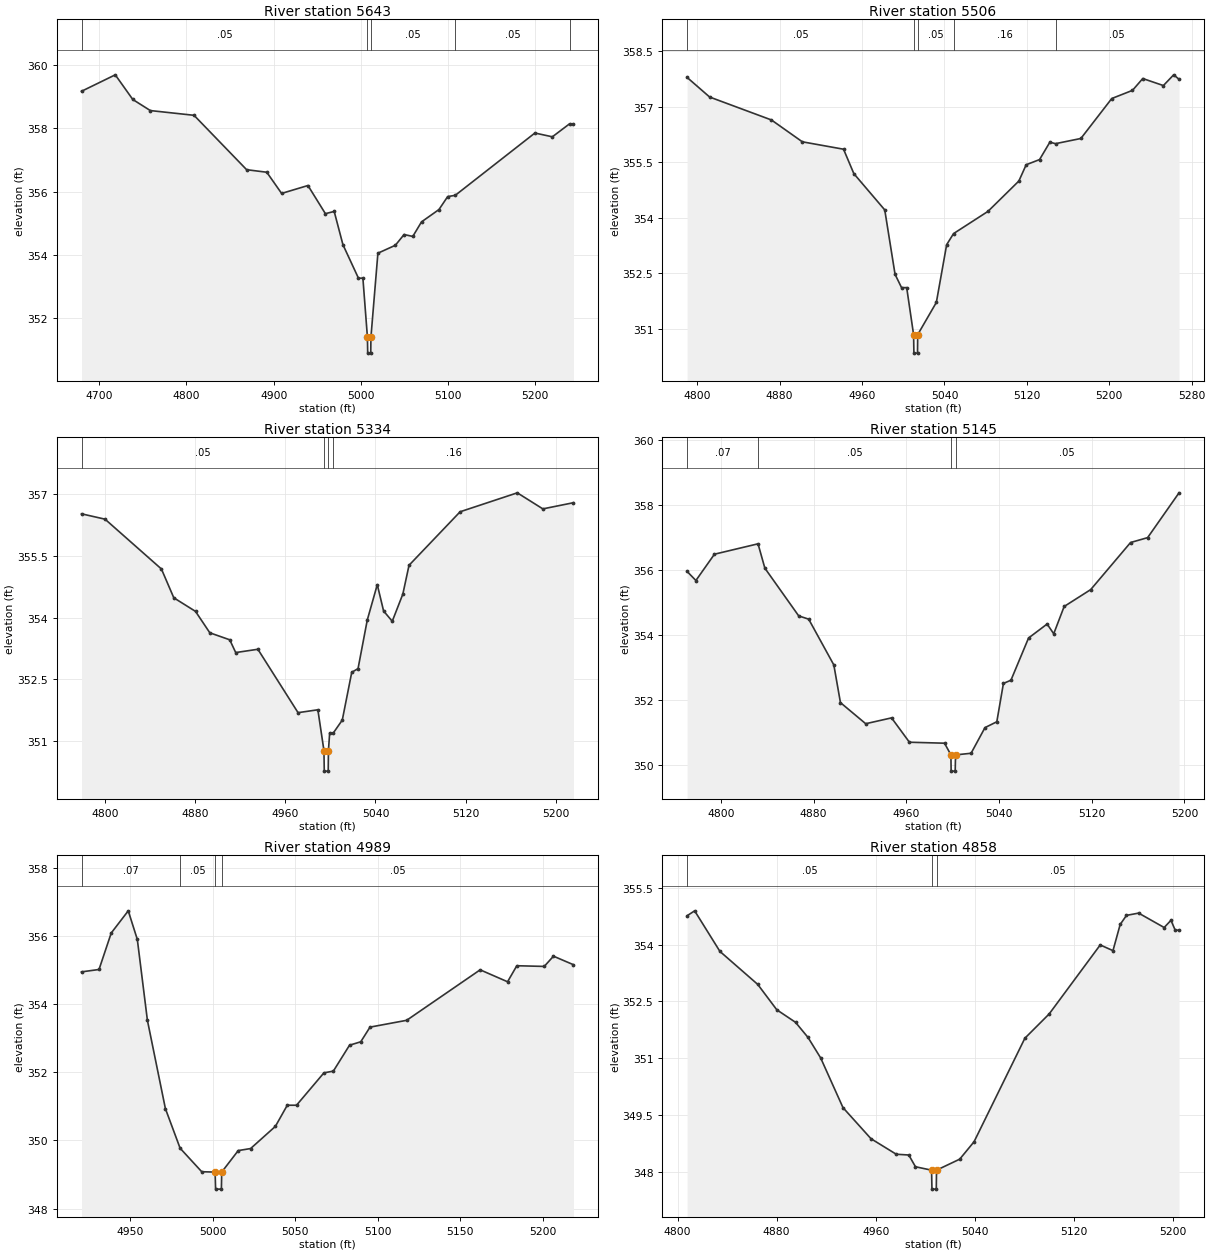
Type RM Length L Ch R = 1,5643,137,137,137
BEGIN DESCRIPTION:
Prairie Creek Trib D5642.742
END DESCRIPTION:
XS GIS Cut Line= 3
      2700344.54      6820364.74      2700025.51      6820336.21
      2699781.81      6820337.75
#Sta/Elev= 30
  4679.7  359.17  4718.4  359.69  4738.5  358.91  4758.6  358.56  4808.7  358.41
  4869.0  356.69  4892.1  356.61  4909.1  355.94  4939.3  356.19  4959.3  355.30
  4969.4  355.37  4979.4  354.32  4997.2  353.26  5002.3  353.26  5007.5  351.39
  5007.8  350.89  5011.3  350.89  5011.5  351.39  5019.5  354.05  5039.5  354.30
  5049.5  354.64  5059.5  354.58  5069.5  355.04  5089.5  355.43  5099.5  355.84
  5108.2  355.88  5199.5  357.85  5219.5  357.73  5239.2  358.14  5243.7  358.14
#Mann=5,-1,0
  4679.7    0.05       0  5007.5    0.05       0  5011.5    0.05       0
  5108.2    0.05       0  5239.2   0.035       0
Bank Sta=5007.5,5011.5
Exp/Cntr=0.3,0.1

Type RM Length L Ch R = 1,5506,172,172,172
BEGIN DESCRIPTION:
Prairie Creek Trib D5506.15
END DESCRIPTION:
XS GIS Cut Line= 3
      2700277.92      6820214.05      2700068.51      6820213.66
      2699800.85      6820196.81
#Sta/Elev= 30
  4790.1  357.79  4812.0  357.26  4872.0  356.64  4902.0  356.05  4942.0  355.85
  4952.0  355.19  4982.0  354.21  4992.0  352.47  4998.3  352.11  5003.3  352.11
  5010.0  350.84  5010.3  350.34  5013.8  350.34  5014.0  350.84  5032.1  351.71
  5042.1  353.27  5048.8  353.57  5082.2  354.17  5112.2  354.99  5119.3  355.43
  5132.3  355.57  5142.3  356.04  5147.8  356.00  5172.4  356.14  5202.4  357.22
  5222.5  357.44  5232.5  357.76  5252.5  357.57  5262.5  357.86  5267.7  357.74
#Mann=5,-1,0
  4790.1    0.05       0  5010.0    0.05       0  5014.0    0.05       0
  5048.8    0.16       0  5147.8    0.05       0
Bank Sta=5010,5014
Exp/Cntr=0.3,0.1

Type RM Length L Ch R = 1,5334,189,189,189
BEGIN DESCRIPTION:
Mapping XS 92818d07
END DESCRIPTION:
XS GIS Cut Line= 3
      2700232.84      6820132.46      2700025.11      6820055.25
      2699830.76      6819962.19
#Sta/Elev= 30
  4778.8  356.52  4799.7  356.39  4849.8  355.18  4860.8  354.48  4880.1  354.15
  4892.8  353.63  4910.5  353.46  4915.8  353.15  4935.5  353.23  4971.2  351.69
  4988.8  351.76  4994.2  350.77  4994.5  350.27  4998.0  350.27  4998.2  350.77
  4999.3  351.20  5002.6  351.20  5010.5  351.51  5018.9  352.67  5024.5  352.76
  5032.7  353.94  5041.6  354.80  5047.2  354.16  5054.9  353.91  5064.3  354.57
  5069.8  355.27  5115.2  356.57  5166.0  357.03  5188.7  356.64  5215.9  356.79
#Mann=4,-1,0
  4778.8    0.05       0  4994.2    0.05       0  4998.2    0.05       0
  5002.6    0.16       0
Bank Sta=4994.2,4998.2
Exp/Cntr=0.3,0.1

Type RM Length L Ch R = 1,5145,156,156,156
BEGIN DESCRIPTION:
Prairie Creek Trib D5144.58
END DESCRIPTION:
XS GIS Cut Line= 3
      2700330.20      6820018.27      2700126.91      6819905.42
      2699959.58      6819811.49
#Sta/Elev= 30
  4770.9  355.96  4778.5  355.68  4794.5  356.49  4832.1  356.81  4838.0  356.06
  4867.2  354.59  4875.8  354.49  4897.5  353.08  4903.2  351.92  4925.0  351.27
  4947.3  351.45  4962.7  350.70  4993.0  350.67  4998.5  350.31  4998.7  349.81
  5002.2  349.81  5002.5  350.31  5015.9  350.36  5027.9  351.15  5038.1  351.33
  5043.8  352.51  5050.3  352.61  5065.5  353.91  5081.5  354.34  5087.2  354.04
  5096.2  354.88  5119.1  355.40  5153.5  356.85  5168.2  357.00  5195.3  358.38
#Mann=4,-1,0
  4770.9    0.07       0  4832.1    0.05       0  4998.5    0.05       0
  5002.5    0.05       0
Bank Sta=4998.5,5002.5
Exp/Cntr=0.3,0.1

Type RM Length L Ch R = 1,4989,131,131,131
BEGIN DESCRIPTION:
Prairie Creek Trib D4989
END DESCRIPTION:
XS GIS Cut Line= 3
      2700312.41      6819829.53      2700235.97      6819795.32
      2700045.24      6819697.94
#Sta/Elev= 30
  4920.6  354.94  4931.2  355.01  4938.6  356.08  4948.9  356.73  4954.4  355.89
  4960.5  353.52  4971.4  350.93  4980.3  349.77  4993.4  349.08  5001.5  349.07
  5001.8  348.57  5005.3  348.57  5005.5  349.07  5015.5  349.70  5023.0  349.76
  5038.0  350.41  5045.2  351.03  5050.8  351.03  5067.4  351.98  5073.1  352.03
  5082.9  352.79  5089.7  352.89  5095.3  353.32  5117.5  353.52  5162.0  355.00
  5178.6  354.65  5184.2  355.12  5200.8  355.10  5206.4  355.40  5218.5  355.15
#Mann=4,-1,0
  4920.6    0.07       0  4980.3    0.05       0  5001.5    0.05       0
  5005.5    0.05       0
Bank Sta=5001.5,5005.5
Exp/Cntr=0.3,0.1

Type RM Length L Ch R = 1,4858,230,230,230
BEGIN DESCRIPTION:
Prairie Creek Trib D4857.9
END DESCRIPTION:
XS GIS Cut Line= 3
      2700522.04      6819739.00      2700331.73      6819704.40
      2700134.38      6819654.48
#Sta/Elev= 30
  4807.7  354.76  4813.8  354.89  4834.2  353.82  4864.7  352.95  4880.1  352.28
  4895.2  351.95  4905.3  351.55  4915.5  351.01  4933.5  349.70  4956.1  348.88
  4976.5  348.47  4986.6  348.45  4992.0  348.14  5005.0  348.05  5005.3  347.55
  5008.8  347.55  5009.0  348.05  5027.7  348.34  5039.3  348.80  5080.3  351.53
  5099.9  352.17  5141.1  353.99  5151.4  353.84  5157.2  354.53  5162.3  354.77
  5172.1  354.83  5192.7  354.45  5198.2  354.64  5201.6  354.38  5204.7  354.38
#Mann=3,-1,0
  4807.7    0.05       0  5005.0    0.05       0  5009.0    0.05       0
Bank Sta=5005,5009
Exp/Cntr=0.3,0.1

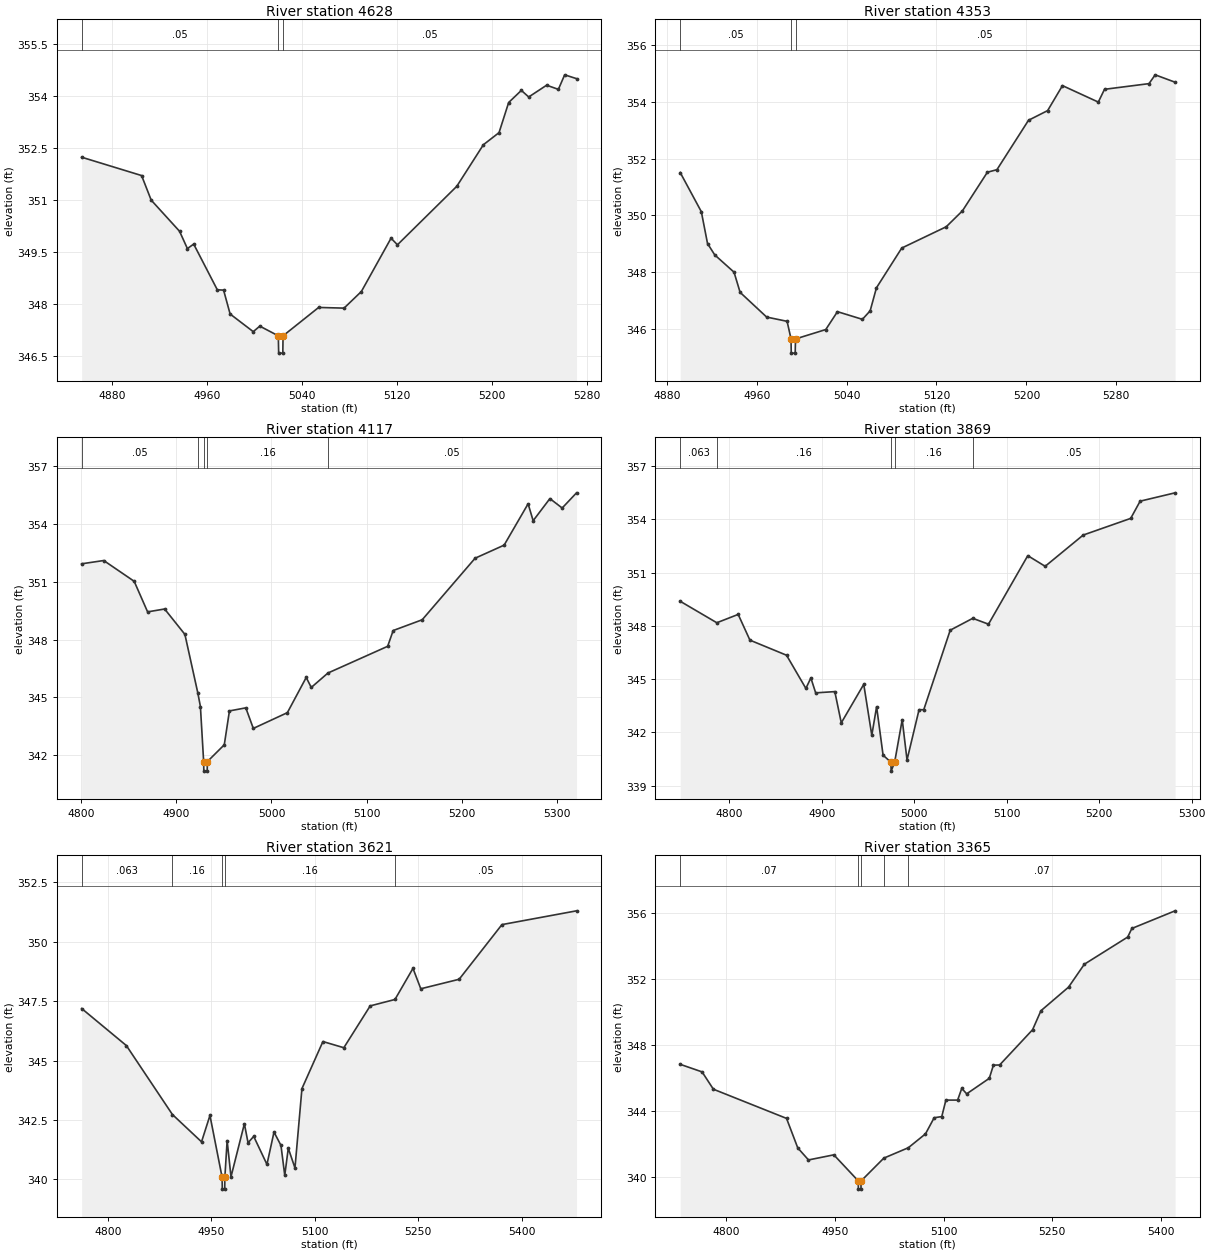
Type RM Length L Ch R = 1,4628,275,275,275
BEGIN DESCRIPTION:
Prairie Creek Trib D4628.43
END DESCRIPTION:
XS GIS Cut Line= 3
      2700553.43      6819454.86      2700414.45      6819505.85
      2700162.42      6819599.75
#Sta/Elev= 30
  4854.5  352.24  4905.0  351.71  4913.1  351.00  4937.0  350.10  4943.6  349.60
  4948.9  349.73  4968.8  348.41  4974.1  348.40  4979.6  347.71  4999.1  347.20
  5004.6  347.36  5020.2  347.08  5020.5  346.58  5024.0  346.58  5024.2  347.08
  5054.2  347.90  5075.6  347.88  5090.2  348.36  5115.2  349.90  5120.6  349.71
  5170.6  351.40  5193.0  352.60  5206.2  352.95  5214.3  353.82  5225.0  354.17
  5231.2  353.98  5246.3  354.32  5256.2  354.20  5261.5  354.62  5271.5  354.51
#Mann=3,-1,0
  4854.5    0.05       0  5020.2    0.05       0  5024.2    0.05       0
Bank Sta=5020.2,5024.2
Exp/Cntr=0.3,0.1

Type RM Length L Ch R = 1,4353,236,236,236
BEGIN DESCRIPTION:
Prairie Creek Trib D4353.19
END DESCRIPTION:
XS GIS Cut Line= 3
      2700330.10      6819172.74      2700283.53      6819282.10
      2700142.89      6819571.14
#Sta/Elev= 30
  4892.0  351.51  4910.8  350.13  4916.3  349.01  4922.7  348.61  4939.9  348.00
  4945.3  347.29  4968.9  346.42  4987.1  346.27  4990.6  345.65  4990.8  345.15
  4994.3  345.15  4994.6  345.65  5021.5  345.98  5031.9  346.61  5054.1  346.34
  5061.0  346.64  5066.6  347.45  5089.1  348.85  5128.7  349.60  5143.1  350.16
  5165.3  351.52  5173.8  351.61  5201.9  353.35  5218.9  353.69  5232.1  354.57
  5264.0  353.99  5269.5  354.44  5309.1  354.64  5314.6  354.95  5332.3  354.69
#Mann=3,-1,0
  4892.0    0.05       0  4990.6    0.05       0  4994.6    0.05       0
Bank Sta=4990.6,4994.6
Exp/Cntr=0.3,0.1

Type RM Length L Ch R = 1,4117,248,248,248
BEGIN DESCRIPTION:
Prairie Creek Trib D4116.96
END DESCRIPTION:
XS GIS Cut Line= 3
      2700144.30      6819019.19      2700073.84      6819210.27
      2699964.72      6819507.30
#Sta/Elev= 30
  4800.5  351.94  4823.7  352.11  4855.7  351.03  4869.8  349.44  4887.7  349.59
  4909.0  348.27  4922.6  345.22  4925.3  344.52  4928.7  341.66  4928.9  341.16
  4932.4  341.16  4932.7  341.66  4950.4  342.53  4955.8  344.29  4973.0  344.45
  4980.9  343.38  5016.7  344.20  5036.5  346.03  5041.8  345.51  5059.3  346.26
  5122.1  347.65  5127.9  348.47  5158.4  349.03  5214.0  352.23  5244.5  352.91
  5269.7  355.06  5275.0  354.18  5292.6  355.33  5305.5  354.84  5320.6  355.63
#Mann=5,-1,0
  4800.5    0.05       0  4922.6    0.16       0  4928.7    0.07       0
  4932.7    0.16       0  5059.3    0.05       0
Bank Sta=4928.7,4932.7
Exp/Cntr=0.3,0.1

Type RM Length L Ch R = 1,3869,248,248,248
BEGIN DESCRIPTION:
Prairie Creek Trib D3869.29
END DESCRIPTION:
XS GIS Cut Line= 3
      2699951.96      6818910.97      2699876.52      6819160.36
      2699813.90      6819427.77
#Sta/Elev= 30
  4746.9  349.38  4786.5  348.17  4809.6  348.64  4822.3  347.19  4861.9  346.34
  4882.8  344.47  4888.2  345.06  4893.4  344.22  4914.1  344.29  4921.1  342.53
  4945.4  344.70  4954.1  341.83  4959.3  343.44  4966.3  340.71  4974.8  340.31
  4975.0  339.81  4978.8  340.31  4987.0  342.71  4992.2  340.44  5005.2  343.27
  5010.3  343.27  5038.9  347.75  5063.3  348.42  5080.3  348.09  5122.8  351.95
  5141.6  351.35  5182.7  353.11  5234.1  354.05  5244.3  355.02  5282.1  355.49
#Mann=5,-1,0
  4746.9   0.063       0  4786.5    0.16       0  4974.8    0.07       0
  4978.8    0.16       0  5063.3    0.05       0
Bank Sta=4974.8,4978.8
Exp/Cntr=0.3,0.1

Type RM Length L Ch R = 1,3621,256,256,256
BEGIN DESCRIPTION:
Prairie Creek Trib D3620.91
END DESCRIPTION:
XS GIS Cut Line= 3
      2699794.88      6818788.34      2699708.84      6819018.04
      2699634.03      6819483.89
#Sta/Elev= 30
  4762.1  347.19  4826.9  345.63  4893.6  342.73  4935.8  341.58  4948.0  342.69
  4965.6  340.09  4965.9  339.59  4969.4  339.59  4969.6  340.09  4972.9  341.63
  4978.5  340.11  4997.9  342.34  5003.2  341.54  5011.4  341.81  5030.6  340.63
  5040.8  341.99  5050.9  341.43  5056.4  340.17  5061.5  341.31  5071.2  340.48
  5081.3  343.82  5111.7  345.80  5142.0  345.54  5180.2  347.30  5216.1  347.57
  5242.2  348.88  5253.5  348.02  5309.1  348.42  5371.1  350.72  5479.2  351.30
#Mann=5,-1,0
  4762.1   0.063       0  4893.6    0.16       0  4965.6    0.07       0
  4969.6    0.16       0  5216.1    0.05       0
Bank Sta=4965.6,4969.6
Exp/Cntr=0.3,0.1

Type RM Length L Ch R = 1,3365,233,233,233
BEGIN DESCRIPTION:
Prairie Creek Trib D3364.87
END DESCRIPTION:
XS GIS Cut Line= 3
      2699636.07      6818659.25      2699498.63      6818887.75
      2699300.12      6819253.96
#Sta/Elev= 30
  4736.3  346.81  4766.5  346.35  4782.1  345.30  4883.1  343.53  4898.6  341.74
  4913.4  341.01  4948.4  341.32  4982.1  339.74  4982.3  339.24  4985.8  339.24
  4986.1  339.74  5017.4  341.12  5051.2  341.75  5074.9  342.59  5086.9  343.57
  5097.4  343.64  5103.1  344.64  5119.3  344.64  5125.0  345.35  5131.8  345.02
  5163.0  345.96  5168.7  346.76  5177.3  346.77  5222.8  348.91  5234.3  350.06
  5272.4  351.49  5294.2  352.88  5354.1  354.53  5359.8  355.05  5419.5  356.12
#Mann=5,-1,0
  4736.3    0.07       0  4982.1    0.07       0  4986.1    0.07       0
  5017.4    0.16       0  5051.2    0.07       0
Bank Sta=4982.1,4986.1
Exp/Cntr=0.3,0.1

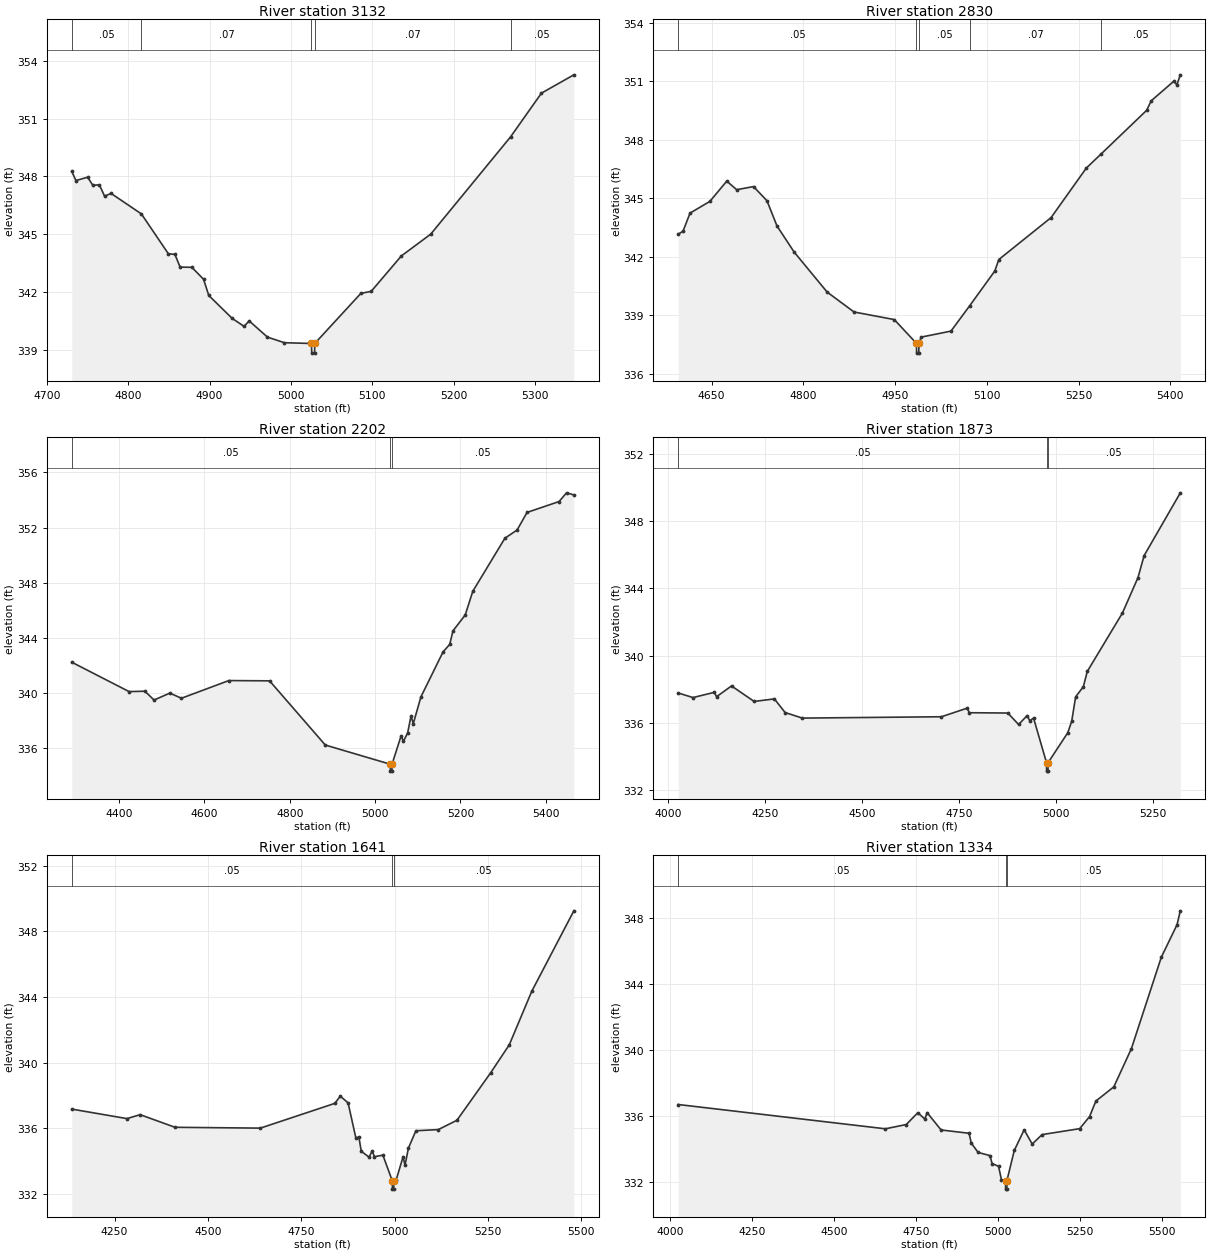
Type RM Length L Ch R = 1,3132,302,302,302
BEGIN DESCRIPTION:
Prairie Creek Trib D3132.36
END DESCRIPTION:
XS GIS Cut Line= 3
      2699503.46      6818511.18      2699333.28      6818723.83
      2699130.70      6819002.39
#Sta/Elev= 30
  4730.7  348.26  4735.8  347.79  4750.2  347.96  4756.6  347.54  4764.6  347.57
  4771.0  346.98  4779.0  347.12  4816.2  346.06  4849.4  343.99  4857.4  343.96
  4863.8  343.30  4878.2  343.29  4892.6  342.67  4899.0  341.83  4927.8  340.64
  4942.3  340.23  4948.7  340.51  4971.1  339.67  4991.9  339.38  5025.2  339.34
  5025.5  338.84  5029.0  338.84  5029.2  339.34  5085.9  341.94  5098.5  342.04
  5135.6  343.88  5171.7  345.01  5269.7  350.05  5307.7  352.32  5347.5  353.27
#Mann=5,-1,0
  4730.7    0.05       0  4816.2    0.07       0  5025.2    0.07       0
  5029.2    0.07       0  5269.7    0.05       0
Bank Sta=5025.2,5029.2
Exp/Cntr=0.3,0.1

Type RM Length L Ch R = 1,2830,628,628,628
BEGIN DESCRIPTION:
Prairie Creek Trib D2830.324
END DESCRIPTION:
XS GIS Cut Line= 3
      2699493.06      6818329.76      2699136.49      6818520.55
      2699048.94      6818927.43
#Sta/Elev= 30
  4595.6  343.15  4603.4  343.30  4614.9  344.23  4647.3  344.83  4674.9  345.87
  4691.1  345.43  4718.7  345.59  4740.7  344.86  4757.0  343.57  4785.1  342.23
  4839.0  340.18  4882.9  339.16  4948.7  338.77  4985.0  337.55  4985.2  337.05
  4988.7  337.05  4989.0  337.55  4992.6  337.87  5041.4  338.18  5072.2  339.49
  5113.0  341.26  5119.6  341.85  5205.0  344.00  5262.6  346.54  5286.7  347.26
  5361.2  349.50  5368.7  349.99  5405.5  350.99  5410.6  350.81  5416.2  351.32
#Mann=5,-1,0
  4595.6    0.05       0  4985.0    0.05       0  4989.0    0.05       0
  5072.2    0.07       0  5286.7    0.05       0
Bank Sta=4985,4989
Exp/Cntr=0.3,0.1

Type RM Length L Ch R = 1,2202,329,329,329
BEGIN DESCRIPTION:
Prairie Creek Trib D2202.185
END DESCRIPTION:
XS GIS Cut Line= 3
      2699686.75      6818344.55      2699075.64      6817981.15
      2698650.27      6817791.57
#Sta/Elev= 30
  4289.0  342.25  4423.4  340.12  4460.4  340.15  4481.8  339.51  4518.8  340.01
  4546.1  339.64  4657.1  340.92  4752.6  340.90  4883.2  336.25  5035.6  334.86
  5035.8  334.36  5039.3  334.36  5039.6  334.86  5060.8  336.91  5066.3  336.52
  5076.2  337.13  5084.0  338.34  5089.5  337.81  5107.3  339.74  5159.2  343.00
  5174.8  343.54  5182.4  344.52  5211.1  345.67  5228.9  347.39  5304.1  351.23
  5332.8  351.83  5356.0  353.10  5431.2  353.89  5448.5  354.52  5465.7  354.37
#Mann=3,-1,0
  4289.0    0.05       0  5035.6    0.05       0  5039.6    0.05       0
Bank Sta=5035.6,5039.6
Exp/Cntr=0.3,0.1

Type RM Length L Ch R = 1,1873,232,232,232
BEGIN DESCRIPTION:
Prairie Creek Trib D1759.809
END DESCRIPTION:
XS GIS Cut Line= 3
      2699959.43      6818141.21      2699095.84      6817691.00
      2698777.68      6817655.81
#Sta/Elev= 30
  4026.1  337.78  4064.2  337.51  4119.2  337.82  4124.9  337.56  4163.4  338.20
  4221.7  337.28  4273.9  337.43  4301.6  336.62  4345.8  336.29  4704.5  336.37
  4770.7  336.88  4776.4  336.61  4875.6  336.59  4903.3  335.91  4925.4  336.44
  4932.2  336.13  4941.9  336.29  4975.3  333.64  4975.5  333.14  4979.0  333.14
  4979.3  333.64  5030.0  335.42  5040.1  336.09  5050.3  337.55  5070.3  338.16
  5080.3  339.06  5170.9  342.53  5211.1  344.64  5226.8  345.94  5320.1  349.67
#Mann=3,-1,0
  4026.1    0.05       0  4975.3    0.05       0  4979.3    0.05       0
Bank Sta=4975.3,4979.3
Exp/Cntr=0.3,0.1

Type RM Length L Ch R = 1,1641,307,307,307
BEGIN DESCRIPTION:
Mapping XS cba68ff7
END DESCRIPTION:
XS GIS Cut Line= 3
      2699917.66      6818036.35      2699224.01      6817505.52
      2698753.22      6817520.90
#Sta/Elev= 30
  4135.5  337.17  4283.3  336.59  4318.6  336.83  4412.1  336.06  4640.6  336.01
  4840.0  337.52  4854.6  337.96  4875.4  337.55  4896.2  335.42  4904.4  335.46
  4910.7  334.60  4931.5  334.24  4939.8  334.61  4946.1  334.27  4968.7  334.36
  4993.9  332.79  4994.2  332.29  4997.7  332.29  4997.9  332.79  5004.2  332.85
  5022.8  334.27  5027.8  333.74  5037.0  334.79  5057.0  335.85  5117.0  335.92
  5167.0  336.49  5257.1  339.38  5307.1  341.09  5367.2  344.35  5480.0  349.26
#Mann=3,-1,0
  4135.5    0.05       0  4993.9    0.05       0  4997.9    0.05       0
Bank Sta=4993.9,4997.9
Exp/Cntr=0.3,0.1

Type RM Length L Ch R = 1,1334,570,570,570
BEGIN DESCRIPTION:
Mapping XS 6a062d1c
END DESCRIPTION:
XS GIS Cut Line= 3
      2699922.73      6817975.88      2699277.61      6817246.97
      2698756.66      6817446.66
#Sta/Elev= 30
  4025.4  336.70  4657.3  335.23  4720.9  335.49  4756.0  336.20  4777.7  335.82
  4784.4  336.21  4827.1  335.16  4912.4  334.96  4919.1  334.37  4940.0  333.80
  4976.0  333.61  4982.7  333.13  5002.3  332.96  5011.2  332.15  5023.7  332.08
  5023.9  331.58  5027.4  331.58  5027.7  332.08  5050.3  333.92  5080.4  335.17
  5105.0  334.31  5135.1  334.88  5249.9  335.24  5279.9  335.97  5299.2  336.91
  5353.9  337.77  5407.5  340.08  5498.7  345.61  5546.7  347.58  5556.7  348.42
#Mann=3,-1,0
  4025.4    0.05       0  5023.7    0.05       0  5027.7    0.05       0
Bank Sta=5023.7,5027.7
Exp/Cntr=0.3,0.1

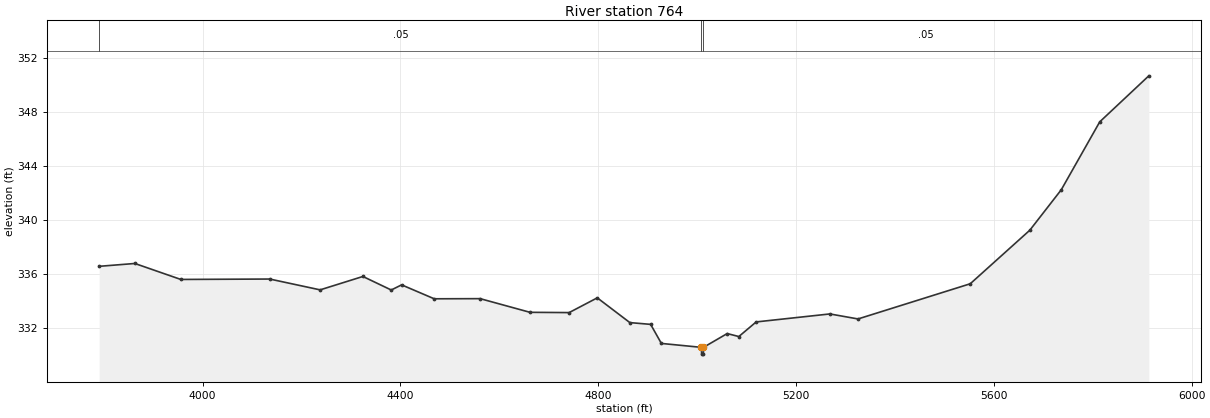
Type RM Length L Ch R = 1,764,0,0,0
BEGIN DESCRIPTION:
Prairie Creek Trib D1287.397
END DESCRIPTION:
XS GIS Cut Line= 4
      2699973.48      6817842.79      2699296.41      6816841.17
      2699235.74      6816821.75      2698675.99      6817461.02
#Sta/Elev= 30
  3791.0  336.57  3863.2  336.78  3956.1  335.60  4135.9  335.63  4237.8  334.83
  4324.3  335.82  4381.6  334.82  4402.6  335.20  4468.5  334.17  4561.4  334.18
  4662.2  333.17  4741.3  333.15  4798.2  334.24  4864.1  332.41  4906.1  332.28
  4927.8  330.87  5008.9  330.58  5009.2  330.08  5012.7  330.08  5012.9  330.58
  5060.9  331.60  5084.4  331.38  5119.5  332.46  5268.5  333.05  5325.4  332.68
  5552.3  335.28  5672.8  339.24  5736.4  342.23  5814.2  347.25  5913.4  350.65
#Mann=3,-1,0
  3791.0    0.05       0  5008.9    0.05       0  5012.9    0.05       0
Bank Sta=5008.9,5012.9
Exp/Cntr=0.3,0.1

Chan Stop Cuts=-1