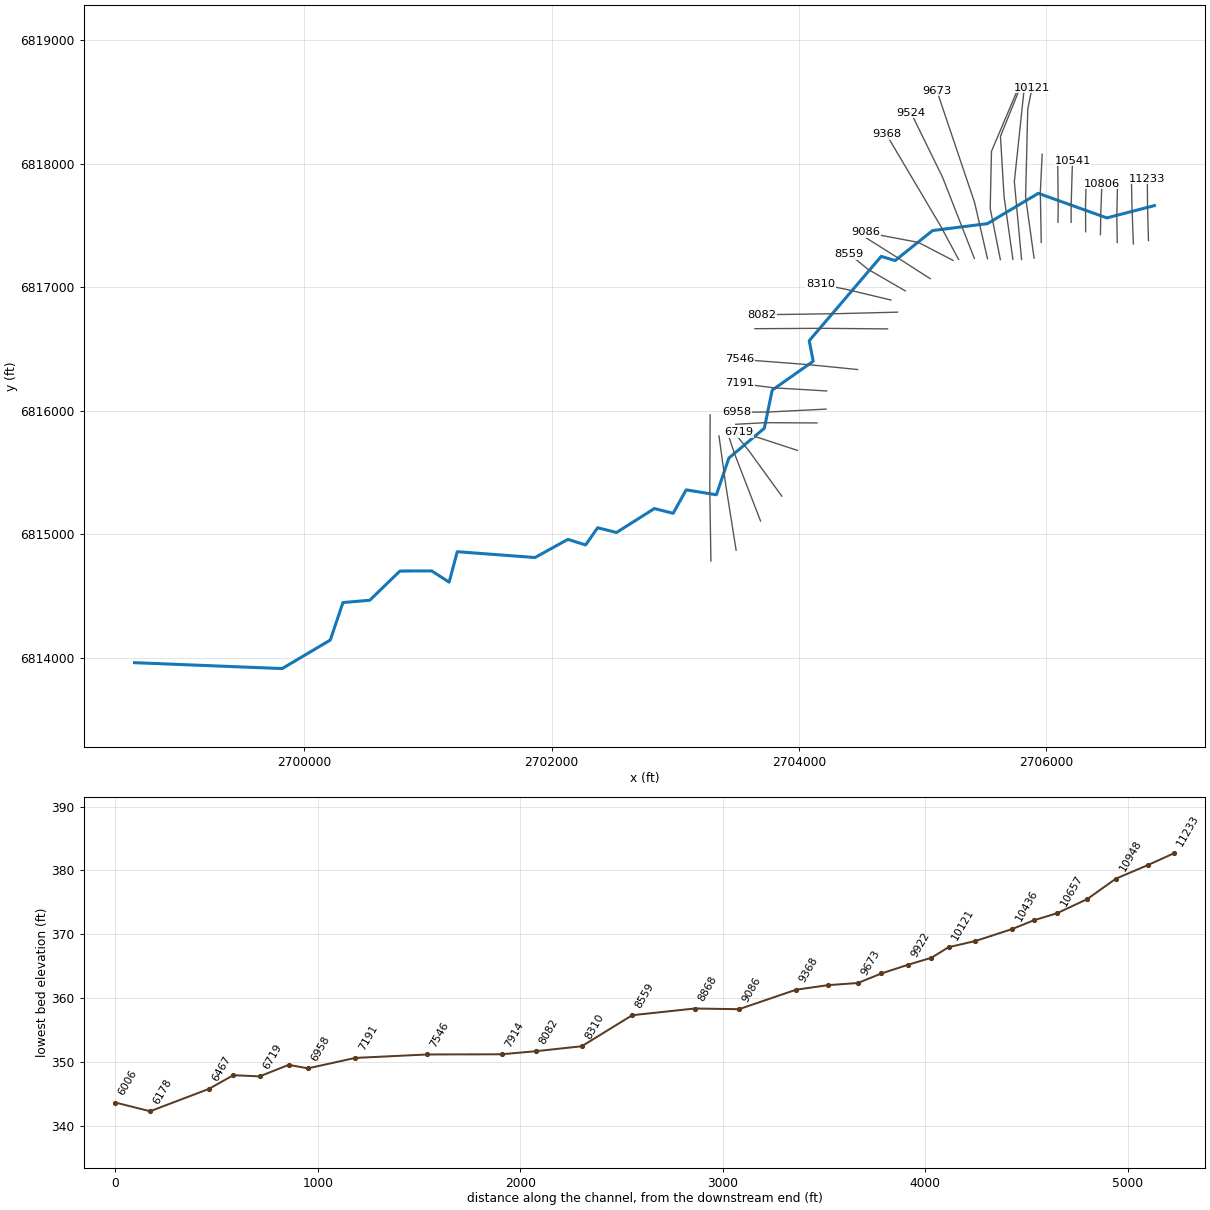
--- Prairie Creek Trib E.prj (project) ---

Proj Title=Prairie Creek Trib E Base Level Engineering
Current Plan=p01
Default Exp/Contr=0.3,0.1
English Units
Geom File=g01
Flow File=f01
Plan File=p01
Y Axis Title=Elevation
X Axis Title(PF)=Main Channel Distance
X Axis Title(XS)=Station
BEGIN DESCRIPTION:
Prairie Creek Trib E
END DESCRIPTION:
DSS Export Rating Curves= 0
DSS Export Rating Curve Sorted= 0
DSS Export Volume Flow Curves= 0
DXF OffsetX= 0
DXF OffsetY= 0
DXF ScaleX= 1
DXF ScaleY= 10

--- Prairie Creek Trib E.p01 (plan) ---

Plan Title=Multiple Run
Program Version=4.10
Short Identifier=Multiple
Geom File=g01
Flow File=f01
Subcritical Flow
K Sum by GR= 0
Std Step Tol= 0.01
Critical Tol= 0.01
Num of Std Step Trials= 20
Max Error Tol= 0.3
Flow Tol Ratio= 0.001
Split Flow NTrial= 30
Split Flow Tol= 0.02
Split Flow Ratio= 0.02
Log Output Level= 0
Friction Slope Method= 1
Unsteady Friction Slope Method= 2
Unsteady Bridges Friction Slope Method= 1
Parabolic Critical Depth
Global Vel Dist= 1 , 1 , 1
Global Log Level= 0
CheckData=True
Encroach Param=-1 ,0,0, 0
BEGIN DESCRIPTION:
Multiple Run
END DESCRIPTION:
Computation Interval=1HOUR
Output Interval=1HOUR
Run HTab= 0
Run UNet= 0
Run PostProcess= 0
Run WQNet= 0
UNET Theta= 1
UNET Theta Warmup= 1
UNET ZTol= 0.02
UNET ZSATol= 0.05
UNET MxIter= 20
UNET MaxInSteps= 0
UNET DtIC= 0
UNET DtMin= 0
UNET MaxCRTS= 20
UNET WFStab= 2
UNET SFStab= 1
UNET WFX= 1
UNET SFX= 1
UNET DSS MLevel= 4
UNET DZMax Abort= 100
UNET Convert EG Bridges= 0
UNET Use Existing IB Tables=-1
UNET Froude Reduction=False
UNET Froude Limit= 1
UNET Froude Power= 10
UNET Time Slicing=0,0, 5
UNET Junction Losses=0
Instantaneous Interval=1HOUR
Write IC File= 0
Write IC File at Sim End=0
Echo Input=False
Echo Parameters=False
Echo Output=False
Write Detailed= 0
WQ AD Non Conservative
WQ ULTIMATE=-1
WQ Max Comp Step=1HOUR
WQ Output Interval=15MIN
WQ Output Selected Increments= 0
WQ Output face flow=0
WQ Output face velocity=0
WQ Output face area=0
WQ Output face dispersion=0
WQ Output cell volume=0
WQ Output cell surface area=0
WQ Output cell continuity=0
WQ Output cumulative cell continuity=0
WQ Output face conc=0
WQ Output face dconc_dx=0
WQ Output face courant=0
WQ Output face peclet=0
WQ Output face adv mass=0
WQ Output face disp mass=0
WQ Output cell mass=0
WQ Output cell source sink temp=0
WQ Output cell source sink nsm=0
WQ Output MaxMinRange=-1
WQ Daily Max Min Mean=-1
WQ Daily Range=0
WQ Daily Time=0
WQ Create Restart=0
WQ Fixed Restart=0
WQ System Summary=0
WQ Use Fixed Temperature=0
Sorting and Armoring Iterations= 10
XS Update Threshold= 0.02
Hydraulics Update Threshold= 0.02
Energy Slope Method= 1
Volume Change Method= 0
XS Weighting Method= 0
Number of US Weighted Cross Sections= 1
Number of DS Weighted Cross Sections= 1
Upstream XS Weight=0.25
Main XS Weight=0.5
Downstream XS Weight=0.25
Number of DS XS's Weighted with US Boundary= 1
Upstream Boundary Weight= 1
Weight of XSs Associated with US Boundary= 0
Number of US XS's Weighted with DS Boundary= 1
Downstream Boundary Weight= 0.5
Weight of XSs Associated with DS Boundary= 0.5
Sediment Output Level= 4
Mass or Volume Output= 0
Output Increment Type= 1
Profile and TS Output Increment= 10
XS Output Flag= 0
XS Output Increment= 10
Disregard all LS=0
Disregard all Conn=0
Disregard all Breaches=0
Disregard all Pumps=0

--- Prairie Creek Trib E.f01 (steady flow) ---

Flow Title=Multiple
Number of Profiles=7
Profile Names=10-year,25-year,50-year,1pct_min,100-year,1pct_plu,500-year
River Rch & RM= Prairie Creek Tr,Reach-1,11233
     233     295     342     198     394     786     522
River Rch & RM= Prairie Creek Tr,Reach-1,9086
     529     701     838     497     992    1979    1388
River Rch & RM= Prairie Creek Tr,Reach-1,3582
     637     853    1027     614    1224    2443    1737
River Rch & RM= Prairie Creek Tr,Reach-1,2837
     679     910    1097     655    1306    2607    1853
Boundary for River Rch & Prof#=Prairie Creek Tr,Reach-1,1
Up Type=0
Dn Type=3
Dn Slope=0.005
Boundary for River Rch & Prof#=Prairie Creek Tr,Reach-1,2
Up Type=0
Dn Type=3
Dn Slope=0.005
Boundary for River Rch & Prof#=Prairie Creek Tr,Reach-1,3
Up Type=0
Dn Type=3
Dn Slope=0.005
Boundary for River Rch & Prof#=Prairie Creek Tr,Reach-1,4
Up Type=0
Dn Type=3
Dn Slope=0.005
Boundary for River Rch & Prof#=Prairie Creek Tr,Reach-1,5
Up Type=0
Dn Type=3
Dn Slope=0.005
Boundary for River Rch & Prof#=Prairie Creek Tr,Reach-1,6
Up Type=0
Dn Type=3
Dn Slope=0.005
Boundary for River Rch & Prof#=Prairie Creek Tr,Reach-1,7
Up Type=0
Dn Type=3
Dn Slope=0.005

--- Prairie Creek Trib E.g01 (geometry) ---

Geom Title=Existing Conditions

River Reach=Prairie Creek Tr,Reach-1
Reach XY= 30
      2706876.00      6817661.00      2706491.22      6817561.24
      2705936.71      6817760.28      2705524.45      6817514.75
      2705081.69      6817459.06      2704778.28      6817216.13
      2704665.95      6817249.89      2704083.48      6816567.06
      2704115.94      6816401.00      2703784.11      6816167.07
      2703720.47      6815858.58      2703433.68      6815617.52
      2703332.69      6815320.29      2703088.00      6815359.83
      2702983.02      6815170.01      2702831.56      6815208.74
      2702524.41      6815014.68      2702372.33      6815053.30
      2702274.58      6814914.04      2702131.63      6814959.25
      2701865.50      6814812.22      2701236.79      6814859.32
      2701170.64      6814612.95      2701029.64      6814703.83
      2700772.68      6814702.96      2700528.70      6814466.36
      2700311.87      6814447.64      2700209.53      6814144.27
      2699820.47      6813913.38      2698626.00      6813961.00

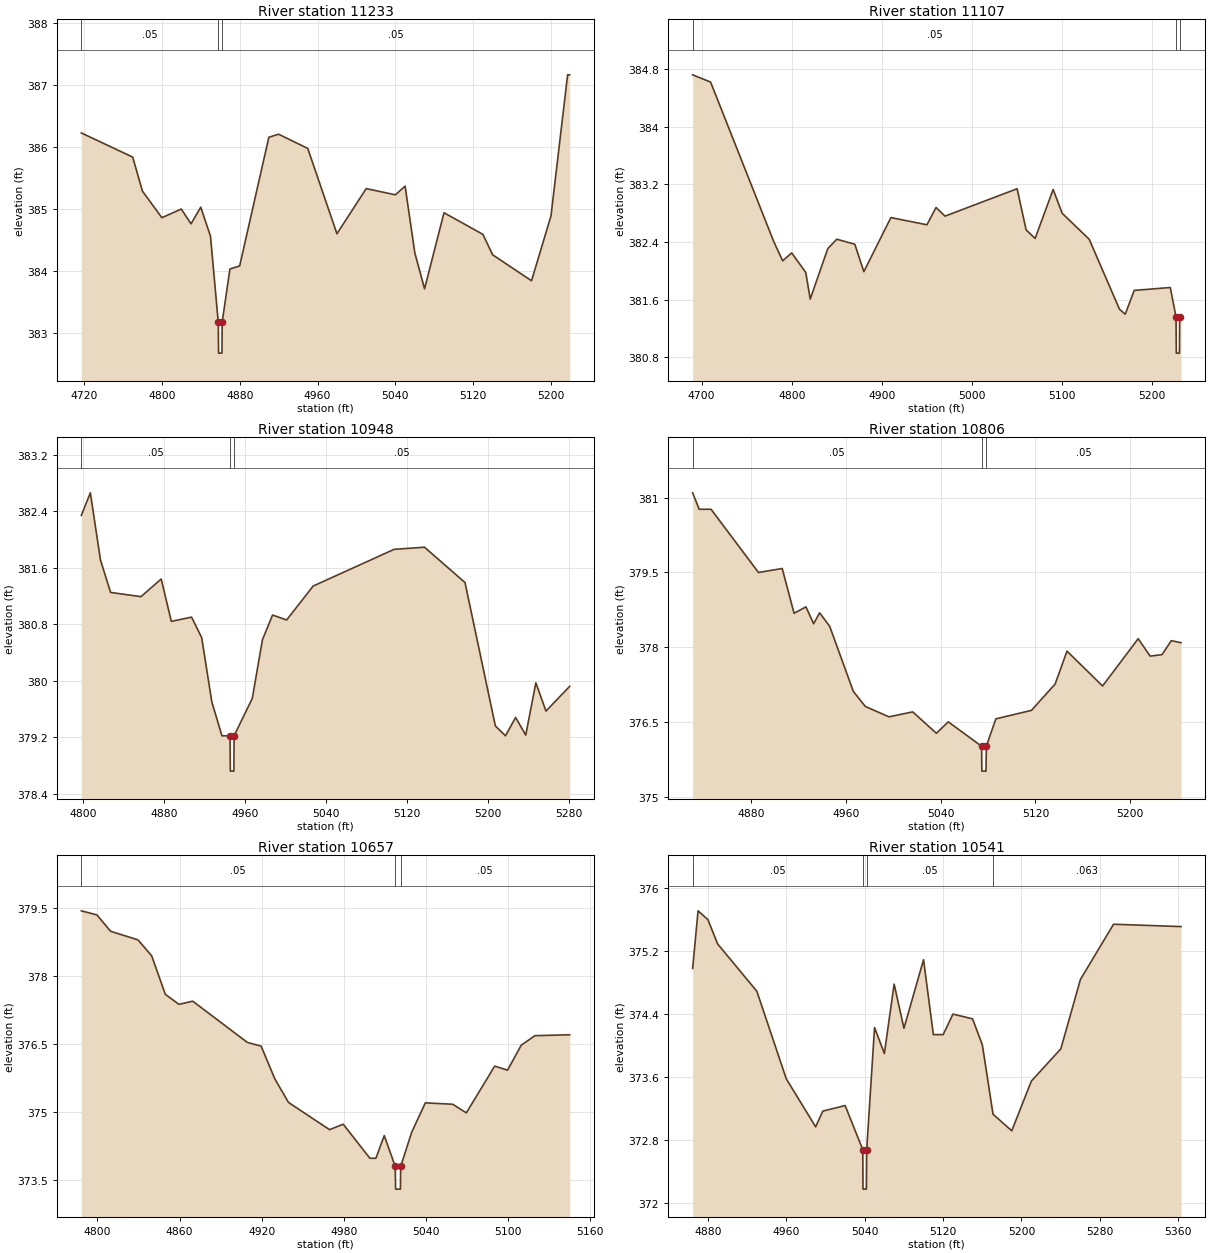
Type RM Length L Ch R = 1,11233,126,126,126
BEGIN DESCRIPTION:
Prairie Creek Trib E11233.452
END DESCRIPTION:
XS GIS Cut Line= 3
      2706827.75      6817378.24      2706820.28      6817661.04
      2706818.53      6817880.24
#Sta/Elev= 30
  4717.1  386.23  4769.9  385.84  4779.9  385.29  4799.9  384.86  4819.9  385.00
  4829.9  384.76  4839.9  385.03  4849.9  384.56  4857.9  383.17  4858.2  382.67
  4861.7  382.67  4861.9  383.17  4869.9  384.03  4879.9  384.08  4909.9  386.16
  4919.9  386.21  4949.9  385.98  4979.9  384.60  5010.0  385.33  5040.0  385.23
  5050.0  385.37  5060.0  384.29  5070.0  383.71  5090.0  384.94  5130.0  384.59
  5140.0  384.26  5180.0  383.84  5200.0  384.89  5217.1  387.17  5219.2  387.17
#Mann=3,-1,0
  4717.1    0.05       0  4857.9    0.05       0  4861.9    0.05       0
Bank Sta=4857.9,4861.9
Exp/Cntr=0.3,0.1

Type RM Length L Ch R = 1,11107,159,159,159
BEGIN DESCRIPTION:
Prairie Creek Trib E11107.41
END DESCRIPTION:
XS GIS Cut Line= 3
      2706705.62      6817351.13      2706694.20      6817662.50
      2706689.61      6817892.88
#Sta/Elev= 30
  4690.0  384.72  4709.9  384.62  4779.9  382.41  4789.9  382.14  4799.9  382.25
  4815.5  381.98  4820.5  381.61  4840.0  382.31  4850.0  382.44  4870.0  382.37
  4880.0  381.99  4910.0  382.74  4950.0  382.64  4960.1  382.88  4970.1  382.76
  5050.1  383.14  5060.1  382.57  5070.1  382.45  5090.1  383.13  5100.1  382.80
  5130.1  382.44  5163.7  381.47  5170.1  381.40  5180.1  381.73  5220.1  381.77
  5226.5  381.36  5226.8  380.86  5230.3  380.86  5230.5  381.36  5232.0  381.36
#Mann=3,-1,0
  4690.0    0.05       0  5226.5    0.05       0  5230.5    0.05       0
Bank Sta=5226.5,5230.5
Exp/Cntr=0.3,0.1

Type RM Length L Ch R = 1,10948,142,142,142
BEGIN DESCRIPTION:
Prairie Creek Trib E10947.98
END DESCRIPTION:
XS GIS Cut Line= 3
      2706575.27      6817362.08      2706571.83      6817564.90
      2706577.52      6817844.39
#Sta/Elev= 30
  4798.5  382.34  4807.4  382.66  4817.4  381.71  4827.4  381.25  4857.4  381.19
  4877.4  381.44  4887.4  380.84  4907.4  380.90  4917.4  380.61  4927.4  379.70
  4937.4  379.22  4945.4  379.22  4945.7  378.72  4949.2  378.72  4949.4  379.22
  4967.4  379.75  4977.4  380.58  4987.4  380.93  5001.3  380.86  5027.5  381.34
  5107.5  381.86  5137.5  381.89  5177.5  381.39  5207.5  379.36  5217.5  379.22
  5227.5  379.48  5237.5  379.23  5247.5  379.97  5257.5  379.57  5280.9  379.92
#Mann=3,-1,0
  4798.5    0.05       0  4945.4    0.05       0  4949.4    0.05       0
Bank Sta=4945.4,4949.4
Exp/Cntr=0.3,0.1

Type RM Length L Ch R = 1,10806,149,149,149
BEGIN DESCRIPTION:
Prairie Creek Trib E10806.16
END DESCRIPTION:
XS GIS Cut Line= 3
      2706439.39      6817425.52      2706442.07      6817598.31
      2706451.20      6817837.02
#Sta/Elev= 30
  4831.0  381.10  4836.5  380.77  4846.5  380.77  4886.5  379.50  4906.5  379.58
  4916.5  378.68  4926.5  378.81  4933.0  378.47  4938.0  378.69  4946.5  378.42
  4966.5  377.11  4976.5  376.81  4996.5  376.60  5016.5  376.70  5036.5  376.27
  5046.5  376.50  5074.6  376.01  5074.8  375.51  5078.3  375.51  5078.6  376.01
  5086.6  376.56  5116.6  376.73  5136.6  377.26  5146.6  377.92  5176.6  377.22
  5206.6  378.17  5216.7  377.82  5226.7  377.85  5234.5  378.13  5242.7  378.09
#Mann=3,-1,0
  4831.0    0.05       0  5074.6    0.05       0  5078.6    0.05       0
Bank Sta=5074.6,5078.6
Exp/Cntr=0.3,0.1

Type RM Length L Ch R = 1,10657,116,116,116
BEGIN DESCRIPTION:
Prairie Creek Trib E10657.16
END DESCRIPTION:
XS GIS Cut Line= 3
      2706319.83      6817449.59      2706318.61      6817664.92
      2706322.72      6817806.43
#Sta/Elev= 30
  4788.2  379.43  4799.6  379.34  4809.6  378.98  4829.6  378.79  4839.6  378.44
  4849.6  377.59  4859.6  377.37  4869.6  377.44  4909.6  376.53  4919.6  376.45
  4929.6  375.73  4939.6  375.21  4969.6  374.61  4979.6  374.73  4999.1  373.98
  5003.5  373.98  5009.6  374.48  5017.6  373.80  5017.9  373.30  5021.4  373.30
  5021.6  373.80  5029.6  374.55  5039.6  375.20  5059.6  375.17  5069.6  374.98
  5090.3  376.01  5099.7  375.92  5109.7  376.47  5119.7  376.68  5145.1  376.70
#Mann=3,-1,0
  4788.2    0.05       0  5017.6    0.05       0  5021.6    0.05       0
Bank Sta=5017.6,5021.6
Exp/Cntr=0.3,0.1

Type RM Length L Ch R = 1,10541,105,105,105
BEGIN DESCRIPTION:
Mapping XS 491a881a
END DESCRIPTION:
XS GIS Cut Line= 3
      2706202.37      6817525.46      2706202.24      6817660.50
      2706213.09      6818023.59
#Sta/Elev= 30
  4864.5  374.98  4870.0  375.71  4880.0  375.60  4890.0  375.29  4930.0  374.69
  4960.0  373.58  4990.0  372.97  4997.3  373.17  5020.1  373.24  5038.1  372.68
  5038.3  372.18  5041.8  372.18  5042.1  372.68  5050.1  374.23  5060.1  373.90
  5070.1  374.78  5080.1  374.22  5100.1  375.09  5110.1  374.14  5120.1  374.14
  5130.1  374.40  5150.1  374.34  5160.1  374.01  5171.0  373.13  5190.1  372.92
  5210.1  373.55  5240.2  373.96  5260.2  374.84  5294.0  375.54  5362.8  375.51
#Mann=4,-1,0
  4864.5    0.05       0  5038.1    0.05       0  5042.1    0.05       0
  5171.0   0.063       0
Bank Sta=5038.1,5042.1
Exp/Cntr=0.3,0.1

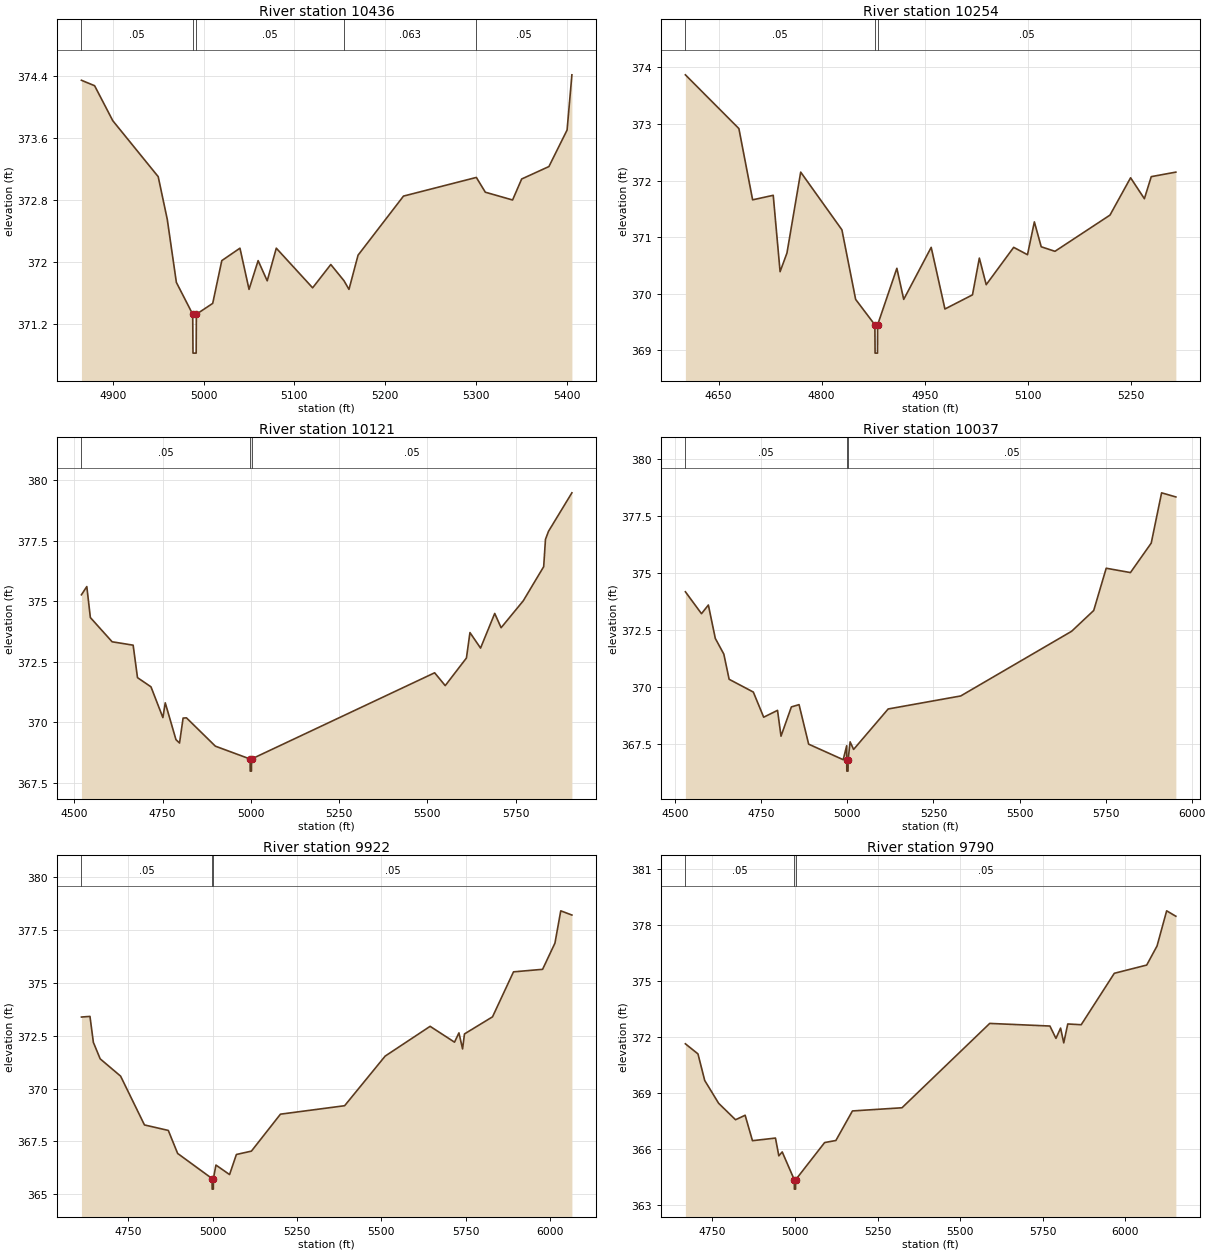
Type RM Length L Ch R = 1,10436,182,182,182
BEGIN DESCRIPTION:
Mapping XS 1bd2ae17
END DESCRIPTION:
XS GIS Cut Line= 3
      2706095.77      6817526.48      2706097.78      6817664.18
      2706093.04      6818066.34
#Sta/Elev= 30
  4865.6  374.34  4880.1  374.27  4900.1  373.82  4950.1  373.10  4960.1  372.55
  4970.1  371.74  4988.1  371.33  4988.4  370.83  4991.9  370.83  4992.1  371.33
  5010.1  371.47  5020.1  372.02  5040.1  372.18  5050.1  371.65  5060.1  372.02
  5070.1  371.76  5080.1  372.18  5120.1  371.67  5140.1  371.97  5154.7  371.76
  5160.1  371.65  5170.1  372.09  5220.1  372.85  5300.3  373.09  5310.2  372.90
  5340.2  372.80  5350.2  373.07  5380.2  373.23  5400.2  373.70  5405.5  374.41
#Mann=5,-1,0
  4865.6    0.05       0  4988.1    0.05       0  4992.1    0.05       0
  5154.7   0.063       0  5300.3    0.05       0
Bank Sta=4988.1,4992.1
Exp/Cntr=0.3,0.1

Type RM Length L Ch R = 1,10254,133,133,133
BEGIN DESCRIPTION:
Prairie Creek Trib E10254.19
END DESCRIPTION:
XS GIS Cut Line= 3
      2705960.37      6817363.12      2705953.06      6817765.58
      2705967.97      6818076.79
#Sta/Elev= 30
  4601.6  373.87  4679.5  372.92  4699.5  371.66  4729.5  371.74  4739.5  370.39
  4749.5  370.72  4769.5  372.15  4829.5  371.13  4849.5  369.90  4877.5  369.45
  4877.8  368.95  4881.3  368.95  4881.5  369.45  4909.5  370.45  4919.5  369.90
  4959.5  370.82  4979.5  369.73  5019.6  369.98  5029.6  370.63  5039.6  370.16
  5079.6  370.82  5099.7  370.69  5109.7  371.27  5119.7  370.83  5139.7  370.75
  5219.8  371.39  5249.8  372.05  5269.9  371.68  5279.9  372.07  5315.7  372.15
#Mann=3,-1,0
  4601.6    0.05       0  4877.5    0.05       0  4881.5    0.05       0
Bank Sta=4877.5,4881.5
Exp/Cntr=0.3,0.1

Type RM Length L Ch R = 1,10121,84,84,84
BEGIN DESCRIPTION:
Mapping XS a2d3ad5f
END DESCRIPTION:
XS GIS Cut Line= 4
      2705902.37      6817235.95      2705833.97      6817730.25
      2705851.53      6818443.80      2705886.58      6818615.99
#Sta/Elev= 30
  4520.5  375.26  4535.7  375.60  4545.8  374.32  4607.4  373.32  4666.9  373.18
  4679.2  371.84  4717.4  371.46  4751.1  370.19  4757.8  370.80  4788.1  369.28
  4798.2  369.14  4808.3  370.17  4817.8  370.18  4899.7  369.01  4998.0  368.48
  4998.3  367.98  5001.8  367.98  5002.0  368.48  5520.4  372.04  5550.4  371.51
  5610.4  372.65  5620.4  373.70  5650.4  373.06  5690.5  374.49  5708.6  373.90
  5771.2  375.01  5829.1  376.42  5834.2  377.55  5842.7  377.88  5909.0  379.47
#Mann=3,-1,0
  4520.5    0.05       0  4998.0    0.05       0  5002.0    0.05       0
Bank Sta=4998,5002
Exp/Cntr=0.3,0.1

Type RM Length L Ch R = 1,10037,115,115,115
BEGIN DESCRIPTION:
Mapping XS db925d32
END DESCRIPTION:
XS GIS Cut Line= 3
      2705801.30      6817224.44      2705742.83      6817853.67
      2705826.23      6818642.13
#Sta/Elev= 30
  4529.3  374.18  4576.1  373.22  4596.1  373.60  4616.2  372.14  4641.0  371.45
  4656.4  370.35  4726.7  369.79  4756.8  368.69  4797.0  368.99  4807.1  367.86
  4837.2  369.14  4859.5  369.24  4887.4  367.51  4987.8  366.83  4997.9  367.44
  4998.0  366.83  4998.3  366.33  5001.8  366.33  5002.0  366.83  5007.9  367.61
  5018.0  367.28  5118.4  369.05  5329.2  369.62  5651.3  372.45  5715.5  373.36
  5751.8  375.21  5822.2  375.02  5882.6  376.31  5912.7  378.51  5954.1  378.33
#Mann=3,-1,0
  4529.3    0.05       0  4998.0    0.05       0  5002.0    0.05       0
Bank Sta=4998,5002
Exp/Cntr=0.3,0.1

Type RM Length L Ch R = 1,9922,132,132,132
BEGIN DESCRIPTION:
Mapping XS 48f5faa3
END DESCRIPTION:
XS GIS Cut Line= 4
      2705731.11      6817225.95      2705659.84      6817732.41
      2705630.54      6818221.47      2705800.27      6818641.60
#Sta/Elev= 30
  4610.6  373.39  4635.9  373.42  4646.0  372.19  4666.2  371.41  4726.8  370.59
  4797.5  368.28  4868.2  368.02  4895.9  366.93  4998.0  365.74  4998.3  365.24
  5001.8  365.24  5002.0  365.74  5009.5  366.38  5049.9  365.93  5070.1  366.88
  5114.7  367.04  5200.8  368.79  5391.1  369.19  5511.3  371.54  5644.6  372.95
  5717.0  372.20  5730.1  372.64  5740.9  371.88  5746.5  372.59  5829.7  373.40
  5891.9  375.53  5978.2  375.65  6014.8  376.89  6032.1  378.42  6065.1  378.22
#Mann=3,-1,0
  4610.6    0.05       0  4998.0    0.05       0  5002.0    0.05       0
Bank Sta=4998,5002
Exp/Cntr=0.3,0.1

Type RM Length L Ch R = 1,9790,117,117,117
BEGIN DESCRIPTION:
Mapping XS a7b6592a
END DESCRIPTION:
XS GIS Cut Line= 4
      2705629.83      6817223.63      2705547.66      6817638.04
      2705557.94      6818100.45      2705791.59      6818652.22
#Sta/Elev= 30
  4668.4  371.64  4706.5  371.10  4726.9  369.68  4769.0  368.46  4820.2  367.58
  4849.2  367.82  4871.4  366.46  4941.0  366.60  4951.2  365.65  4961.4  365.86
  4998.0  364.37  4998.3  363.87  5001.8  363.87  5002.0  364.37  5089.8  366.36
  5123.8  366.47  5173.9  368.05  5323.9  368.22  5589.4  372.73  5771.5  372.59
  5789.8  371.93  5803.8  372.48  5813.4  371.69  5825.5  372.70  5866.2  372.66
  5966.4  375.41  6064.4  375.85  6095.7  376.87  6124.8  378.75  6152.6  378.46
#Mann=3,-1,0
  4668.4    0.05       0  4998.0    0.05       0  5002.0    0.05       0
Bank Sta=4998,5002
Exp/Cntr=0.3,0.1

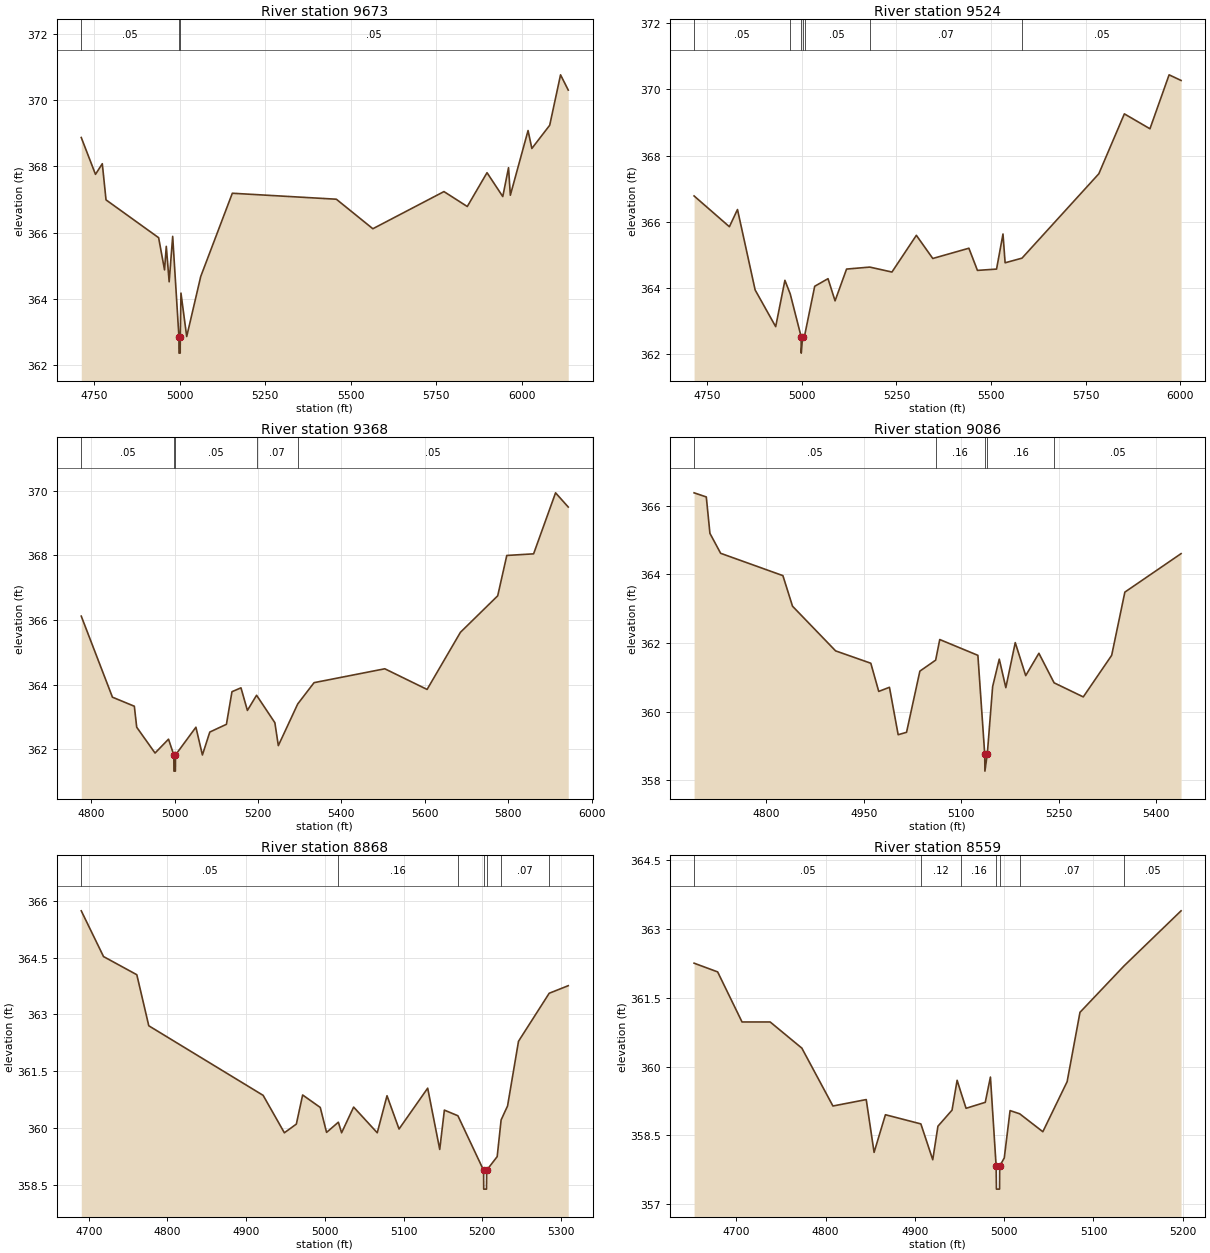
Type RM Length L Ch R = 1,9673,149,149,149
BEGIN DESCRIPTION:
Mapping XS 64b0dd31
END DESCRIPTION:
XS GIS Cut Line= 3
      2705525.74      6817230.47      2705421.90      6817684.15
      2705115.48      6818592.33
#Sta/Elev= 30
  4712.5  368.87  4754.1  367.76  4774.0  368.08  4784.9  366.99  4938.7  365.85
  4956.0  364.88  4961.1  365.59  4969.5  364.52  4979.8  365.89  4998.0  362.87
  4998.3  362.37  5001.8  362.37  5002.0  362.87  5004.0  364.18  5020.8  362.87
  5061.8  364.68  5154.2  367.19  5458.3  367.01  5565.1  366.12  5773.0  367.24
  5841.2  366.79  5898.9  367.81  5945.0  367.09  5961.8  367.96  5967.1  367.13
  6018.9  369.08  6030.0  368.54  6082.2  369.24  6113.9  370.76  6136.4  370.30
#Mann=3,-1,0
  4712.5    0.05       0  4998.0    0.05       0  5002.0    0.05       0
Bank Sta=4998,5002
Exp/Cntr=0.3,0.1

Type RM Length L Ch R = 1,9524,156,156,156
BEGIN DESCRIPTION:
Mapping XS 2f0bad9f
END DESCRIPTION:
XS GIS Cut Line= 3
      2705419.14      6817234.15      2705162.61      6817889.45
      2704906.49      6818413.16
#Sta/Elev= 30
  4715.2  366.78  4808.5  365.85  4829.9  366.37  4876.5  363.94  4930.8  362.83
  4955.2  364.23  4969.2  363.82  4998.0  362.53  4998.3  362.03  5002.0  362.53
  5007.8  362.59  5033.9  364.05  5069.1  364.28  5087.7  363.61  5118.1  364.57
  5179.4  364.63  5238.0  364.48  5302.5  365.59  5345.9  364.89  5441.3  365.20
  5463.9  364.53  5514.4  364.57  5531.4  365.63  5537.0  364.76  5581.6  364.90
  5784.6  367.45  5852.1  369.26  5919.7  368.81  5970.3  370.44  6001.9  370.27
#Mann=7,-1,0
  4715.2    0.05       0  4969.2    0.07       0  4998.0    0.07       0
  5002.0    0.07       0  5007.8    0.05       0  5179.4    0.07       0
  5581.6    0.05       0
Bank Sta=4998,5002
Exp/Cntr=0.3,0.1

Type RM Length L Ch R = 1,9368,282,282,282
BEGIN DESCRIPTION:
Mapping XS 799093d0
END DESCRIPTION:
XS GIS Cut Line= 3
      2705292.02      6817225.15      2705145.54      6817497.29
      2704708.17      6818236.66
#Sta/Elev= 30
  4776.0  366.12  4850.8  363.61  4903.3  363.33  4909.0  362.68  4953.0  361.88
  4985.3  362.31  4998.0  361.82  4998.3  361.32  5001.8  361.32  5002.0  361.82
  5051.0  362.68  5066.6  361.82  5084.3  362.53  5124.2  362.77  5137.5  363.78
  5159.1  363.90  5174.5  363.20  5196.5  363.67  5240.4  362.82  5248.7  362.11
  5295.2  363.40  5334.4  364.06  5504.1  364.49  5605.5  363.85  5685.5  365.62
  5774.9  366.75  5796.7  368.00  5861.0  368.05  5913.7  369.94  5944.1  369.50
#Mann=5,-1,0
  4776.0    0.05       0  4998.0    0.05       0  5002.0    0.05       0
  5196.5    0.07       0  5295.2    0.05       0
Bank Sta=4998,5002
Exp/Cntr=0.3,0.1

Type RM Length L Ch R = 1,9086,218,218,218
BEGIN DESCRIPTION:
Prairie Creek Trib E9085.58
END DESCRIPTION:
XS GIS Cut Line= 3
      2705247.35      6817217.19      2704966.23      6817363.18
      2704541.03      6817443.58
#Sta/Elev= 30
  4688.6  366.37  4707.4  366.25  4713.0  365.19  4729.5  364.61  4825.3  363.96
  4840.1  363.07  4906.4  361.77  4960.6  361.41  4972.8  360.59  4989.3  360.71
  5002.7  359.33  5015.6  359.40  5036.1  361.18  5060.4  361.50  5066.7  362.10
  5125.4  361.64  5135.9  358.77  5136.2  358.27  5139.9  358.77  5148.1  360.73
  5158.3  361.53  5168.4  360.70  5182.9  362.01  5199.0  361.05  5219.3  361.70
  5242.7  360.84  5287.6  360.43  5331.3  361.64  5351.6  363.48  5438.1  364.60
#Mann=5,-1,0
  4688.6    0.05       0  5060.4    0.16       0  5135.9    0.05       0
  5139.9    0.16       0  5242.7    0.05       0
Bank Sta=5135.9,5139.9
Exp/Cntr=0.3,0.1

Type RM Length L Ch R = 1,8868,309,309,309
BEGIN DESCRIPTION:
Prairie Creek Trib E8868.29
END DESCRIPTION:
XS GIS Cut Line= 3
      2705062.60      6817069.22      2704800.01      6817238.18
      2704540.79      6817401.82
#Sta/Elev= 30
  4690.5  365.74  4718.8  364.53  4761.1  364.05  4776.3  362.70  4921.6  360.86
  4948.6  359.87  4963.8  360.10  4971.8  360.87  4994.2  360.54  5002.2  359.88
  5017.2  360.15  5021.3  359.87  5036.6  360.55  5066.6  359.87  5079.0  360.85
  5094.3  359.97  5130.7  361.05  5146.0  359.43  5151.9  360.47  5169.1  360.32
  5201.7  358.88  5201.9  358.38  5205.4  358.38  5205.7  358.88  5219.0  359.24
  5224.0  360.21  5232.2  360.58  5246.1  362.29  5285.1  363.56  5309.3  363.76
#Mann=7,-1,0
  4690.5    0.05       0  5017.2    0.16       0  5169.1    0.05       0
  5201.7    0.05       0  5205.7    0.05       0  5224.0    0.07       0
  5285.1    0.05       0
Bank Sta=5201.7,5205.7
Exp/Cntr=0.3,0.1

Type RM Length L Ch R = 1,8559,249,249,249
BEGIN DESCRIPTION:
Prairie Creek Trib E8559.02
END DESCRIPTION:
XS GIS Cut Line= 3
      2704860.38      6816970.77      2704558.68      6817145.77
      2704405.94      6817269.58
#Sta/Elev= 30
  4652.7  362.25  4679.1  362.06  4706.4  360.97  4737.9  360.97  4773.4  360.40
  4808.2  359.14  4845.5  359.28  4854.3  358.13  4867.0  358.95  4906.7  358.75
  4920.0  357.97  4925.8  358.70  4941.6  359.05  4947.3  359.70  4951.5  359.44
  4957.3  359.09  4978.8  359.22  4984.6  359.77  4991.0  357.83  4991.3  357.33
  4994.8  357.33  4995.0  357.83  5000.1  358.01  5006.6  359.04  5017.4  358.97
  5043.3  358.58  5070.5  359.67  5084.9  361.18  5134.2  362.19  5198.1  363.39
#Mann=7,-1,0
  4652.7    0.05       0  4906.7    0.12       0  4951.5    0.16       0
  4991.0    0.07       0  4995.0    0.16       0  5017.4    0.07       0
  5134.2    0.05       0
Bank Sta=4991,4995
Exp/Cntr=0.3,0.1

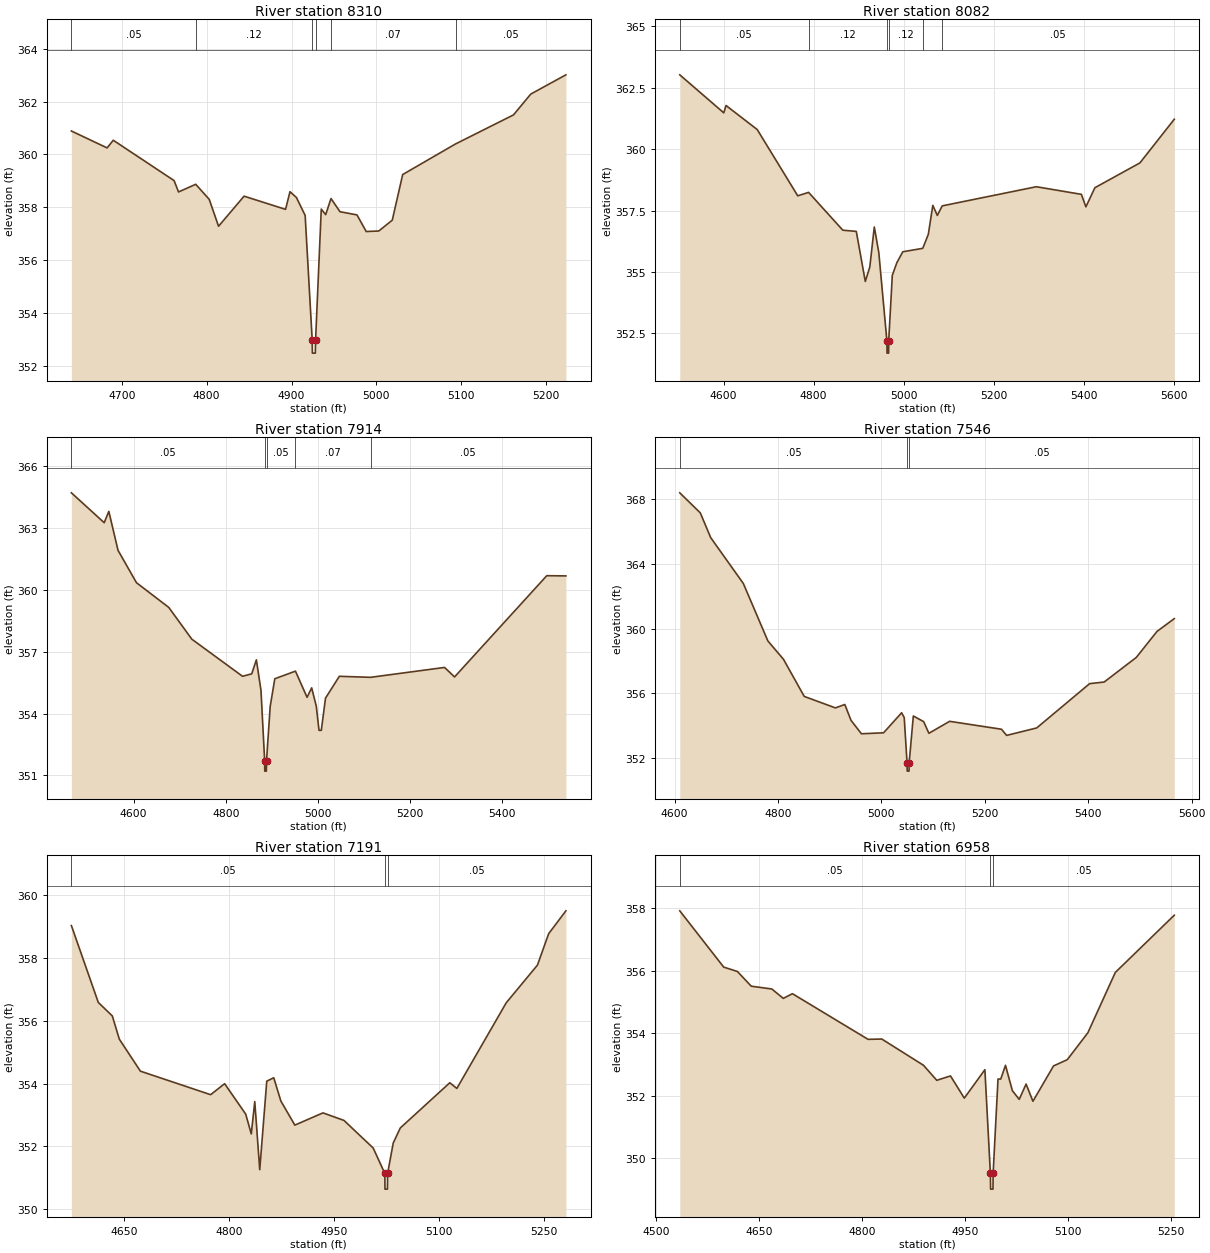
Type RM Length L Ch R = 1,8310,228,228,228
BEGIN DESCRIPTION:
Prairie Creek Trib E8310.1
END DESCRIPTION:
XS GIS Cut Line= 3
      2704744.05      6816896.71      2704391.53      6816980.93
      2704175.50      6817025.38
#Sta/Elev= 30
  4640.5  360.89  4682.6  360.25  4689.9  360.54  4761.6  359.01  4766.8  358.58
  4787.1  358.87  4803.0  358.30  4814.0  357.28  4844.1  358.42  4893.0  357.92
  4898.2  358.59  4905.8  358.37  4916.1  357.69  4924.4  352.97  4924.6  352.47
  4928.1  352.47  4928.4  352.97  4935.1  357.93  4940.3  357.72  4946.6  358.33
  4957.2  357.83  4977.2  357.71  4988.1  357.08  5002.9  357.10  5018.8  357.51
  5031.1  359.24  5093.4  360.40  5161.7  361.50  5182.1  362.29  5223.5  363.02
#Mann=6,-1,0
  4640.5    0.05       0  4787.1    0.12       0  4924.4    0.07       0
  4928.4    0.12       0  4946.6    0.07       0  5093.4    0.05       0
Bank Sta=4924.4,4928.4
Exp/Cntr=0.3,0.1

Type RM Length L Ch R = 1,8082,168,168,168
BEGIN DESCRIPTION:
Prairie Creek Trib E8081.56
END DESCRIPTION:
XS GIS Cut Line= 3
      2704798.05      6816798.49      2704301.03      6816785.92
      2703699.57      6816777.46
#Sta/Elev= 30
  4502.8  363.03  4600.6  361.48  4605.6  361.78  4674.9  360.80  4764.9  358.10
  4789.0  358.24  4865.0  356.70  4895.0  356.65  4915.0  354.61  4925.0  355.20
  4935.0  356.83  4945.0  355.79  4963.0  352.19  4963.3  351.69  4966.8  351.69
  4967.0  352.19  4975.0  354.86  4985.0  355.37  4998.3  355.82  5042.7  355.96
  5055.0  356.53  5065.0  357.71  5075.0  357.30  5085.9  357.69  5295.0  358.47
  5395.1  358.16  5405.1  357.65  5425.1  358.43  5525.1  359.44  5601.5  361.22
#Mann=6,-1,0
  4502.8    0.05       0  4789.0    0.12       0  4963.0    0.07       0
  4967.0    0.12       0  5042.7    0.07       0  5085.9    0.05       0
Bank Sta=4963,4967
Exp/Cntr=0.3,0.1

Type RM Length L Ch R = 1,7914,368,368,368
BEGIN DESCRIPTION:
Prairie Creek Trib E7914.02
END DESCRIPTION:
XS GIS Cut Line= 3
      2704717.24      6816662.88      2704179.13      6816667.56
      2703644.47      6816664.53
#Sta/Elev= 30
  4465.2  364.71  4536.4  363.26  4546.4  363.81  4566.4  361.92  4606.4  360.35
  4676.5  359.15  4726.5  357.61  4836.5  355.81  4856.5  355.93  4866.5  356.61
  4876.5  355.13  4884.5  351.71  4884.7  351.21  4888.2  351.21  4888.5  351.71
  4896.5  354.35  4906.5  355.69  4951.3  356.06  4976.5  354.79  4986.5  355.25
  4996.5  354.36  5002.4  353.19  5007.4  353.19  5016.5  354.75  5046.5  355.81
  5114.1  355.76  5274.7  356.24  5296.5  355.78  5496.5  360.69  5538.0  360.68
#Mann=5,-1,0
  4465.2    0.05       0  4884.5    0.07       0  4888.5    0.05       0
  4951.3    0.07       0  5114.1    0.05       0
Bank Sta=4884.5,4888.5
Exp/Cntr=0.3,0.1

Type RM Length L Ch R = 1,7546,355,355,355
BEGIN DESCRIPTION:
Prairie Creek Trib E7546.07
END DESCRIPTION:
XS GIS Cut Line= 3
      2704475.55      6816333.99      2704083.26      6816373.15
      2703522.75      6816416.13
#Sta/Elev= 30
  4610.0  368.39  4649.7  367.15  4669.8  365.62  4733.0  362.78  4780.4  359.23
  4810.5  358.10  4850.7  355.80  4911.0  355.09  4929.2  355.30  4941.2  354.32
  4961.3  353.49  5004.2  353.55  5039.1  354.79  5044.1  354.49  5049.6  351.68
  5049.9  351.18  5053.4  351.18  5053.6  351.68  5061.7  354.59  5081.7  354.24
  5091.8  353.52  5131.9  354.26  5232.2  353.77  5242.2  353.39  5300.3  353.85
  5402.7  356.59  5430.8  356.69  5492.9  358.21  5533.0  359.82  5566.4  360.61
#Mann=3,-1,0
  4610.0    0.05       0  5049.6    0.05       0  5053.6    0.05       0
Bank Sta=5049.6,5053.6
Exp/Cntr=0.3,0.1

Type RM Length L Ch R = 1,7191,233,233,233
BEGIN DESCRIPTION:
Prairie Creek Trib E7191.04
END DESCRIPTION:
XS GIS Cut Line= 3
      2704224.32      6816160.55      2703798.10      6816185.96
      2703521.62      6816221.26
#Sta/Elev= 30
  4575.2  359.04  4613.6  356.59  4633.6  356.16  4643.6  355.42  4673.7  354.40
  4773.9  353.65  4793.9  354.00  4824.0  353.03  4831.9  352.40  4836.9  353.43
  4844.0  351.26  4854.0  354.08  4864.0  354.19  4874.1  353.45  4894.1  352.68
  4934.2  353.07  4964.2  352.83  5005.9  351.95  5022.5  351.14  5022.7  350.64
  5026.2  350.64  5026.5  351.14  5034.5  352.11  5044.6  352.59  5115.2  354.03
  5125.3  353.85  5195.8  356.58  5240.3  357.78  5256.3  358.78  5280.9  359.51
#Mann=3,-1,0
  4575.2    0.05       0  5022.5    0.05       0  5026.5    0.05       0
Bank Sta=5022.5,5026.5
Exp/Cntr=0.3,0.1

Type RM Length L Ch R = 1,6958,96,96,96
BEGIN DESCRIPTION:
Prairie Creek Trib E6958.23
END DESCRIPTION:
XS GIS Cut Line= 3
      2704219.93      6816013.69      2703752.92      6815990.12
      2703500.14      6815988.27
#Sta/Elev= 30
  4534.7  357.91  4598.7  356.11  4618.7  355.97  4638.8  355.50  4668.8  355.41
  4685.5  355.11  4698.8  355.26  4809.0  353.80  4829.0  353.81  4889.8  352.97
  4909.1  352.49  4929.1  352.63  4949.2  351.92  4979.2  352.83  4987.2  349.51
  4987.5  349.01  4991.0  349.01  4991.2  349.51  4998.3  352.53  5002.3  352.53
  5009.2  352.97  5019.2  352.16  5029.2  351.88  5039.2  352.37  5049.2  351.82
  5079.2  352.95  5099.2  353.15  5129.2  354.01  5169.2  355.94  5255.1  357.77
#Mann=3,-1,0
  4534.7    0.05       0  4987.2    0.05       0  4991.2    0.05       0
Bank Sta=4987.2,4991.2
Exp/Cntr=0.3,0.1

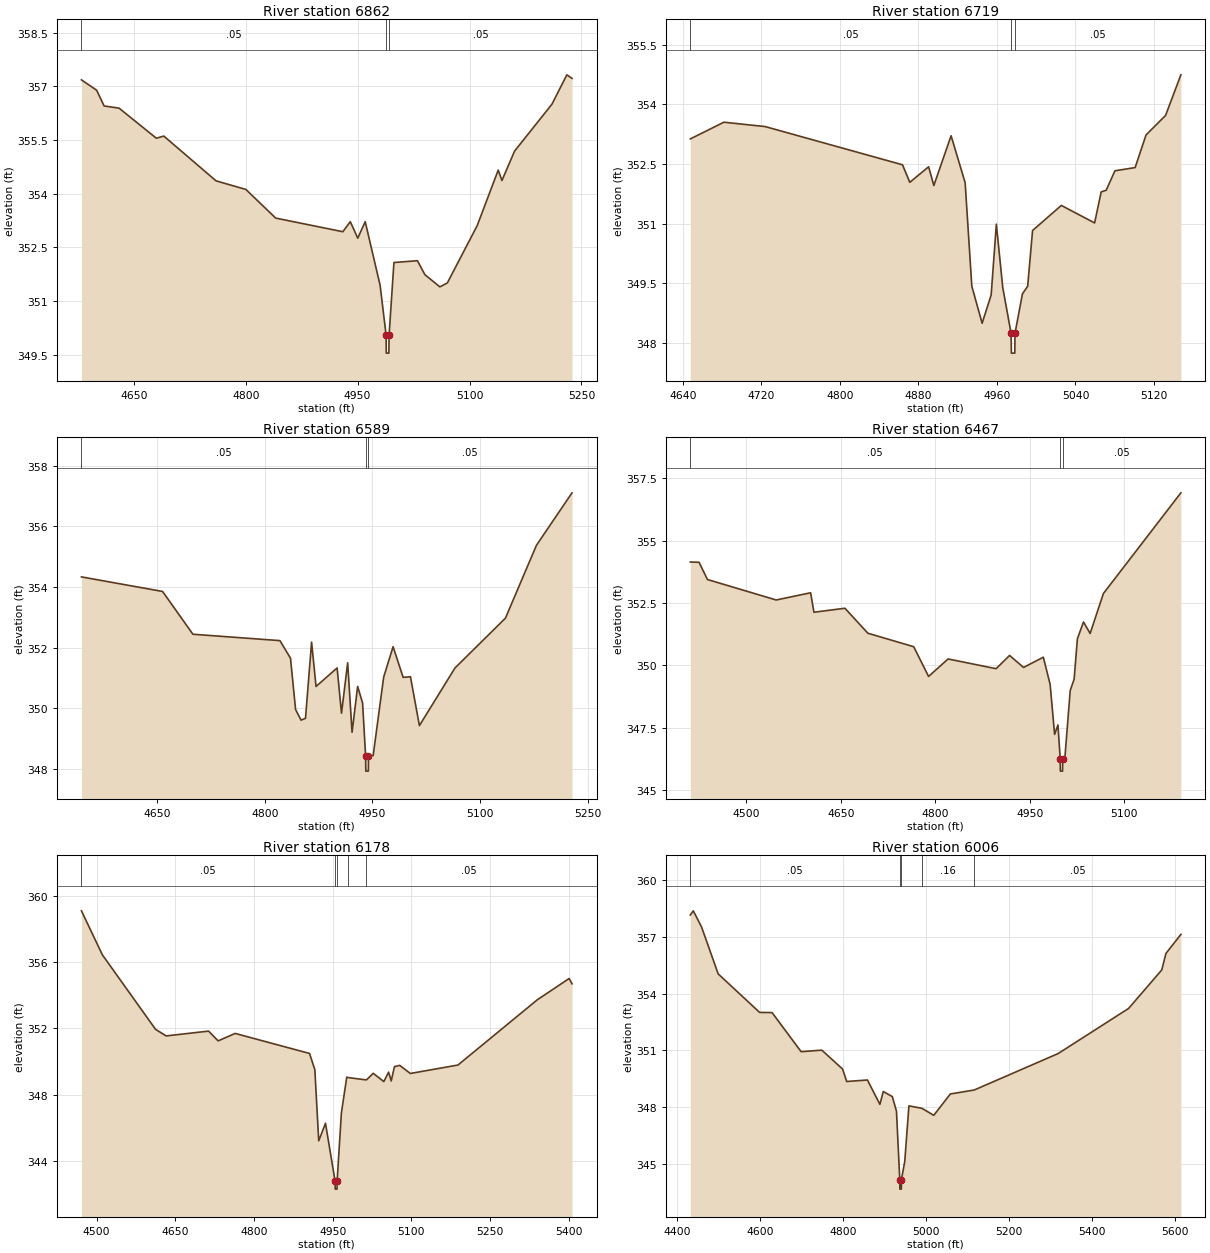
Type RM Length L Ch R = 1,6862,143,143,143
BEGIN DESCRIPTION:
Prairie Creek Trib E6862.1
END DESCRIPTION:
XS GIS Cut Line= 3
      2704146.36      6815901.62      2703724.01      6815903.74
      2703489.13      6815890.68
#Sta/Elev= 30
  4579.8  357.18  4600.2  356.89  4610.2  356.45  4630.2  356.39  4680.2  355.55
  4690.2  355.61  4760.2  354.36  4800.2  354.12  4840.2  353.32  4930.2  352.94
  4940.2  353.22  4950.2  352.76  4960.2  353.22  4980.2  351.44  4988.2  350.05
  4988.4  349.55  4991.9  349.55  4992.2  350.05  4998.7  352.08  5030.2  352.13
  5040.2  351.74  5060.3  351.40  5070.3  351.51  5110.3  353.11  5138.5  354.66
  5143.5  354.37  5160.4  355.19  5210.5  356.50  5230.5  357.32  5237.4  357.22
#Mann=3,-1,0
  4579.8    0.05       0  4988.2    0.05       0  4992.2    0.05       0
Bank Sta=4988.2,4992.2
Exp/Cntr=0.3,0.1

Type RM Length L Ch R = 1,6719,130,130,130
BEGIN DESCRIPTION:
Prairie Creek Trib E6719.45
END DESCRIPTION:
XS GIS Cut Line= 3
      2703988.53      6815679.39      2703653.25      6815789.14
      2703510.93      6815826.00
#Sta/Elev= 30
  4647.6  353.13  4681.8  353.55  4723.9  353.44  4863.8  352.48  4871.2  352.04
  4890.4  352.43  4895.7  351.96  4913.3  353.21  4927.6  352.03  4934.4  349.43
  4944.9  348.50  4954.1  349.21  4959.4  350.99  4965.9  349.40  4974.4  348.25
  4974.7  347.75  4978.2  347.75  4978.4  348.25  4986.0  349.24  4991.3  349.43
  4996.3  350.83  5025.6  351.46  5059.5  351.02  5066.2  351.80  5071.3  351.84
  5080.2  352.33  5100.8  352.41  5111.9  353.23  5131.8  353.72  5147.4  354.74
#Mann=3,-1,0
  4647.6    0.05       0  4974.4    0.05       0  4978.4    0.05       0
Bank Sta=4974.4,4978.4
Exp/Cntr=0.3,0.1

Type RM Length L Ch R = 1,6589,122,122,122
BEGIN DESCRIPTION:
Prairie Creek Trib E6588.95
END DESCRIPTION:
XS GIS Cut Line= 3
      2703861.64      6815309.42      2703592.31      6815680.60
      2703450.84      6815855.82
#Sta/Elev= 30
  4544.4  354.33  4657.5  353.85  4699.8  352.44  4821.1  352.23  4835.8  351.65
  4842.9  349.96  4850.5  349.61  4856.7  349.67  4865.2  352.18  4871.4  350.72
  4900.8  351.33  4906.9  349.84  4915.5  351.50  4921.6  349.21  4929.4  350.72
  4936.3  350.17  4940.5  348.43  4940.8  347.93  4944.3  347.93  4944.5  348.43
  4951.0  348.44  4965.7  351.03  4978.8  352.03  4992.8  351.02  5003.0  351.04
  5015.5  349.43  5065.1  351.33  5135.4  352.97  5178.6  355.37  5228.2  357.10
#Mann=3,-1,0
  4544.4    0.05       0  4940.5    0.05       0  4944.5    0.05       0
Bank Sta=4940.5,4944.5
Exp/Cntr=0.3,0.1

Type RM Length L Ch R = 1,6467,289,289,289
BEGIN DESCRIPTION:
Prairie Creek Trib E6467.49
END DESCRIPTION:
XS GIS Cut Line= 3
      2703689.81      6815108.04      2703477.01      6815659.59
      2703418.02      6815837.81
#Sta/Elev= 30
  4410.9  354.14  4424.8  354.13  4438.1  353.44  4547.3  352.62  4601.9  352.91
  4607.2  352.13  4656.4  352.29  4692.8  351.29  4765.6  350.75  4789.2  349.56
  4820.2  350.26  4896.4  349.87  4917.8  350.40  4940.0  349.92  4971.4  350.33
  4982.2  349.24  4989.3  347.24  4994.6  347.62  4998.2  346.27  4998.4  345.77
  5001.9  345.77  5002.2  346.27  5005.5  346.27  5014.1  349.00  5020.3  349.45
  5025.5  351.07  5035.2  351.74  5045.7  351.28  5066.8  352.88  5189.8  356.91
#Mann=3,-1,0
  4410.9    0.05       0  4998.2    0.05       0  5002.2    0.05       0
Bank Sta=4998.2,5002.2
Exp/Cntr=0.3,0.1

Type RM Length L Ch R = 1,6178,172,172,172
BEGIN DESCRIPTION:
Prairie Creek Trib E6177.13
END DESCRIPTION:
XS GIS Cut Line= 3
      2703492.27      6814871.59      2703408.74      6815397.92
      2703353.75      6815796.32
#Sta/Elev= 30
  4471.1  359.11  4511.0  356.45  4612.3  351.95  4632.5  351.55  4713.5  351.84
  4731.6  351.25  4764.1  351.70  4905.9  350.49  4916.0  349.51  4923.4  345.21
  4936.3  346.27  4954.5  342.79  4954.8  342.29  4958.3  342.29  4958.5  342.79
  4966.6  346.89  4976.8  349.06  4979.9  349.03  5014.3  348.89  5027.3  349.29
  5047.5  348.79  5056.6  349.36  5061.6  348.83  5067.7  349.69  5077.8  349.77
  5098.0  349.28  5188.8  349.79  5340.3  353.74  5400.8  355.02  5406.2  354.70
#Mann=5,-1,0
  4471.1    0.05       0  4954.5    0.07       0  4958.5    0.05       0
  4979.9    0.16       0  5014.3    0.05       0
Bank Sta=4954.5,4958.5
Exp/Cntr=0.3,0.1

Type RM Length L Ch R = 1,6006,94,94,94
BEGIN DESCRIPTION:
Prairie Creek Trib E5992.93
END DESCRIPTION:
XS GIS Cut Line= 3
      2703288.44      6814783.78      2703279.41      6815352.61
      2703282.19      6815967.10
#Sta/Elev= 30
  4431.1  358.17  4438.3  358.39  4458.3  357.53  4498.3  355.05  4598.3  353.01
  4628.3  353.00  4698.4  350.93  4748.4  351.01  4798.4  350.01  4808.4  349.35
  4858.4  349.43  4888.4  348.14  4896.6  348.82  4918.4  348.55  4928.4  347.78
  4936.4  344.15  4936.6  343.65  4940.1  343.65  4940.4  344.15  4948.4  345.12
  4958.4  348.06  4989.8  347.93  5018.4  347.56  5058.4  348.69  5116.1  348.90
  5318.4  350.83  5488.4  353.22  5568.4  355.26  5578.4  356.13  5614.5  357.14
#Mann=5,-1,0
  4431.1    0.05       0  4936.4    0.07       0  4940.4    0.05       0
  4989.8    0.16       0  5116.1    0.05       0
Bank Sta=4936.4,4940.4
Exp/Cntr=0.3,0.1