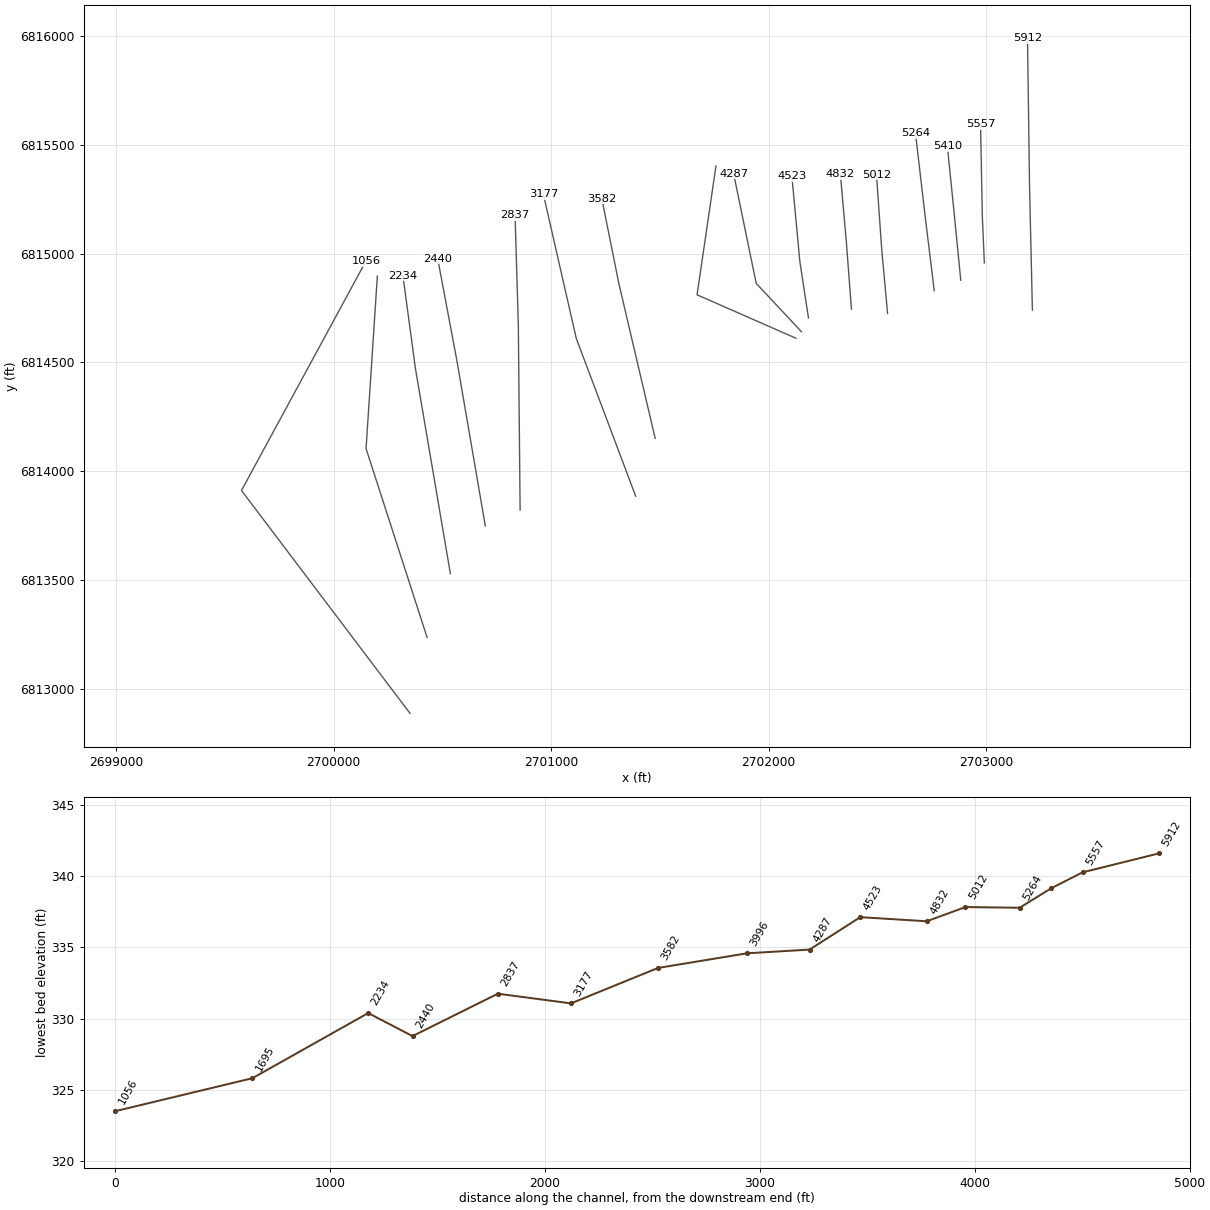
HEC-RAS study Prairie Creek Trib E.prj: Prairie Creek Trib E Base Level Engineering

--- Prairie Creek Trib E.g01 (geometry) --- (continued)

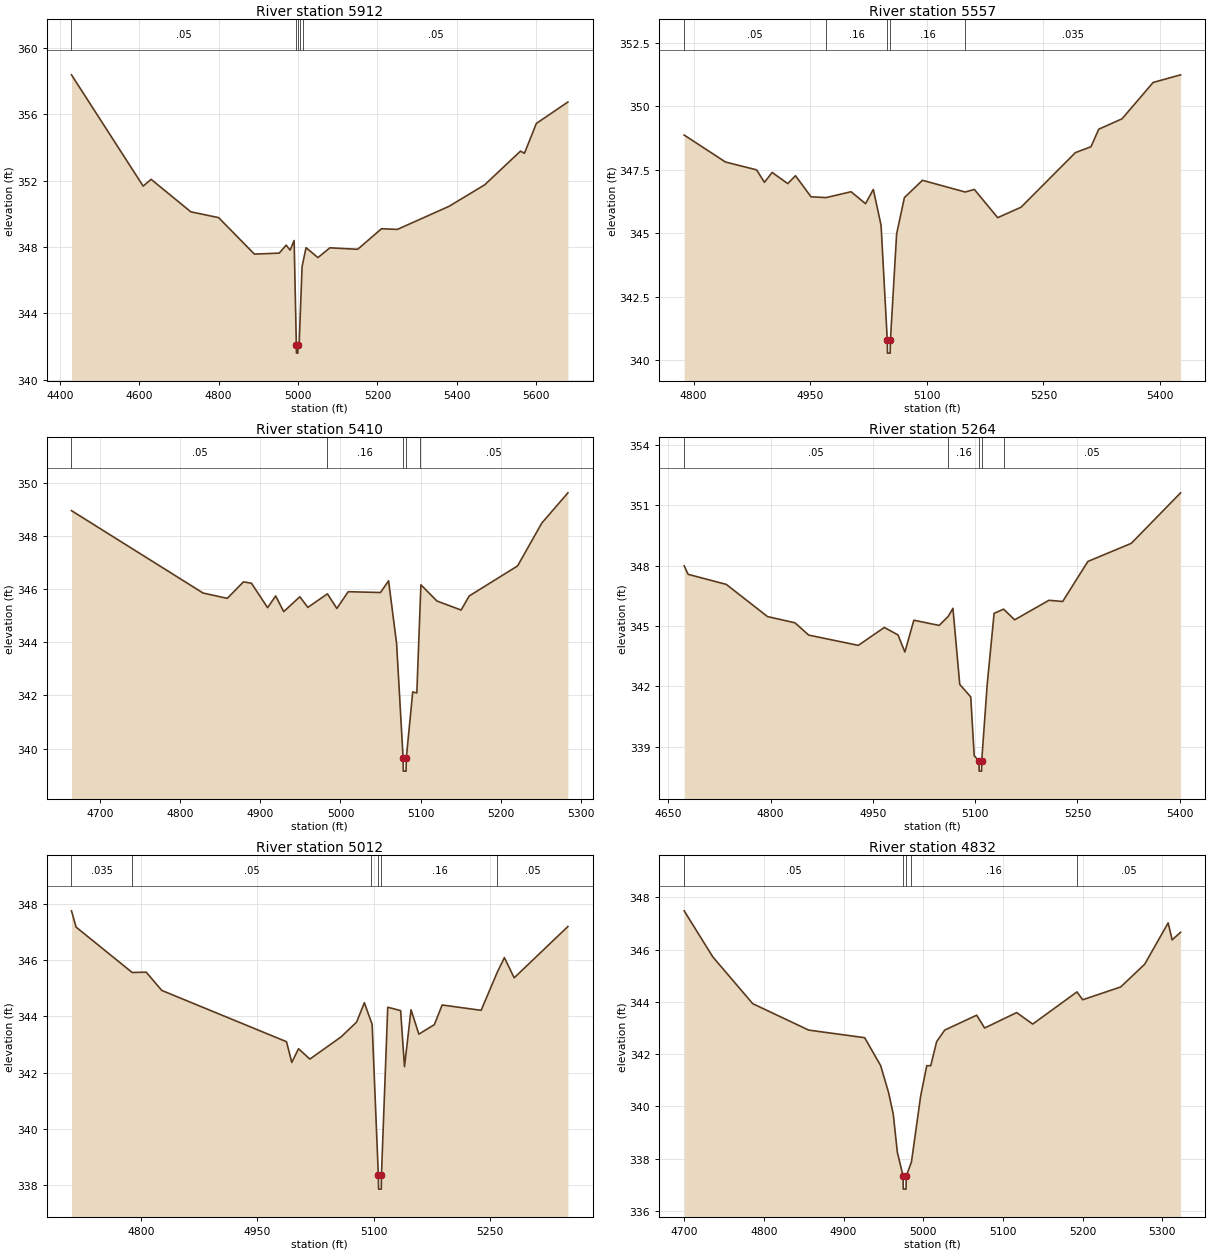
Type RM Length L Ch R = 1,5912,355,355,355
BEGIN DESCRIPTION:
Prairie Creek Trib E5911.86
END DESCRIPTION:
XS GIS Cut Line= 3
      2703212.97      6814740.57      2703199.84      6815311.34
      2703190.54      6815990.36
#Sta/Elev= 30
  4429.7  358.39  4610.2  351.68  4630.2  352.09  4730.2  350.13  4800.2  349.78
  4890.3  347.58  4952.7  347.64  4970.3  348.12  4980.3  347.82  4990.3  348.40
  4995.9  342.11  4996.2  341.61  4999.7  341.61  4999.9  342.11  5002.9  342.11
  5004.4  343.06  5010.3  346.82  5013.8  347.22  5020.3  347.97  5050.3  347.37
  5080.3  347.96  5150.3  347.87  5210.3  349.11  5250.3  349.07  5380.3  350.46
  5470.3  351.76  5560.3  353.79  5570.3  353.66  5600.3  355.46  5679.7  356.75
#Mann=5,-1,0
  4429.7    0.05       0  4995.9    0.05       0  4999.9    0.05       0
  5004.4    0.16       0  5013.8    0.05       0
Bank Sta=4995.9,4999.9
Exp/Cntr=0.3,0.1

Type RM Length L Ch R = 1,5557,147,147,147
BEGIN DESCRIPTION:
Prairie Creek Trib E5556.6
END DESCRIPTION:
XS GIS Cut Line= 3
      2702991.99      6814957.94      2702982.72      6815172.45
      2702974.60      6815596.26
#Sta/Elev= 30
  4787.8  348.86  4840.9  347.80  4881.0  347.49  4891.0  347.00  4901.0  347.39
  4921.0  346.95  4931.0  347.26  4951.0  346.43  4970.4  346.40  5002.5  346.63
  5021.1  346.16  5031.1  346.72  5041.1  345.31  5049.1  340.78  5049.3  340.28
  5052.8  340.28  5053.1  340.78  5061.1  344.97  5071.1  346.40  5094.3  347.08
  5149.3  346.62  5161.1  346.72  5191.1  345.61  5221.1  346.02  5291.1  348.17
  5311.1  348.40  5321.1  349.09  5351.1  349.50  5391.1  350.93  5426.4  351.23
#Mann=5,-1,0
  4787.8    0.05       0  4970.4    0.16       0  5049.1    0.07       0
  5053.1    0.16       0  5149.3   0.035       0
Bank Sta=5049.1,5053.1
Exp/Cntr=0.3,0.1

Type RM Length L Ch R = 1,5410,146,146,146
BEGIN DESCRIPTION:
Prairie Creek Trib E5409.93
END DESCRIPTION:
XS GIS Cut Line= 3
      2702883.67      6814877.79      2702850.31      6815214.77
      2702821.95      6815493.40
#Sta/Elev= 30
  4664.8  348.95  4828.8  345.85  4859.0  345.65  4879.1  346.27  4889.1  346.22
  4909.2  345.30  4919.3  345.74  4929.3  345.15  4949.4  345.71  4959.4  345.31
  4983.8  345.82  4995.5  345.27  5009.7  345.90  5049.9  345.87  5060.0  346.31
  5070.0  343.95  5078.1  339.65  5078.3  339.15  5081.8  339.15  5082.1  339.65
  5090.1  342.13  5095.2  342.09  5099.1  345.20  5100.3  346.16  5120.3  345.55
  5150.4  345.21  5160.5  345.74  5220.8  346.87  5250.9  348.48  5283.5  349.62
#Mann=5,-1,0
  4664.8    0.05       0  4983.8    0.16       0  5078.1    0.07       0
  5082.1    0.16       0  5099.1    0.05       0
Bank Sta=5078.1,5082.1
Exp/Cntr=0.3,0.1

Type RM Length L Ch R = 1,5264,252,252,252
BEGIN DESCRIPTION:
Prairie Creek Trib E5264.23
END DESCRIPTION:
XS GIS Cut Line= 3
      2702761.63      6814829.61      2702721.03      6815162.05
      2702675.43      6815552.79
#Sta/Elev= 30
  4673.1  347.99  4678.9  347.57  4734.9  347.07  4795.4  345.47  4835.7  345.16
  4855.8  344.55  4928.6  344.04  4966.7  344.93  4986.8  344.56  4996.9  343.71
  5010.1  345.29  5047.2  345.03  5060.5  345.48  5067.4  345.88  5077.4  342.10
  5093.5  341.48  5098.6  338.56  5105.6  338.29  5105.9  337.79  5109.4  337.79
  5109.6  338.29  5117.7  342.11  5127.8  345.63  5141.7  345.84  5158.0  345.31
  5208.3  346.28  5228.4  346.22  5265.4  348.21  5329.1  349.11  5401.4  351.62
#Mann=5,-1,0
  4673.1    0.05       0  5060.5    0.16       0  5105.6    0.05       0
  5109.6    0.16       0  5141.7    0.05       0
Bank Sta=5105.6,5109.6
Exp/Cntr=0.3,0.1

Type RM Length L Ch R = 1,5012,180,180,180
BEGIN DESCRIPTION:
Prairie Creek Trib E5011.72
END DESCRIPTION:
XS GIS Cut Line= 3
      2702547.14      6814725.15      2702520.33      6815016.81
      2702495.97      6815362.57
#Sta/Elev= 30
  4710.6  347.77  4716.5  347.19  4788.8  345.57  4806.9  345.58  4826.9  344.93
  4987.6  343.10  4994.4  342.36  5003.1  342.85  5017.7  342.48  5057.8  343.27
  5077.9  343.80  5087.9  344.49  5096.6  343.82  5097.9  343.72  5105.9  338.34
  5106.2  337.84  5109.7  337.84  5109.9  338.34  5118.0  344.33  5134.6  344.21
  5139.6  342.21  5148.0  344.24  5158.1  343.37  5178.1  343.71  5188.1  344.41
  5238.3  344.22  5259.3  345.59  5268.3  346.10  5280.9  345.38  5350.1  347.21
#Mann=6,-1,0
  4710.6   0.035       0  4788.8    0.05       0  5096.6    0.16       0
  5105.9    0.05       0  5109.9    0.16       0  5259.3    0.05       0
Bank Sta=5105.9,5109.9
Exp/Cntr=0.3,0.1

Type RM Length L Ch R = 1,4832,309,309,309
BEGIN DESCRIPTION:
Prairie Creek Trib E4832.05
END DESCRIPTION:
XS GIS Cut Line= 3
      2702380.80      6814745.19      2702357.71      6815051.23
      2702330.01      6815365.81
#Sta/Elev= 30
  4700.1  347.48  4736.0  345.72  4786.1  343.93  4856.3  342.92  4926.5  342.63
  4946.6  341.56  4956.6  340.52  4962.4  339.70  4967.5  338.25  4974.7  337.34
  4974.9  336.84  4978.4  336.84  4978.7  337.34  4985.2  337.88  4996.7  340.39
  5004.4  341.56  5009.4  341.56  5016.8  342.48  5026.9  342.92  5067.0  343.49
  5077.0  343.00  5117.2  343.59  5137.3  343.15  5192.8  344.38  5200.0  344.08
  5247.7  344.57  5277.8  345.44  5307.2  347.02  5312.2  346.37  5322.8  346.66
#Mann=5,-1,0
  4700.1    0.05       0  4974.7    0.07       0  4978.7    0.05       0
  4985.2    0.16       0  5192.8    0.05       0
Bank Sta=4974.7,4978.7
Exp/Cntr=0.3,0.1

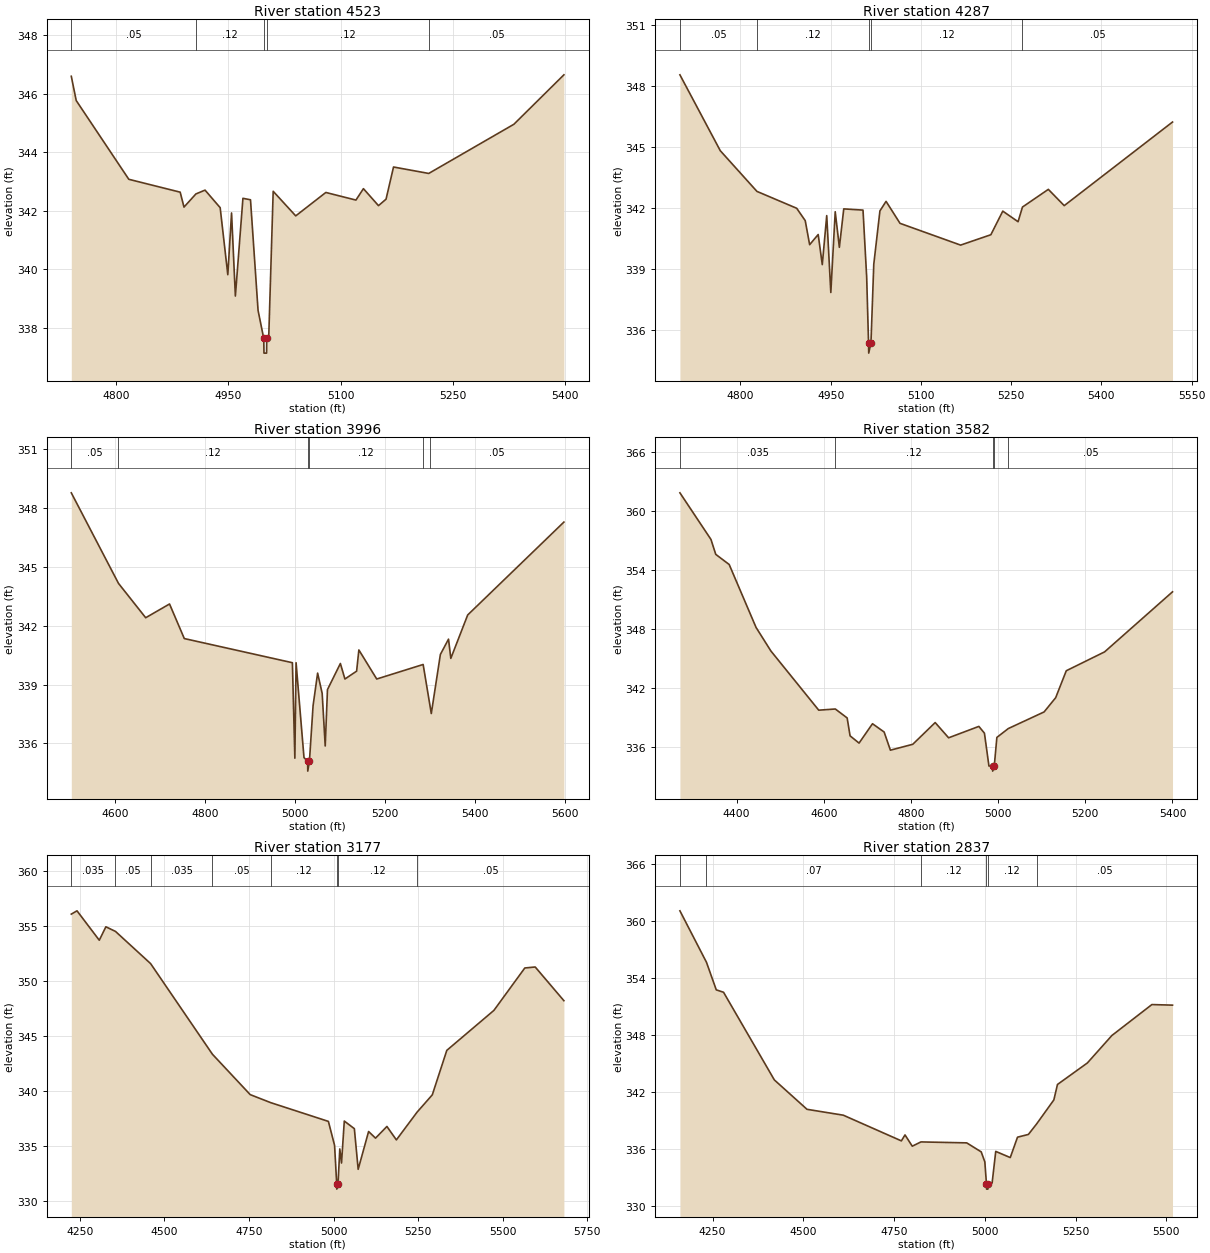
Type RM Length L Ch R = 1,4523,236,236,236
BEGIN DESCRIPTION:
Prairie Creek Trib E4522.75
END DESCRIPTION:
XS GIS Cut Line= 3
      2702183.25      6814704.43      2702143.54      6814964.99
      2702106.84      6815357.51
#Sta/Elev= 30
  4740.2  346.59  4746.8  345.76  4817.0  343.07  4885.6  342.63  4890.7  342.12
  4906.6  342.57  4918.8  342.70  4939.0  342.10  4949.2  339.81  4954.2  341.92
  4959.3  339.08  4969.4  342.42  4979.5  342.37  4989.6  338.59  4997.2  337.63
  4997.5  337.13  5001.0  337.13  5001.2  337.63  5003.8  337.63  5009.8  342.66
  5039.9  341.82  5080.1  342.62  5120.3  342.36  5130.3  342.75  5150.4  342.17
  5160.5  342.39  5170.5  343.49  5217.5  343.27  5331.2  344.95  5398.0  346.64
#Mann=5,-1,0
  4740.2    0.05       0  4906.6    0.12       0  4997.2    0.07       0
  5001.2    0.12       0  5217.5    0.05       0
Bank Sta=4997.2,5001.2
Exp/Cntr=0.3,0.1

Type RM Length L Ch R = 1,4287,291,291,291
BEGIN DESCRIPTION:
Prairie Creek Trib E4286.8
END DESCRIPTION:
XS GIS Cut Line= 3
      2702150.89      6814641.29      2701942.95      6814863.48
      2701839.17      6815367.29
#Sta/Elev= 30
  4699.5  348.53  4766.6  344.80  4827.5  342.80  4893.6  341.97  4907.8  341.36
  4915.1  340.18  4929.3  340.68  4936.1  339.20  4943.5  341.61  4950.3  337.83
  4957.6  341.80  4964.5  340.05  4971.8  341.94  5003.8  341.88  5009.9  338.58
  5013.0  335.35  5013.3  334.85  5017.0  335.35  5021.7  339.22  5031.9  341.84
  5042.1  342.31  5065.3  341.23  5166.0  340.16  5216.3  340.67  5236.1  341.83
  5261.5  341.31  5268.8  342.03  5311.8  342.90  5338.2  342.10  5518.2  346.21
#Mann=5,-1,0
  4699.5    0.05       0  4827.5    0.12       0  5013.0    0.07       0
  5017.0    0.12       0  5268.8    0.05       0
Bank Sta=5013,5017
Exp/Cntr=0.3,0.1

Type RM Length L Ch R = 1,3996,414,414,414
BEGIN DESCRIPTION:
Prairie Creek Trib E3996.148
END DESCRIPTION:
XS GIS Cut Line= 3
      2702125.99      6814611.01      2701670.96      6814810.91
      2701757.81      6815402.67
#Sta/Elev= 30
  4503.0  348.76  4607.9  344.15  4668.4  342.40  4721.4  343.10  4754.2  341.34
  4994.5  340.11  5000.0  335.25  5002.7  340.11  5020.3  335.28  5028.4  335.09
  5028.7  334.59  5032.4  335.09  5040.5  337.92  5050.6  339.58  5060.7  338.55
  5067.5  335.87  5072.5  338.74  5101.2  340.07  5111.3  339.28  5137.3  339.68
  5142.3  340.76  5182.0  339.28  5285.2  340.02  5300.0  337.98  5303.3  337.52
  5323.5  340.53  5341.6  341.31  5346.7  340.33  5384.2  342.54  5598.1  347.27
#Mann=6,-1,0
  4503.0    0.05       0  4607.9    0.12       0  5028.4    0.07       0
  5032.4    0.12       0  5285.2    0.07       0  5300.0    0.05       0
Bank Sta=5028.4,5032.4
Exp/Cntr=0.3,0.1

Type RM Length L Ch R = 1,3582,405,405,405
BEGIN DESCRIPTION:
Prairie Creek Trib E3582.31
END DESCRIPTION:
XS GIS Cut Line= 3
      2701478.27      6814150.99      2701311.53      6814861.53
      2701232.82      6815253.77
#Sta/Elev= 30
  4270.2  361.87  4341.4  357.13  4352.4  355.61  4383.2  354.58  4444.8  348.18
  4478.9  345.78  4588.6  339.76  4626.6  339.88  4653.8  338.97  4660.5  337.15
  4681.1  336.41  4711.9  338.38  4738.6  337.54  4753.0  335.69  4804.3  336.29
  4855.7  338.50  4886.5  336.95  4955.9  338.11  4968.7  337.42  4979.0  334.08
  4987.2  334.06  4987.5  333.56  4991.2  334.06  4997.2  336.99  5023.4  337.89
  5105.5  339.58  5132.1  341.03  5156.4  343.77  5244.3  345.69  5400.1  351.80
#Mann=5,-1,0
  4270.2   0.035       0  4626.6    0.12       0  4987.2    0.07       0
  4991.2    0.12       0  5023.4    0.05       0
Bank Sta=4987.2,4991.2
Exp/Cntr=0.3,0.1

Type RM Length L Ch R = 1,3177,340,340,340
BEGIN DESCRIPTION:
Prairie Creek Trib E3177.132
END DESCRIPTION:
XS GIS Cut Line= 3
      2701388.72      6813884.84      2701115.57      6814610.00
      2700964.08      6815273.63
#Sta/Elev= 30
  4225.1  356.04  4242.0  356.34  4307.8  353.67  4327.3  354.89  4355.7  354.47
  4459.4  351.55  4642.1  343.32  4753.8  339.65  4814.6  338.92  4984.8  337.22
  5003.1  335.04  5009.3  331.57  5009.5  331.07  5013.3  331.57  5018.5  334.72
  5023.6  333.44  5031.8  337.25  5061.5  336.56  5072.8  332.87  5103.6  336.30
  5124.1  335.70  5157.7  336.76  5185.7  335.54  5246.9  338.06  5291.8  339.63
  5334.7  343.67  5473.9  347.30  5565.2  351.15  5595.9  351.24  5680.7  348.18
#Mann=8,-1,0
  4225.1   0.035       0  4355.7    0.05       0  4459.4   0.035       0
  4642.1    0.05       0  4814.6    0.12       0  5009.3    0.07       0
  5013.3    0.12       0  5246.9    0.05       0
Bank Sta=5009.3,5013.3
Exp/Cntr=0.3,0.1

Type RM Length L Ch R = 1,2837,397,397,397
BEGIN DESCRIPTION:
Prairie Creek Trib E2836.94
END DESCRIPTION:
XS GIS Cut Line= 3
      2700857.21      6813820.85      2700849.09      6814669.26
      2700833.94      6815177.89
#Sta/Elev= 30
  4159.9  361.11  4233.1  355.68  4260.1  352.77  4280.1  352.52  4420.1  343.27
  4510.1  340.17  4610.1  339.55  4770.1  336.84  4780.1  337.47  4800.1  336.28
  4824.0  336.73  4950.1  336.63  4990.1  335.68  5000.1  334.62  5004.6  332.25
  5004.9  331.75  5008.5  331.75  5008.8  332.25  5020.1  332.39  5030.1  335.73
  5070.1  335.08  5090.1  337.23  5120.1  337.52  5142.6  338.62  5190.2  341.16
  5200.2  342.79  5282.6  345.06  5350.2  347.96  5460.3  351.22  5517.2  351.16
#Mann=6,-1,0
  4159.9    0.16       0  4233.1    0.07       0  4824.0    0.12       0
  5004.6    0.07       0  5008.8    0.12       0  5142.6    0.05       0
Bank Sta=5004.6,5008.8
Exp/Cntr=0.3,0.1

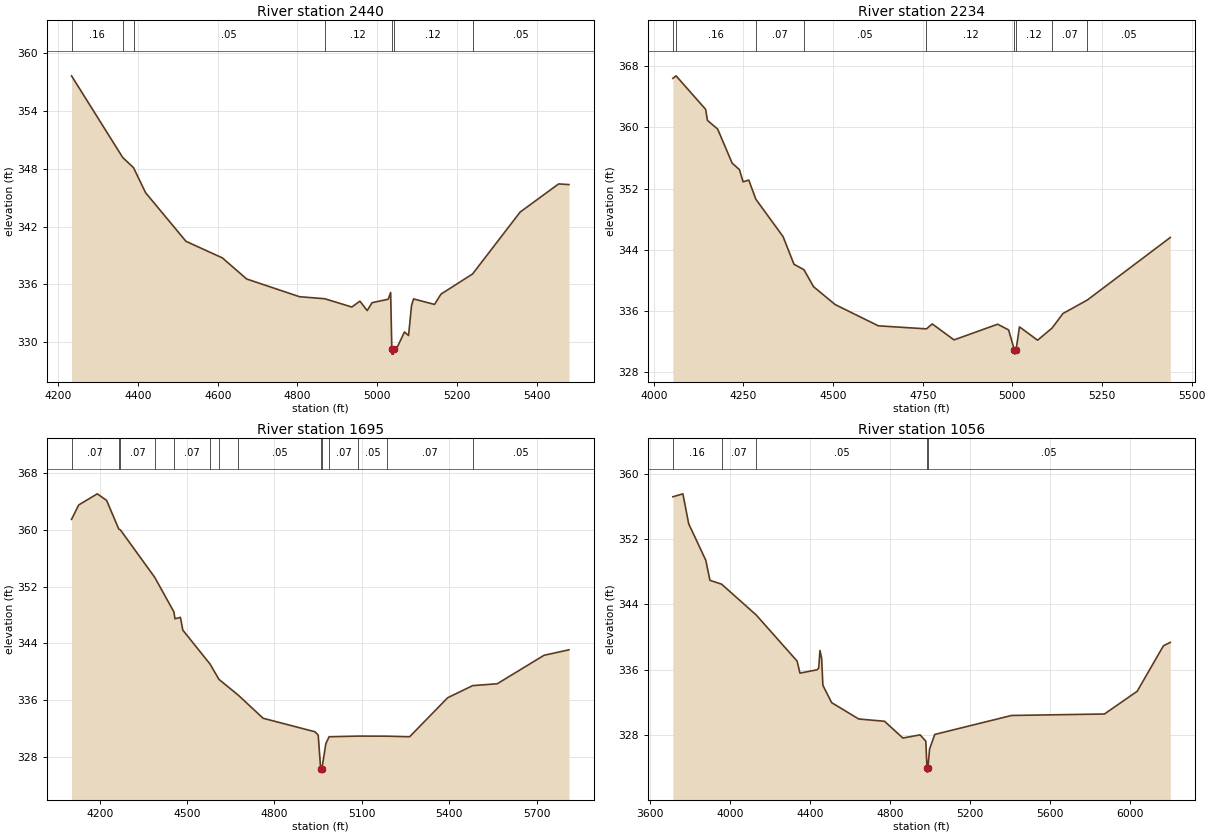
Type RM Length L Ch R = 1,2440,206,206,206
BEGIN DESCRIPTION:
Prairie Creek Trib E2440.25
END DESCRIPTION:
XS GIS Cut Line= 3
      2700697.13      6813748.02      2700565.96      6814511.34
      2700478.36      6814976.45
#Sta/Elev= 30
  4233.3  357.66  4361.9  349.17  4388.8  348.13  4419.0  345.53  4520.4  340.48
  4611.7  338.76  4672.6  336.57  4805.3  334.73  4868.5  334.52  4936.4  333.66
  4956.7  334.27  4975.0  333.29  4987.2  334.11  5027.8  334.47  5033.8  335.17
  5036.8  329.27  5037.0  328.77  5040.7  328.77  5041.0  329.27  5048.2  329.30
  5068.5  331.07  5078.7  330.70  5086.2  333.81  5091.3  334.50  5143.8  333.93
  5160.1  335.00  5239.3  337.09  5358.7  343.52  5455.2  346.44  5481.1  346.37
#Mann=7,-1,0
  4233.3    0.16       0  4361.9    0.07       0  4388.8    0.05       0
  4868.5    0.12       0  5036.8    0.07       0  5041.0    0.12       0
  5239.3    0.05       0
Bank Sta=5036.8,5041
Exp/Cntr=0.3,0.1

Type RM Length L Ch R = 1,2234,539,539,539
BEGIN DESCRIPTION:
Prairie Creek Trib E2234.33
END DESCRIPTION:
XS GIS Cut Line= 3
      2700536.69      6813527.96      2700375.72      6814472.41
      2700318.55      6814897.81
#Sta/Elev= 30
  4053.1  366.42  4062.0  366.75  4144.5  362.37  4149.5  360.93  4177.9  359.80
  4218.5  355.34  4238.8  354.49  4248.9  352.90  4264.8  353.13  4284.5  350.63
  4360.5  345.74  4390.9  342.13  4418.7  341.42  4445.4  339.20  4505.6  336.87
  4626.0  334.09  4760.4  333.69  4776.4  334.34  4837.3  332.25  4959.0  334.30
  4989.5  333.55  5005.8  330.89  5006.1  330.39  5010.0  330.89  5019.8  333.95
  5070.3  332.21  5110.8  333.80  5140.9  335.69  5209.3  337.47  5440.4  345.63
#Mann=9,-1,0
  4053.1    0.07       0  4062.0    0.16       0  4284.5    0.07       0
  4418.7    0.05       0  4760.4    0.12       0  5005.8    0.07       0
  5010.0    0.12       0  5110.8    0.07       0  5209.3    0.05       0
Bank Sta=5005.8,5010
Exp/Cntr=0.3,0.1

Type RM Length L Ch R = 1,1695,639,639,639
BEGIN DESCRIPTION:
Prairie Creek Trib E1695.21
END DESCRIPTION:
XS GIS Cut Line= 3
      2700429.35      6813235.45      2700148.80      6814103.62
      2700200.71      6814896.55
#Sta/Elev= 30
  4103.5  361.51  4127.9  363.54  4191.9  365.12  4223.9  364.19  4265.7  360.14
  4271.4  360.02  4389.4  353.30  4454.7  348.45  4458.6  347.47  4477.2  347.67
  4485.4  345.87  4579.0  341.07  4609.2  338.92  4675.3  336.70  4760.9  333.42
  4939.0  331.51  4950.1  331.02  4958.4  326.31  4958.7  325.81  4962.7  326.31
  4976.3  329.84  4987.5  330.81  5086.8  330.90  5185.1  330.89  5263.8  330.81
  5394.1  336.31  5480.0  338.03  5564.4  338.29  5724.8  342.31  5810.5  343.09
#Mann=14,-1,0
  4103.5    0.07       0  4265.7    0.16       0  4271.4    0.07       0
  4389.4    0.16       0  4454.7    0.07       0  4579.0    0.16       0
  4609.2    0.07       0  4675.3    0.05       0  4958.4    0.07       0
  4962.7    0.05       0  4987.5    0.07       0  5086.8    0.05       0
  5185.1    0.07       0  5480.0    0.05       0
Bank Sta=4958.4,4962.7
Exp/Cntr=0.3,0.1

Type RM Length L Ch R = 1,1056,0,0,0
BEGIN DESCRIPTION:
Prairie Creek Trib E1055.963
END DESCRIPTION:
XS GIS Cut Line= 3
      2700351.02      6812885.97      2699575.97      6813910.92
      2700147.75      6814965.15
#Sta/Elev= 30
  3715.0  357.17  3765.0  357.53  3794.1  353.86  3879.4  349.41  3900.2  346.95
  3958.4  346.48  4131.2  342.71  4335.6  337.07  4349.7  335.60  4435.9  336.01
  4443.4  336.23  4449.6  338.37  4457.9  337.43  4464.2  334.11  4507.9  331.99
  4643.1  329.99  4772.1  329.71  4863.7  327.66  4949.9  328.05  4978.2  327.27
  4984.3  323.99  4984.6  323.49  4988.7  323.99  4996.9  326.30  5022.8  328.10
  5406.5  330.42  5870.4  330.60  6034.0  333.38  6165.2  338.95  6199.3  339.36
#Mann=5,-1,0
  3715.0    0.16       0  3958.4    0.07       0  4131.2    0.05       0
  4984.3    0.05       0  4988.7    0.05       0
Bank Sta=4984.3,4988.7
Exp/Cntr=0.3,0.1

Chan Stop Cuts=-1