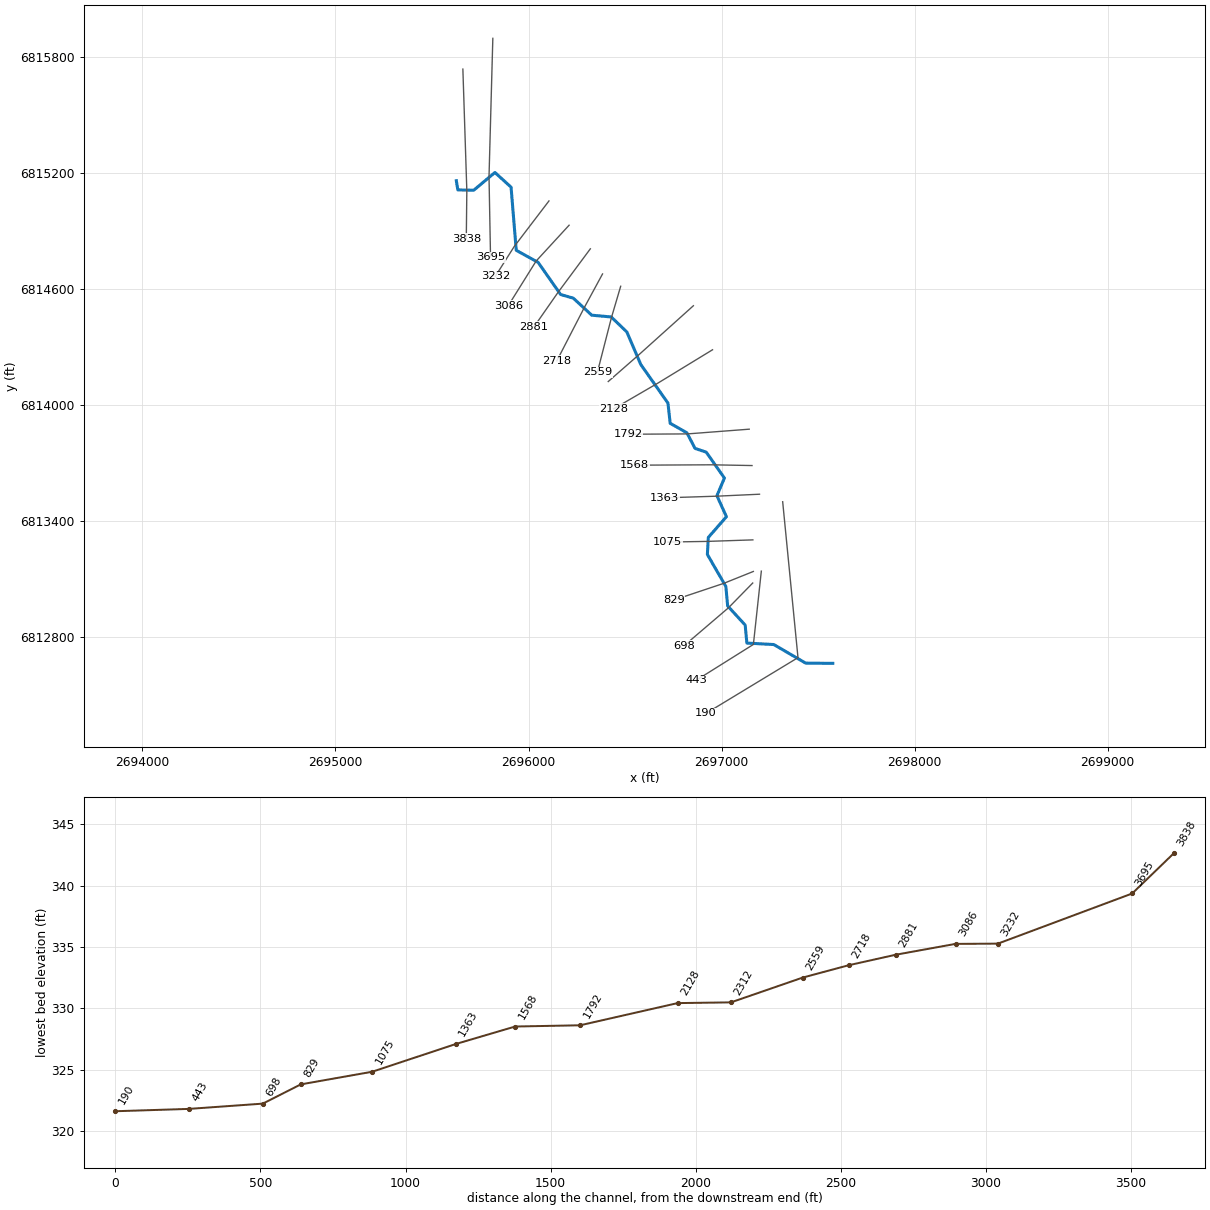
--- Prairie Creek Trib F.prj (project) ---

Proj Title=Prairie Creek Trib F Base Level Engineering
Current Plan=p01
Default Exp/Contr=0.3,0.1
English Units
Geom File=g01
Flow File=f01
Plan File=p01
BEGIN DESCRIPTION:
Prairie Creek Trib F
END DESCRIPTION:

--- Prairie Creek Trib F.p01 (plan) ---

Plan Title=Multiple Run
Short Identifier=Multiple
Geom File=g01
Flow File=f01
Subcritical Flow
K Sum by GR= 0
Std Step Tol= 0.01
Critical Tol= 0.01
Num of Std Step Trials= 20
Max Error Tol= 0.3
Flow Tol Ratio= 0.001
Split Flow NTrial= 30
Split Flow Tol= 0.02
Split Flow Ratio= 0.02
Log Output Level= 0
Friction Slope Method= 1
Unsteady Friction Slope Method= 2
Unsteady Bridges Friction Slope Method= 1
Parabolic Critical Depth
Global Vel Dist=  1 , 1 , 1
Global Log Level= 0
CheckData=True
Encroach Param= -1, 0, 0, 0
BEGIN DESCRIPTION:
Multiple Run
END DESCRIPTION:

--- Prairie Creek Trib F.f01 (steady flow) ---

Flow Title=Multiple
Number of Profiles=7
Profile Names=10-year,25-year,50-year,1pct_min,100-year,1pct_plu,500-year
River Rch & RM= Prairie Creek Tr,Reach-1,3838
     353     456     535     312     623    1242     842
River Rch & RM= Prairie Creek Tr,Reach-1,2312
     482     634     755     446     889    1774    1233
Boundary for River Rch & Prof#=Prairie Creek Tr,Reach-1,1
Up Type=0
Dn Type=3
Dn Slope=0.005
Boundary for River Rch & Prof#=Prairie Creek Tr,Reach-1,2
Up Type=0
Dn Type=3
Dn Slope=0.005
Boundary for River Rch & Prof#=Prairie Creek Tr,Reach-1,3
Up Type=0
Dn Type=3
Dn Slope=0.005
Boundary for River Rch & Prof#=Prairie Creek Tr,Reach-1,4
Up Type=0
Dn Type=3
Dn Slope=0.005
Boundary for River Rch & Prof#=Prairie Creek Tr,Reach-1,5
Up Type=0
Dn Type=3
Dn Slope=0.005
Boundary for River Rch & Prof#=Prairie Creek Tr,Reach-1,6
Up Type=0
Dn Type=3
Dn Slope=0.005
Boundary for River Rch & Prof#=Prairie Creek Tr,Reach-1,7
Up Type=0
Dn Type=3
Dn Slope=0.005

--- Prairie Creek Trib F.g01 (geometry) ---

Geom Title=Existing Conditions

River Reach=Prairie Creek Tr,Reach-1
Reach XY= 30
      2695626.00      6815161.00      2695633.76      6815113.56
      2695716.33      6815112.05      2695826.02      6815203.92
      2695909.57      6815127.84      2695936.35      6814800.88
      2696049.83      6814738.14      2696166.30      6814571.77
      2696232.04      6814552.82      2696327.50      6814464.63
      2696428.44      6814455.48      2696509.37      6814377.71
      2696581.85      6814208.71      2696722.17      6814009.41
      2696733.79      6813904.56      2696820.34      6813855.34
      2696862.69      6813774.65      2696920.35      6813755.37
      2697014.87      6813621.05      2696975.91      6813529.46
      2697025.24      6813420.78      2696931.41      6813313.42
      2696926.53      6813224.97      2697022.17      6813059.41
      2697031.54      6812958.58      2697122.34      6812859.42
      2697131.08      6812766.04      2697270.47      6812758.63
      2697435.63      6812662.31      2697576.00      6812661.00

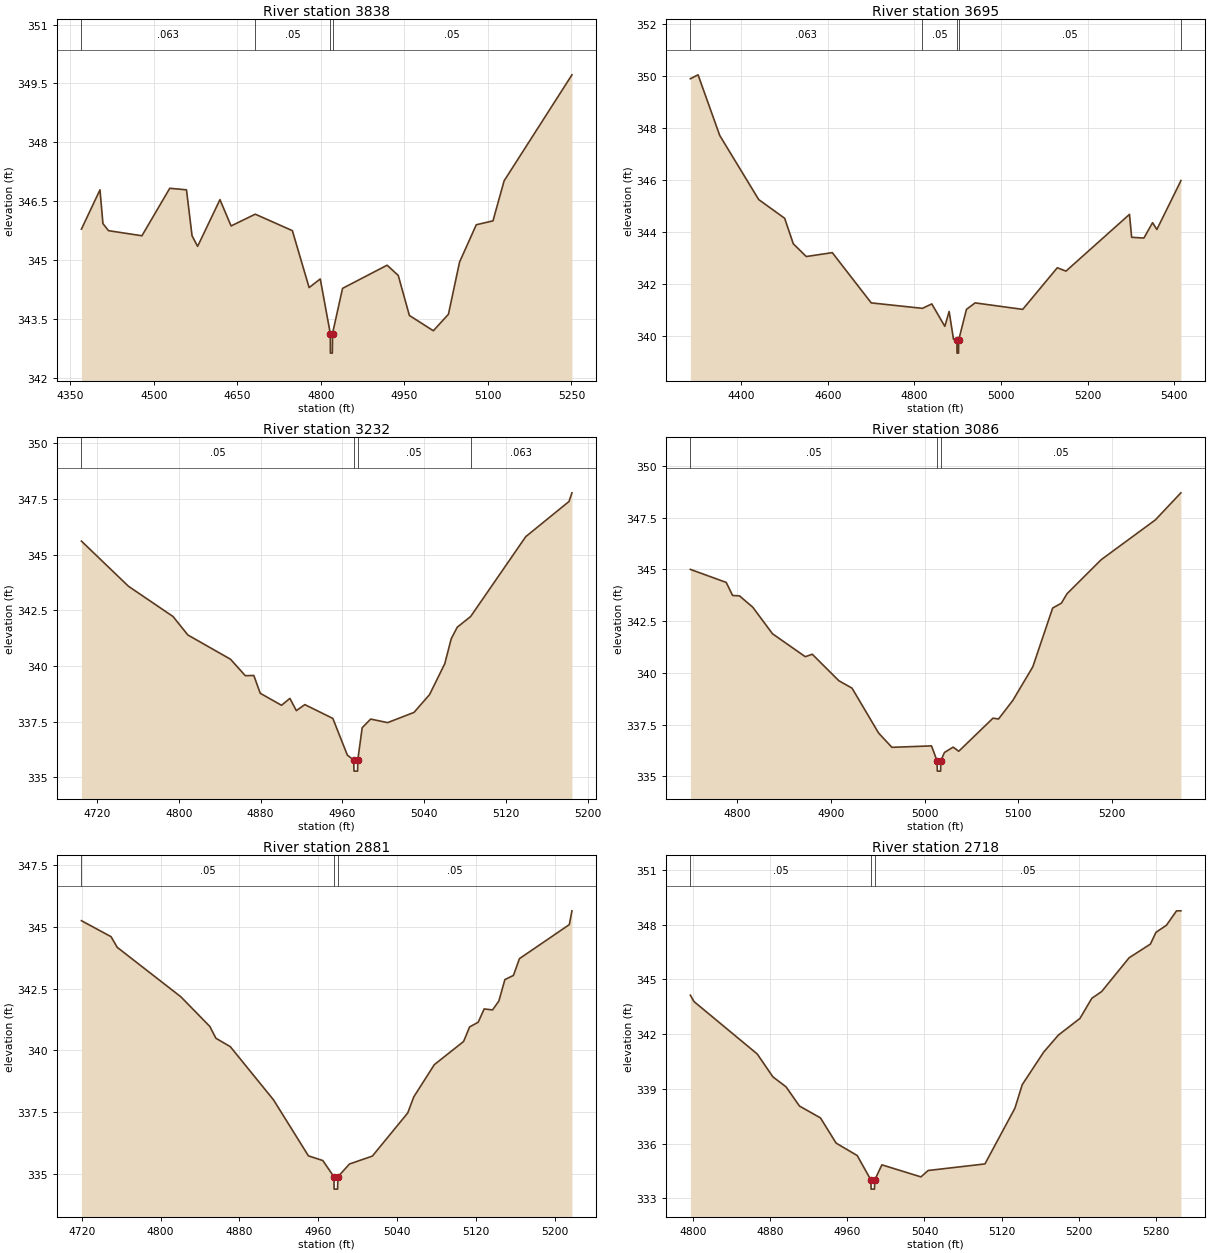
Type RM Length L Ch R = 1,3838,143,143,143
BEGIN DESCRIPTION:
Prairie Creek Trib F3837.542
END DESCRIPTION:
XS GIS Cut Line= 3
      2695659.92      6815739.54      2695680.41      6815110.07
      2695677.62      6814859.19
#Sta/Elev= 30
  4370.2  345.79  4403.5  346.79  4408.8  345.93  4418.8  345.75  4478.8  345.62
  4528.8  346.83  4558.8  346.79  4568.8  345.62  4578.8  345.35  4618.9  346.54
  4638.9  345.87  4682.3  346.17  4748.9  345.75  4779.0  344.30  4799.0  344.52
  4817.0  343.13  4817.2  342.63  4820.7  342.63  4821.0  343.13  4839.0  344.28
  4919.0  344.87  4939.0  344.61  4959.0  343.59  5002.0  343.20  5029.1  343.62
  5049.1  344.95  5079.1  345.90  5109.1  346.00  5129.1  347.02  5250.9  349.72
#Mann=4,-1,0
  4370.2   0.063       0  4682.3    0.05       0  4817.0    0.05       0
  4821.0    0.05       0
Bank Sta=4817,4821
Exp/Cntr=0.3,0.1

Type RM Length L Ch R = 1,3695,463,463,463
BEGIN DESCRIPTION:
Prairie Creek Trib F3695.28
END DESCRIPTION:
XS GIS Cut Line= 3
      2695815.12      6815898.83      2695795.34      6815182.22
      2695803.21      6814765.48
#Sta/Elev= 30
  4282.1  349.90  4299.9  350.05  4350.0  347.72  4440.0  345.26  4500.0  344.54
  4520.0  343.56  4550.0  343.07  4610.1  343.22  4700.1  341.29  4818.4  341.08
  4840.1  341.25  4870.2  340.39  4880.2  340.96  4890.2  339.90  4898.2  339.86
  4898.4  339.36  4901.9  339.36  4902.2  339.86  4920.2  341.04  4940.2  341.29
  5050.2  341.04  5130.2  342.64  5150.2  342.51  5297.0  344.69  5302.0  343.81
  5330.3  343.78  5350.3  344.37  5360.3  344.11  5415.5  345.97  5415.8  345.99
#Mann=5,-1,0
  4282.1   0.063       0  4818.4    0.05       0  4898.2    0.05       0
  4902.2    0.05       0  5415.5   0.063       0
Bank Sta=4898.2,4902.2
Exp/Cntr=0.3,0.1

Type RM Length L Ch R = 1,3232,146,146,146
BEGIN DESCRIPTION:
Prairie Creek Trib F3231.64
END DESCRIPTION:
XS GIS Cut Line= 3
      2696105.87      6815056.54      2695925.91      6814820.44
      2695827.98      6814665.92
#Sta/Elev= 30
  4704.8  345.61  4750.8  343.58  4794.4  342.22  4808.9  341.39  4850.6  340.30
  4865.1  339.56  4873.4  339.57  4879.7  338.77  4900.5  338.23  4908.7  338.54
  4915.0  337.99  4923.3  338.26  4950.7  337.64  4964.9  335.99  4971.1  335.77
  4971.4  335.27  4974.9  335.27  4975.1  335.77  4979.4  337.22  4987.7  337.61
  5004.3  337.45  5030.1  337.91  5045.3  338.71  5060.2  340.10  5066.5  341.22
  5072.4  341.74  5085.5  342.22  5139.4  345.81  5181.7  347.39  5184.6  347.78
#Mann=4,-1,0
  4704.8    0.05       0  4971.1    0.05       0  4975.1    0.05       0
  5085.5   0.063       0
Bank Sta=4971.1,4975.1
Exp/Cntr=0.3,0.1

Type RM Length L Ch R = 1,3086,205,205,205
BEGIN DESCRIPTION:
Prairie Creek Trib F3086.09
END DESCRIPTION:
XS GIS Cut Line= 3
      2696210.14      6814930.74      2696039.34      6814745.06
      2695895.43      6814514.59
#Sta/Elev= 30
  4749.7  345.00  4788.0  344.37  4794.8  343.74  4802.2  343.72  4816.4  343.17
  4837.4  341.89  4872.5  340.78  4879.9  340.90  4908.3  339.62  4922.4  339.26
  4950.8  337.09  4965.0  336.40  5007.3  336.47  5013.2  335.75  5013.5  335.25
  5017.0  335.25  5017.2  335.75  5021.1  336.15  5030.4  336.41  5036.4  336.21
  5073.0  337.81  5078.9  337.77  5094.2  338.67  5115.5  340.29  5136.7  343.13
  5146.1  343.37  5152.0  343.82  5188.6  345.47  5246.4  347.39  5273.7  348.70
#Mann=3,-1,0
  4749.7    0.05       0  5013.2    0.05       0  5017.2    0.05       0
Bank Sta=5013.2,5017.2
Exp/Cntr=0.3,0.1

Type RM Length L Ch R = 1,2881,163,163,163
BEGIN DESCRIPTION:
Prairie Creek Trib F2881.08
END DESCRIPTION:
XS GIS Cut Line= 3
      2696320.17      6814808.48      2696151.80      6814581.33
      2696028.72      6814404.85
#Sta/Elev= 30
  4719.7  345.26  4749.8  344.61  4756.0  344.18  4820.7  342.17  4850.0  340.97
  4856.2  340.49  4870.8  340.15  4914.7  337.99  4950.1  335.72  4964.7  335.53
  4976.0  334.87  4976.2  334.37  4979.7  334.37  4980.0  334.87  4991.8  335.39
  5015.0  335.71  5050.9  337.46  5057.0  338.11  5077.9  339.42  5107.6  340.36
  5113.7  340.95  5122.4  341.14  5128.5  341.68  5137.0  341.64  5143.4  342.00
  5149.5  342.87  5158.2  343.04  5164.3  343.72  5214.9  345.10  5217.6  345.66
#Mann=3,-1,0
  4719.7    0.05       0  4976.0    0.05       0  4980.0    0.05       0
Bank Sta=4976,4980
Exp/Cntr=0.3,0.1

Type RM Length L Ch R = 1,2718,159,159,159
BEGIN DESCRIPTION:
Prairie Creek Trib F2717.94
END DESCRIPTION:
XS GIS Cut Line= 3
      2696383.40      6814678.34      2696287.39      6814501.25
      2696146.51      6814227.96
#Sta/Elev= 30
  4797.1  344.13  4800.9  343.78  4866.5  340.91  4882.7  339.66  4896.4  339.11
  4910.3  338.06  4932.1  337.41  4948.3  336.03  4970.2  335.35  4984.4  334.01
  4984.6  333.51  4988.1  333.51  4988.4  334.01  4995.8  334.84  5036.3  334.18
  5043.8  334.53  5102.7  334.89  5133.8  337.94  5141.4  339.23  5163.6  341.01
  5178.8  341.94  5201.3  342.86  5213.6  343.96  5223.8  344.33  5252.3  346.18
  5274.4  346.93  5280.1  347.57  5291.0  347.96  5301.5  348.75  5306.0  348.75
#Mann=3,-1,0
  4797.1    0.05       0  4984.4    0.05       0  4988.4    0.05       0
Bank Sta=4984.4,4988.4
Exp/Cntr=0.3,0.1

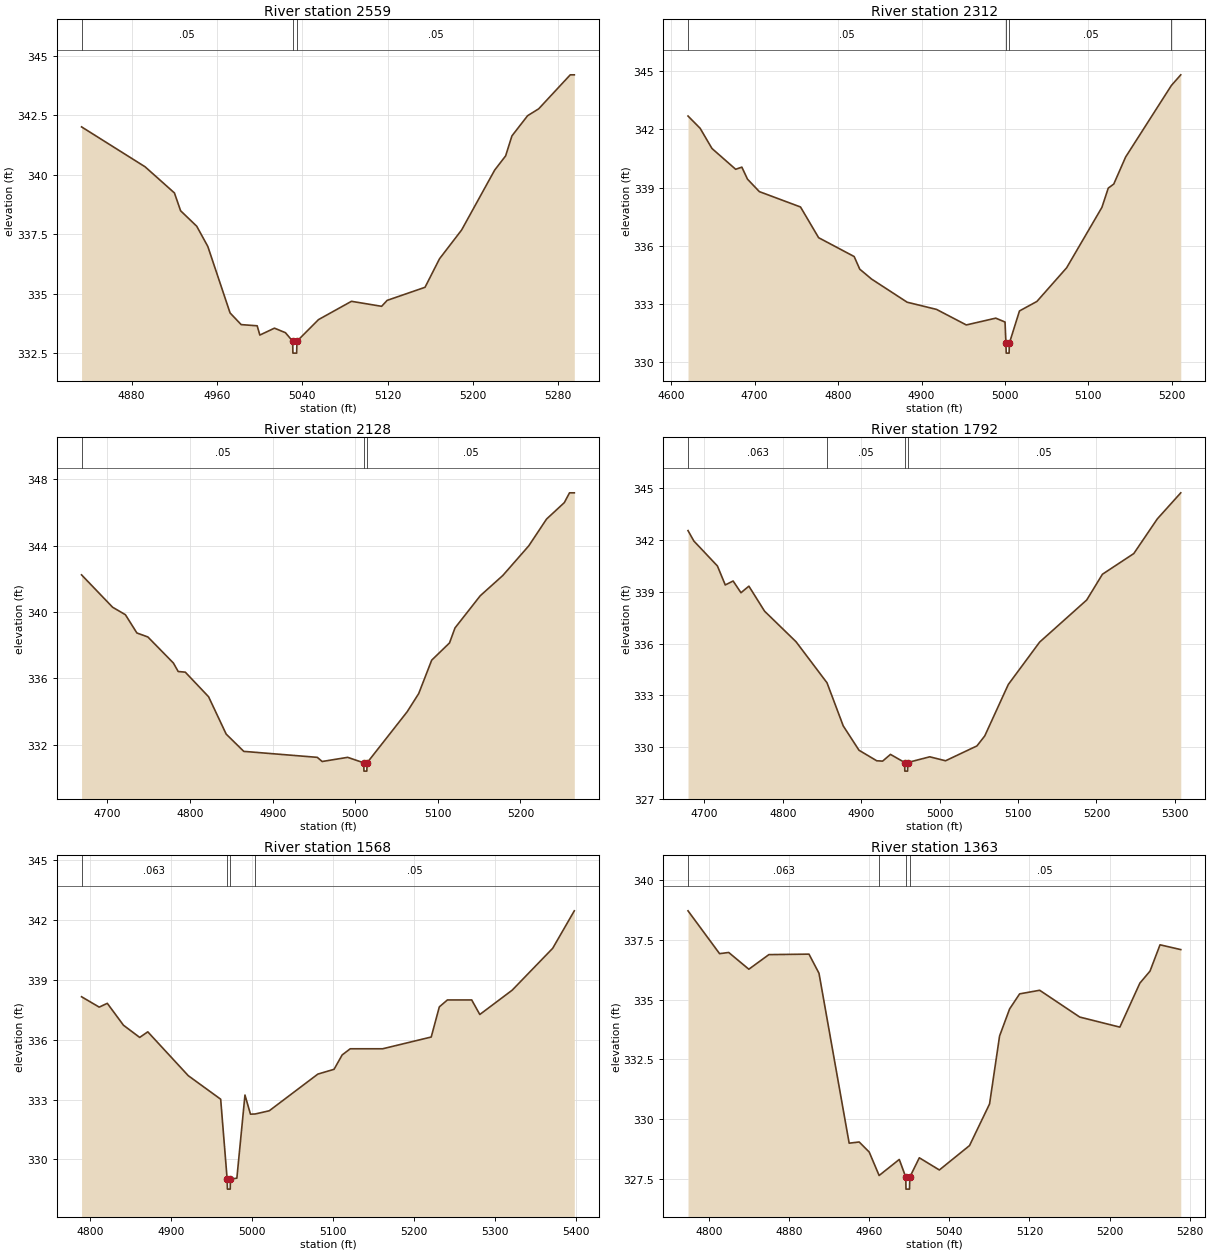
Type RM Length L Ch R = 1,2559,247,247,247
BEGIN DESCRIPTION:
Prairie Creek Trib F2559.44
END DESCRIPTION:
XS GIS Cut Line= 3
      2696477.42      6814614.57      2696429.62      6814452.49
      2696356.61      6814168.62
#Sta/Elev= 30
  4833.0  342.02  4892.6  340.34  4920.1  339.24  4925.9  338.49  4941.0  337.84
  4951.4  336.99  4972.3  334.19  4982.7  333.70  4997.7  333.65  5000.2  333.26
  5013.9  333.55  5024.2  333.36  5031.0  333.00  5031.2  332.50  5034.7  332.50
  5035.0  333.00  5055.2  333.91  5086.1  334.68  5114.4  334.47  5119.6  334.72
  5155.1  335.27  5168.7  336.47  5189.4  337.68  5220.4  340.20  5230.7  340.80
  5236.6  341.64  5251.3  342.49  5261.7  342.78  5291.3  344.21  5295.1  344.21
#Mann=3,-1,0
  4833.0    0.05       0  5031.0    0.05       0  5035.0    0.05       0
Bank Sta=5031,5035
Exp/Cntr=0.3,0.1

Type RM Length L Ch R = 1,2312,184,184,184
BEGIN DESCRIPTION:
Prairie Creek Trib F2311.5
END DESCRIPTION:
XS GIS Cut Line= 3
      2696854.02      6814513.63      2696571.56      6814259.64
      2696412.97      6814121.02
#Sta/Elev= 30
  4620.2  342.68  4634.7  342.05  4648.9  341.01  4677.3  339.94  4684.7  340.05
  4691.5  339.43  4705.7  338.79  4755.0  338.00  4776.7  336.42  4819.3  335.45
  4826.0  334.80  4840.2  334.29  4882.8  333.10  4918.0  332.73  4953.7  331.93
  4989.0  332.28  5000.1  332.08  5001.2  330.98  5001.5  330.48  5005.0  330.48
  5005.2  330.98  5017.4  332.65  5038.3  333.14  5073.9  334.87  5116.2  337.98
  5123.8  338.97  5130.4  339.18  5144.6  340.57  5199.4  344.25  5210.7  344.80
#Mann=4,-1,0
  4620.2    0.05       0  5001.2    0.05       0  5005.2    0.05       0
  5199.4   0.035       0
Bank Sta=5001.2,5005.2
Exp/Cntr=0.3,0.1

Type RM Length L Ch R = 1,2128,336,336,336
BEGIN DESCRIPTION:
Prairie Creek Trib F2128.37
END DESCRIPTION:
XS GIS Cut Line= 3
      2696953.23      6814285.53      2696670.41      6814112.93
      2696441.07      6813979.61
#Sta/Elev= 30
  4668.6  342.24  4706.2  340.29  4721.7  339.84  4735.6  338.74  4748.9  338.50
  4779.8  336.93  4785.6  336.42  4794.2  336.38  4822.4  334.90  4843.7  332.65
  4865.0  331.61  4954.0  331.25  4959.9  331.00  4990.8  331.25  5010.3  330.92
  5010.5  330.42  5014.0  330.42  5014.3  330.92  5062.9  334.00  5076.8  335.09
  5092.5  337.10  5114.1  338.14  5120.7  339.04  5151.3  340.98  5178.6  342.20
  5210.1  343.99  5231.6  345.60  5253.1  346.59  5259.4  347.18  5265.2  347.18
#Mann=3,-1,0
  4668.6    0.05       0  5010.3    0.05       0  5014.3    0.05       0
Bank Sta=5010.3,5014.3
Exp/Cntr=0.3,0.1

Type RM Length L Ch R = 1,1792,224,224,224
BEGIN DESCRIPTION:
Prairie Creek Trib F1791.58
END DESCRIPTION:
XS GIS Cut Line= 3
      2697143.34      6813874.18      2696823.34      6813849.68
      2696516.09      6813847.97
#Sta/Elev= 30
  4679.3  342.55  4686.7  341.95  4716.8  340.50  4726.8  339.40  4736.8  339.63
  4746.8  338.95  4756.9  339.33  4776.9  337.88  4817.0  336.11  4856.5  333.73
  4877.2  331.23  4897.3  329.82  4919.9  329.21  4927.4  329.19  4937.4  329.58
  4955.5  329.11  4955.7  328.61  4959.2  328.61  4959.5  329.11  4987.5  329.44
  5007.6  329.21  5047.6  330.07  5057.6  330.65  5087.6  333.63  5127.6  336.09
  5187.6  338.53  5207.6  340.02  5247.6  341.22  5277.6  343.23  5307.5  344.74
#Mann=4,-1,0
  4679.3   0.063       0  4856.5    0.05       0  4955.5    0.05       0
  4959.5    0.05       0
Bank Sta=4955.5,4959.5
Exp/Cntr=0.3,0.1

Type RM Length L Ch R = 1,1568,205,205,205
BEGIN DESCRIPTION:
Prairie Creek Trib F1568.28
END DESCRIPTION:
XS GIS Cut Line= 3
      2697157.78      6813685.75      2696947.49      6813689.68
      2696549.32      6813687.64
#Sta/Elev= 30
  4789.5  338.16  4811.3  337.64  4821.3  337.83  4841.3  336.73  4861.3  336.12
  4871.3  336.40  4921.3  334.20  4961.3  333.02  4969.3  329.01  4969.6  328.51
  4973.1  328.51  4973.3  329.01  4981.3  329.06  4991.3  333.23  4998.1  332.27
  5004.0  332.28  5021.3  332.44  5081.3  334.28  5101.3  334.52  5111.3  335.24
  5121.3  335.55  5161.3  335.55  5221.3  336.14  5231.3  337.65  5241.3  338.00
  5271.3  338.00  5281.3  337.27  5321.3  338.49  5371.3  340.59  5398.0  342.47
#Mann=4,-1,0
  4789.5   0.063       0  4969.3   0.063       0  4973.3   0.063       0
  5004.0    0.05       0
Bank Sta=4969.3,4973.3
Exp/Cntr=0.3,0.1

Type RM Length L Ch R = 1,1363,288,288,288
BEGIN DESCRIPTION:
Prairie Creek Trib F1362.84
END DESCRIPTION:
XS GIS Cut Line= 3
      2697196.59      6813537.25      2696974.09      6813527.06
      2696705.27      6813518.43
#Sta/Elev= 30
  4779.3  338.71  4810.8  336.92  4819.9  336.97  4840.0  336.27  4860.0  336.88
  4900.0  336.90  4910.0  336.10  4940.1  329.00  4950.1  329.05  4960.1  328.63
  4970.0  327.65  4990.1  328.32  4996.6  327.58  4996.8  327.08  5000.3  327.08
  5000.6  327.58  5010.1  328.39  5030.1  327.88  5060.2  328.90  5080.2  330.64
  5090.2  333.48  5100.2  334.61  5110.2  335.24  5130.2  335.39  5170.2  334.27
  5210.2  333.85  5230.2  335.69  5240.3  336.19  5250.3  337.29  5271.0  337.09
#Mann=4,-1,0
  4779.3   0.063       0  4970.0    0.05       0  4996.6    0.05       0
  5000.6    0.05       0
Bank Sta=4996.6,5000.6
Exp/Cntr=0.3,0.1

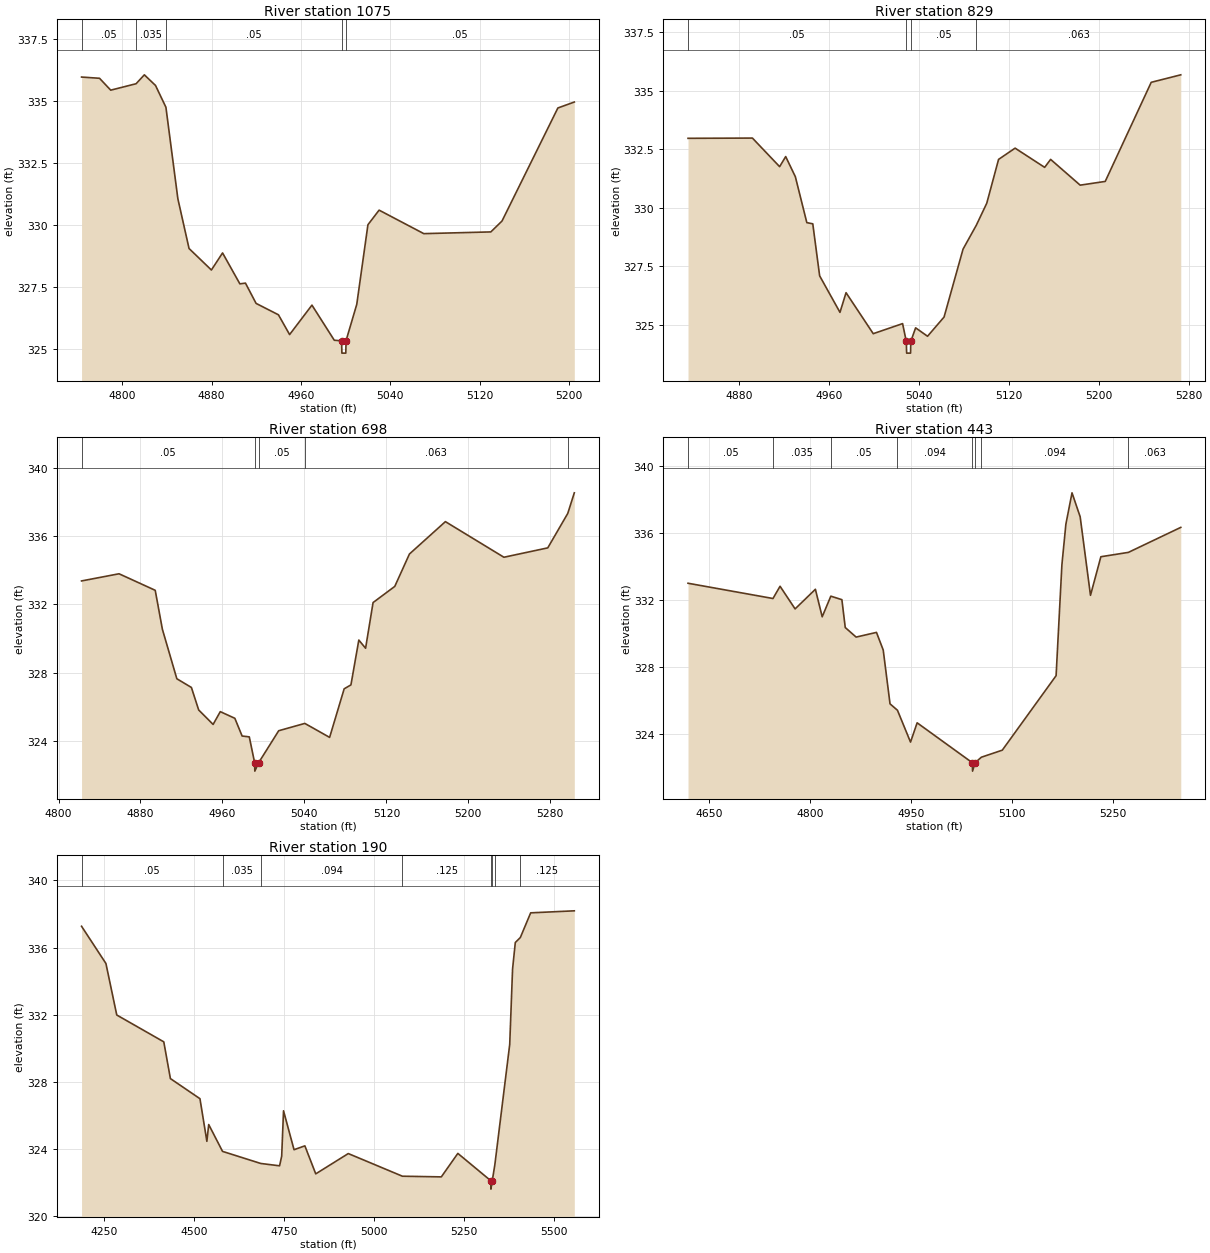
Type RM Length L Ch R = 1,1075,246,246,246
BEGIN DESCRIPTION:
Prairie Creek Trib F1074.53
END DESCRIPTION:
XS GIS Cut Line= 3
      2697162.12      6813300.74      2696924.10      6813292.80
      2696721.28      6813289.55
#Sta/Elev= 30
  4763.7  335.98  4779.8  335.93  4789.8  335.45  4812.5  335.71  4819.9  336.07
  4829.9  335.64  4839.2  334.76  4849.9  331.06  4859.9  329.05  4879.9  328.18
  4889.9  328.87  4905.4  327.62  4910.4  327.65  4919.9  326.83  4939.9  326.37
  4949.9  325.57  4969.9  326.76  4989.9  325.34  4996.4  325.32  4996.7  324.82
  5000.2  324.82  5000.4  325.32  5010.0  326.79  5020.0  330.01  5030.0  330.60
  5070.0  329.65  5130.0  329.72  5140.0  330.16  5190.0  334.73  5204.7  334.97
#Mann=5,-1,0
  4763.7    0.05       0  4812.5   0.035       0  4839.2    0.05       0
  4996.4    0.05       0  5000.4    0.05       0
Bank Sta=4996.4,5000.4
Exp/Cntr=0.3,0.1

Type RM Length L Ch R = 1,829,131,131,131
BEGIN DESCRIPTION:
Prairie Creek Trib F829.34
END DESCRIPTION:
XS GIS Cut Line= 3
      2697164.66      6813137.15      2697010.59      6813075.24
      2696752.27      6812988.91
#Sta/Elev= 30
  4834.5  332.96  4891.8  332.97  4916.0  331.75  4921.4  332.18  4930.0  331.32
  4940.2  329.36  4945.5  329.31  4951.6  327.09  4969.7  325.53  4975.1  326.37
  4999.3  324.62  5025.4  325.05  5028.7  324.29  5029.0  323.79  5032.5  323.79
  5032.7  324.29  5037.0  324.87  5047.6  324.51  5062.3  325.33  5079.2  328.23
  5091.0  329.25  5100.3  330.19  5110.8  332.06  5125.5  332.54  5151.8  331.72
  5157.1  332.06  5183.4  330.96  5205.7  331.12  5246.6  335.35  5272.9  335.67
#Mann=4,-1,0
  4834.5    0.05       0  5028.7    0.05       0  5032.7    0.05       0
  5091.0   0.063       0
Bank Sta=5028.7,5032.7
Exp/Cntr=0.3,0.1

Type RM Length L Ch R = 1,698,255,255,255
BEGIN DESCRIPTION:
Prairie Creek Trib F697.71
END DESCRIPTION:
XS GIS Cut Line= 3
      2697161.42      6813077.22      2697035.66      6812948.85
      2696806.65      6812753.21
#Sta/Elev= 30
  4822.5  333.38  4859.1  333.80  4894.4  332.83  4901.4  330.54  4915.5  327.64
  4929.7  327.13  4936.8  325.81  4950.9  324.96  4957.9  325.71  4972.1  325.32
  4979.2  324.28  4986.2  324.23  4991.4  322.72  4991.6  322.22  4995.4  322.72
  5014.9  324.59  5040.4  325.02  5064.6  324.20  5078.8  327.05  5085.4  327.28
  5093.1  329.91  5099.7  329.43  5107.0  332.11  5128.2  333.06  5142.5  334.96
  5177.6  336.86  5234.7  334.77  5277.5  335.32  5297.0  337.34  5303.4  338.55
#Mann=5,-1,0
  4822.5    0.05       0  4991.4    0.05       0  4995.4    0.05       0
  5040.4   0.063       0  5297.0   0.094       0
Bank Sta=4991.4,4995.4
Exp/Cntr=0.3,0.1

Type RM Length L Ch R = 1,443,253,253,253
BEGIN DESCRIPTION:
Prairie Creek Trib F442.74
END DESCRIPTION:
XS GIS Cut Line= 3
      2697205.99      6813138.84      2697164.90      6812759.10
      2696869.34      6812573.80
#Sta/Elev= 30
  4619.3  332.99  4745.3  332.08  4755.8  332.81  4778.1  331.46  4808.2  332.63
  4818.3  330.99  4831.1  332.22  4847.5  332.01  4852.5  330.35  4868.6  329.78
  4898.8  330.06  4908.8  329.01  4918.9  325.80  4929.9  325.42  4949.3  323.52
  4959.1  324.67  5041.0  322.29  5041.3  321.79  5045.0  322.29  5054.4  322.62
  5085.4  323.04  5165.2  327.48  5173.8  334.09  5179.7  336.51  5188.8  338.38
  5200.9  336.95  5216.2  332.27  5231.6  334.57  5272.4  334.83  5350.1  336.32
#Mann=8,-1,0
  4619.3    0.05       0  4745.3   0.035       0  4831.1    0.05       0
  4929.9   0.094       0  5041.0    0.07       0  5045.0   0.094       0
  5054.4   0.094       0  5272.4   0.063       0
Bank Sta=5041,5045
Exp/Cntr=0.3,0.1

Type RM Length L Ch R = 1,190,0,0,0
BEGIN DESCRIPTION:
Prairie Creek Trib F190.09
END DESCRIPTION:
XS GIS Cut Line= 3
      2697316.56      6813498.35      2697395.89      6812690.73
      2696919.34      6812401.98
#Sta/Elev= 30
  4188.5  337.27  4256.2  335.05  4286.3  331.98  4416.9  330.38  4435.3  328.19
  4517.4  326.99  4536.6  324.45  4541.7  325.45  4580.1  323.85  4686.2  323.13
  4738.5  322.99  4744.4  323.56  4749.5  326.27  4778.7  323.95  4808.8  324.18
  4839.0  322.51  4929.4  323.72  5079.7  322.37  5187.8  322.33  5233.7  323.73
  5325.3  322.10  5325.5  321.60  5329.3  322.10  5336.4  323.04  5377.8  330.23
  5385.7  334.72  5393.3  336.30  5407.3  336.60  5436.0  338.07  5557.2  338.19
#Mann=8,-1,0
  4188.5    0.05       0  4580.1   0.035       0  4686.2   0.094       0
  5079.7   0.125       0  5325.3    0.07       0  5329.3   0.125       0
  5336.4   0.094       0  5407.3   0.125       0
Bank Sta=5325.3,5329.3
Exp/Cntr=0.3,0.1

Chan Stop Cuts=-1