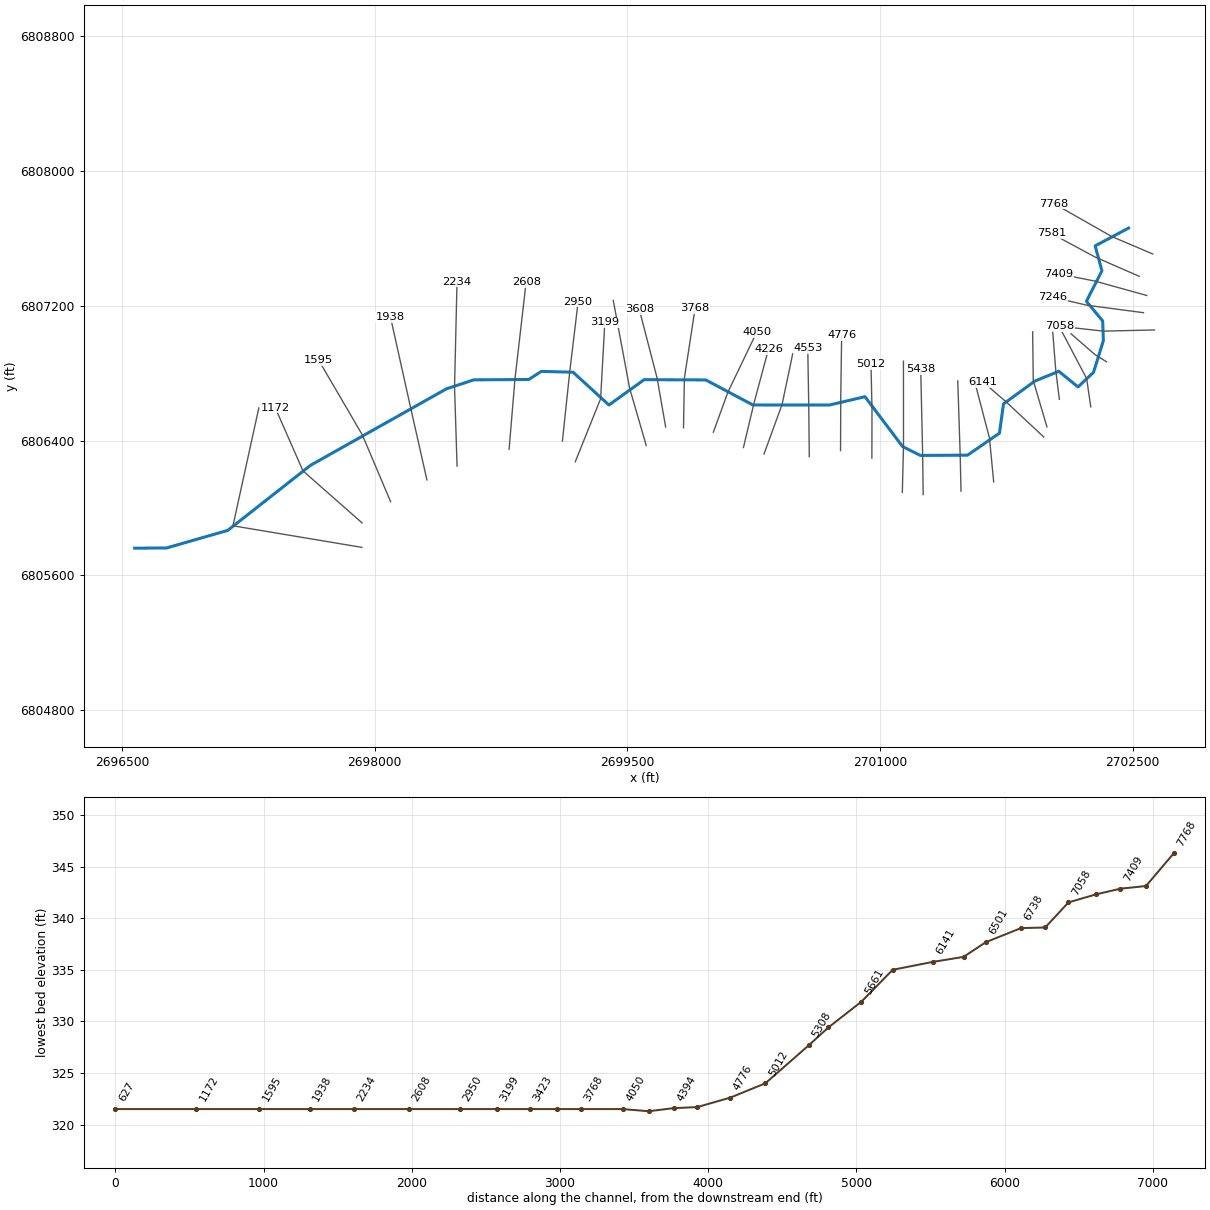
--- Prairie Creek Trib G.prj (project) ---

Proj Title=Prairie Creek Trib G Base Level Engineering
Current Plan=p01
Default Exp/Contr=0.3,0.1
English Units
Geom File=g01
Flow File=f01
Plan File=p01
BEGIN DESCRIPTION:
Prairie Creek Trib G
END DESCRIPTION:

--- Prairie Creek Trib G.p01 (plan) ---

Plan Title=Multiple Run
Short Identifier=Multiple
Geom File=g01
Flow File=f01
Subcritical Flow
K Sum by GR= 0
Std Step Tol= 0.01
Critical Tol= 0.01
Num of Std Step Trials= 20
Max Error Tol= 0.3
Flow Tol Ratio= 0.001
Split Flow NTrial= 30
Split Flow Tol= 0.02
Split Flow Ratio= 0.02
Log Output Level= 0
Friction Slope Method= 1
Unsteady Friction Slope Method= 2
Unsteady Bridges Friction Slope Method= 1
Parabolic Critical Depth
Global Vel Dist=  1 , 1 , 1
Global Log Level= 0
CheckData=True
Encroach Param= -1, 0, 0, 0
BEGIN DESCRIPTION:
Multiple Run
END DESCRIPTION:

--- Prairie Creek Trib G.f01 (steady flow) ---

Flow Title=Multiple
Number of Profiles=7
Profile Names=10-year,25-year,50-year,1pct_min,100-year,1pct_plu,500-year
River Rch & RM= Prairie Creek Tr,Reach-1,7768
     276     351     408     236     470     938     624
River Rch & RM= Prairie Creek Tr,Reach-1,6141
     600     799     958     569    1136    2267    1598
Boundary for River Rch & Prof#=Prairie Creek Tr,Reach-1,1
Up Type=0
Dn Type=3
Dn Slope=0.005
Boundary for River Rch & Prof#=Prairie Creek Tr,Reach-1,2
Up Type=0
Dn Type=3
Dn Slope=0.005
Boundary for River Rch & Prof#=Prairie Creek Tr,Reach-1,3
Up Type=0
Dn Type=3
Dn Slope=0.005
Boundary for River Rch & Prof#=Prairie Creek Tr,Reach-1,4
Up Type=0
Dn Type=3
Dn Slope=0.005
Boundary for River Rch & Prof#=Prairie Creek Tr,Reach-1,5
Up Type=0
Dn Type=3
Dn Slope=0.005
Boundary for River Rch & Prof#=Prairie Creek Tr,Reach-1,6
Up Type=0
Dn Type=3
Dn Slope=0.005
Boundary for River Rch & Prof#=Prairie Creek Tr,Reach-1,7
Up Type=0
Dn Type=3
Dn Slope=0.005

--- Prairie Creek Trib G.g01 (geometry) ---

Geom Title=Existing Conditions

River Reach=Prairie Creek Tr,Reach-1
Reach XY= 30
      2702476.00      6807661.00      2702277.88      6807555.31
      2702317.95      6807407.68      2702225.95      6807226.34
      2702322.46      6807109.53      2702326.43      6806992.67
      2702268.14      6806804.79      2702176.02      6806718.08
      2702061.96      6806810.90      2701919.95      6806752.85
      2701733.70      6806617.47      2701709.72      6806443.86
      2701520.14      6806313.06      2701239.90      6806311.66
      2701134.48      6806364.51      2700911.30      6806660.12
      2700701.12      6806610.88      2700246.03      6806611.06
      2699966.35      6806759.64      2699600.88      6806761.30
      2699391.36      6806610.89      2699178.45      6806805.54
      2698989.92      6806810.32      2698915.50      6806762.22
      2698589.92      6806760.32      2698427.58      6806707.17
      2697619.95      6806252.84      2697128.43      6805866.52
      2696765.50      6805762.21      2696576.00      6805761.00

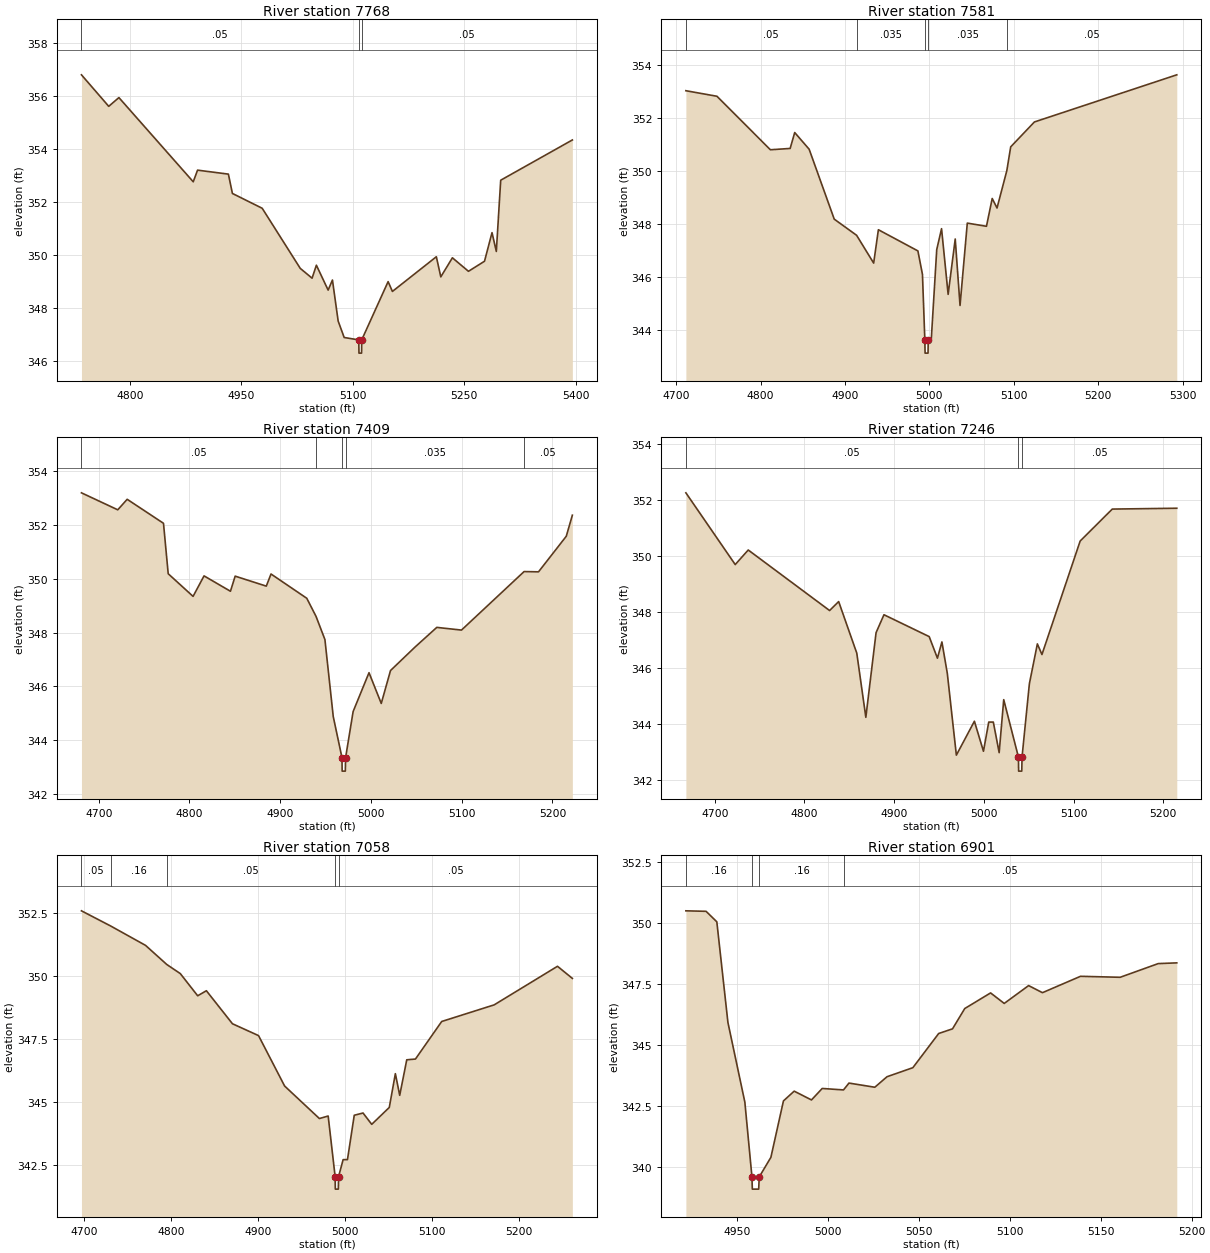
Type RM Length L Ch R = 1,7768,187,187,187
BEGIN DESCRIPTION:
Prairie Creek Trib G7768.042
END DESCRIPTION:
XS GIS Cut Line= 3
      2702619.75      6807507.27      2702376.00      6807611.00
      2702032.20      6807806.71
#Sta/Elev= 30
  4734.8  356.79  4771.5  355.60  4785.2  355.93  4885.2  352.75  4891.0  353.19
  4932.5  353.04  4937.9  352.31  4978.0  351.75  5029.2  349.48  5045.1  349.11
  5050.9  349.60  5066.7  348.66  5072.5  349.04  5080.2  347.49  5088.3  346.87
  5107.9  346.78  5108.2  346.28  5111.7  346.28  5111.9  346.78  5147.4  348.98
  5153.2  348.61  5212.3  349.92  5218.3  349.16  5233.9  349.88  5255.5  349.37
  5277.1  349.75  5287.2  350.83  5293.0  350.12  5298.9  352.81  5395.3  354.33
#Mann=3,-1,0
  4734.8    0.05       0  5107.9    0.05       0  5111.9    0.05       0
Bank Sta=5107.9,5111.9
Exp/Cntr=0.3,0.1

Type RM Length L Ch R = 1,7581,172,172,172
BEGIN DESCRIPTION:
Prairie Creek Trib G7580.59
END DESCRIPTION:
XS GIS Cut Line= 3
      2702539.73      6807374.61      2702276.11      6807489.87
      2702017.49      6807629.04
#Sta/Elev= 30
  4711.6  353.03  4748.4  352.82  4811.7  350.80  4835.1  350.85  4840.5  351.45
  4857.6  350.82  4887.3  348.18  4913.8  347.57  4934.0  346.52  4939.6  347.78
  4986.4  346.98  4991.8  346.09  4994.6  343.62  4994.9  343.12  4998.4  343.12
  4998.6  343.62  5002.2  343.62  5008.7  347.03  5014.4  347.82  5022.2  345.34
  5030.6  347.43  5036.3  344.92  5044.9  348.03  5067.6  347.91  5074.4  348.96
  5080.1  348.60  5091.7  350.01  5096.3  350.91  5124.4  351.85  5293.0  353.63
#Mann=5,-1,0
  4711.6    0.05       0  4913.8   0.035       0  4994.6   0.035       0
  4998.6   0.035       0  5091.7    0.05       0
Bank Sta=4994.6,4998.6
Exp/Cntr=0.3,0.1

Type RM Length L Ch R = 1,7409,163,163,163
BEGIN DESCRIPTION:
Prairie Creek Trib G7408.6
END DESCRIPTION:
XS GIS Cut Line= 3
      2702584.57      6807260.90      2702273.83      6807346.95
      2702059.42      6807389.36
#Sta/Elev= 30
  4681.0  353.18  4721.0  352.55  4731.4  352.94  4771.4  352.05  4776.6  350.18
  4804.0  349.34  4816.1  350.10  4845.2  349.53  4850.4  350.09  4884.7  349.72
  4889.9  350.17  4929.3  349.27  4939.5  348.60  4949.3  347.74  4958.5  344.88
  4968.1  343.36  4968.3  342.86  4971.8  342.86  4972.1  343.36  4980.4  345.07
  4997.9  346.51  5011.4  345.37  5021.6  346.59  5048.6  347.46  5072.6  348.19
  5099.8  348.09  5168.8  350.26  5184.7  350.25  5215.3  351.57  5222.0  352.35
#Mann=5,-1,0
  4681.0    0.05       0  4939.5   0.035       0  4968.1   0.035       0
  4972.1   0.035       0  5168.8    0.05       0
Bank Sta=4968.1,4972.1
Exp/Cntr=0.3,0.1

Type RM Length L Ch R = 1,7246,188,188,188
BEGIN DESCRIPTION:
Prairie Creek Trib G7246.39
END DESCRIPTION:
XS GIS Cut Line= 3
      2702564.86      6807158.71      2702229.29      6807203.07
      2702026.02      6807250.43
#Sta/Elev= 30
  4667.8  352.25  4722.8  349.69  4737.3  350.21  4828.0  348.05  4838.1  348.37
  4858.3  346.53  4868.4  344.24  4879.8  347.26  4888.6  347.90  4939.0  347.12
  4948.2  346.35  4953.2  346.93  4959.2  345.81  4969.3  342.89  4989.4  344.10
  4999.5  343.03  5005.4  344.07  5010.5  344.07  5017.0  342.98  5022.1  344.87
  5038.5  342.82  5038.7  342.32  5042.2  342.32  5042.5  342.82  5050.7  345.44
  5059.6  346.86  5064.7  346.48  5107.3  350.53  5143.1  351.67  5215.0  351.70
#Mann=3,-1,0
  4667.8    0.05       0  5038.5    0.05       0  5042.5    0.05       0
Bank Sta=5038.5,5042.5
Exp/Cntr=0.3,0.1

Type RM Length L Ch R = 1,7058,157,157,157
BEGIN DESCRIPTION:
Prairie Creek Trib G7058.34
END DESCRIPTION:
XS GIS Cut Line= 3
      2702629.68      6807056.27      2702326.51      6807049.41
      2702066.64      6807078.18
#Sta/Elev= 30
  4696.7  352.57  4730.2  351.97  4770.4  351.20  4794.9  350.44  4810.4  350.08
  4830.4  349.20  4840.4  349.40  4870.4  348.09  4900.4  347.62  4930.4  345.62
  4970.4  344.33  4980.5  344.43  4988.5  342.03  4988.7  341.53  4992.2  341.53
  4992.5  342.03  4997.7  342.70  5002.7  342.70  5010.5  344.46  5020.6  344.55
  5030.6  344.10  5050.8  344.77  5057.8  346.11  5062.8  345.25  5070.9  346.66
  5080.9  346.69  5111.1  348.18  5171.5  348.84  5244.3  350.37  5261.4  349.89
#Mann=5,-1,0
  4696.7    0.05       0  4730.2    0.16       0  4794.9    0.05       0
  4988.5    0.05       0  4992.5    0.05       0
Bank Sta=4988.5,4992.5
Exp/Cntr=0.3,0.1

Type RM Length L Ch R = 1,6901,163,163,163
BEGIN DESCRIPTION:
Prairie Creek Trib G6901.43
END DESCRIPTION:
XS GIS Cut Line= 3
      2702345.67      6806867.17      2702275.61      6806910.59
      2702134.59      6807033.82
#Sta/Elev= 30
  4922.1  350.49  4933.2  350.47  4939.1  350.04  4945.2  345.92  4954.5  342.66
  4958.4  339.60  4958.6  339.10  4962.1  339.10  4962.4  339.60  4968.8  340.40
  4975.7  342.71  4981.6  343.11  4991.1  342.75  4997.0  343.22  5008.7  343.16
  5011.7  343.44  5025.9  343.27  5032.6  343.70  5046.8  344.07  5061.0  345.47
  5068.6  345.66  5075.3  346.49  5089.5  347.13  5097.0  346.70  5110.4  347.43
  5118.0  347.14  5138.9  347.81  5160.7  347.77  5181.6  348.33  5191.8  348.36
#Mann=4,-1,0
  4922.1    0.16       0  4958.4    0.07       0  4962.4    0.16       0
  5008.7    0.05       0
Bank Sta=4958.4,4962.4
Exp/Cntr=0.3,0.1

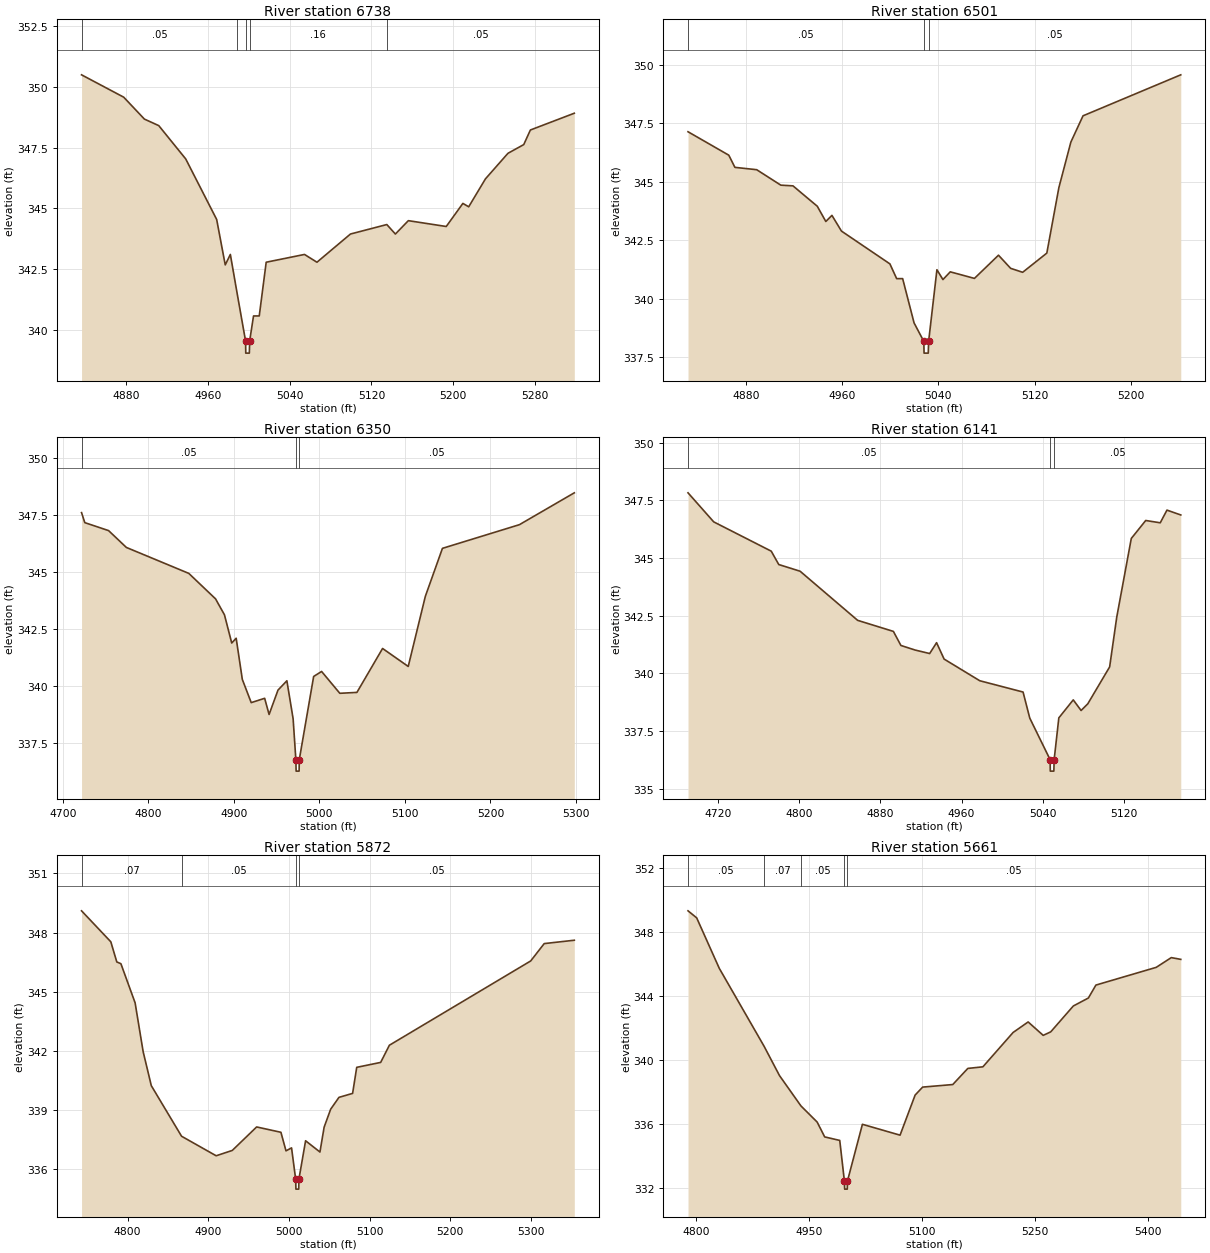
Type RM Length L Ch R = 1,6738,237,237,237
BEGIN DESCRIPTION:
Prairie Creek Trib G6737.7
END DESCRIPTION:
XS GIS Cut Line= 3
      2702251.74      6806600.11      2702227.38      6806767.49
      2702081.39      6807044.76
#Sta/Elev= 30
  4836.1  350.49  4877.4  349.57  4897.6  348.67  4911.7  348.40  4938.1  347.03
  4968.4  344.54  4976.8  342.67  4981.8  343.10  4988.4  341.51  4996.7  339.54
  4996.9  339.04  5000.4  339.04  5000.7  339.54  5004.5  340.57  5010.1  340.57
  5016.9  342.78  5054.4  343.10  5066.6  342.78  5099.4  343.94  5135.0  344.33
  5143.4  343.94  5156.1  344.49  5193.2  344.25  5209.5  345.20  5215.2  345.06
  5231.6  346.21  5253.6  347.26  5269.1  347.62  5275.6  348.22  5318.6  348.91
#Mann=5,-1,0
  4836.1    0.05       0  4988.4    0.16       0  4996.7    0.07       0
  5000.7    0.16       0  5135.0    0.05       0
Bank Sta=4996.7,5000.7
Exp/Cntr=0.3,0.1

Type RM Length L Ch R = 1,6501,151,151,151
BEGIN DESCRIPTION:
Prairie Creek Trib G6501.4
END DESCRIPTION:
XS GIS Cut Line= 3
      2702065.46      6806644.36      2702043.91      6806817.03
      2702025.36      6807052.09
#Sta/Elev= 30
  4831.8  347.13  4865.7  346.13  4870.8  345.61  4888.9  345.51  4909.0  344.85
  4919.1  344.82  4939.3  343.95  4946.4  343.30  4951.5  343.56  4959.4  342.89
  4999.7  341.49  5005.3  340.86  5010.3  340.86  5019.8  338.97  5027.9  338.18
  5028.1  337.68  5031.6  337.68  5031.9  338.18  5038.8  341.24  5043.8  340.82
  5049.9  341.15  5070.0  340.87  5090.0  341.86  5100.1  341.30  5110.1  341.13
  5130.2  341.95  5140.2  344.74  5150.2  346.69  5160.3  347.81  5241.6  349.56
#Mann=3,-1,0
  4831.8    0.05       0  5027.9    0.05       0  5031.9    0.05       0
Bank Sta=5027.9,5031.9
Exp/Cntr=0.3,0.1

Type RM Length L Ch R = 1,6350,209,209,209
BEGIN DESCRIPTION:
Prairie Creek Trib G6350.25
END DESCRIPTION:
XS GIS Cut Line= 3
      2701991.60      6806480.70      2701910.37      6806756.00
      2701906.77      6807045.15
#Sta/Elev= 30
  4721.9  347.61  4725.7  347.17  4753.5  346.82  4774.3  346.08  4847.3  344.94
  4878.6  343.82  4889.0  343.12  4897.5  341.88  4902.7  342.09  4909.9  340.28
  4920.3  339.26  4936.0  339.45  4941.2  338.74  4951.6  339.81  4962.0  340.22
  4969.3  338.55  4972.5  336.75  4972.8  336.25  4976.3  336.25  4976.5  336.75
  4993.3  340.41  5002.6  340.63  5023.9  339.67  5043.9  339.71  5073.9  341.64
  5103.9  340.85  5123.9  343.93  5143.9  346.04  5233.9  347.08  5298.1  348.48
#Mann=3,-1,0
  4721.9    0.05       0  4972.5    0.05       0  4976.5    0.05       0
Bank Sta=4972.5,4976.5
Exp/Cntr=0.3,0.1

Type RM Length L Ch R = 1,6141,269,269,269
BEGIN DESCRIPTION:
Prairie Creek Trib G6140.85
END DESCRIPTION:
XS GIS Cut Line= 3
      2701972.33      6806421.44      2701745.51      6806632.78
      2701612.90      6806746.78
#Sta/Elev= 30
  4690.8  347.83  4716.1  346.57  4772.7  345.30  4780.1  344.72  4801.1  344.43
  4857.7  342.30  4892.9  341.82  4900.3  341.21  4914.4  341.01  4928.6  340.86
  4935.4  341.33  4942.8  340.62  4977.9  339.68  5020.5  339.19  5027.1  338.06
  5047.1  336.26  5047.3  335.76  5050.8  335.76  5051.1  336.26  5055.7  338.07
  5069.9  338.85  5077.6  338.39  5084.2  338.68  5105.7  340.28  5112.7  342.44
  5127.0  345.85  5141.2  346.63  5155.5  346.53  5162.1  347.08  5175.7  346.87
#Mann=3,-1,0
  4690.8    0.05       0  5047.1    0.05       0  5051.1    0.05       0
Bank Sta=5047.1,5051.1
Exp/Cntr=0.3,0.1

Type RM Length L Ch R = 1,5872,211,211,211
BEGIN DESCRIPTION:
Prairie Creek Trib G5871.79
END DESCRIPTION:
XS GIS Cut Line= 3
      2701675.43      6806154.92      2701650.45      6806414.16
      2701561.90      6806753.35
#Sta/Elev= 30
  4742.8  349.10  4779.1  347.53  4786.5  346.51  4791.6  346.42  4809.2  344.44
  4819.2  341.96  4829.3  340.24  4866.8  337.68  4909.7  336.69  4929.7  336.96
  4959.9  338.15  4990.0  337.88  4996.3  336.94  5003.2  337.09  5008.3  335.50
  5008.6  335.00  5012.1  335.00  5012.3  335.50  5020.6  337.45  5038.4  336.88
  5043.6  338.14  5051.7  339.05  5062.0  339.65  5078.9  339.85  5084.0  341.17
  5113.7  341.42  5124.5  342.29  5299.7  346.56  5316.5  347.44  5353.8  347.61
#Mann=4,-1,0
  4742.8    0.07       0  4866.8    0.05       0  5008.3    0.05       0
  5012.3    0.05       0
Bank Sta=5008.3,5012.3
Exp/Cntr=0.3,0.1

Type RM Length L Ch R = 1,5661,223,223,223
BEGIN DESCRIPTION:
Prairie Creek Trib G5660.81
END DESCRIPTION:
XS GIS Cut Line= 3
      2701481.46      6806099.51      2701476.65      6806312.39
      2701462.27      6806753.62
#Sta/Elev= 30
  4788.9  349.34  4800.4  348.90  4830.4  345.74  4889.9  340.86  4910.4  339.02
  4938.9  337.12  4960.4  336.11  4970.4  335.18  4990.4  334.96  4996.6  332.41
  4996.9  331.91  5000.4  331.91  5000.6  332.41  5020.5  335.97  5070.5  335.29
  5090.5  337.80  5100.5  338.30  5140.5  338.46  5160.5  339.47  5180.5  339.57
  5220.6  341.72  5240.6  342.38  5260.6  341.54  5270.6  341.76  5300.6  343.38
  5320.6  343.88  5330.6  344.69  5410.7  345.80  5430.7  346.41  5443.3  346.30
#Mann=5,-1,0
  4788.9    0.05       0  4889.9    0.07       0  4938.9    0.05       0
  4996.6    0.05       0  5000.6    0.05       0
Bank Sta=4996.6,5000.6
Exp/Cntr=0.3,0.1

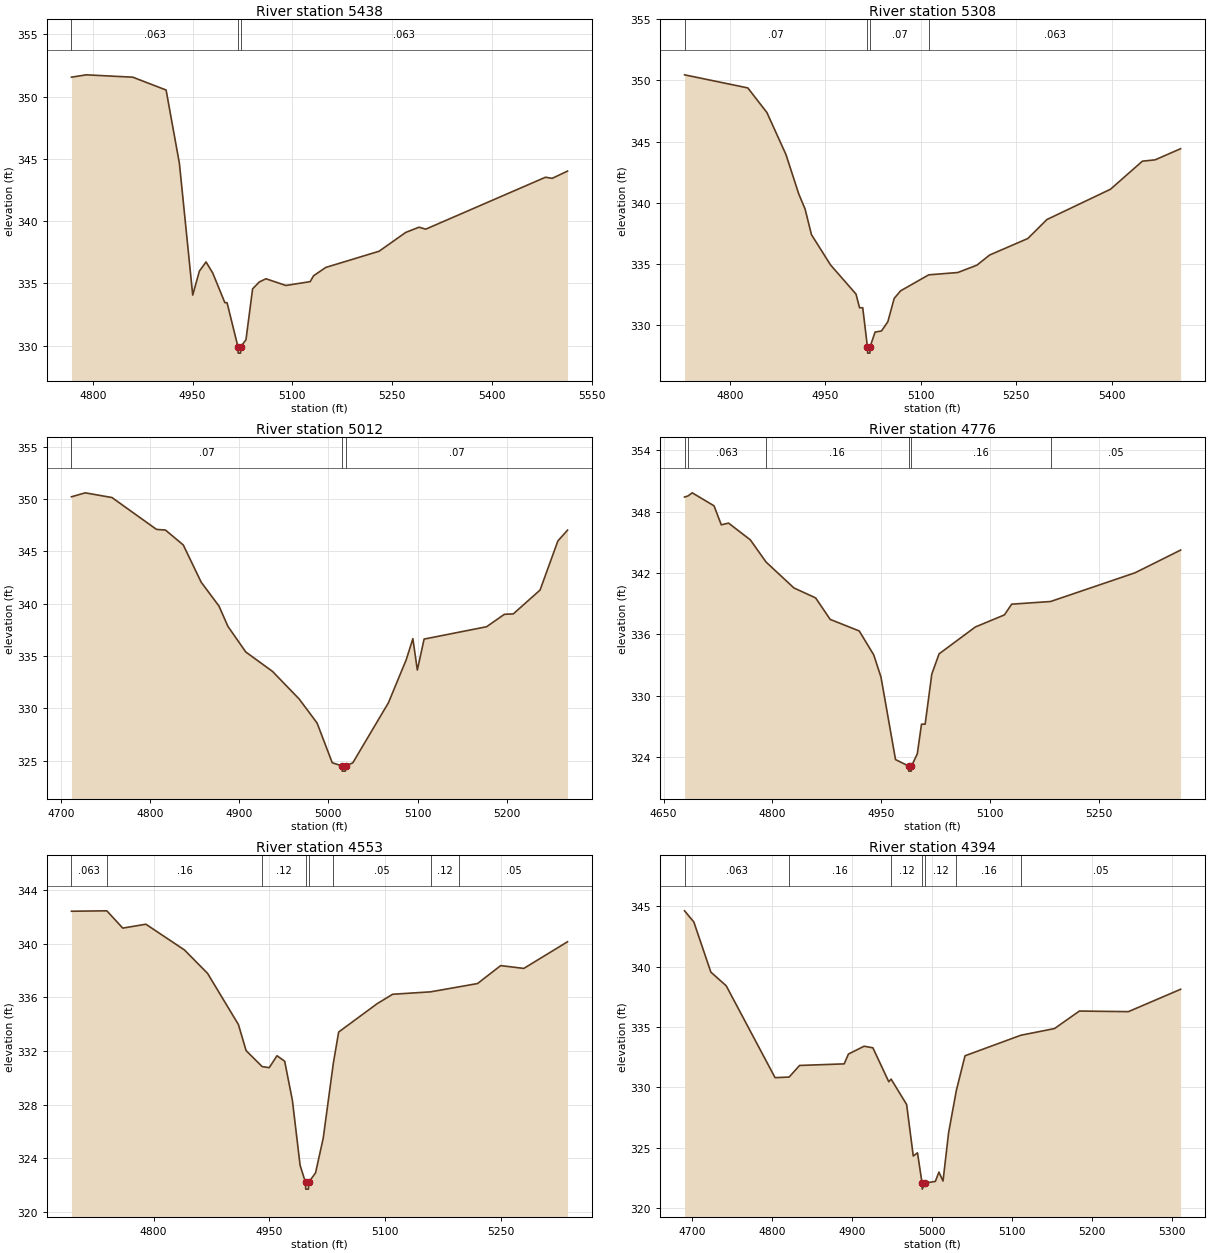
Type RM Length L Ch R = 1,5438,130,130,130
BEGIN DESCRIPTION:
Prairie Creek Trib G5438
END DESCRIPTION:
XS GIS Cut Line= 3
      2701256.93      6806078.81      2701253.86      6806312.55
      2701242.30      6806824.06
#Sta/Elev= 30
  4768.1  351.56  4790.3  351.75  4860.3  351.56  4910.3  350.53  4930.3  344.64
  4950.3  334.07  4960.3  335.99  4970.3  336.73  4980.3  335.85  4998.6  333.46
  5001.9  333.46  5018.3  329.91  5018.6  329.41  5022.1  329.41  5022.3  329.91
  5030.3  330.48  5040.3  334.57  5050.3  335.12  5060.3  335.38  5090.3  334.84
  5126.8  335.15  5131.9  335.62  5150.3  336.29  5230.4  337.59  5270.4  339.10
  5290.4  339.52  5300.4  339.36  5480.4  343.53  5490.4  343.44  5513.5  344.02
#Mann=3,-1,0
  4768.1   0.063       0  5018.3   0.063       0  5022.3   0.063       0
Bank Sta=5018.3,5022.3
Exp/Cntr=0.3,0.1

Type RM Length L Ch R = 1,5308,296,296,296
BEGIN DESCRIPTION:
Prairie Creek Trib G5308.29
END DESCRIPTION:
XS GIS Cut Line= 3
      2701133.11      6806091.67      2701140.13      6806367.13
      2701139.78      6806871.08
#Sta/Elev= 30
  4729.0  350.46  4828.4  349.39  4858.4  347.38  4888.4  343.94  4908.4  340.73
  4918.4  339.49  4928.4  337.40  4958.4  334.92  4998.4  332.54  5004.0  331.42
  5009.0  331.42  5016.4  328.21  5016.7  327.71  5020.2  327.71  5020.4  328.21
  5028.4  329.43  5038.4  329.52  5048.4  330.27  5058.4  332.18  5068.4  332.80
  5112.7  334.11  5158.4  334.30  5188.4  334.90  5208.4  335.73  5268.4  337.08
  5298.4  338.63  5398.4  341.11  5448.4  343.40  5468.4  343.51  5508.5  344.42
#Mann=4,-1,0
  4729.0    0.07       0  5016.4    0.07       0  5020.4    0.07       0
  5112.7   0.063       0
Bank Sta=5016.4,5020.4
Exp/Cntr=0.3,0.1

Type RM Length L Ch R = 1,5012,236,236,236
BEGIN DESCRIPTION:
Prairie Creek Trib G5011.53
END DESCRIPTION:
XS GIS Cut Line= 3
      2700952.35      6806295.62      2700953.05      6806589.99
      2700947.14      6806851.75
#Sta/Elev= 30
  4712.0  350.23  4727.4  350.61  4757.4  350.16  4807.4  347.11  4817.4  347.05
  4837.4  345.62  4857.4  342.07  4877.4  339.78  4887.4  337.84  4907.4  335.39
  4937.4  333.53  4967.4  330.88  4987.4  328.59  5004.4  324.79  5015.4  324.49
  5015.6  323.99  5019.1  323.99  5019.4  324.49  5027.4  324.78  5067.4  330.53
  5087.4  334.66  5094.8  336.66  5099.8  333.66  5107.4  336.62  5177.4  337.80
  5197.4  338.99  5207.4  339.03  5237.4  341.31  5257.4  346.01  5268.2  347.04
#Mann=3,-1,0
  4712.0    0.07       0  5015.4    0.07       0  5019.4    0.07       0
Bank Sta=5015.4,5019.4
Exp/Cntr=0.3,0.1

Type RM Length L Ch R = 1,4776,223,223,223
BEGIN DESCRIPTION:
Mapping XS db05b04e
END DESCRIPTION:
XS GIS Cut Line= 3
      2700766.37      6806340.44      2700767.81      6806667.74
      2700773.00      6807023.70
#Sta/Elev= 30
  4678.9  349.42  4683.8  349.53  4689.5  349.83  4719.5  348.56  4729.5  346.70
  4739.5  346.87  4769.5  345.23  4791.2  343.06  4829.5  340.53  4859.5  339.55
  4879.5  337.45  4919.5  336.32  4939.5  333.98  4949.5  331.80  4969.5  323.74
  4987.5  323.11  4987.7  322.61  4991.2  322.61  4991.5  323.11  4999.5  324.30
  5005.3  327.20  5010.3  327.20  5019.5  332.11  5029.5  334.08  5079.5  336.71
  5119.5  337.89  5129.5  338.94  5183.1  339.20  5299.5  342.01  5362.2  344.23
#Mann=6,-1,0
  4678.9    0.07       0  4683.8   0.063       0  4791.2    0.16       0
  4987.5    0.07       0  4991.5    0.16       0  5183.1    0.05       0
Bank Sta=4987.5,4991.5
Exp/Cntr=0.3,0.1

Type RM Length L Ch R = 1,4553,159,159,159
BEGIN DESCRIPTION:
Prairie Creek Trib G4553.4
END DESCRIPTION:
XS GIS Cut Line= 3
      2700580.83      6806304.49      2700577.52      6806613.98
      2700571.82      6806947.72
#Sta/Elev= 30
  4693.5  342.44  4739.4  342.47  4760.0  341.18  4790.0  341.47  4840.0  339.55
  4870.0  337.80  4910.0  333.98  4920.0  332.03  4940.8  330.84  4950.0  330.76
  4960.0  331.65  4970.0  331.24  4980.0  328.32  4990.0  323.47  4997.0  322.19
  4997.3  321.69  5000.8  321.69  5001.0  322.19  5010.0  322.90  5020.0  325.50
  5033.1  331.09  5040.0  333.42  5090.0  335.54  5110.0  336.24  5159.1  336.42
  5196.6  336.80  5220.1  337.04  5250.1  338.38  5280.1  338.17  5336.8  340.16
#Mann=8,-1,0
  4693.5   0.063       0  4739.4    0.16       0  4940.8    0.12       0
  4997.0    0.07       0  5001.0    0.12       0  5033.1    0.05       0
  5159.1    0.12       0  5196.6    0.05       0
Bank Sta=4997,5001
Exp/Cntr=0.3,0.1

Type RM Length L Ch R = 1,4394,168,168,168
BEGIN DESCRIPTION:
Prairie Creek Trib G4393.89
END DESCRIPTION:
XS GIS Cut Line= 3
      2700312.09      6806320.07      2700419.42      6806614.74
      2700482.50      6806914.88
#Sta/Elev= 30
  4690.4  344.61  4702.0  343.69  4723.3  339.54  4742.5  338.41  4803.6  330.81
  4821.2  330.86  4834.2  331.82  4890.0  331.95  4895.3  332.76  4914.9  333.41
  4925.9  333.28  4945.8  330.47  4948.7  330.69  4968.1  328.59  4976.4  324.33
  4981.7  324.59  4987.4  322.09  4987.6  321.59  4991.4  322.09  5004.0  322.23
  5008.5  323.00  5013.6  322.26  5020.6  326.26  5030.3  329.76  5041.1  332.62
  5111.0  334.32  5153.0  334.87  5184.1  336.32  5245.4  336.27  5310.7  338.12
#Mann=7,-1,0
  4690.4   0.063       0  4821.2    0.16       0  4948.7    0.12       0
  4987.4    0.07       0  4991.4    0.12       0  5030.3    0.16       0
  5111.0    0.05       0
Bank Sta=4987.4,4991.4
Exp/Cntr=0.3,0.1

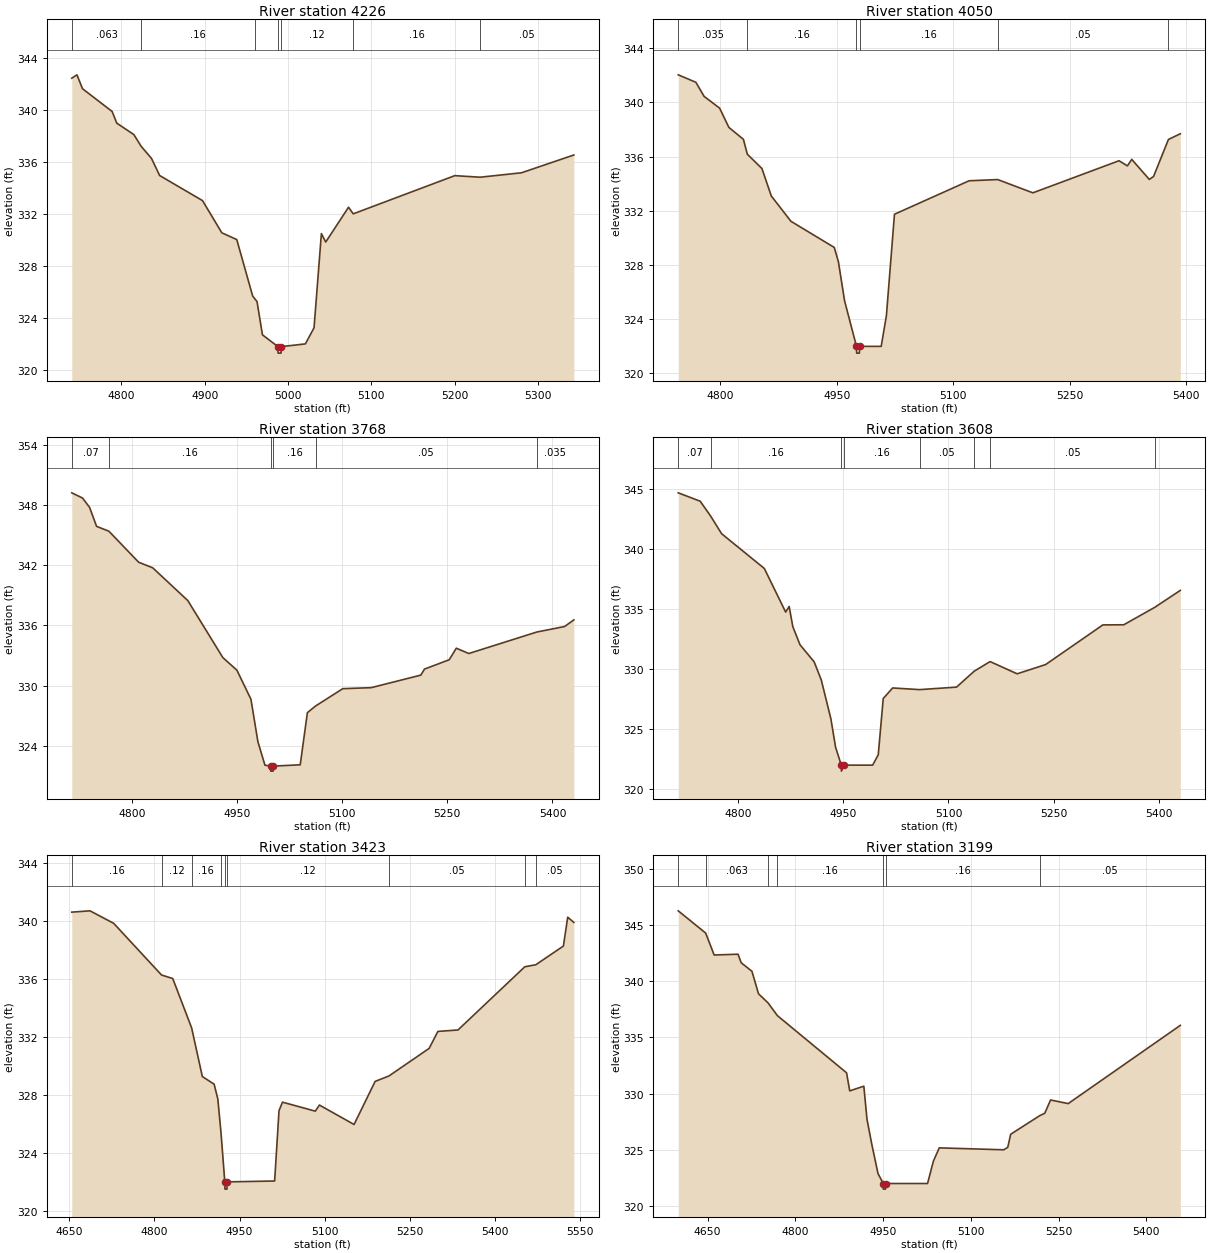
Type RM Length L Ch R = 1,4226,176,176,176
BEGIN DESCRIPTION:
Prairie Creek Trib G4225.78
END DESCRIPTION:
XS GIS Cut Line= 3
      2700189.92      6806358.48      2700252.03      6806619.63
      2700338.52      6806942.00
#Sta/Elev= 30
  4740.6  342.45  4746.8  342.71  4753.5  341.64  4789.0  339.89  4794.6  338.99
  4815.1  338.11  4823.8  337.21  4836.3  336.27  4846.0  334.96  4897.4  333.03
  4920.6  330.55  4938.5  330.03  4957.6  325.68  4960.7  325.43  4962.8  325.26
  4969.3  322.70  4987.9  321.79  4988.1  321.29  4991.6  321.29  4991.9  321.79
  5020.8  322.00  5031.2  323.24  5040.0  330.49  5045.2  329.84  5072.6  332.52
  5078.2  332.01  5200.0  334.95  5230.5  334.83  5280.0  335.17  5342.8  336.54
#Mann=7,-1,0
  4740.6   0.063       0  4823.8    0.16       0  4960.7    0.12       0
  4987.9    0.07       0  4991.9    0.12       0  5078.2    0.16       0
  5230.5    0.05       0
Bank Sta=4987.9,4991.9
Exp/Cntr=0.3,0.1

Type RM Length L Ch R = 1,4050,282,282,282
BEGIN DESCRIPTION:
Prairie Creek Trib G4049.56
END DESCRIPTION:
XS GIS Cut Line= 3
      2700011.40      6806449.71      2700097.93      6806687.59
      2700268.23      6807042.08
#Sta/Elev= 30
  4745.9  342.04  4768.6  341.49  4779.2  340.45  4799.2  339.58  4811.1  338.16
  4829.8  337.28  4834.9  336.18  4853.7  335.12  4865.7  333.10  4891.0  331.23
  4946.8  329.30  4952.1  328.25  4960.1  325.35  4975.4  322.00  4975.6  321.50
  4979.1  321.50  4979.4  322.00  5007.2  322.00  5013.9  324.26  5024.3  331.75
  5120.4  334.22  5157.2  334.31  5202.5  333.33  5313.4  335.70  5324.2  335.32
  5329.8  335.80  5352.4  334.32  5357.9  334.54  5377.0  337.27  5392.3  337.69
#Mann=6,-1,0
  4745.9   0.035       0  4834.9    0.16       0  4975.4    0.07       0
  4979.4    0.16       0  5157.2    0.05       0  5377.0   0.035       0
Bank Sta=4975.4,4979.4
Exp/Cntr=0.3,0.1

Type RM Length L Ch R = 1,3768,160,160,160
BEGIN DESCRIPTION:
Prairie Creek Trib G3767.66
END DESCRIPTION:
XS GIS Cut Line= 3
      2699834.19      6806475.57      2699839.32      6806770.10
      2699903.36      6807186.63
#Sta/Elev= 30
  4714.5  349.21  4729.9  348.69  4739.9  347.76  4749.9  345.87  4767.4  345.39
  4809.9  342.30  4830.0  341.74  4880.0  338.48  4930.0  332.80  4950.0  331.55
  4970.0  328.66  4980.0  324.41  4990.0  322.09  4998.0  322.00  4998.2  321.50
  5001.7  321.50  5002.0  322.00  5040.3  322.13  5050.5  327.32  5062.1  327.98
  5101.0  329.71  5141.5  329.81  5212.3  331.06  5217.5  331.66  5252.8  332.59
  5262.9  333.74  5280.7  333.21  5377.7  335.35  5417.4  335.90  5430.5  336.56
#Mann=6,-1,0
  4714.5    0.07       0  4767.4    0.16       0  4998.0    0.07       0
  5002.0    0.16       0  5062.1    0.05       0  5377.7   0.035       0
Bank Sta=4998,5002
Exp/Cntr=0.3,0.1

Type RM Length L Ch R = 1,3608,185,185,185
BEGIN DESCRIPTION:
Prairie Creek Trib G3607.61
END DESCRIPTION:
XS GIS Cut Line= 3
      2699728.21      6806480.14      2699677.56      6806769.92
      2699571.75      6807177.84
#Sta/Elev= 30
  4714.8  344.72  4746.1  344.02  4761.0  342.78  4776.6  341.31  4837.5  338.41
  4867.9  334.77  4872.9  335.24  4878.1  333.56  4888.3  332.05  4908.6  330.61
  4918.7  329.10  4932.4  325.86  4939.0  323.51  4947.2  322.00  4947.4  321.50
  4951.2  322.00  4991.9  322.00  4999.9  322.87  5007.0  327.56  5020.4  328.44
  5058.8  328.30  5111.5  328.51  5136.7  329.84  5159.3  330.64  5197.8  329.62
  5238.4  330.39  5320.0  333.70  5349.8  333.71  5394.1  335.17  5430.4  336.58
#Mann=8,-1,0
  4714.8    0.07       0  4761.0    0.16       0  4947.2    0.07       0
  4951.2    0.16       0  5058.8    0.05       0  5136.7    0.12       0
  5159.3    0.05       0  5394.1   0.035       0
Bank Sta=4947.2,4951.2
Exp/Cntr=0.3,0.1

Type RM Length L Ch R = 1,3423,224,224,224
BEGIN DESCRIPTION:
Prairie Creek Trib G3422.94
END DESCRIPTION:
XS GIS Cut Line= 3
      2699613.05      6806370.14      2699514.19      6806710.82
      2699417.17      6807231.63
#Sta/Elev= 30
  4654.5  340.61  4686.6  340.70  4728.3  339.84  4812.7  336.27  4832.4  336.03
  4865.7  332.62  4884.5  329.27  4905.3  328.74  4911.8  327.72  4917.4  325.40
  4924.1  322.00  4924.4  321.50  4927.9  321.50  4928.1  322.00  5011.9  322.06
  5019.6  326.91  5025.7  327.50  5083.5  326.88  5090.8  327.30  5151.8  325.96
  5188.9  328.93  5213.4  329.31  5284.1  331.21  5299.5  332.38  5334.9  332.48
  5452.6  336.84  5472.0  336.98  5520.6  338.27  5528.2  340.26  5539.0  339.90
#Mann=9,-1,0
  4654.5    0.16       0  4812.7    0.12       0  4865.7    0.16       0
  4917.4    0.12       0  4924.1    0.07       0  4928.1    0.12       0
  5213.4    0.05       0  5452.6   0.035       0  5472.0    0.05       0
Bank Sta=4924.1,4928.1
Exp/Cntr=0.3,0.1

Type RM Length L Ch R = 1,3199,249,249,249
BEGIN DESCRIPTION:
Prairie Creek Trib G3199.06
END DESCRIPTION:
XS GIS Cut Line= 3
      2699191.67      6806274.06      2699342.08      6806648.07
      2699367.14      6807102.36
#Sta/Elev= 30
  4599.8  346.26  4646.7  344.28  4661.2  342.33  4702.0  342.40  4707.4  341.64
  4725.8  340.88  4737.0  338.88  4753.3  338.07  4769.2  336.94  4887.5  331.85
  4892.9  330.24  4917.0  330.66  4922.4  327.72  4930.6  325.49  4941.2  322.89
  4950.2  322.00  4950.4  321.50  4953.9  321.50  4954.2  322.00  5025.9  322.00
  5035.9  323.99  5045.9  325.17  5156.1  325.00  5163.0  325.22  5168.0  326.38
  5217.4  328.03  5226.2  328.25  5236.2  329.43  5266.3  329.11  5457.9  336.07
#Mann=7,-1,0
  4599.8   0.035       0  4646.7   0.063       0  4753.3   0.035       0
  4769.2    0.16       0  4950.2    0.07       0  4954.2    0.16       0
  5217.4    0.05       0
Bank Sta=4950.2,4954.2
Exp/Cntr=0.3,0.1

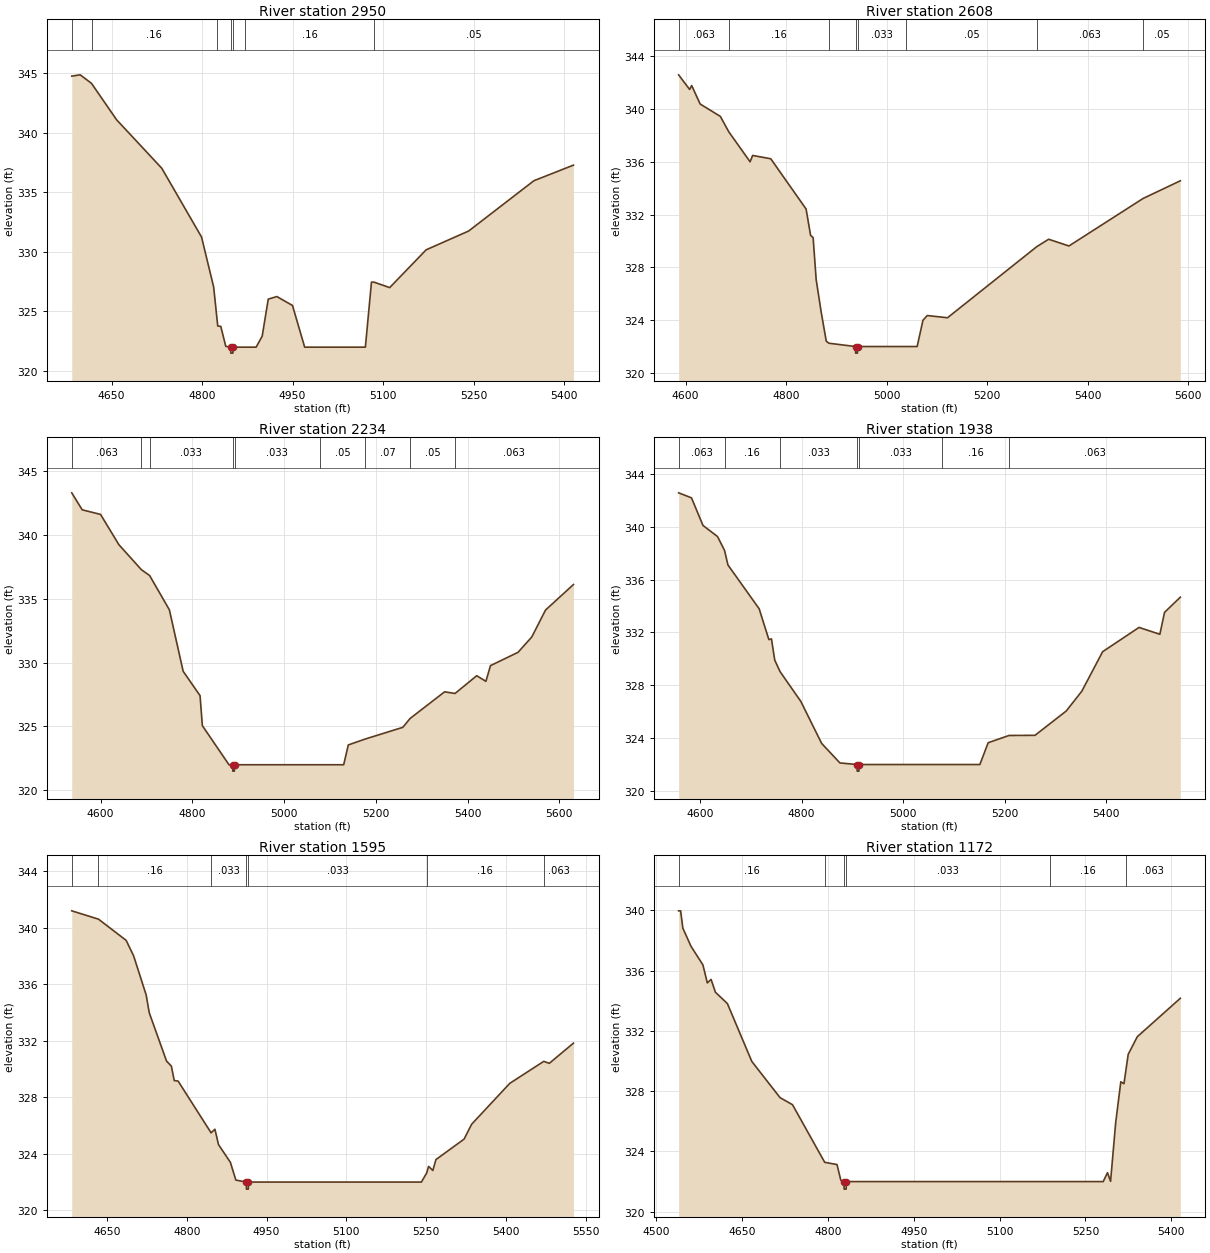
Type RM Length L Ch R = 1,2950,342,342,342
BEGIN DESCRIPTION:
Prairie Creek Trib G2950.45
END DESCRIPTION:
XS GIS Cut Line= 3
      2699115.39      6806397.08      2699159.02      6806810.19
      2699208.53      6807223.42
#Sta/Elev= 30
  4584.0  344.75  4598.0  344.86  4616.8  344.14  4658.3  341.09  4733.2  337.02
  4799.1  331.25  4819.2  327.06  4825.0  324.26  4826.0  323.78  4831.1  323.74
  4839.3  322.07  4847.4  322.00  4847.6  321.50  4851.1  321.50  4851.4  322.00
  4871.6  322.00  4889.6  322.00  4899.7  322.93  4909.7  326.03  4923.9  326.25
  4949.9  325.50  4970.1  322.00  5070.7  322.00  5080.8  327.46  5084.9  327.46
  5111.0  327.00  5171.4  330.17  5241.9  331.75  5350.0  335.97  5415.6  337.28
#Mann=7,-1,0
  4584.0   0.063       0  4616.8    0.16       0  4825.0    0.07       0
  4847.4    0.07       0  4851.4    0.07       0  4871.6    0.16       0
  5084.9    0.05       0
Bank Sta=4847.4,4851.4
Exp/Cntr=0.3,0.1

Type RM Length L Ch R = 1,2608,374,374,374
BEGIN DESCRIPTION:
Prairie Creek Trib G2608.46
END DESCRIPTION:
XS GIS Cut Line= 3
      2698798.84      6806348.32      2698833.59      6806764.77
      2698900.02      6807341.16
#Sta/Elev= 30
  4586.0  342.59  4607.9  341.48  4612.0  341.78  4628.8  340.38  4669.0  339.44
  4685.8  338.27  4728.2  336.00  4733.2  336.48  4769.3  336.23  4839.6  332.42
  4848.5  330.43  4853.6  330.25  4859.6  327.08  4869.7  324.59  4879.7  322.41
  4885.0  322.25  4937.9  322.00  4938.2  321.50  4941.7  321.50  4941.9  322.00
  5037.7  322.00  5060.5  322.00  5072.1  323.99  5080.6  324.35  5120.9  324.18
  5298.9  329.58  5322.2  330.13  5362.5  329.62  5510.0  333.22  5584.1  334.56
#Mann=8,-1,0
  4586.0   0.063       0  4685.8    0.16       0  4885.0   0.033       0
  4937.9   0.033       0  4941.9   0.033       0  5037.7    0.05       0
  5298.9   0.063       0  5510.0    0.05       0
Bank Sta=4937.9,4941.9
Exp/Cntr=0.3,0.1

Type RM Length L Ch R = 1,2234,296,296,296
BEGIN DESCRIPTION:
Prairie Creek Trib G2234.35
END DESCRIPTION:
XS GIS Cut Line= 3
      2698489.98      6806248.25      2698474.99      6806718.08
      2698489.64      6807341.84
#Sta/Elev= 30
  4537.0  343.29  4559.8  341.96  4599.8  341.60  4639.8  339.23  4688.9  337.27
  4706.7  336.82  4749.9  334.13  4779.9  329.32  4816.8  327.41  4821.8  325.06
  4879.9  322.00  4887.9  322.00  4888.2  321.50  4891.7  321.50  4891.9  322.00
  5078.7  322.00  5130.0  322.00  5140.0  323.55  5176.7  324.01  5259.0  324.93
  5274.7  325.62  5350.1  327.71  5372.8  327.58  5420.1  328.97  5440.1  328.53
  5450.1  329.76  5510.1  330.80  5540.1  332.00  5570.1  334.11  5631.0  336.11
#Mann=9,-1,0
  4537.0   0.063       0  4688.9    0.16       0  4706.7   0.033       0
  4887.9   0.033       0  4891.9   0.033       0  5078.7    0.05       0
  5176.7    0.07       0  5274.7    0.05       0  5372.8   0.063       0
Bank Sta=4887.9,4891.9
Exp/Cntr=0.3,0.1

Type RM Length L Ch R = 1,1938,343,343,343
BEGIN DESCRIPTION:
Prairie Creek Trib G1938.04
END DESCRIPTION:
XS GIS Cut Line= 3
      2698310.93      6806166.33      2698212.94      6806600.49
      2698095.14      6807130.37
#Sta/Elev= 30
  4557.9  342.57  4583.2  342.19  4605.9  340.10  4634.5  339.26  4648.3  338.21
  4655.0  337.11  4716.5  333.79  4735.6  331.46  4740.7  331.51  4747.2  329.90
  4757.7  329.03  4798.5  326.78  4839.5  323.60  4875.5  322.12  4909.2  322.00
  4909.5  321.50  4913.0  321.50  4913.2  322.00  5077.4  322.00  5151.1  322.00
  5167.4  323.65  5208.5  324.20  5259.6  324.21  5321.1  326.05  5351.8  327.55
  5392.8  330.54  5464.5  332.38  5505.5  331.86  5514.7  333.52  5545.8  334.67
#Mann=7,-1,0
  4557.9   0.063       0  4648.3    0.16       0  4757.7   0.033       0
  4909.2   0.033       0  4913.2   0.033       0  5077.4    0.16       0
  5208.5   0.063       0
Bank Sta=4909.2,4913.2
Exp/Cntr=0.3,0.1

Type RM Length L Ch R = 1,1595,423,423,423
BEGIN DESCRIPTION:
Prairie Creek Trib G1594.92
END DESCRIPTION:
XS GIS Cut Line= 3
      2698095.47      6806036.76      2697927.75      6806433.02
      2697668.70      6806876.28
#Sta/Elev= 30
  4583.5  341.21  4633.8  340.62  4685.8  339.12  4699.9  338.02  4723.5  335.25
  4729.3  333.99  4761.8  330.57  4770.9  330.21  4776.3  329.19  4783.6  329.15
  4845.6  325.49  4852.8  325.74  4859.6  324.65  4881.9  323.40  4892.2  322.14
  4911.9  322.00  4912.1  321.50  4915.6  321.50  4915.9  322.00  5241.2  322.00
  5251.2  322.65  5254.7  323.11  5262.7  322.82  5268.5  323.59  5321.4  325.04
  5335.8  326.10  5407.4  328.99  5471.4  330.55  5481.8  330.41  5527.2  331.84
#Mann=7,-1,0
  4583.5   0.063       0  4633.8    0.16       0  4845.6   0.033       0
  4911.9   0.033       0  4915.9   0.033       0  5251.2    0.16       0
  5471.4   0.063       0
Bank Sta=4911.9,4915.9
Exp/Cntr=0.3,0.1

Type RM Length L Ch R = 1,1172,545,545,545
BEGIN DESCRIPTION:
Prairie Creek Trib G1171.56
END DESCRIPTION:
XS GIS Cut Line= 3
      2697926.25      6805910.87      2697575.19      6806219.89
      2697410.59      6806594.42
#Sta/Elev= 30
  4539.1  339.96  4542.6  339.96  4546.5  338.81  4560.7  337.61  4581.6  336.37
  4589.2  335.18  4595.8  335.41  4603.4  334.56  4624.3  333.81  4667.0  329.97
  4716.3  327.57  4738.1  327.10  4794.4  323.28  4815.9  323.13  4822.6  322.08
  4828.1  322.00  4828.4  321.50  4831.9  321.50  4832.1  322.00  5188.1  322.00
  5281.1  322.00  5288.6  322.59  5294.0  322.02  5302.9  325.90  5311.9  328.62
  5317.4  328.49  5320.1  329.20  5324.8  330.44  5340.7  331.61  5415.9  334.16
#Mann=6,-1,0
  4539.1    0.16       0  4794.4   0.033       0  4828.1   0.033       0
  4832.1   0.033       0  5188.1    0.16       0  5320.1   0.063       0
Bank Sta=4828.1,4832.1
Exp/Cntr=0.3,0.1

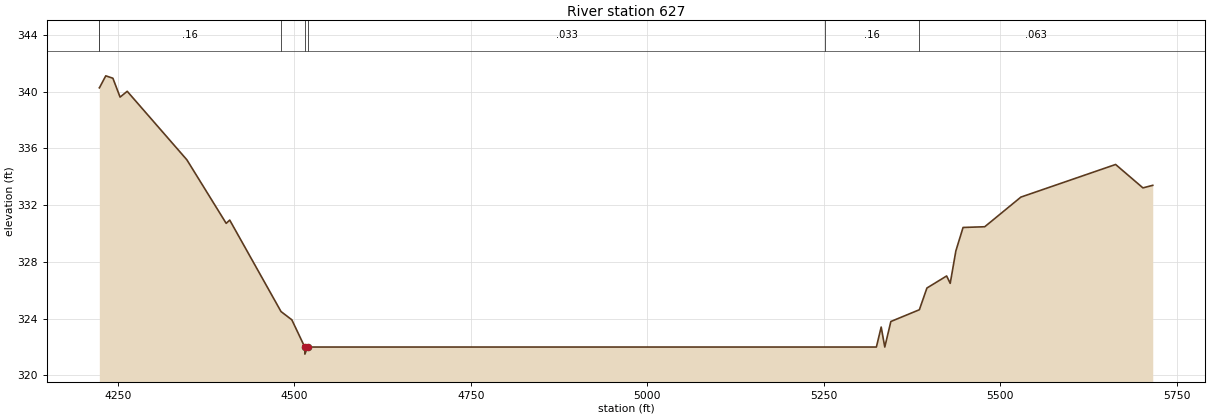
Type RM Length L Ch R = 1,627,0,0,0
BEGIN DESCRIPTION:
Prairie Creek Trib G627.003
END DESCRIPTION:
XS GIS Cut Line= 3
      2697924.98      6805765.81      2697159.52      6805893.88
      2697313.14      6806593.41
#Sta/Elev= 30
  4223.9  340.27  4224.1  340.28  4233.0  341.12  4243.1  340.95  4253.3  339.62
  4263.4  340.03  4347.9  335.20  4403.6  330.72  4408.6  330.95  4481.3  324.50
  4496.6  323.92  4514.9  322.00  4515.1  321.50  4518.9  322.00  5252.4  322.00
  5324.7  322.00  5331.5  323.41  5336.6  322.00  5345.2  323.80  5385.6  324.63
  5396.3  326.16  5424.2  327.01  5429.3  326.49  5437.3  328.78  5447.5  330.43
  5478.2  330.48  5529.4  332.57  5663.6  334.87  5702.3  333.22  5716.2  333.40
#Mann=7,-1,0
  4223.9   0.063       0  4224.1    0.16       0  4481.3   0.033       0
  4514.9   0.033       0  4518.9   0.033       0  5252.4    0.16       0
  5385.6   0.063       0
Bank Sta=4514.9,4518.9
Exp/Cntr=0.3,0.1

Chan Stop Cuts=-1