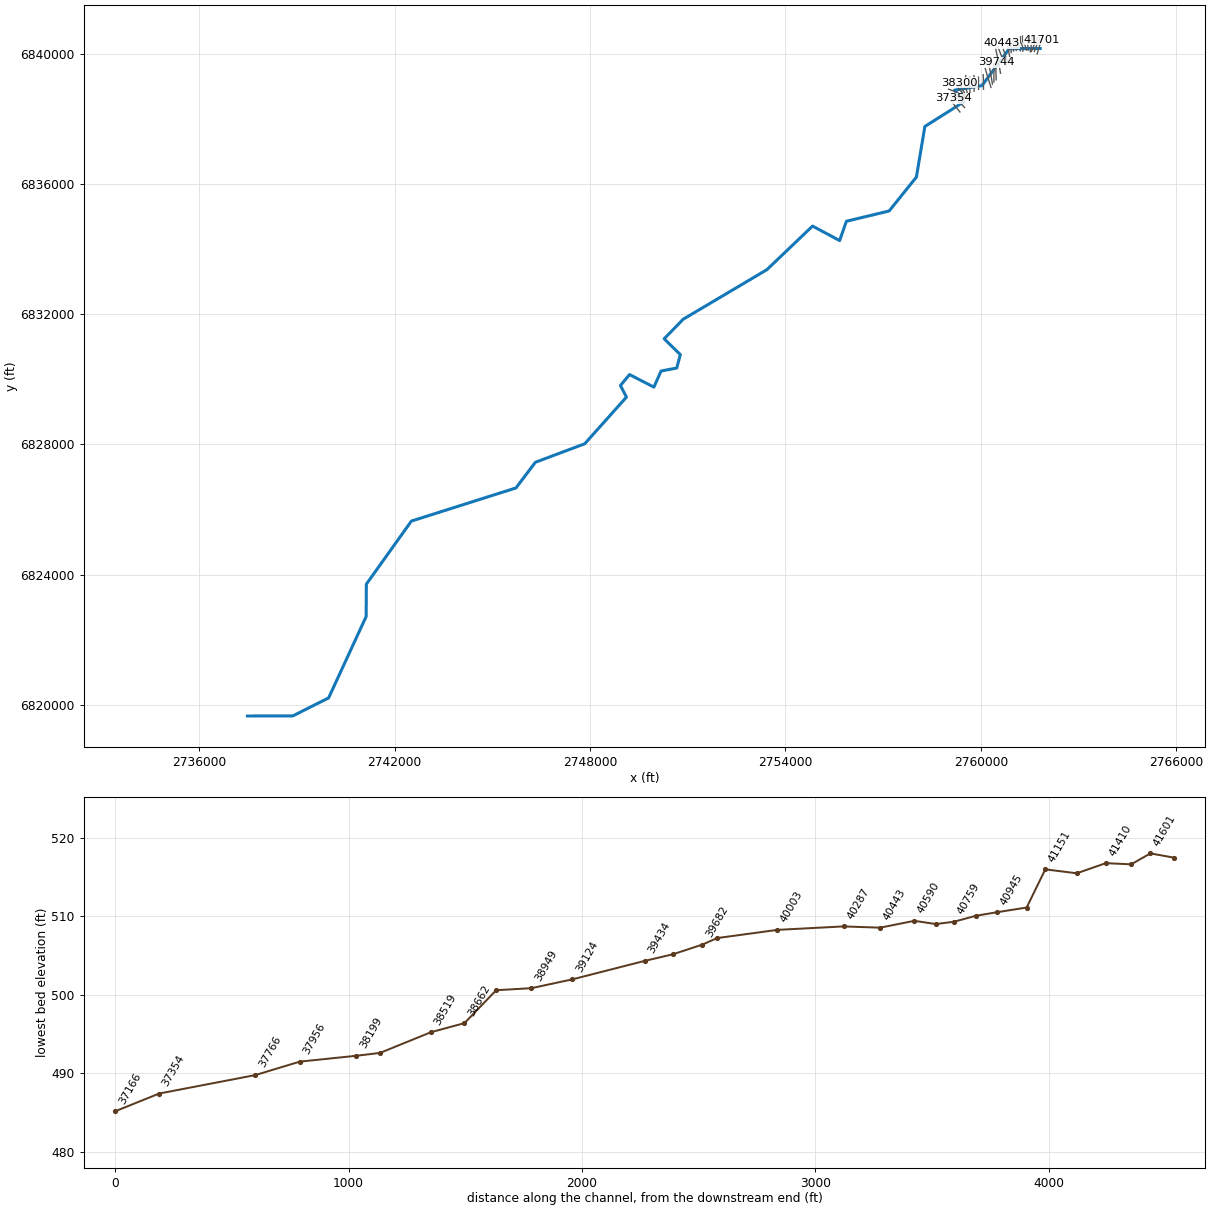
--- Purtis Creek.prj (project) ---

Proj Title=Purtis Creek Base Level Engineering
Current Plan=p01
Default Exp/Contr=0.3,0.1
English Units
Geom File=g01
Flow File=f01
Plan File=p01
BEGIN DESCRIPTION:
Purtis Creek
END DESCRIPTION:

--- Purtis Creek.p01 (plan) ---

Plan Title=Multiple Run
Short Identifier=Multiple
Geom File=g01
Flow File=f01
Subcritical Flow
K Sum by GR= 0
Std Step Tol= 0.01
Critical Tol= 0.01
Num of Std Step Trials= 20
Max Error Tol= 0.3
Flow Tol Ratio= 0.001
Split Flow NTrial= 30
Split Flow Tol= 0.02
Split Flow Ratio= 0.02
Log Output Level= 0
Friction Slope Method= 1
Unsteady Friction Slope Method= 2
Unsteady Bridges Friction Slope Method= 1
Parabolic Critical Depth
Global Vel Dist=  1 , 1 , 1
Global Log Level= 0
CheckData=True
Encroach Param= -1, 0, 0, 0
BEGIN DESCRIPTION:
Multiple Run
END DESCRIPTION:

--- Purtis Creek.f01 (steady flow) ---

Flow Title=Multiple
Number of Profiles=7
Profile Names=10-year,25-year,50-year,1pct_min,100-year,1pct_plu,500-year
River Rch & RM= Purtis Creek,Reach-1,41701
     541     726     876     526    1049    2094    1508
River Rch & RM= Purtis Creek,Reach-1,33117
     700     951    1159     701    1398    2790    2042
River Rch & RM= Purtis Creek,Reach-1,30004
    1016    1407    1735    1061    2117    4224    3162
River Rch & RM= Purtis Creek,Reach-1,27019
    1098    1523    1878    1148    2291    4572    3421
River Rch & RM= Purtis Creek,Reach-1,22931
    1645    2327    2910    1802    3595    7172    5505
River Rch & RM= Purtis Creek,Reach-1,21620
    1704    2415    3023    1874    3739    7461    5741
River Rch & RM= Purtis Creek,Reach-1,19896
    1922    2728    3417    2118    4227    8434    6489
River Rch & RM= Purtis Creek,Reach-1,14180
    1990    2826    3541    2196    4381    8742    6730
River Rch & RM= Purtis Creek,Reach-1,13353
    2140    3038    3807    2359    4707    9391    7219
River Rch & RM= Purtis Creek,Reach-1,9889
    2244    3186    3992    2474    4935    9847    7567
River Rch & RM= Purtis Creek,Reach-1,8352
    2287    3248    4071    2523    5034   10045    7723
River Rch & RM= Purtis Creek,Reach-1,7986
    2303    3272    4102    2542    5072   10121    7783
River Rch & RM= Purtis Creek,Reach-1,7640
    2288    3249    4070    2521    5029   10034    7706
River Rch & RM= Purtis Creek,Reach-1,6579
    2283    3239    4057    2512    5011    9999    7673
River Rch & RM= Purtis Creek,Reach-1,5962
    2266    3211    4017    2484    4956    9889    7571
River Rch & RM= Purtis Creek,Reach-1,4610
    3071    4391    5522    3424    6833   13633   10467
Boundary for River Rch & Prof#=Purtis Creek,Reach-1,1
Up Type=0
Dn Type=3
Dn Slope=0.005
Boundary for River Rch & Prof#=Purtis Creek,Reach-1,2
Up Type=0
Dn Type=3
Dn Slope=0.005
Boundary for River Rch & Prof#=Purtis Creek,Reach-1,3
Up Type=0
Dn Type=3
Dn Slope=0.005
Boundary for River Rch & Prof#=Purtis Creek,Reach-1,4
Up Type=0
Dn Type=3
Dn Slope=0.005
Boundary for River Rch & Prof#=Purtis Creek,Reach-1,5
Up Type=0
Dn Type=3
Dn Slope=0.005
Boundary for River Rch & Prof#=Purtis Creek,Reach-1,6
Up Type=0
Dn Type=3
Dn Slope=0.005
Boundary for River Rch & Prof#=Purtis Creek,Reach-1,7
Up Type=0
Dn Type=3
Dn Slope=0.005

--- Purtis Creek.g01 (geometry) ---

Geom Title=Existing Conditions

River Reach=Purtis Creek,Reach-1
Reach XY= 30
      2761826.00      6840161.00      2760877.58      6840157.17
      2760035.82      6839021.46      2759195.41      6838882.03
      2759473.26      6838519.24      2758283.69      6837767.47
      2758022.56      6836212.19      2757185.80      6835171.48
      2755872.99      6834855.54      2755665.54      6834261.81
      2754834.46      6834708.37      2753432.08      6833369.13
      2750862.35      6831847.81      2750276.36      6831245.84
      2750772.60      6830759.71      2750662.46      6830347.57
      2750180.89      6830255.88      2749960.84      6829761.38
      2749212.61      6830147.59      2748933.07      6829811.01
      2749118.20      6829454.79      2747836.17      6828021.32
      2746319.92      6827452.87      2745724.42      6826664.83
      2742512.79      6825647.38      2741129.29      6823709.64
      2741123.76      6822716.93      2739970.55      6820216.19
      2738870.14      6819663.07      2737476.00      6819661.00

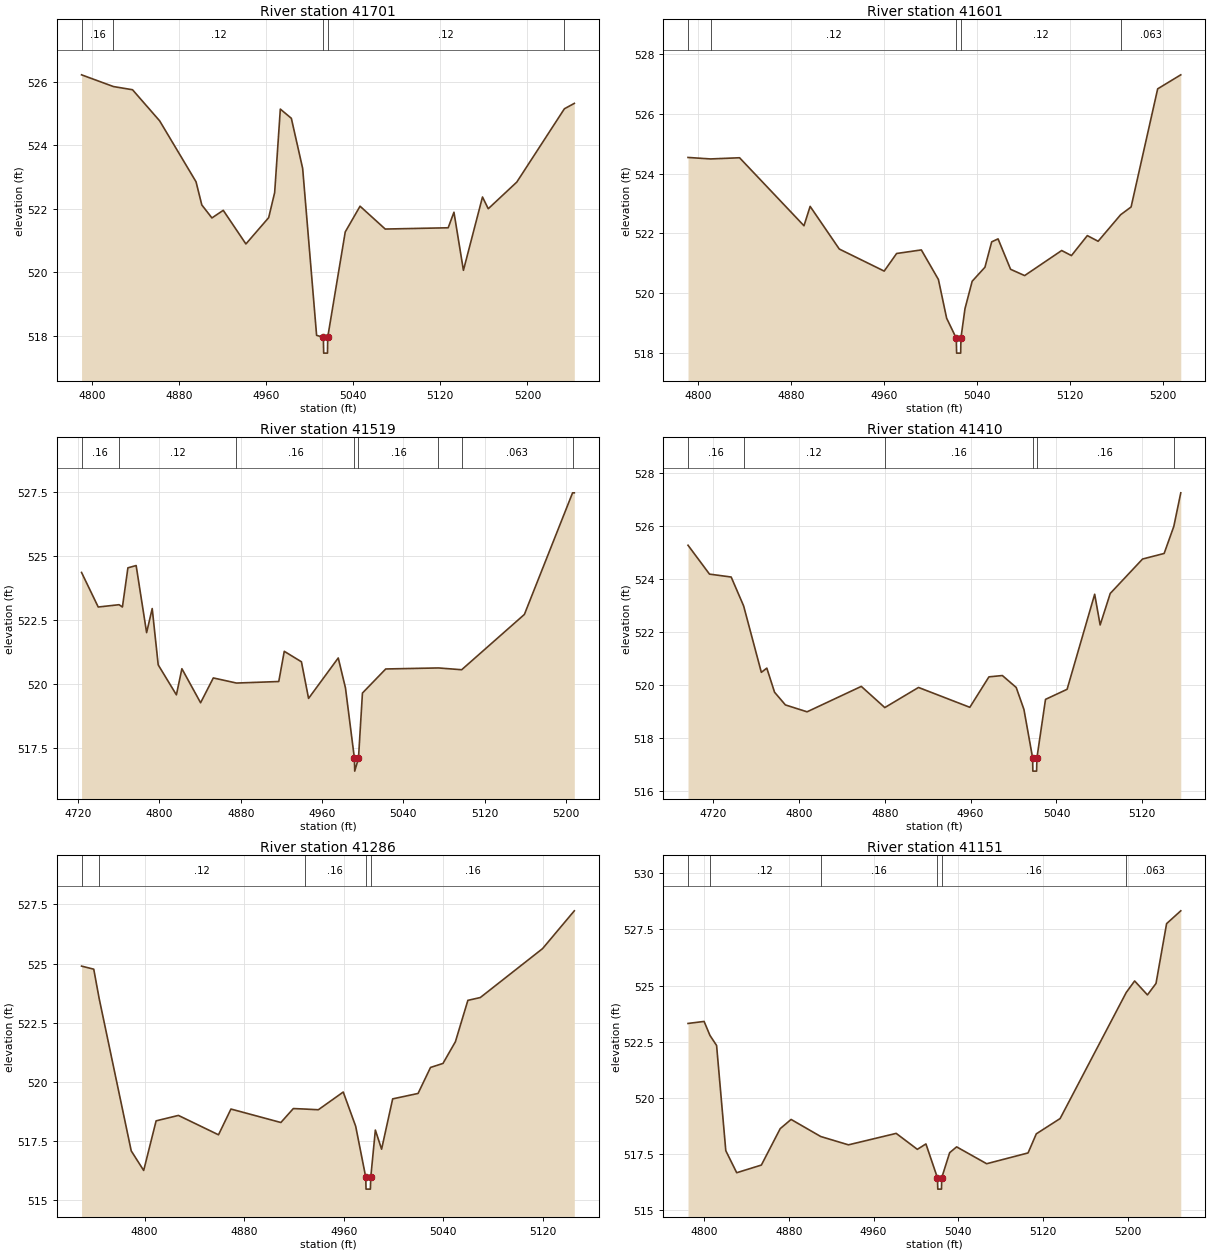
Type RM Length L Ch R = 1,41701,100,100,100
BEGIN DESCRIPTION:
Purtis Creek41701.428
END DESCRIPTION:
XS GIS Cut Line= 3
      2761731.24      6839996.10      2761789.90      6840197.12
      2761867.33      6840427.45
#Sta/Elev= 30
  4790.6  526.22  4819.9  525.85  4837.4  525.75  4862.3  524.77  4895.7  522.85
  4901.0  522.12  4910.3  521.71  4920.7  521.95  4941.5  520.89  4962.4  521.72
  4967.9  522.51  4973.1  525.14  4983.2  524.85  4993.6  523.27  5006.4  518.01
  5012.6  517.95  5012.9  517.45  5016.4  517.45  5016.6  517.95  5032.7  521.27
  5046.3  522.08  5069.4  521.36  5127.2  521.40  5132.5  521.89  5141.2  520.06
  5158.7  522.37  5164.0  522.00  5190.2  522.84  5233.9  525.15  5243.0  525.32
#Mann=5,-1,0
  4790.6    0.16       0  4819.9    0.12       0  5012.6    0.07       0
  5016.6    0.12       0  5233.9   0.063       0
Bank Sta=5012.6,5016.6
Exp/Cntr=0.3,0.1

Type RM Length L Ch R = 1,41601,82,82,82
BEGIN DESCRIPTION:
Purtis Creek41600.76
END DESCRIPTION:
XS GIS Cut Line= 3
      2761646.26      6840072.50      2761718.62      6840268.06
      2761809.34      6840464.07
#Sta/Elev= 30
  4791.2  524.54  4810.6  524.49  4835.6  524.53  4891.1  522.25  4896.4  522.90
  4921.5  521.47  4960.2  520.73  4970.9  521.32  4992.2  521.44  5006.9  520.45
  5014.0  519.15  5022.3  518.48  5022.6  517.98  5026.1  517.98  5026.3  518.48
  5029.8  519.47  5036.0  520.39  5047.0  520.86  5052.8  521.71  5058.3  521.81
  5069.1  520.79  5081.2  520.58  5113.1  521.42  5121.5  521.25  5135.2  521.92
  5144.5  521.73  5163.9  522.62  5172.9  522.88  5195.8  526.84  5215.7  527.31
#Mann=5,-1,0
  4791.2    0.16       0  4810.6    0.12       0  5022.3    0.07       0
  5026.3    0.12       0  5163.9   0.063       0
Bank Sta=5022.3,5026.3
Exp/Cntr=0.3,0.1

Type RM Length L Ch R = 1,41519,109,109,109
BEGIN DESCRIPTION:
Purtis Creek41518.59
END DESCRIPTION:
XS GIS Cut Line= 3
      2761554.49      6840071.40      2761661.16      6840327.27
      2761748.36      6840515.54
#Sta/Elev= 30
  4723.4  524.35  4739.8  523.00  4760.3  523.09  4763.6  523.00  4769.0  524.53
  4777.1  524.62  4787.4  522.00  4792.9  522.94  4798.8  520.74  4816.7  519.57
  4822.1  520.59  4840.5  519.26  4853.0  520.23  4875.8  520.03  4917.4  520.09
  4922.8  521.27  4939.7  520.86  4946.7  519.43  4975.9  521.01  4983.0  519.84
  4991.8  517.09  4992.1  516.59  4995.8  517.09  4999.7  519.64  5022.6  520.58
  5074.5  520.62  5097.3  520.55  5159.0  522.71  5206.4  527.46  5208.1  527.46
#Mann=8,-1,0
  4723.4    0.16       0  4760.3    0.12       0  4875.8    0.16       0
  4991.8    0.07       0  4995.8    0.16       0  5074.5    0.12       0
  5097.3   0.063       0  5206.4    0.05       0
Bank Sta=4991.8,4995.8
Exp/Cntr=0.3,0.1

Type RM Length L Ch R = 1,41410,124,124,124
BEGIN DESCRIPTION:
Purtis Creek41409.57
END DESCRIPTION:
XS GIS Cut Line= 3
      2761520.92      6840061.18      2761563.90      6840361.69
      2761578.44      6840516.44
#Sta/Elev= 30
  4696.8  525.27  4716.8  524.18  4737.0  524.07  4748.6  522.98  4765.1  520.47
  4770.2  520.63  4777.4  519.72  4787.5  519.24  4807.7  518.98  4858.2  519.94
  4880.1  519.14  4911.5  519.90  4959.3  519.15  4977.1  520.30  4989.6  520.35
  5002.5  519.90  5009.7  519.07  5017.8  517.24  5018.0  516.74  5021.5  516.74
  5021.8  517.24  5029.8  519.45  5049.9  519.83  5075.6  523.42  5080.7  522.26
  5090.1  523.45  5120.2  524.75  5140.3  524.96  5149.3  525.98  5155.8  527.25
#Mann=6,-1,0
  4696.8    0.16       0  4748.6    0.12       0  4880.1    0.16       0
  5017.8    0.07       0  5021.8    0.16       0  5149.3   0.063       0
Bank Sta=5017.8,5021.8
Exp/Cntr=0.3,0.1

Type RM Length L Ch R = 1,41286,135,135,135
BEGIN DESCRIPTION:
Purtis Creek41285.83
END DESCRIPTION:
XS GIS Cut Line= 3
      2761456.17      6840111.22      2761439.86      6840365.15
      2761439.15      6840506.49
#Sta/Elev= 30
  4749.4  524.89  4759.2  524.76  4763.5  523.53  4789.3  517.07  4799.3  516.24
  4809.3  518.34  4827.2  518.57  4859.4  517.75  4869.4  518.84  4909.5  518.27
  4919.5  518.86  4928.5  518.84  4939.6  518.81  4959.6  519.56  4969.6  518.11
  4977.7  515.95  4977.9  515.45  4981.4  515.45  4981.7  515.95  4985.4  517.95
  4990.4  517.14  4999.3  519.27  5019.7  519.50  5029.7  520.60  5039.7  520.77
  5049.7  521.69  5059.7  523.44  5069.7  523.56  5119.7  525.63  5145.2  527.23
#Mann=5,-1,0
  4749.4    0.16       0  4763.5    0.12       0  4928.5    0.16       0
  4977.7    0.07       0  4981.7    0.16       0
Bank Sta=4977.7,4981.7
Exp/Cntr=0.3,0.1

Type RM Length L Ch R = 1,41151,80,80,80
BEGIN DESCRIPTION:
Purtis Creek41150.64
END DESCRIPTION:
XS GIS Cut Line= 6
      2761396.36      6840116.23      2761363.59      6840255.05
      2761318.00      6840316.71      2761292.06      6840363.70
      2761280.49      6840424.03      2761294.75      6840554.30
#Sta/Elev= 30
  4784.7  523.32  4799.9  523.41  4805.4  522.79  4811.7  522.34  4820.4  517.66
  4830.7  516.68  4854.0  517.02  4871.8  518.64  4882.1  519.05  4910.1  518.29
  4936.3  517.92  4981.4  518.43  5001.4  517.72  5009.5  517.96  5020.4  516.45
  5020.7  515.95  5024.2  515.95  5024.4  516.45  5031.9  517.57  5038.5  517.83
  5066.9  517.08  5106.0  517.56  5113.8  518.41  5136.3  519.09  5198.8  524.70
  5206.7  525.21  5218.8  524.59  5226.9  525.10  5236.9  527.76  5250.3  528.33
#Mann=6,-1,0
  4784.7    0.16       0  4805.4    0.12       0  4910.1    0.16       0
  5020.4    0.07       0  5024.4    0.16       0  5198.8   0.063       0
Bank Sta=5020.4,5024.4
Exp/Cntr=0.3,0.1

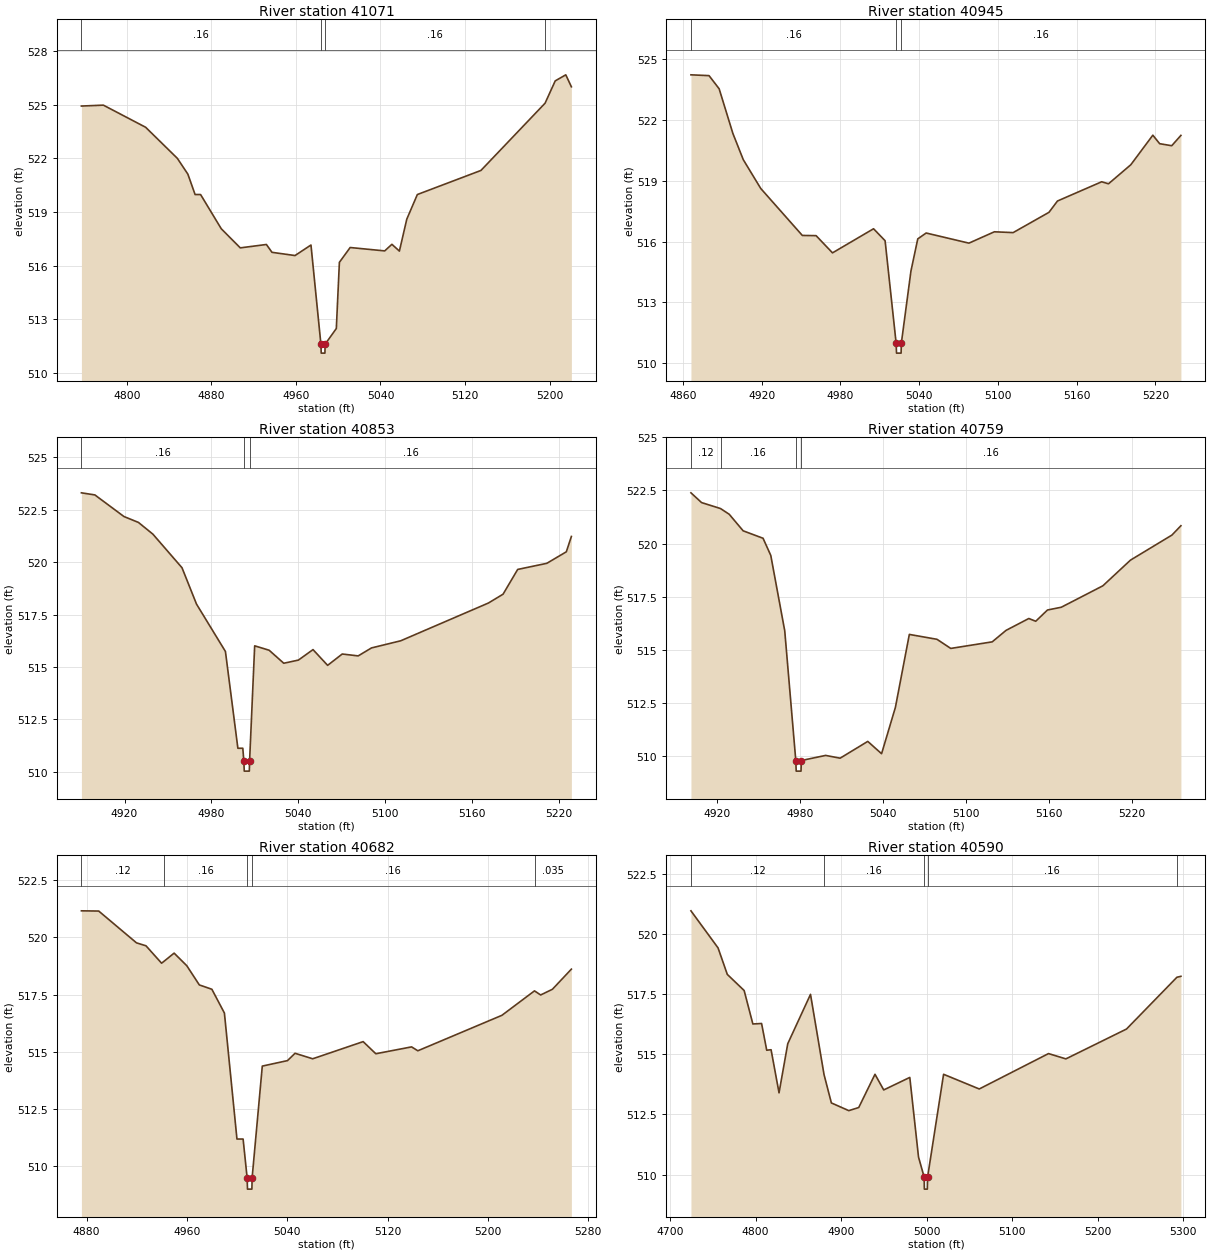
Type RM Length L Ch R = 1,41071,126,126,126
BEGIN DESCRIPTION:
Purtis Creek41070.94
END DESCRIPTION:
XS GIS Cut Line= 6
      2761293.49      6840080.19      2761296.32      6840189.54
      2761268.85      6840261.39      2761219.57      6840361.93
      2761215.20      6840427.85      2761223.78      6840526.28
#Sta/Elev= 30
  4756.9  524.94  4777.7  524.99  4817.7  523.75  4847.7  522.01  4857.7  521.12
  4864.5  519.98  4869.7  519.98  4889.3  518.06  4907.3  516.99  4932.0  517.18
  4937.3  516.74  4959.1  516.56  4974.2  517.15  4983.6  511.59  4983.9  511.09
  4987.4  511.09  4987.6  511.59  4998.2  512.47  5001.1  516.18  5011.3  517.01
  5044.0  516.82  5050.8  517.19  5057.9  516.81  5064.9  518.60  5074.9  519.98
  5135.1  521.33  5195.8  525.10  5205.4  526.35  5215.4  526.69  5220.7  526.02
#Mann=4,-1,0
  4756.9    0.16       0  4983.6    0.07       0  4987.6    0.16       0
  5195.8   0.063       0
Bank Sta=4983.6,4987.6
Exp/Cntr=0.3,0.1

Type RM Length L Ch R = 1,40945,92,92,92
BEGIN DESCRIPTION:
Purtis Creek40945.14
END DESCRIPTION:
XS GIS Cut Line= 3
      2761214.69      6840090.67      2761171.17      6840218.41
      2761105.42      6840447.72
#Sta/Elev= 30
  4866.0  524.24  4879.8  524.20  4887.5  523.55  4898.0  521.34  4905.9  520.05
  4919.2  518.63  4950.9  516.31  4961.4  516.30  4973.9  515.45  5005.2  516.64
  5014.0  516.05  5022.4  511.00  5022.7  510.50  5026.2  510.50  5026.4  511.00
  5033.7  514.55  5038.9  516.14  5045.3  516.43  5077.9  515.93  5097.3  516.49
  5111.6  516.45  5138.9  517.45  5145.4  518.01  5179.1  518.96  5184.3  518.86
  5201.3  519.80  5218.1  521.26  5223.3  520.84  5232.5  520.74  5239.5  521.25
#Mann=3,-1,0
  4866.0    0.16       0  5022.4    0.07       0  5026.4    0.16       0
Bank Sta=5022.4,5026.4
Exp/Cntr=0.3,0.1

Type RM Length L Ch R = 1,40853,94,94,94
BEGIN DESCRIPTION:
Purtis Creek40853.28
END DESCRIPTION:
XS GIS Cut Line= 3
      2761089.54      6840101.73      2761081.31      6840212.97
      2761050.30      6840437.79
#Sta/Elev= 30
  4890.2  523.30  4899.5  523.20  4919.6  522.17  4929.6  521.89  4939.6  521.33
  4959.7  519.73  4969.7  518.00  4989.7  515.74  4998.3  511.13  5001.7  511.13
  5002.4  510.54  5002.7  510.04  5006.2  510.04  5006.4  510.54  5009.9  516.01
  5019.9  515.80  5030.0  515.18  5040.1  515.33  5050.2  515.83  5060.3  515.08
  5070.4  515.62  5081.4  515.53  5090.6  515.91  5110.8  516.25  5171.4  518.05
  5181.5  518.47  5191.6  519.65  5211.7  519.94  5225.2  520.49  5228.7  521.22
#Mann=3,-1,0
  4890.2    0.16       0  5002.4    0.07       0  5006.4    0.16       0
Bank Sta=5002.4,5006.4
Exp/Cntr=0.3,0.1

Type RM Length L Ch R = 1,40759,77,77,77
BEGIN DESCRIPTION:
Purtis Creek40759.02
END DESCRIPTION:
XS GIS Cut Line= 3
      2761005.52      6840083.38      2760996.60      6840184.92
      2760986.78      6840437.50
#Sta/Elev= 30
  4901.0  522.39  4908.7  521.93  4922.4  521.65  4928.7  521.38  4938.8  520.60
  4953.2  520.25  4958.8  519.44  4968.9  515.89  4976.9  509.78  4977.2  509.28
  4980.7  509.28  4980.9  509.78  4998.5  510.02  5009.0  509.89  5029.0  510.68
  5039.0  510.10  5049.0  512.28  5059.1  515.72  5079.1  515.49  5089.1  515.06
  5119.1  515.37  5129.1  515.91  5145.6  516.47  5150.6  516.34  5159.1  516.87
  5169.1  517.00  5199.2  518.01  5219.2  519.22  5249.2  520.40  5255.7  520.84
#Mann=4,-1,0
  4901.0    0.12       0  4922.4    0.16       0  4976.9    0.07       0
  4980.9    0.16       0
Bank Sta=4976.9,4980.9
Exp/Cntr=0.3,0.1

Type RM Length L Ch R = 1,40682,92,92,92
BEGIN DESCRIPTION:
Purtis Creek40681.59
END DESCRIPTION:
XS GIS Cut Line= 3
      2760935.02      6840037.27      2760925.45      6840165.86
      2760897.97      6840426.06
#Sta/Elev= 30
  4875.9  521.16  4889.7  521.15  4919.8  519.76  4927.4  519.63  4939.8  518.87
  4941.7  518.95  4949.8  519.31  4959.9  518.76  4969.9  517.92  4979.9  517.73
  4989.9  516.69  4999.9  511.18  5004.8  511.18  5008.0  509.49  5008.3  508.99
  5011.8  508.99  5012.0  509.49  5020.1  514.37  5040.2  514.61  5046.2  514.93
  5060.3  514.69  5100.5  515.44  5110.6  514.91  5139.1  515.21  5144.1  515.04
  5211.1  516.59  5237.1  517.66  5242.0  517.48  5251.4  517.73  5266.5  518.61
#Mann=5,-1,0
  4875.9    0.12       0  4941.7    0.16       0  5008.0    0.07       0
  5012.0    0.16       0  5237.1   0.035       0
Bank Sta=5008,5012
Exp/Cntr=0.3,0.1

Type RM Length L Ch R = 1,40590,147,147,147
BEGIN DESCRIPTION:
Purtis Creek40590.35
END DESCRIPTION:
XS GIS Cut Line= 3
      2760898.41      6839859.94      2760844.35      6840132.70
      2760797.57      6840423.80
#Sta/Elev= 30
  4724.4  520.96  4756.1  519.42  4766.9  518.32  4786.6  517.65  4796.8  516.26
  4807.0  516.28  4813.0  515.17  4818.1  515.19  4827.4  513.40  4837.6  515.44
  4864.2  517.49  4880.0  514.16  4888.6  512.98  4909.0  512.66  4920.6  512.79
  4939.6  514.17  4949.8  513.52  4980.3  514.04  4990.5  510.73  4997.1  509.90
  4997.3  509.40  5000.8  509.40  5001.1  509.90  5019.8  514.17  5061.5  513.56
  5142.5  515.03  5162.8  514.81  5233.7  516.05  5292.6  518.20  5297.3  518.24
#Mann=5,-1,0
  4724.4    0.12       0  4880.0    0.16       0  4997.1    0.07       0
  5001.1    0.16       0  5292.6   0.035       0
Bank Sta=4997.1,5001.1
Exp/Cntr=0.3,0.1

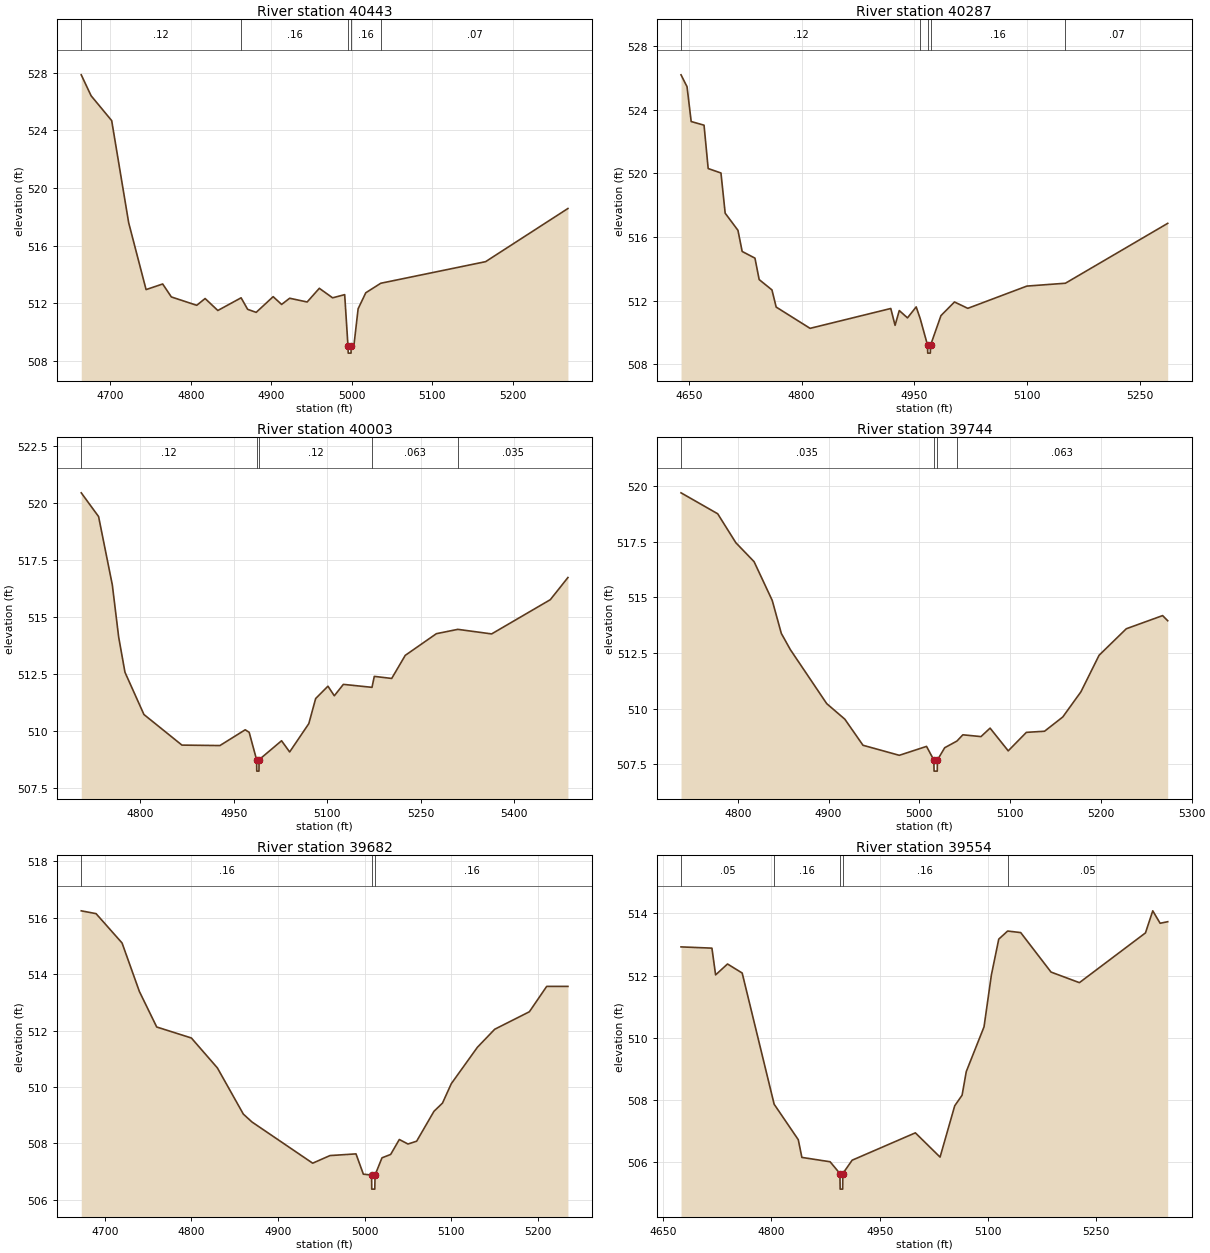
Type RM Length L Ch R = 1,40443,156,156,156
BEGIN DESCRIPTION:
Purtis Creek40442.63
END DESCRIPTION:
XS GIS Cut Line= 3
      2760825.17      6839745.21      2760717.07      6840065.95
      2760632.16      6840317.86
#Sta/Elev= 30
  4664.1  527.85  4676.3  526.40  4701.9  524.67  4723.0  517.58  4744.6  512.94
  4765.2  513.33  4776.0  512.43  4807.5  511.85  4817.9  512.32  4833.7  511.49
  4862.6  512.37  4870.7  511.57  4881.3  511.36  4902.4  512.45  4912.9  511.91
  4922.9  512.34  4944.6  512.08  4959.7  513.03  4976.2  512.37  4991.2  512.59
  4995.3  509.03  4995.6  508.53  4999.1  508.53  4999.3  509.03  5002.6  509.03
  5007.9  511.61  5017.4  512.72  5036.0  513.38  5166.2  514.88  5268.4  518.57
#Mann=5,-1,0
  4664.1    0.12       0  4862.6    0.16       0  4995.3    0.07       0
  4999.3    0.16       0  5036.0    0.07       0
Bank Sta=4995.3,4999.3
Exp/Cntr=0.3,0.1

Type RM Length L Ch R = 1,40287,284,284,284
BEGIN DESCRIPTION:
Purtis Creek40287.12
END DESCRIPTION:
XS GIS Cut Line= 3
      2760785.00      6839629.93      2760626.03      6839958.51
      2760522.65      6840220.97
#Sta/Elev= 30
  4639.8  526.21  4647.8  525.46  4653.3  523.27  4670.4  523.04  4675.9  520.31
  4692.9  520.03  4698.5  517.50  4715.5  516.42  4721.1  515.09  4738.1  514.67
  4743.7  513.32  4760.7  512.67  4766.3  511.59  4811.4  510.25  4918.7  511.50
  4924.4  510.44  4930.0  511.37  4940.9  510.91  4952.5  511.60  4957.7  510.88
  4967.6  509.19  4967.8  508.69  4971.3  508.69  4971.6  509.19  4985.4  511.05
  5003.4  511.91  5021.1  511.51  5099.6  512.91  5150.9  513.09  5286.9  516.86
#Mann=5,-1,0
  4639.8    0.12       0  4957.7    0.16       0  4967.6    0.07       0
  4971.6    0.16       0  5150.9    0.07       0
Bank Sta=4967.6,4971.6
Exp/Cntr=0.3,0.1

Type RM Length L Ch R = 1,40003,259,259,259
BEGIN DESCRIPTION:
Purtis Creek40003.32
END DESCRIPTION:
XS GIS Cut Line= 3
      2760606.21      6839401.87      2760556.86      6839692.87
      2760455.91      6840167.29
#Sta/Elev= 30
  4705.6  520.44  4733.4  519.40  4755.4  516.41  4765.6  514.12  4775.7  512.58
  4806.1  510.73  4867.0  509.39  4927.9  509.37  4968.4  510.06  4974.8  509.95
  4986.7  508.75  4987.0  508.25  4990.5  508.25  4990.7  508.75  5026.7  509.58
  5039.7  509.09  5070.4  510.33  5081.4  511.43  5101.1  511.97  5111.3  511.55
  5125.8  512.05  5171.7  511.92  5175.4  512.40  5203.3  512.31  5225.0  513.32
  5274.9  514.27  5309.3  514.46  5363.5  514.26  5457.6  515.76  5485.8  516.73
#Mann=5,-1,0
  4705.6    0.12       0  4986.7    0.07       0  4990.7    0.12       0
  5171.7   0.063       0  5309.3   0.035       0
Bank Sta=4986.7,4990.7
Exp/Cntr=0.3,0.1

Type RM Length L Ch R = 1,39744,62,62,62
BEGIN DESCRIPTION:
Purtis Creek39744.02
END DESCRIPTION:
XS GIS Cut Line= 3
      2760473.76      6839200.59      2760465.48      6839464.49
      2760467.99      6839736.64
#Sta/Elev= 30
  4737.4  519.69  4777.8  518.75  4797.8  517.45  4817.9  516.60  4837.9  514.86
  4847.9  513.38  4857.9  512.65  4897.9  510.23  4917.9  509.53  4937.9  508.36
  4977.9  507.91  5007.9  508.31  5015.9  507.70  5016.2  507.20  5019.7  507.20
  5019.9  507.70  5027.9  508.25  5041.4  508.55  5047.9  508.83  5067.9  508.75
  5077.9  509.13  5097.9  508.11  5117.9  508.94  5137.9  508.99  5158.0  509.63
  5178.0  510.76  5198.0  512.40  5228.0  513.59  5268.0  514.18  5273.6  513.95
#Mann=4,-1,0
  4737.4   0.035       0  5015.9   0.035       0  5019.9   0.035       0
  5041.4   0.063       0
Bank Sta=5015.9,5019.9
Exp/Cntr=0.3,0.1

Type RM Length L Ch R = 1,39682,128,128,128
BEGIN DESCRIPTION:
Purtis Creek39682.24
END DESCRIPTION:
XS GIS Cut Line= 3
      2760403.77      6839133.91      2760403.99      6839462.98
      2760396.48      6839695.49
#Sta/Elev= 30
  4672.9  516.25  4690.0  516.15  4720.0  515.11  4740.0  513.39  4760.0  512.13
  4800.0  511.74  4830.0  510.68  4860.0  509.04  4870.0  508.76  4940.0  507.30
  4960.0  507.57  4990.0  507.63  4998.5  506.91  5008.0  506.88  5008.2  506.38
  5011.7  506.38  5012.0  506.88  5020.0  507.49  5030.0  507.61  5040.0  508.14
  5050.0  507.98  5060.0  508.08  5080.0  509.14  5089.8  509.43  5100.0  510.12
  5130.1  511.41  5150.1  512.05  5190.1  512.67  5210.1  513.57  5234.6  513.57
#Mann=3,-1,0
  4672.9    0.16       0  5008.0    0.07       0  5012.0    0.16       0
Bank Sta=5008,5012
Exp/Cntr=0.3,0.1

Type RM Length L Ch R = 1,39554,120,120,120
BEGIN DESCRIPTION:
Purtis Creek39553.58
END DESCRIPTION:
XS GIS Cut Line= 3
      2760358.95      6839067.51      2760303.36      6839388.68
      2760241.73      6839731.34
#Sta/Elev= 30
  4674.7  512.92  4717.5  512.88  4722.6  512.02  4739.1  512.37  4759.4  512.08
  4803.7  507.86  4837.1  506.72  4842.1  506.15  4881.2  506.01  4894.8  505.63
  4895.1  505.13  4898.6  505.13  4898.8  505.63  4911.7  506.06  4999.3  506.94
  5033.5  506.16  5053.8  507.81  5064.0  508.15  5069.8  508.91  5094.4  510.35
  5104.6  512.02  5114.8  513.17  5127.1  513.43  5145.2  513.38  5187.2  512.11
  5226.5  511.77  5318.0  513.37  5328.1  514.08  5338.3  513.68  5348.8  513.73
#Mann=5,-1,0
  4674.7    0.05       0  4803.7    0.16       0  4894.8    0.07       0
  4898.8    0.16       0  5127.1    0.05       0
Bank Sta=4894.8,4898.8
Exp/Cntr=0.3,0.1

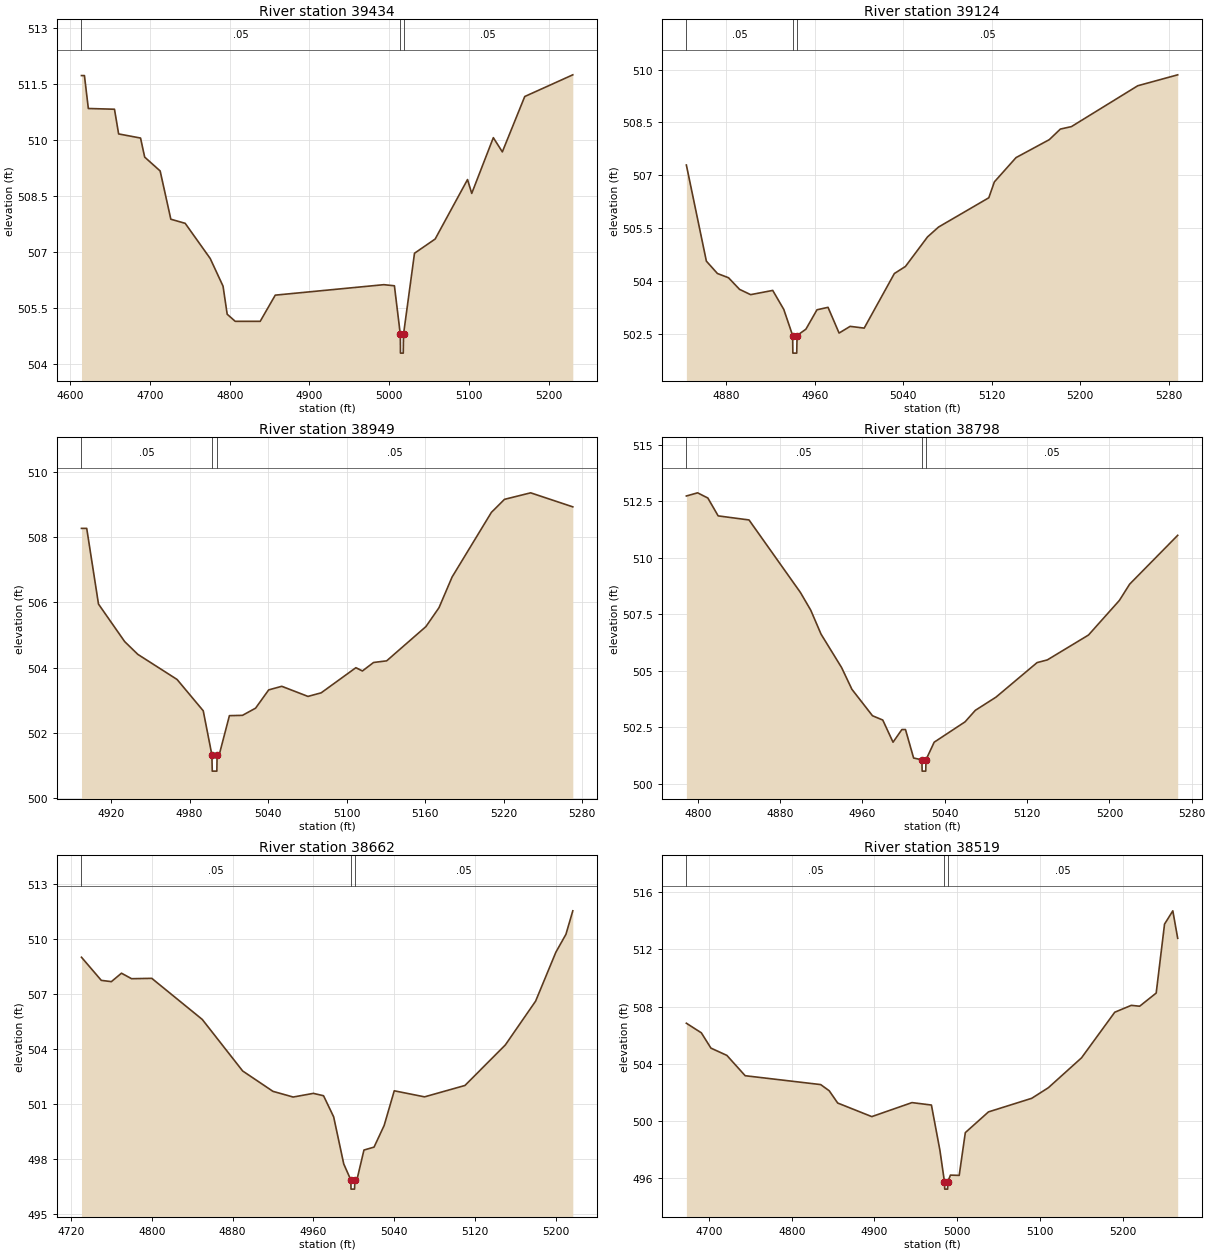
Type RM Length L Ch R = 1,39434,310,310,310
BEGIN DESCRIPTION:
Purtis Creek39433.6
END DESCRIPTION:
XS GIS Cut Line= 3
      2760313.16      6838966.60      2760199.40      6839337.91
      2760134.71      6839556.59
#Sta/Elev= 30
  4614.0  511.72  4617.7  511.72  4622.6  510.84  4655.4  510.82  4660.6  510.16
  4688.1  510.05  4693.3  509.54  4712.7  509.17  4726.1  507.88  4744.1  507.77
  4775.5  506.83  4791.6  506.09  4796.8  505.34  4806.9  505.15  4838.2  505.15
  4857.1  505.85  4993.4  506.13  5006.6  506.10  5014.0  504.80  5014.2  504.30
  5017.7  504.30  5018.0  504.80  5031.8  506.97  5057.7  507.35  5098.3  508.94
  5103.6  508.57  5130.7  510.06  5142.0  509.68  5170.1  511.16  5230.4  511.74
#Mann=3,-1,0
  4614.0    0.05       0  5014.0    0.05       0  5018.0    0.05       0
Bank Sta=5014,5018
Exp/Cntr=0.3,0.1

Type RM Length L Ch R = 1,39124,175,175,175
BEGIN DESCRIPTION:
Purtis Creek39123.59
END DESCRIPTION:
XS GIS Cut Line= 3
      2760083.06      6838912.94      2760084.70      6839071.44
      2760075.53      6839357.09
#Sta/Elev= 30
  4844.0  507.29  4862.1  504.56  4872.1  504.21  4882.1  504.09  4892.1  503.76
  4902.1  503.61  4922.1  503.73  4932.1  503.19  4940.1  502.45  4940.3  501.95
  4943.8  501.95  4944.1  502.45  4952.1  502.63  4962.1  503.18  4972.1  503.25
  4982.1  502.52  4992.1  502.71  5004.8  502.66  5032.1  504.21  5042.1  504.41
  5062.1  505.25  5072.1  505.53  5117.5  506.36  5122.5  506.81  5142.1  507.50
  5172.2  508.01  5182.2  508.31  5192.2  508.38  5252.2  509.54  5288.3  509.85
#Mann=3,-1,0
  4844.0    0.05       0  4940.1    0.05       0  4944.1    0.05       0
Bank Sta=4940.1,4944.1
Exp/Cntr=0.3,0.1

Type RM Length L Ch R = 1,38949,151,151,151
BEGIN DESCRIPTION:
Purtis Creek38949.06
END DESCRIPTION:
XS GIS Cut Line= 3
      2759932.22      6838907.95      2759931.86      6839013.16
      2759929.67      6839283.24
#Sta/Elev= 30
  4897.4  508.27  4901.4  508.27  4910.4  505.95  4930.4  504.80  4940.4  504.41
  4970.4  503.64  4990.4  502.68  4997.0  501.33  4997.3  500.83  5000.8  500.83
  5001.0  501.33  5002.6  501.33  5010.4  502.53  5020.4  502.54  5030.4  502.76
  5040.4  503.32  5050.4  503.43  5070.4  503.12  5080.5  503.23  5107.0  504.00
  5112.0  503.90  5120.5  504.16  5130.5  504.21  5160.5  505.26  5170.5  505.84
  5180.5  506.78  5210.5  508.76  5220.5  509.16  5240.5  509.36  5272.7  508.93
#Mann=3,-1,0
  4897.4    0.05       0  4997.0    0.05       0  5001.0    0.05       0
Bank Sta=4997,5001
Exp/Cntr=0.3,0.1

Type RM Length L Ch R = 1,38798,136,136,136
BEGIN DESCRIPTION:
Purtis Creek38798.35
END DESCRIPTION:
XS GIS Cut Line= 3
      2759795.90      6838850.10      2759797.31      6839063.13
      2759794.13      6839327.67
#Sta/Elev= 30
  4788.8  512.74  4799.7  512.88  4809.7  512.65  4819.7  511.86  4849.7  511.68
  4899.7  508.47  4909.7  507.69  4919.7  506.63  4939.7  505.15  4949.7  504.19
  4969.7  503.02  4979.7  502.83  4989.7  501.85  4998.3  502.41  5001.8  502.41
  5009.7  501.15  5017.7  501.07  5018.0  500.57  5021.5  500.57  5021.7  501.07
  5029.7  501.85  5059.7  502.75  5069.7  503.26  5089.7  503.84  5129.7  505.37
  5139.7  505.49  5179.7  506.59  5209.7  508.12  5219.7  508.84  5266.4  511.00
#Mann=3,-1,0
  4788.8    0.05       0  5017.7    0.05       0  5021.7    0.05       0
Bank Sta=5017.7,5021.7
Exp/Cntr=0.3,0.1

Type RM Length L Ch R = 1,38662,143,143,143
BEGIN DESCRIPTION:
Purtis Creek38662.49
END DESCRIPTION:
XS GIS Cut Line= 3
      2759668.03      6838791.42      2759661.37      6839064.03
      2759660.52      6839277.84
#Sta/Elev= 30
  4730.3  509.02  4749.9  507.76  4759.9  507.69  4769.9  508.15  4779.9  507.85
  4799.9  507.87  4849.9  505.63  4889.9  502.82  4919.9  501.71  4939.9  501.40
  4959.9  501.60  4970.0  501.47  4980.0  500.32  4990.0  497.75  4997.0  496.88
  4997.2  496.38  5000.7  496.38  5001.0  496.88  5003.0  496.88  5010.0  498.51
  5020.0  498.67  5030.0  499.85  5040.0  501.74  5070.0  501.41  5110.0  502.03
  5150.0  504.24  5180.0  506.63  5200.0  509.29  5210.0  510.27  5216.8  511.55
#Mann=3,-1,0
  4730.3    0.05       0  4997.0    0.05       0  5001.0    0.05       0
Bank Sta=4997,5001
Exp/Cntr=0.3,0.1

Type RM Length L Ch R = 1,38519,219,219,219
BEGIN DESCRIPTION:
Purtis Creek38519.43
END DESCRIPTION:
XS GIS Cut Line= 3
      2759597.22      6838743.40      2759517.79      6839063.56
      2759539.91      6839326.87
#Sta/Elev= 30
  4672.6  506.83  4690.7  506.16  4702.3  505.09  4721.6  504.58  4743.7  503.16
  4835.0  502.54  4845.3  502.11  4855.6  501.25  4896.8  500.30  4945.4  501.28
  4968.9  501.11  4979.2  497.94  4984.7  495.73  4985.0  495.23  4988.5  495.23
  4988.7  495.73  4991.9  496.21  5002.5  496.19  5009.9  499.18  5037.9  500.63
  5090.2  501.58  5110.3  502.32  5150.4  504.41  5190.6  507.60  5210.6  508.08
  5220.7  508.02  5240.7  508.94  5250.8  513.76  5260.8  514.69  5266.7  512.77
#Mann=3,-1,0
  4672.6    0.05       0  4984.7    0.05       0  4988.7    0.05       0
Bank Sta=4984.7,4988.7
Exp/Cntr=0.3,0.1

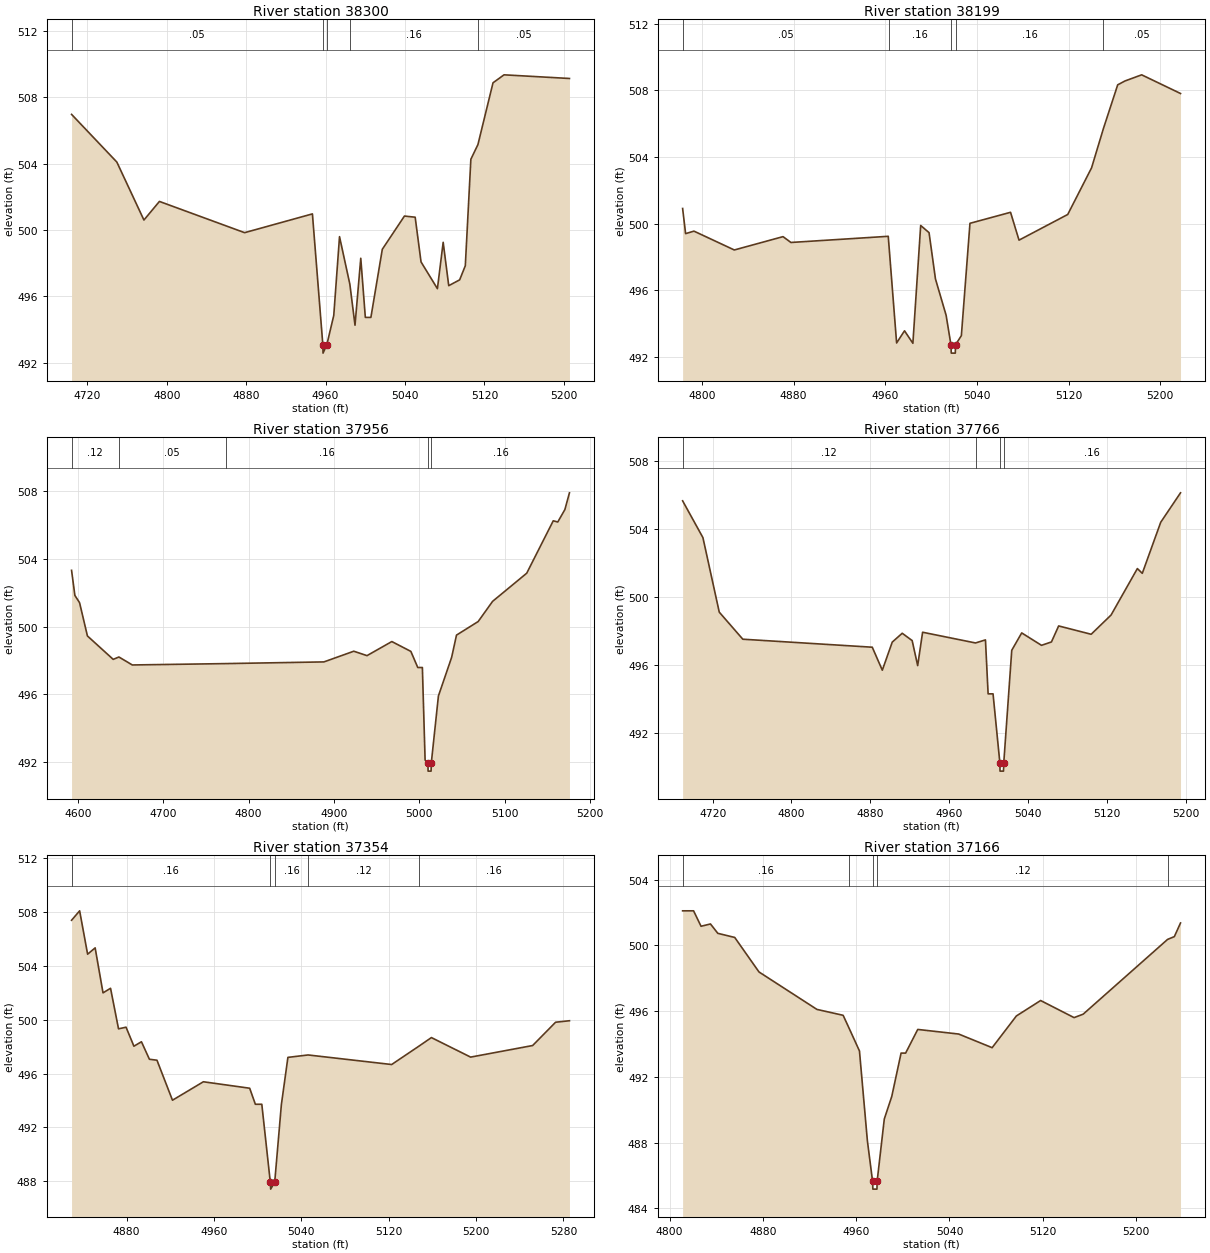
Type RM Length L Ch R = 1,38300,101,101,101
BEGIN DESCRIPTION:
Purtis Creek38299.97
END DESCRIPTION:
XS GIS Cut Line= 3
      2759576.96      6838671.42      2759426.37      6838926.24
      2759333.76      6839109.69
#Sta/Elev= 30
  4704.1  506.96  4749.7  504.09  4777.0  500.60  4792.6  501.72  4878.4  499.84
  4946.7  500.97  4957.2  493.09  4957.4  492.59  4961.2  493.09  4968.2  494.86
  4974.0  499.60  4984.4  496.74  4989.6  494.27  4995.4  498.30  5000.0  494.74
  5005.6  494.74  5017.1  498.84  5039.4  500.84  5050.2  500.77  5056.1  498.08
  5072.6  496.47  5078.4  499.26  5084.0  496.65  5095.0  497.00  5100.7  497.85
  5106.3  504.26  5113.4  505.14  5128.6  508.86  5139.7  509.34  5205.6  509.12
#Mann=5,-1,0
  4704.1    0.05       0  4957.2    0.07       0  4961.2    0.05       0
  4984.4    0.16       0  5113.4    0.05       0
Bank Sta=4957.2,4961.2
Exp/Cntr=0.3,0.1

Type RM Length L Ch R = 1,38199,243,243,243
BEGIN DESCRIPTION:
Purtis Creek38199.18
END DESCRIPTION:
XS GIS Cut Line= 3
      2759531.69      6838702.89      2759378.98      6838864.15
      2759250.67      6839033.30
#Sta/Elev= 30
  4783.2  500.91  4785.8  499.40  4793.1  499.55  4828.3  498.42  4870.8  499.22
  4877.7  498.87  4962.6  499.24  4963.3  498.63  4969.9  492.84  4976.8  493.57
  4984.1  492.82  4990.9  499.89  4998.2  499.46  5003.8  496.68  5013.1  494.50
  5017.3  492.73  5017.6  492.23  5021.1  492.23  5021.3  492.73  5026.4  493.28
  5033.9  500.02  5069.3  500.68  5076.7  499.01  5119.2  500.55  5140.0  503.35
  5150.3  505.70  5162.8  508.33  5169.1  508.56  5183.7  508.93  5217.6  507.81
#Mann=5,-1,0
  4783.2    0.05       0  4963.3    0.16       0  5017.3    0.07       0
  5021.3    0.16       0  5150.3    0.05       0
Bank Sta=5017.3,5021.3
Exp/Cntr=0.3,0.1

Type RM Length L Ch R = 1,37956,190,190,190
BEGIN DESCRIPTION:
Purtis Creek37955.87
END DESCRIPTION:
XS GIS Cut Line= 3
      2759542.73      6838673.43      2759176.54      6838853.91
      2759010.92      6838911.51
#Sta/Elev= 30
  4592.5  503.32  4596.4  501.84  4601.9  501.41  4611.1  499.45  4641.3  498.07
  4648.0  498.21  4663.7  497.74  4773.0  497.82  4888.3  497.92  4923.3  498.55
  4938.8  498.29  4967.9  499.12  4990.2  498.54  4998.3  497.59  5003.7  497.59
  5006.9  492.13  5010.2  491.98  5010.4  491.48  5013.9  491.48  5014.2  491.98
  5022.5  495.91  5038.0  498.19  5043.7  499.50  5069.1  500.30  5086.0  501.49
  5126.0  503.15  5157.1  506.24  5162.4  506.17  5170.7  506.90  5176.1  507.89
#Mann=5,-1,0
  4592.5    0.12       0  4648.0    0.05       0  4773.0    0.16       0
  5010.2    0.07       0  5014.2    0.16       0
Bank Sta=5010.2,5014.2
Exp/Cntr=0.3,0.1

Type RM Length L Ch R = 1,37766,412,412,412
BEGIN DESCRIPTION:
Purtis Creek37765.64
END DESCRIPTION:
XS GIS Cut Line= 3
      2759556.38      6838640.21      2759248.56      6838686.81
      2759056.04      6838711.34
#Sta/Elev= 30
  4689.5  505.65  4710.1  503.49  4726.7  499.11  4750.6  497.52  4882.0  497.05
  4892.2  495.70  4902.3  497.35  4912.4  497.87  4922.5  497.44  4928.1  495.97
  4933.1  497.93  4986.8  497.30  4996.9  497.48  4999.6  494.31  5004.6  494.31
  5011.5  490.27  5011.7  489.77  5015.2  489.77  5015.5  490.27  5023.6  496.87
  5033.7  497.89  5053.8  497.16  5063.9  497.36  5071.2  498.30  5104.2  497.81
  5124.4  498.94  5151.1  501.67  5156.1  501.39  5174.8  504.39  5194.9  506.12
#Mann=4,-1,0
  4689.5    0.12       0  4986.8    0.16       0  5011.5    0.07       0
  5015.5    0.16       0
Bank Sta=5011.5,5015.5
Exp/Cntr=0.3,0.1

Type RM Length L Ch R = 1,37354,188,188,188
BEGIN DESCRIPTION:
Purtis Creek37354.39
END DESCRIPTION:
XS GIS Cut Line= 3
      2759504.69      6838349.11      2759385.98      6838473.47
      2759151.74      6838634.02
#Sta/Elev= 30
  4829.6  507.38  4837.0  508.08  4844.3  504.86  4851.2  505.33  4858.4  501.99
  4865.3  502.33  4872.6  499.32  4879.5  499.44  4886.7  498.03  4893.6  498.36
  4900.9  497.06  4907.8  496.99  4922.0  494.02  4950.3  495.39  4992.7  494.91
  4997.9  493.72  5003.8  493.72  5011.6  487.92  5011.9  487.42  5015.6  487.92
  5021.7  493.68  5027.7  497.20  5046.2  497.38  5122.7  496.67  5147.6  498.03
  5159.1  498.67  5195.0  497.22  5251.8  498.08  5272.8  499.81  5285.5  499.92
#Mann=5,-1,0
  4829.6    0.16       0  5011.6    0.07       0  5015.6    0.16       0
  5046.2    0.12       0  5147.6    0.16       0
Bank Sta=5011.6,5015.6
Exp/Cntr=0.3,0.1

Type RM Length L Ch R = 1,37166,165,165,165
BEGIN DESCRIPTION:
Purtis Creek37166.02
END DESCRIPTION:
XS GIS Cut Line= 3
      2759359.31      6838211.75      2759241.04      6838362.13
      2759090.51      6838543.62
#Sta/Elev= 30
  4811.1  502.11  4820.5  502.11  4826.9  501.17  4835.0  501.31  4841.3  500.74
  4855.8  500.49  4876.6  498.39  4926.3  496.11  4948.8  495.75  4954.0  494.95
  4962.8  493.58  4969.6  488.11  4974.0  485.67  4974.3  485.17  4977.8  485.17
  4978.0  485.67  4984.1  489.44  4990.5  490.81  4998.5  493.45  5002.4  493.45
  5012.8  494.89  5047.9  494.61  5076.6  493.78  5097.4  495.71  5118.2  496.65
  5146.9  495.61  5154.7  495.82  5227.1  500.37  5232.9  500.54  5238.2  501.37
#Mann=5,-1,0
  4811.1    0.16       0  4954.0    0.12       0  4974.0    0.07       0
  4978.0    0.12       0  5227.1    0.16       0
Bank Sta=4974,4978
Exp/Cntr=0.3,0.1