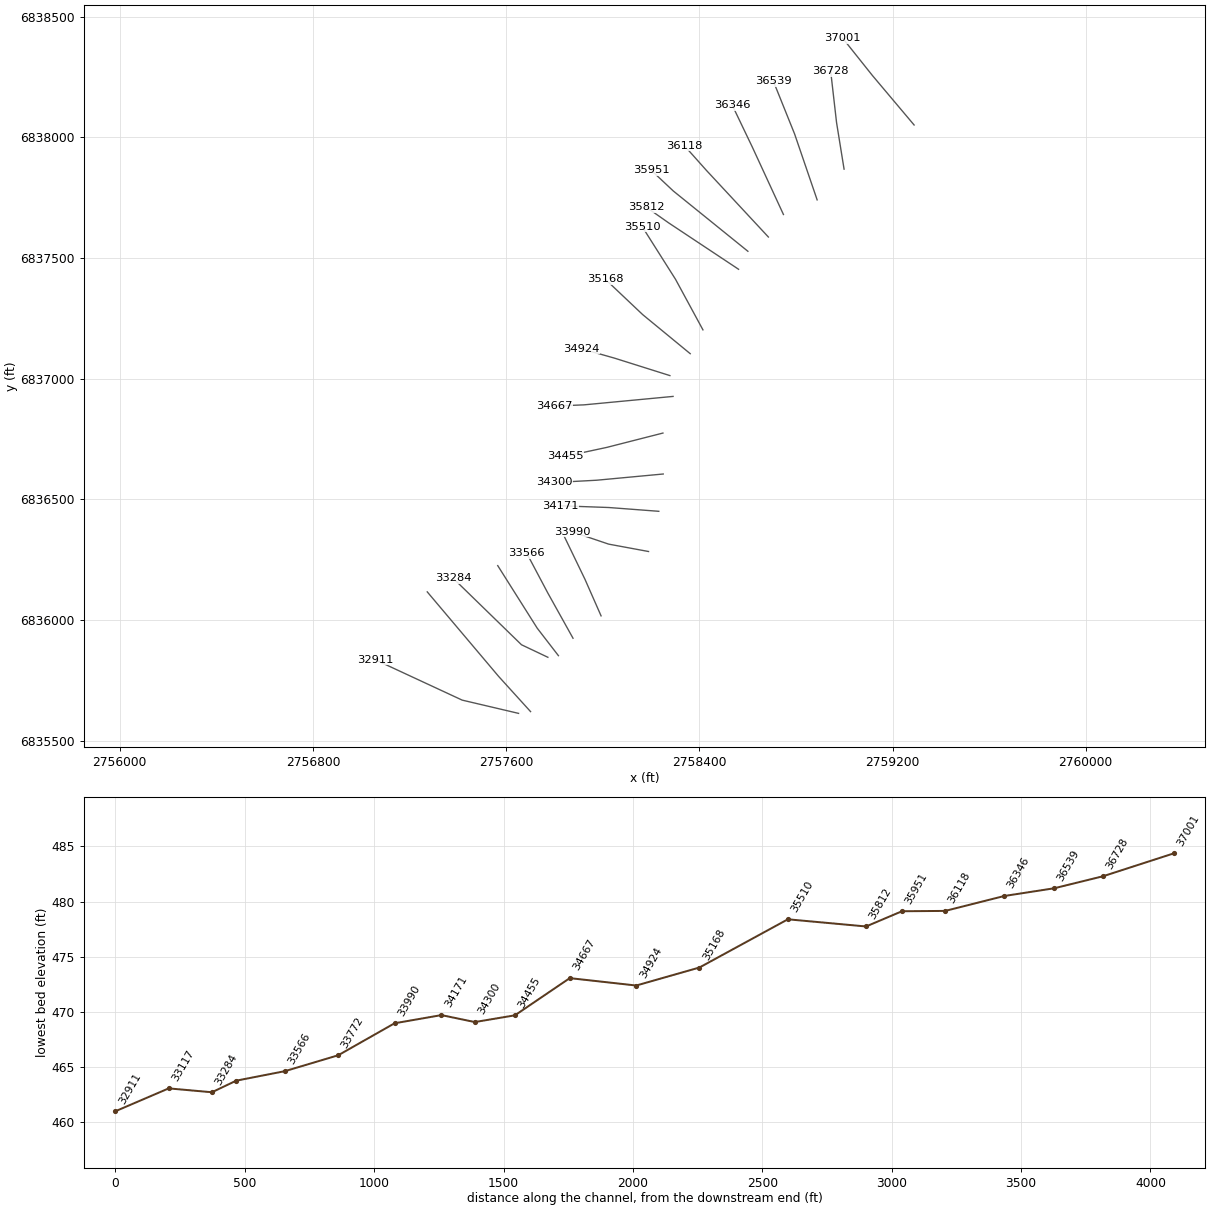
HEC-RAS study Purtis Creek.prj: Purtis Creek Base Level Engineering

--- Purtis Creek.g01 (geometry) --- (continued)

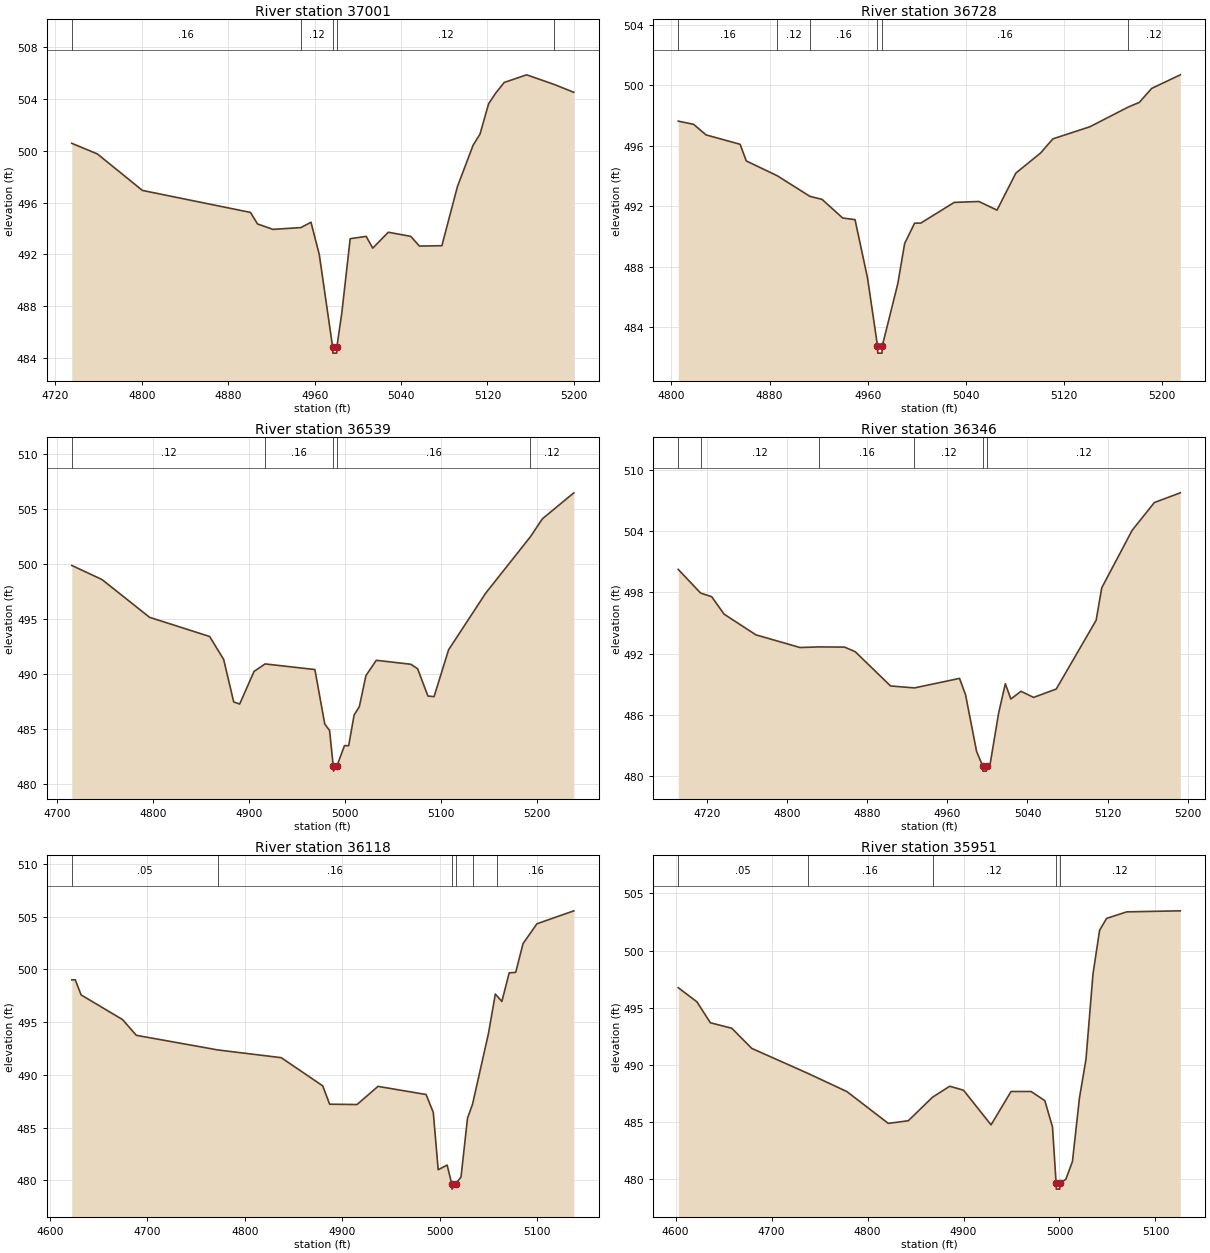
Type RM Length L Ch R = 1,37001,273,273,273
BEGIN DESCRIPTION:
Purtis Creek37000.62
END DESCRIPTION:
XS GIS Cut Line= 3
      2759289.39      6838051.57      2759116.89      6838256.49
      2758994.15      6838410.63
#Sta/Elev= 30
  4735.1  500.58  4758.8  499.76  4800.5  496.94  4900.6  495.24  4907.1  494.35
  4921.4  493.93  4947.3  494.07  4956.6  494.48  4964.3  491.98  4976.6  484.87
  4976.9  484.37  4980.4  484.37  4980.6  484.87  4985.1  487.44  4992.9  493.21
  5007.7  493.39  5013.8  492.48  5028.2  493.71  5049.0  493.39  5057.0  492.64
  5077.8  492.67  5092.2  497.23  5106.7  500.43  5113.1  501.29  5121.1  503.64
  5127.5  504.44  5135.5  505.28  5156.3  505.87  5181.7  505.13  5200.0  504.52
#Mann=5,-1,0
  4735.1    0.16       0  4947.3    0.12       0  4976.6    0.07       0
  4980.6    0.12       0  5181.7    0.16       0
Bank Sta=4976.6,4980.6
Exp/Cntr=0.3,0.1

Type RM Length L Ch R = 1,36728,189,189,189
BEGIN DESCRIPTION:
Purtis Creek36727.6
END DESCRIPTION:
XS GIS Cut Line= 3
      2758999.43      6837868.61      2758968.27      6838061.81
      2758943.99      6838274.23
#Sta/Elev= 30
  4805.5  497.63  4818.0  497.42  4828.2  496.72  4856.0  496.10  4861.0  495.00
  4886.3  494.02  4912.9  492.66  4922.8  492.46  4939.6  491.23  4949.7  491.12
  4959.9  487.26  4968.0  482.80  4968.2  482.30  4971.7  482.30  4972.0  482.80
  4984.6  486.90  4990.2  489.55  4998.3  490.89  5003.3  490.89  5030.6  492.26
  5050.7  492.32  5065.5  491.75  5080.9  494.20  5101.0  495.52  5111.1  496.46
  5141.3  497.26  5172.5  498.56  5181.6  498.87  5191.6  499.79  5215.0  500.69
#Mann=6,-1,0
  4805.5    0.16       0  4886.3    0.12       0  4912.9    0.16       0
  4968.0    0.07       0  4972.0    0.16       0  5172.5    0.12       0
Bank Sta=4968,4972
Exp/Cntr=0.3,0.1

Type RM Length L Ch R = 1,36539,193,193,193
BEGIN DESCRIPTION:
Purtis Creek36538.82
END DESCRIPTION:
XS GIS Cut Line= 3
      2758887.92      6837741.24      2758794.59      6838014.28
      2758707.00      6838232.08
#Sta/Elev= 30
  4715.0  499.88  4746.5  498.60  4796.1  495.17  4858.7  493.43  4873.3  491.35
  4883.8  487.49  4890.0  487.30  4905.0  490.26  4916.5  490.94  4968.4  490.43
  4978.7  485.48  4983.7  484.90  4987.5  481.71  4987.8  481.21  4991.5  481.71
  4999.2  483.52  5003.6  483.52  5009.3  486.31  5014.7  487.05  5021.6  489.88
  5032.4  491.27  5068.4  490.91  5075.5  490.50  5086.2  488.03  5092.6  487.97
  5107.8  492.23  5146.4  497.36  5193.1  502.49  5205.5  504.11  5238.3  506.47
#Mann=5,-1,0
  4715.0    0.12       0  4916.5    0.16       0  4987.5    0.07       0
  4991.5    0.16       0  5193.1    0.12       0
Bank Sta=4987.5,4991.5
Exp/Cntr=0.3,0.1

Type RM Length L Ch R = 1,36346,228,228,228
BEGIN DESCRIPTION:
Purtis Creek36346.16
END DESCRIPTION:
XS GIS Cut Line= 3
      2758748.37      6837680.63      2758619.61      6837959.79
      2758536.02      6838134.39
#Sta/Elev= 30
  4691.5  500.24  4713.8  497.93  4724.9  497.57  4737.2  495.87  4769.0  493.84
  4813.0  492.60  4832.4  492.66  4857.5  492.64  4868.1  492.19  4903.4  488.84
  4927.2  488.65  4972.2  489.58  4978.2  487.98  4989.2  482.44  4995.3  481.01
  4995.5  480.51  4999.0  480.51  4999.3  481.01  5002.4  481.01  5011.3  486.23
  5017.9  489.06  5023.4  487.56  5033.5  488.32  5046.1  487.72  5068.7  488.54
  5108.5  495.26  5114.1  498.44  5144.4  504.06  5166.6  506.78  5192.5  507.73
#Mann=6,-1,0
  4691.5    0.05       0  4713.8    0.12       0  4832.4    0.16       0
  4927.2    0.12       0  4995.3    0.07       0  4999.3    0.12       0
Bank Sta=4995.3,4999.3
Exp/Cntr=0.3,0.1

Type RM Length L Ch R = 1,36118,167,167,167
BEGIN DESCRIPTION:
Purtis Creek36117.85
END DESCRIPTION:
XS GIS Cut Line= 3
      2758685.98      6837587.35      2758429.49      6837863.37
      2758337.67      6837966.40
#Sta/Elev= 30
  4622.6  499.00  4626.2  499.00  4632.2  497.57  4674.7  495.23  4688.8  493.74
  4772.6  492.35  4837.4  491.62  4879.9  488.95  4887.0  487.21  4915.1  487.18
  4936.6  488.90  4985.9  488.13  4993.3  486.42  4998.3  481.00  5007.5  481.44
  5012.2  479.66  5012.5  479.16  5016.2  479.66  5021.7  480.30  5028.4  485.90
  5033.5  487.20  5049.8  493.89  5056.9  497.65  5058.7  497.46  5063.6  496.95
  5071.1  499.66  5077.8  499.71  5085.3  502.43  5099.5  504.31  5137.4  505.54
#Mann=6,-1,0
  4622.6    0.05       0  4772.6    0.16       0  5012.2    0.07       0
  5016.2    0.16       0  5033.5    0.12       0  5058.7    0.16       0
Bank Sta=5012.2,5016.2
Exp/Cntr=0.3,0.1

Type RM Length L Ch R = 1,35951,139,139,139
BEGIN DESCRIPTION:
Purtis Creek35950.51
END DESCRIPTION:
XS GIS Cut Line= 3
      2758601.14      6837528.25      2758292.04      6837778.30
      2758200.48      6837864.31
#Sta/Elev= 30
  4602.7  496.75  4622.2  495.51  4636.2  493.68  4658.5  493.20  4679.3  491.44
  4737.9  489.25  4778.5  487.66  4821.6  484.88  4842.4  485.11  4867.7  487.17
  4885.6  488.13  4900.0  487.78  4928.7  484.75  4949.5  487.67  4970.4  487.67
  4984.7  486.87  4992.7  484.57  4996.5  479.63  4996.7  479.13  5000.2  479.13
  5000.5  479.63  5006.6  479.99  5013.5  481.55  5020.8  487.10  5027.6  490.48
  5034.9  497.95  5041.8  501.77  5049.1  502.81  5070.1  503.38  5125.9  503.47
#Mann=5,-1,0
  4602.7    0.05       0  4737.9    0.16       0  4867.7    0.12       0
  4996.5    0.07       0  5000.5    0.12       0
Bank Sta=4996.5,5000.5
Exp/Cntr=0.3,0.1

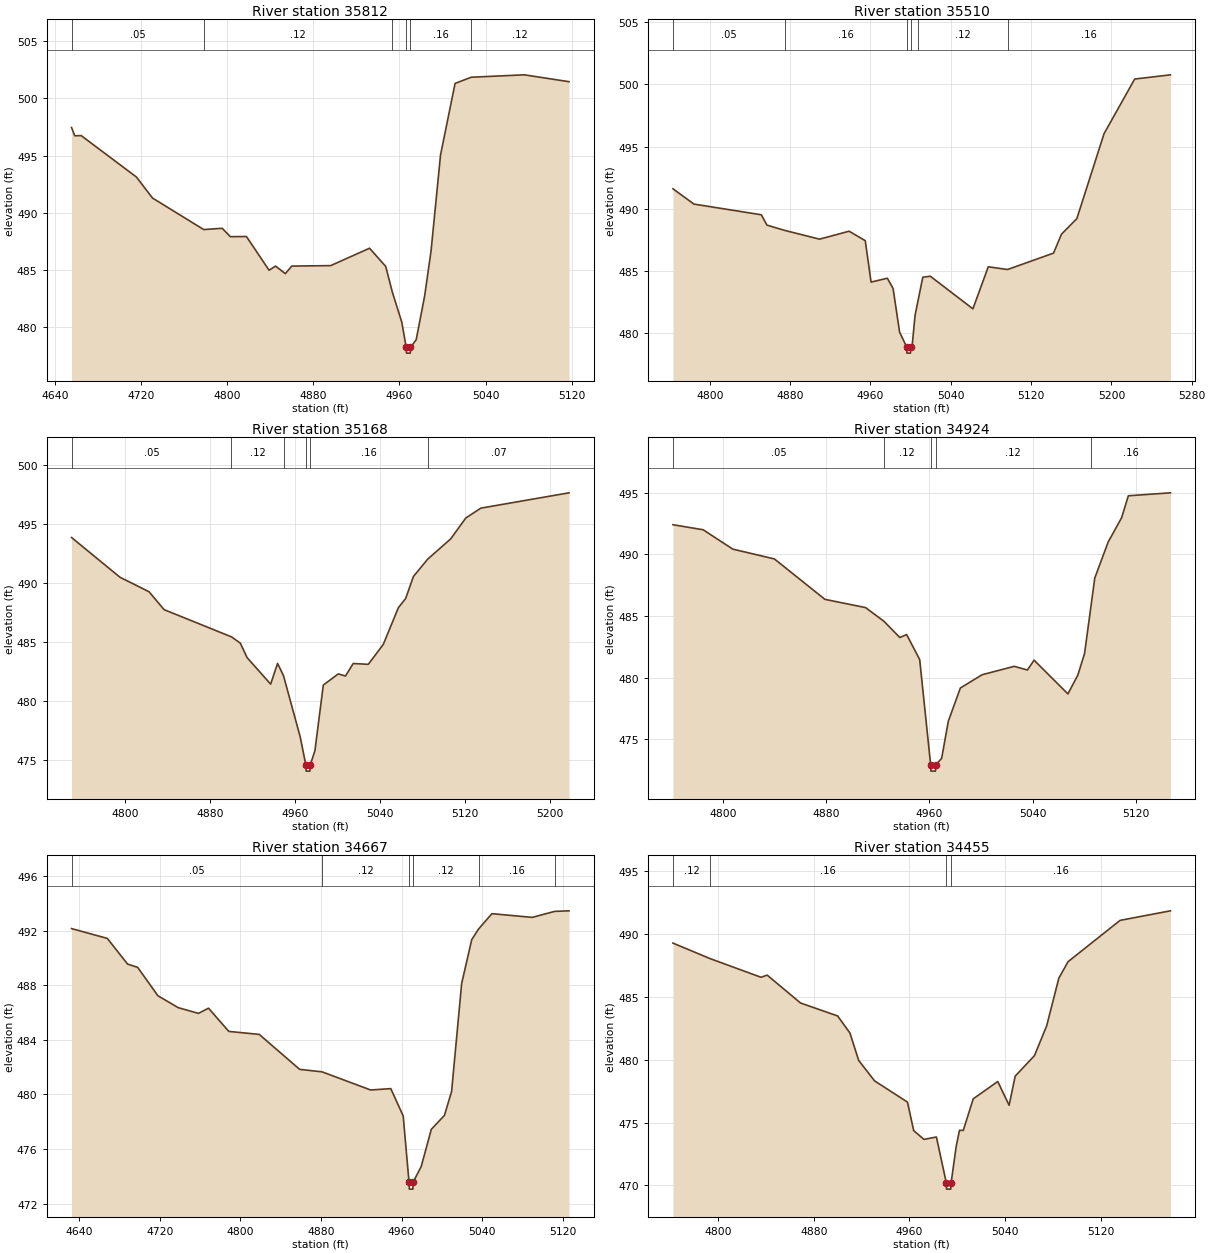
Type RM Length L Ch R = 1,35812,302,302,302
BEGIN DESCRIPTION:
Purtis Creek35812.08
END DESCRIPTION:
XS GIS Cut Line= 3
      2758562.57      6837453.69      2758273.23      6837645.79
      2758179.46      6837711.67
#Sta/Elev= 30
  4655.5  497.45  4658.5  496.73  4664.5  496.74  4715.7  493.13  4730.7  491.29
  4778.2  488.54  4795.4  488.65  4802.9  487.92  4817.9  487.93  4838.9  484.99
  4844.9  485.35  4854.0  484.69  4860.0  485.35  4896.1  485.39  4932.2  486.91
  4947.2  485.32  4953.3  483.10  4962.2  480.43  4966.2  478.25  4966.5  477.75
  4970.0  477.75  4970.2  478.25  4975.5  478.92  4983.3  482.71  4989.3  486.67
  4998.1  495.05  5011.6  501.30  5026.6  501.84  5075.8  502.05  5117.4  501.45
#Mann=6,-1,0
  4655.5    0.05       0  4778.2    0.12       0  4953.3    0.16       0
  4966.2    0.07       0  4970.2    0.16       0  5026.6    0.12       0
Bank Sta=4966.2,4970.2
Exp/Cntr=0.3,0.1

Type RM Length L Ch R = 1,35510,342,342,342
BEGIN DESCRIPTION:
Purtis Creek35510.13
END DESCRIPTION:
XS GIS Cut Line= 3
      2758415.04      6837202.59      2758301.58      6837411.97
      2758164.07      6837629.39
#Sta/Elev= 30
  4763.4  491.61  4784.3  490.38  4851.4  489.52  4857.0  488.69  4874.5  488.27
  4909.4  487.56  4938.8  488.20  4954.9  487.44  4960.7  484.11  4976.9  484.42
  4982.6  483.60  4989.1  480.09  4996.1  478.90  4996.4  478.40  4999.9  478.40
  5000.1  478.90  5001.5  478.90  5004.5  481.44  5007.1  482.47  5012.2  484.50
  5019.7  484.58  5062.1  481.96  5077.4  485.34  5096.6  485.12  5142.4  486.44
  5150.3  487.96  5165.6  489.21  5192.7  496.04  5223.2  500.43  5258.8  500.77
#Mann=6,-1,0
  4763.4    0.05       0  4874.5    0.16       0  4996.1    0.07       0
  5000.1    0.16       0  5007.1    0.12       0  5096.6    0.16       0
Bank Sta=4996.1,5000.1
Exp/Cntr=0.3,0.1

Type RM Length L Ch R = 1,35168,244,244,244
BEGIN DESCRIPTION:
Purtis Creek35168.14
END DESCRIPTION:
XS GIS Cut Line= 3
      2758362.37      6837103.87      2758165.56      6837265.78
      2758010.27      6837412.81
#Sta/Elev= 30
  4749.2  493.85  4794.8  490.48  4822.2  489.25  4836.4  487.73  4899.9  485.42
  4908.2  484.89  4914.6  483.66  4936.8  481.41  4943.3  483.17  4948.9  482.13
  4964.6  476.95  4970.0  474.53  4970.3  474.03  4973.8  474.03  4974.0  474.53
  4978.5  475.76  4986.4  481.33  5000.5  482.28  5007.3  482.10  5014.6  483.16
  5028.8  483.09  5042.9  484.78  5057.1  487.89  5064.0  488.68  5071.3  490.54
  5084.7  492.01  5106.5  493.74  5120.6  495.50  5134.8  496.34  5217.9  497.64
#Mann=6,-1,0
  4749.2    0.05       0  4899.9    0.12       0  4948.9    0.16       0
  4970.0    0.07       0  4974.0    0.16       0  5084.7    0.07       0
Bank Sta=4970,4974
Exp/Cntr=0.3,0.1

Type RM Length L Ch R = 1,34924,257,257,257
BEGIN DESCRIPTION:
Purtis Creek34924.48
END DESCRIPTION:
XS GIS Cut Line= 3
      2758278.27      6837013.07      2758048.74      6837085.42
      2757909.60      6837124.89
#Sta/Elev= 30
  4761.4  492.41  4784.8  492.00  4807.7  490.43  4840.0  489.63  4879.1  486.35
  4910.6  485.68  4924.9  484.56  4937.1  483.25  4942.4  483.49  4952.5  481.46
  4961.0  472.90  4961.2  472.40  4964.7  472.40  4965.0  472.90  4969.5  473.44
  4974.7  476.46  4984.0  479.15  5000.9  480.23  5025.7  480.91  5035.9  480.61
  5041.1  481.41  5067.3  478.67  5075.0  480.20  5080.2  481.96  5084.8  485.52
  5088.1  488.08  5098.5  491.01  5108.9  492.98  5114.1  494.76  5146.7  495.00
#Mann=5,-1,0
  4761.4    0.05       0  4924.9    0.12       0  4961.0    0.07       0
  4965.0    0.12       0  5084.8    0.16       0
Bank Sta=4961,4965
Exp/Cntr=0.3,0.1

Type RM Length L Ch R = 1,34667,212,212,212
BEGIN DESCRIPTION:
Purtis Creek34666.93
END DESCRIPTION:
XS GIS Cut Line= 3
      2758291.33      6836926.81      2757923.05      6836891.86
      2757799.59      6836886.71
#Sta/Elev= 30
  4632.6  492.15  4668.1  491.43  4688.2  489.55  4698.2  489.31  4718.3  487.23
  4738.4  486.36  4758.5  485.94  4768.5  486.32  4788.6  484.62  4818.8  484.40
  4858.9  481.84  4881.1  481.66  4929.3  480.33  4949.3  480.43  4961.6  478.43
  4967.4  473.57  4967.7  473.07  4971.2  473.07  4971.4  473.57  4979.5  474.73
  4989.5  477.45  5002.5  478.47  5009.6  480.21  5019.6  488.13  5029.6  491.34
  5036.4  492.12  5049.6  493.24  5089.7  492.97  5111.9  493.41  5126.1  493.45
#Mann=6,-1,0
  4632.6    0.05       0  4881.1    0.12       0  4967.4    0.07       0
  4971.4    0.12       0  5036.4    0.16       0  5111.9    0.07       0
Bank Sta=4967.4,4971.4
Exp/Cntr=0.3,0.1

Type RM Length L Ch R = 1,34455,155,155,155
BEGIN DESCRIPTION:
Purtis Creek34454.87
END DESCRIPTION:
XS GIS Cut Line= 3
      2758249.39      6836774.97      2758017.24      6836715.63
      2757844.80      6836678.54
#Sta/Elev= 30
  4762.3  489.29  4793.5  488.05  4835.9  486.57  4841.1  486.74  4869.0  484.52
  4900.0  483.49  4910.3  482.13  4917.6  479.95  4930.9  478.32  4958.4  476.63
  4963.6  474.36  4972.2  473.66  4982.6  473.85  4990.9  470.20  4991.1  469.70
  4994.6  469.70  4994.9  470.20  4999.2  473.13  5001.9  474.38  5005.1  474.38
  5013.4  476.89  5033.9  478.27  5043.4  476.38  5048.5  478.70  5064.6  480.33
  5074.8  482.70  5085.0  486.50  5092.7  487.81  5136.2  491.10  5178.3  491.86
#Mann=4,-1,0
  4762.3    0.12       0  4793.5    0.16       0  4990.9    0.07       0
  4994.9    0.16       0
Bank Sta=4990.9,4994.9
Exp/Cntr=0.3,0.1

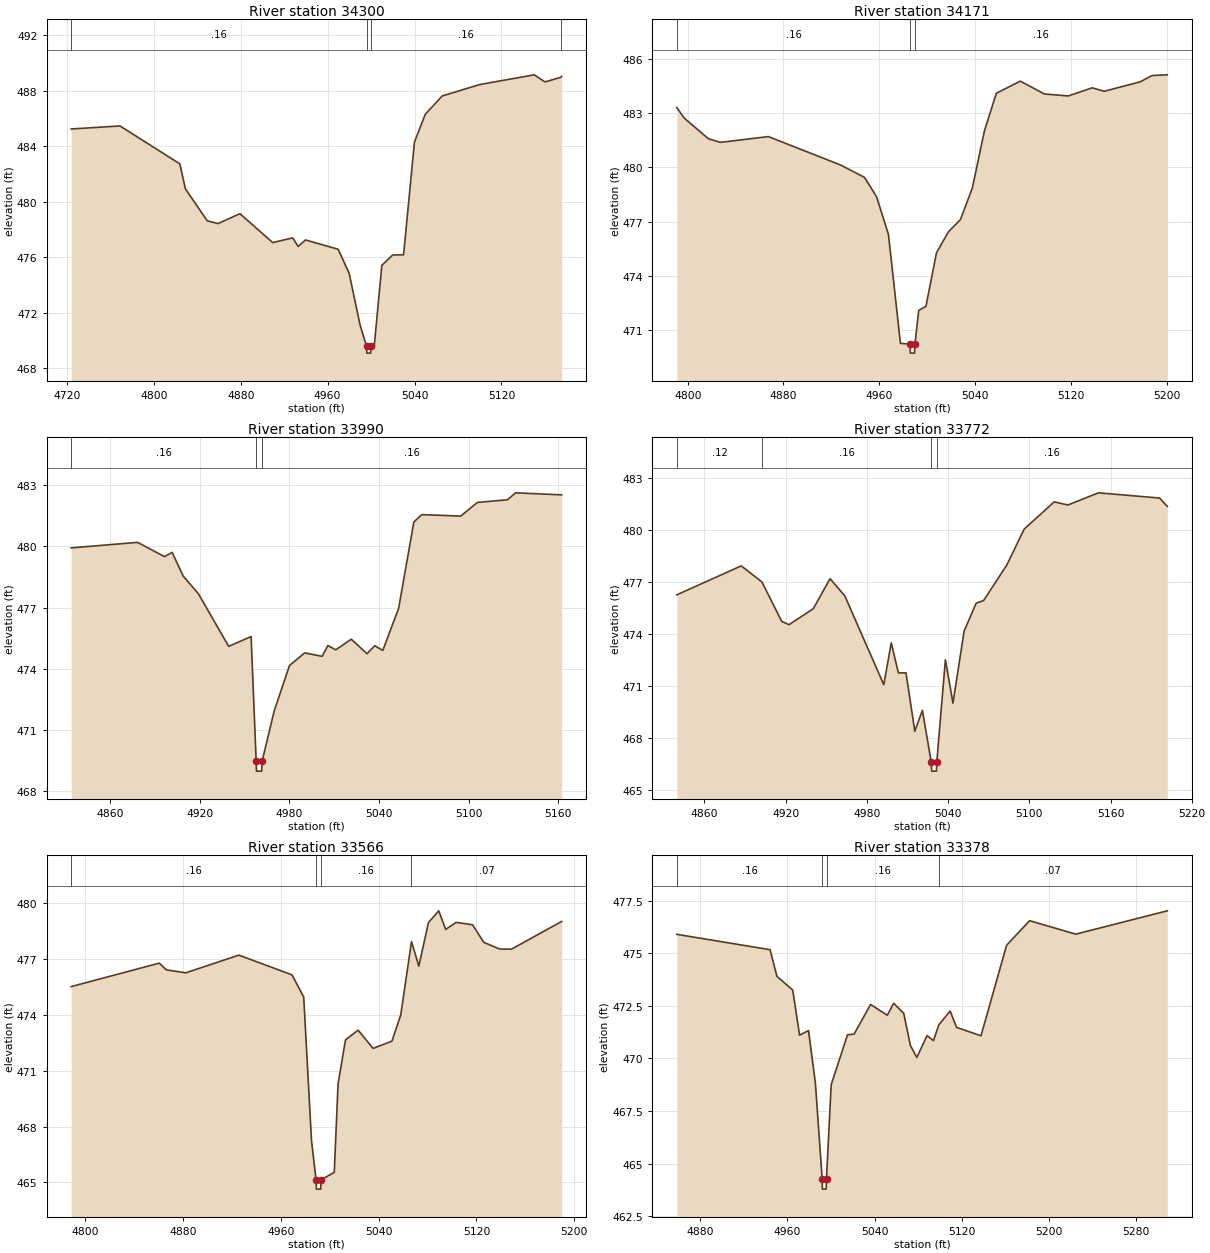
Type RM Length L Ch R = 1,34300,129,129,129
BEGIN DESCRIPTION:
Purtis Creek34300.4
END DESCRIPTION:
XS GIS Cut Line= 3
      2758250.66      6836605.29      2757975.01      6836579.52
      2757800.72      6836570.09
#Sta/Elev= 30
  4724.0  485.23  4768.9  485.45  4824.0  482.72  4829.1  480.92  4849.2  478.62
  4859.2  478.42  4879.3  479.13  4909.5  477.05  4927.9  477.39  4932.9  476.77
  4939.6  477.24  4969.7  476.57  4979.8  474.84  4989.8  471.14  4995.8  469.59
  4996.1  469.09  4999.6  469.09  4999.8  469.59  5002.9  469.59  5009.9  475.41
  5019.9  476.16  5029.9  476.17  5039.9  484.29  5049.9  486.29  5065.5  487.61
  5100.0  488.43  5150.1  489.13  5160.1  488.62  5174.5  488.95  5175.4  489.02
#Mann=4,-1,0
  4724.0    0.16       0  4995.8    0.07       0  4999.8    0.16       0
  5174.5    0.07       0
Bank Sta=4995.8,4999.8
Exp/Cntr=0.3,0.1

Type RM Length L Ch R = 1,34171,181,181,181
BEGIN DESCRIPTION:
Purtis Creek34170.54
END DESCRIPTION:
XS GIS Cut Line= 3
      2758232.30      6836450.71      2758024.78      6836466.44
      2757823.33      6836473.65
#Sta/Elev= 30
  4790.9  483.32  4797.2  482.73  4817.3  481.59  4827.3  481.39  4867.4  481.71
  4927.6  480.14  4947.7  479.45  4957.7  478.39  4967.7  476.29  4977.7  470.26
  4985.8  470.22  4986.0  469.72  4989.5  469.72  4989.8  470.22  4993.0  472.09
  4999.0  472.31  5007.8  475.27  5017.8  476.44  5027.8  477.11  5037.8  478.87
  5047.8  482.01  5057.8  484.11  5077.8  484.78  5097.9  484.07  5117.9  483.96
  5137.9  484.41  5147.9  484.22  5177.9  484.74  5187.9  485.09  5200.6  485.13
#Mann=3,-1,0
  4790.9    0.16       0  4985.8    0.07       0  4989.8    0.16       0
Bank Sta=4985.8,4989.8
Exp/Cntr=0.3,0.1

Type RM Length L Ch R = 1,33990,218,218,218
BEGIN DESCRIPTION:
Purtis Creek33990.42
END DESCRIPTION:
XS GIS Cut Line= 3
      2758189.77      6836284.12      2758024.51      6836314.72
      2757872.57      6836366.20
#Sta/Elev= 30
  4833.9  479.93  4878.4  480.20  4896.4  479.50  4901.5  479.71  4908.9  478.55
  4919.1  477.68  4939.4  475.10  4954.4  475.58  4957.8  469.48  4958.0  468.98
  4961.5  468.98  4961.8  469.48  4969.9  471.94  4980.1  474.16  4990.3  474.78
  5002.0  474.61  5005.8  475.14  5011.1  474.93  5021.5  475.45  5032.0  474.74
  5037.2  475.13  5042.6  474.90  5053.2  476.96  5063.4  481.20  5068.7  481.56
  5094.8  481.49  5106.0  482.16  5126.2  482.29  5131.5  482.63  5162.4  482.53
#Mann=3,-1,0
  4833.9    0.16       0  4957.8    0.07       0  4961.8    0.16       0
Bank Sta=4957.8,4961.8
Exp/Cntr=0.3,0.1

Type RM Length L Ch R = 1,33772,206,206,206
BEGIN DESCRIPTION:
Purtis Creek33772.04
END DESCRIPTION:
XS GIS Cut Line= 3
      2757993.23      6836017.43      2757926.69      6836168.60
      2757841.07      6836346.17
#Sta/Elev= 30
  4839.6  476.24  4887.2  477.91  4902.5  476.98  4917.1  474.71  4922.5  474.52
  4940.4  475.44  4952.8  477.17  4963.7  476.18  4992.5  471.06  4998.0  473.47
  5003.3  471.74  5008.9  471.74  5015.4  468.38  5021.0  469.58  5027.6  466.58
  5027.9  466.08  5031.4  466.08  5031.6  466.58  5038.0  472.50  5043.6  470.00
  5051.8  474.14  5060.7  475.76  5066.2  475.91  5083.3  477.95  5096.2  480.03
  5118.4  481.60  5128.5  481.42  5151.1  482.12  5196.2  481.82  5201.9  481.34
#Mann=4,-1,0
  4839.6    0.12       0  4902.5    0.16       0  5027.6    0.07       0
  5031.6    0.16       0
Bank Sta=5027.6,5031.6
Exp/Cntr=0.3,0.1

Type RM Length L Ch R = 1,33566,188,188,188
BEGIN DESCRIPTION:
Purtis Creek33565.91
END DESCRIPTION:
XS GIS Cut Line= 3
      2757877.02      6835924.77      2757772.29      6836112.89
      2757685.23      6836277.36
#Sta/Elev= 30
  4788.4  475.52  4860.5  476.78  4866.2  476.42  4882.2  476.26  4925.6  477.21
  4969.1  476.15  4978.7  474.96  4985.1  467.22  4988.8  465.14  4989.1  464.64
  4992.6  464.64  4992.8  465.14  5003.7  465.54  5006.8  470.29  5012.9  472.66
  5023.2  473.18  5035.5  472.20  5050.9  472.59  5058.1  473.99  5066.9  477.94
  5072.9  476.62  5080.8  478.96  5089.2  479.59  5094.9  478.59  5103.4  478.97
  5116.9  478.84  5126.0  477.90  5138.9  477.54  5148.7  477.53  5189.8  479.02
#Mann=4,-1,0
  4788.4    0.16       0  4988.8    0.07       0  4992.8    0.16       0
  5066.9    0.07       0
Bank Sta=4988.8,4992.8
Exp/Cntr=0.3,0.1

Type RM Length L Ch R = 1,33378,94,94,94
BEGIN DESCRIPTION:
Purtis Creek33378.46
END DESCRIPTION:
XS GIS Cut Line= 3
      2757816.57      6835852.56      2757728.84      6835966.36
      2757565.32      6836225.60
#Sta/Elev= 30
  4858.5  475.91  4944.1  475.18  4950.4  473.91  4964.9  473.26  4971.2  471.11
  4979.4  471.33  4985.7  468.83  4991.9  464.28  4992.1  463.78  4995.6  463.78
  4995.9  464.28  5000.2  468.75  5015.2  471.13  5021.2  471.16  5036.4  472.57
  5051.7  472.06  5057.6  472.63  5066.8  472.15  5072.9  470.62  5078.8  470.05
  5088.2  471.09  5094.1  470.85  5099.0  471.60  5109.4  472.26  5115.3  471.48
  5137.7  471.08  5161.2  475.39  5182.3  476.56  5224.7  475.92  5308.7  477.03
#Mann=4,-1,0
  4858.5    0.16       0  4991.9    0.07       0  4995.9    0.16       0
  5099.0    0.07       0
Bank Sta=4991.9,4995.9
Exp/Cntr=0.3,0.1

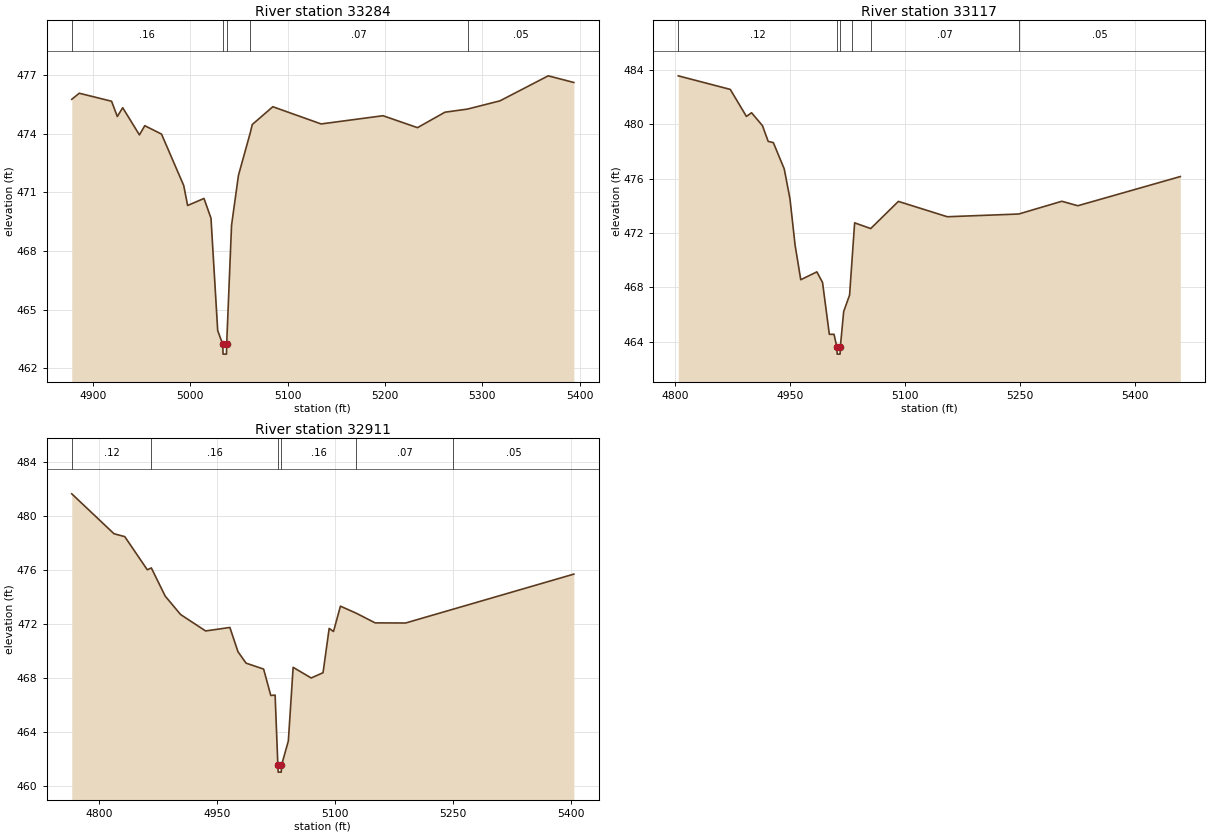
Type RM Length L Ch R = 1,33284,167,167,167
BEGIN DESCRIPTION:
Purtis Creek33284.04
END DESCRIPTION:
XS GIS Cut Line= 3
      2757772.97      6835845.79      2757663.72      6835897.68
      2757380.91      6836173.08
#Sta/Elev= 30
  4878.3  475.76  4886.0  476.07  4919.2  475.66  4925.1  474.88  4930.6  475.33
  4947.8  473.94  4953.3  474.41  4970.5  473.98  4993.3  471.35  4997.3  470.33
  5014.1  470.69  5021.3  469.68  5028.2  463.93  5033.4  463.23  5033.7  462.73
  5037.2  462.73  5037.4  463.23  5042.4  469.31  5049.5  471.87  5061.6  474.04
  5063.7  474.47  5084.8  475.38  5134.4  474.50  5198.0  474.92  5233.4  474.31
  5261.6  475.10  5284.8  475.26  5318.1  475.68  5367.7  476.96  5394.0  476.62
#Mann=5,-1,0
  4878.3    0.16       0  5033.4    0.07       0  5037.4    0.16       0
  5061.6    0.07       0  5284.8    0.05       0
Bank Sta=5033.4,5037.4
Exp/Cntr=0.3,0.1

Type RM Length L Ch R = 1,33117,206,206,206
BEGIN DESCRIPTION:
Purtis Creek33116.74
END DESCRIPTION:
XS GIS Cut Line= 3
      2757701.30      6835620.66      2757568.83      6835766.78
      2757273.49      6836116.80
#Sta/Elev= 30
  4804.2  483.58  4872.1  482.58  4893.2  480.59  4899.9  480.86  4914.1  479.91
  4921.6  478.75  4928.3  478.66  4942.5  476.73  4950.0  474.53  4956.7  471.11
  4964.1  468.56  4985.1  469.14  4992.5  468.36  5001.4  464.54  5007.5  464.54
  5011.3  463.58  5011.6  463.08  5015.4  463.08  5015.7  463.58  5020.1  466.22
  5027.8  467.43  5031.4  470.33  5034.4  472.75  5055.4  472.33  5091.5  474.33
  5155.3  473.20  5248.5  473.40  5304.8  474.34  5325.6  474.01  5459.4  476.16
#Mann=6,-1,0
  4804.2    0.12       0  5011.3    0.07       0  5015.7    0.12       0
  5031.4    0.16       0  5055.4    0.07       0  5248.5    0.05       0
Bank Sta=5011.3,5015.7
Exp/Cntr=0.3,0.1

Type RM Length L Ch R = 1,32911,172,172,172
BEGIN DESCRIPTION:
Purtis Creek32911.41
END DESCRIPTION:
XS GIS Cut Line= 3
      2757651.57      6835613.36      2757418.05      6835668.29
      2757057.04      6835836.09
#Sta/Elev= 30
  4765.4  481.67  4819.0  478.71  4832.8  478.49  4861.4  476.03  4866.5  476.17
  4884.1  474.08  4903.7  472.71  4935.5  471.49  4966.3  471.75  4976.6  469.95
  4986.9  469.10  5009.2  468.66  5018.3  466.70  5023.8  466.73  5027.3  461.51
  5027.7  461.01  5031.6  461.01  5031.9  461.51  5040.6  463.32  5046.7  468.79
  5069.6  468.00  5084.7  468.39  5092.5  471.68  5098.0  471.45  5106.8  473.33
  5126.8  472.81  5150.9  472.09  5189.6  472.08  5249.7  473.10  5403.4  475.71
#Mann=6,-1,0
  4765.4    0.12       0  4866.5    0.16       0  5027.3    0.07       0
  5031.9    0.16       0  5126.8    0.07       0  5249.7    0.05       0
Bank Sta=5027.3,5031.9
Exp/Cntr=0.3,0.1