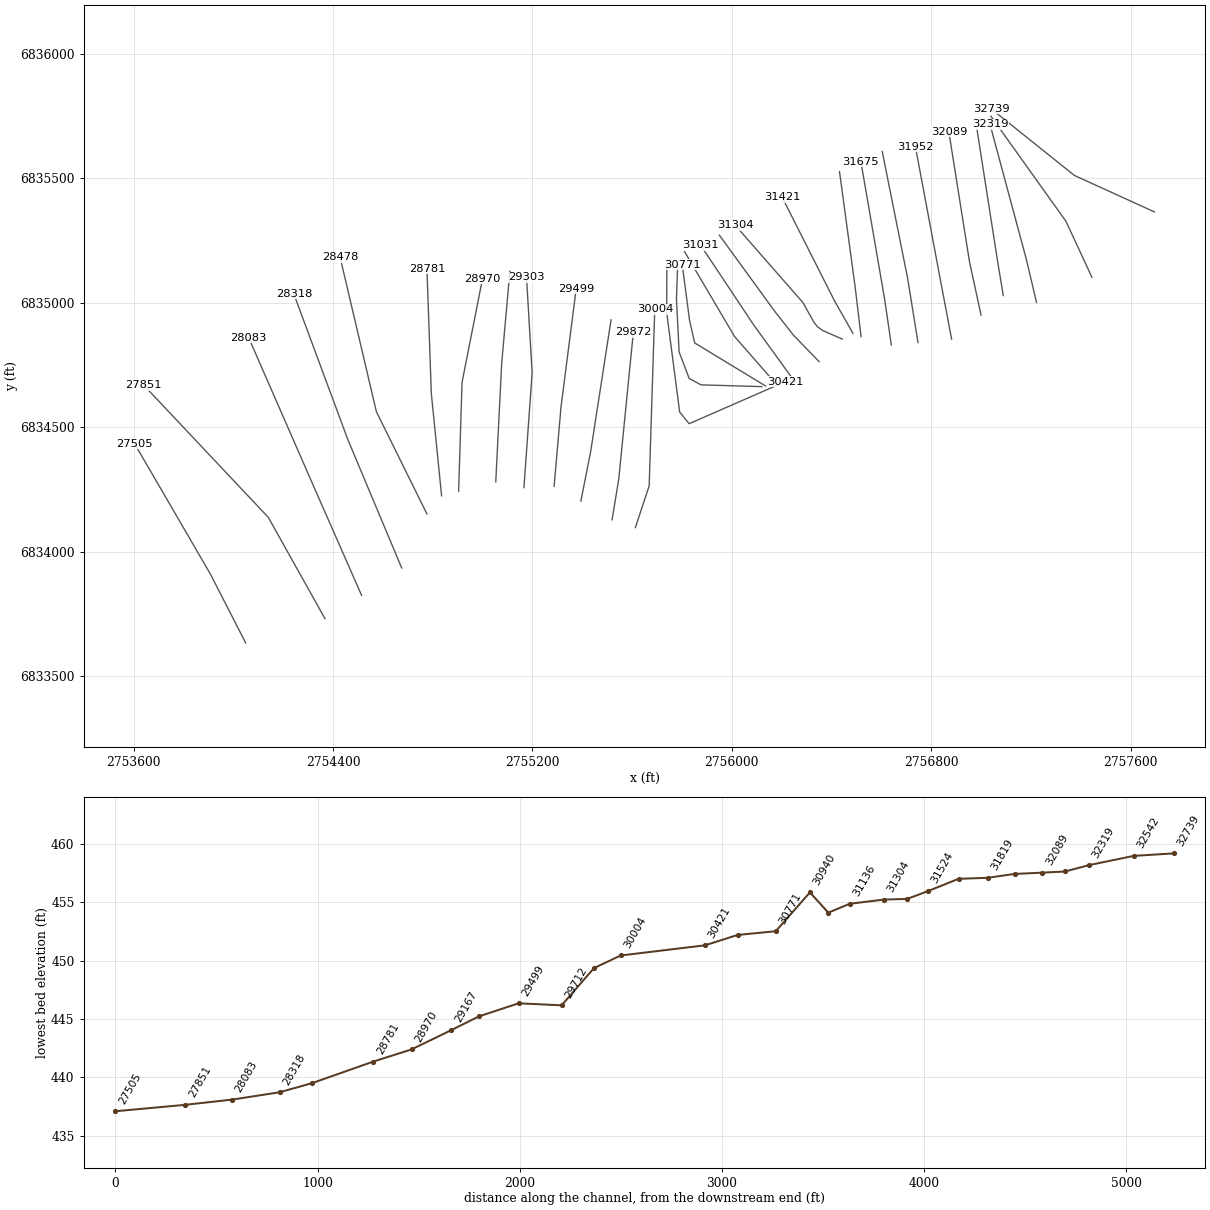
HEC-RAS study Purtis Creek.prj: Purtis Creek Base Level Engineering

--- Purtis Creek.g01 (geometry) --- (continued)

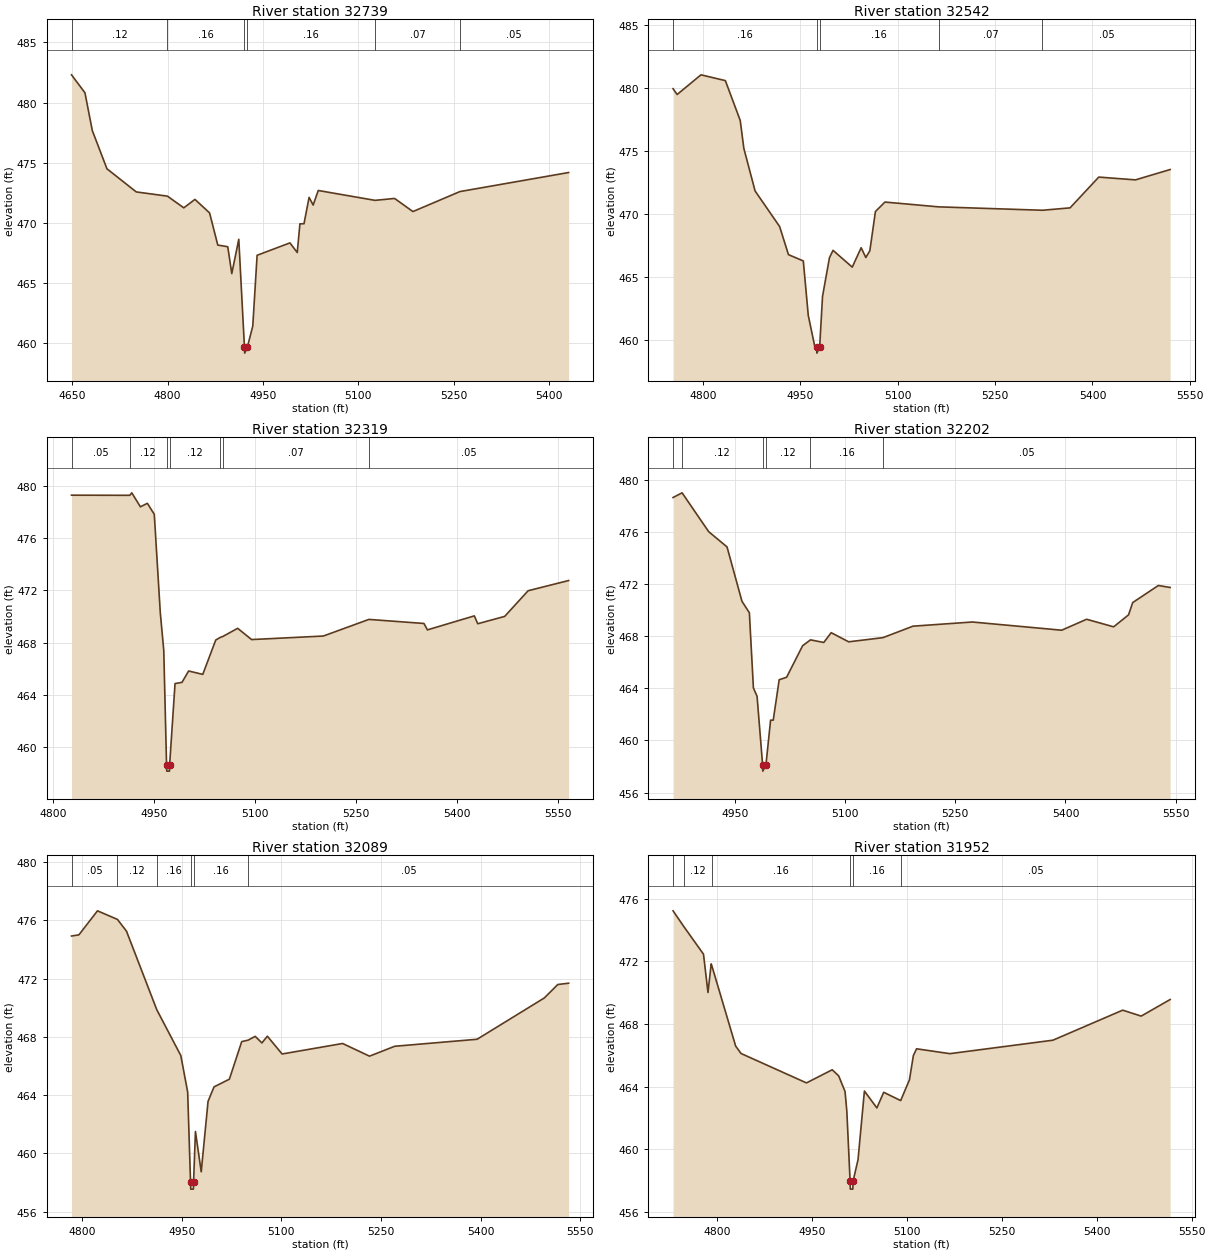
Type RM Length L Ch R = 1,32739,197,197,197
BEGIN DESCRIPTION:
Purtis Creek32738.75
END DESCRIPTION:
XS GIS Cut Line= 3
      2757695.21      6835364.47      2757374.27      6835510.79
      2757039.79      6835778.75
#Sta/Elev= 30
  4649.1  482.30  4670.2  480.81  4681.8  477.67  4704.8  474.50  4750.9  472.58
  4799.8  472.23  4825.6  471.26  4843.1  471.96  4866.1  470.84  4879.0  468.17
  4894.7  468.03  4901.0  465.80  4912.0  468.65  4920.9  459.70  4921.3  459.20
  4925.5  459.70  4934.0  461.45  4940.8  467.32  4992.4  468.35  5003.9  467.55
  5008.1  469.93  5014.5  469.94  5022.5  472.13  5028.9  471.49  5036.9  472.70
  5126.2  471.88  5156.9  472.04  5185.7  470.95  5259.6  472.61  5430.4  474.19
#Mann=6,-1,0
  4649.1    0.12       0  4799.8    0.16       0  4920.9    0.07       0
  4925.5    0.16       0  5126.2    0.07       0  5259.6    0.05       0
Bank Sta=4920.9,4925.5
Exp/Cntr=0.3,0.1

Type RM Length L Ch R = 1,32542,223,223,223
BEGIN DESCRIPTION:
Purtis Creek32541.89
END DESCRIPTION:
XS GIS Cut Line= 3
      2757444.48      6835102.02      2757340.56      6835326.39
      2757039.33      6835748.58
#Sta/Elev= 30
  4753.8  479.96  4760.1  479.50  4796.8  481.06  4834.4  480.60  4857.3  477.44
  4862.9  475.22  4880.2  471.85  4918.0  469.03  4931.6  466.80  4954.5  466.30
  4962.1  461.99  4971.9  459.58  4975.1  459.49  4975.4  458.99  4979.7  459.49
  4984.1  463.49  4994.8  466.56  5000.3  467.14  5029.9  465.81  5043.6  467.35
  5050.8  466.57  5057.0  467.11  5065.6  470.22  5080.3  470.97  5162.8  470.59
  5323.0  470.32  5365.5  470.51  5409.7  472.95  5466.3  472.73  5519.7  473.55
#Mann=5,-1,0
  4753.8    0.16       0  4975.1    0.07       0  4979.7    0.16       0
  5162.8    0.07       0  5323.0    0.05       0
Bank Sta=4975.1,4979.7
Exp/Cntr=0.3,0.1

Type RM Length L Ch R = 1,32319,117,117,117
BEGIN DESCRIPTION:
Purtis Creek32319.27
END DESCRIPTION:
XS GIS Cut Line= 3
      2757222.10      6835001.40      2757181.13      6835175.31
      2757035.76      6835715.52
#Sta/Elev= 30
  4827.7  479.27  4914.2  479.26  4917.2  479.45  4930.0  478.38  4940.3  478.65
  4950.6  477.81  4959.5  470.31  4964.7  467.39  4968.8  458.69  4969.1  458.19
  4973.1  458.19  4973.4  458.69  4981.4  464.88  4991.7  464.97  5001.6  465.84
  5022.6  465.58  5041.8  468.20  5048.3  468.40  5052.9  468.49  5074.4  469.10
  5095.1  468.24  5201.6  468.51  5269.3  469.78  5351.0  469.47  5356.2  468.98
  5425.8  470.05  5430.9  469.45  5470.9  470.01  5505.7  471.97  5565.8  472.75
#Mann=7,-1,0
  4827.7    0.05       0  4914.2    0.12       0  4968.8    0.07       0
  4973.4    0.12       0  5048.3    0.16       0  5052.9    0.07       0
  5269.3    0.05       0
Bank Sta=4968.8,4973.4
Exp/Cntr=0.3,0.1

Type RM Length L Ch R = 1,32202,113,113,113
BEGIN DESCRIPTION:
Purtis Creek32201.99
END DESCRIPTION:
XS GIS Cut Line= 3
      2757089.00      6835028.46      2757066.62      6835163.02
      2756983.22      6835696.94
#Sta/Elev= 30
  4865.7  478.64  4878.0  479.00  4914.2  476.02  4939.2  474.85  4959.5  470.68
  4969.6  469.80  4975.1  464.03  4980.1  463.39  4987.6  458.15  4987.9  457.65
  4992.2  458.15  4998.5  461.56  5002.1  461.56  5010.2  464.66  5020.3  464.85
  5042.1  467.27  5052.8  467.72  5070.9  467.52  5081.0  468.27  5104.8  467.57
  5151.5  467.89  5192.4  468.77  5273.3  469.09  5394.8  468.46  5428.8  469.30
  5465.6  468.72  5485.9  469.64  5491.5  470.58  5526.4  471.89  5542.5  471.74
#Mann=6,-1,0
  4865.7    0.05       0  4878.0    0.12       0  4987.6    0.07       0
  4992.2    0.12       0  5052.8    0.16       0  5151.5    0.05       0
Bank Sta=4987.6,4992.2
Exp/Cntr=0.3,0.1

Type RM Length L Ch R = 1,32089,137,137,137
BEGIN DESCRIPTION:
Purtis Creek32089.03
END DESCRIPTION:
XS GIS Cut Line= 3
      2756999.80      6834950.12      2756953.46      6835163.73
      2756870.35      6835687.09
#Sta/Elev= 30
  4784.0  474.93  4795.1  475.01  4823.1  476.66  4853.2  476.07  4866.8  475.26
  4912.4  469.87  4948.6  466.72  4958.9  464.22  4963.2  458.05  4963.5  457.55
  4967.5  457.55  4967.8  458.05  4970.6  461.51  4979.3  458.74  4989.6  463.58
  4998.6  464.57  5021.7  465.10  5040.3  467.68  5049.9  467.78  5060.6  468.04
  5070.7  467.59  5078.9  468.05  5101.1  466.83  5192.2  467.55  5232.7  466.68
  5270.7  467.36  5394.7  467.84  5496.0  470.68  5516.2  471.60  5532.5  471.69
#Mann=6,-1,0
  4784.0    0.05       0  4853.2    0.12       0  4912.4    0.16       0
  4963.2    0.07       0  4967.8    0.16       0  5049.9    0.05       0
Bank Sta=4963.2,4967.8
Exp/Cntr=0.3,0.1

Type RM Length L Ch R = 1,31952,133,133,133
BEGIN DESCRIPTION:
Purtis Creek31951.92
END DESCRIPTION:
XS GIS Cut Line= 3
      2756881.65      6834853.74      2756831.07      6835120.92
      2756736.51      6835626.02
#Sta/Elev= 30
  4730.2  475.23  4747.3  474.22  4778.3  472.46  4785.4  470.01  4790.5  471.84
  4792.4  471.60  4829.2  466.58  4837.7  466.11  4941.1  464.23  4981.8  465.07
  4992.0  464.68  5002.1  463.68  5004.9  462.42  5010.1  457.94  5010.4  457.44
  5014.4  457.44  5014.7  457.94  5022.6  459.32  5032.7  463.71  5052.4  462.63
  5063.2  463.63  5090.0  463.10  5103.9  464.43  5110.1  465.98  5115.2  466.41
  5167.8  466.10  5330.7  466.96  5441.0  468.88  5470.2  468.50  5516.0  469.56
#Mann=6,-1,0
  4730.2    0.05       0  4747.3    0.12       0  4792.4    0.16       0
  5010.1    0.07       0  5014.7    0.16       0  5090.0    0.05       0
Bank Sta=5010.1,5014.7
Exp/Cntr=0.3,0.1

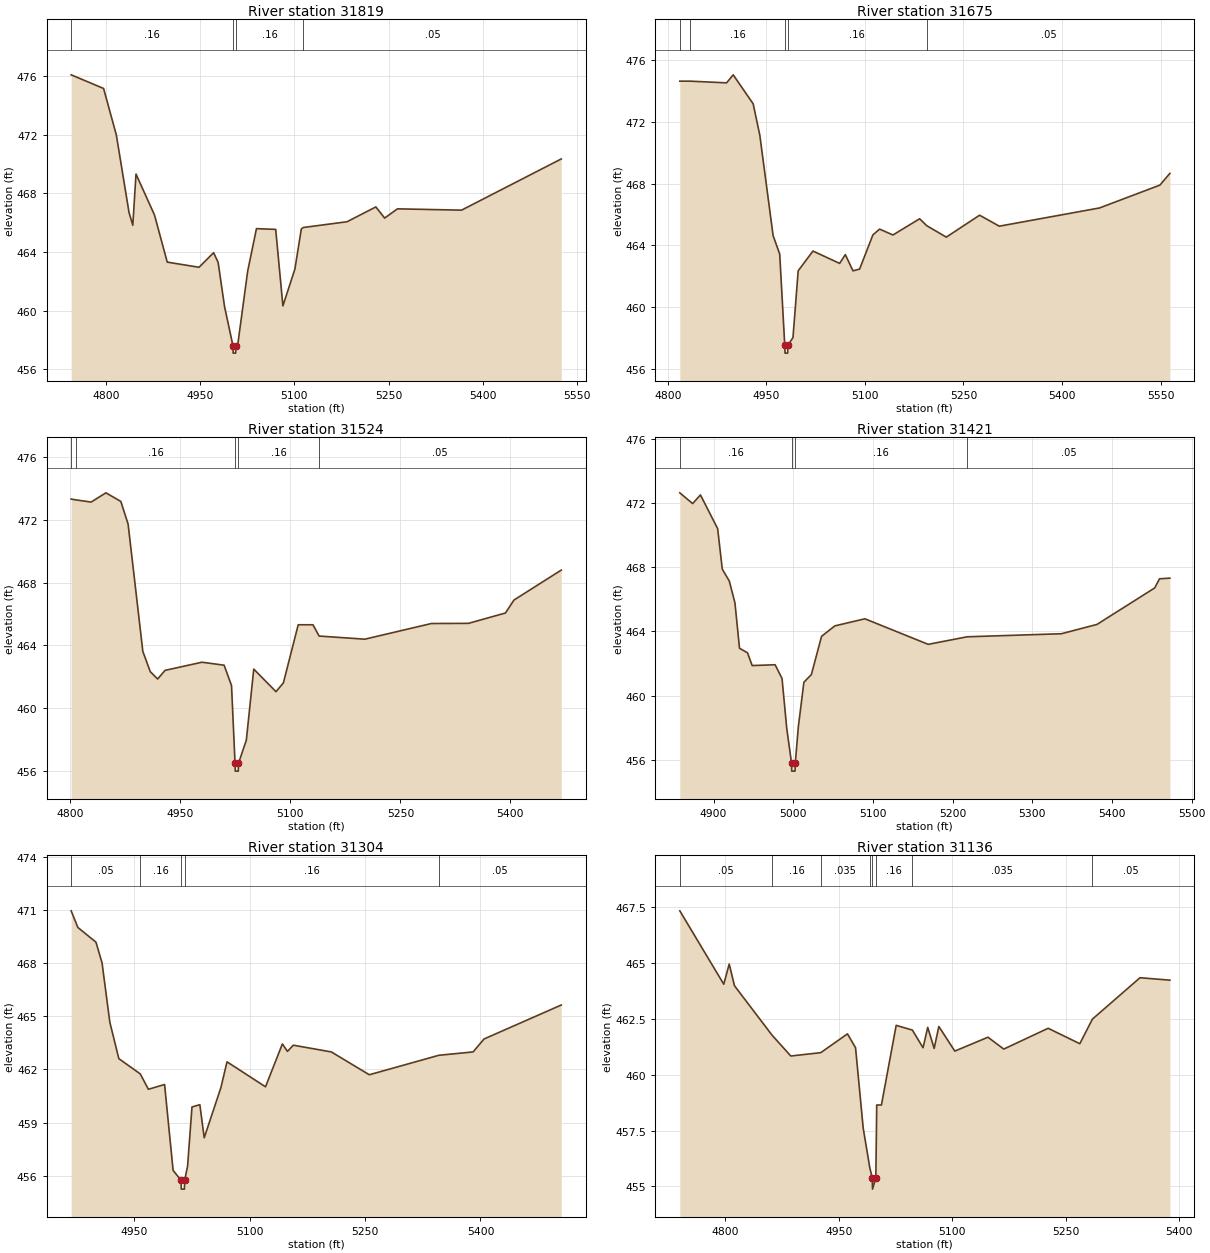
Type RM Length L Ch R = 1,31819,144,144,144
BEGIN DESCRIPTION:
Purtis Creek31819.49
END DESCRIPTION:
XS GIS Cut Line= 3
      2756746.80      6834840.06      2756705.29      6835097.08
      2756603.37      6835606.63
#Sta/Elev= 30
  4744.8  476.07  4796.4  475.14  4816.7  471.97  4836.9  466.69  4842.9  465.82
  4848.0  469.31  4877.4  466.52  4897.7  463.31  4948.3  462.96  4971.5  463.95
  4978.7  463.29  4988.9  460.28  5002.3  457.61  5002.6  457.11  5006.6  457.11
  5006.9  457.61  5009.7  457.61  5025.7  462.69  5039.7  465.59  5070.3  465.54
  5081.8  460.33  5100.9  462.84  5111.1  465.57  5114.4  465.67  5183.8  466.06
  5229.7  467.07  5243.7  466.31  5264.1  466.94  5366.1  466.85  5524.8  470.34
#Mann=4,-1,0
  4744.8    0.16       0  5002.3    0.07       0  5006.9    0.16       0
  5114.4    0.05       0
Bank Sta=5002.3,5006.9
Exp/Cntr=0.3,0.1

Type RM Length L Ch R = 1,31675,151,151,151
BEGIN DESCRIPTION:
Purtis Creek31674.65
END DESCRIPTION:
XS GIS Cut Line= 3
      2756639.77      6834830.51      2756613.32      6835011.72
      2756517.63      6835566.50
#Sta/Elev= 30
  4818.2  474.63  4833.9  474.63  4889.4  474.52  4899.5  475.04  4929.9  473.16
  4940.0  471.13  4960.2  464.64  4970.3  463.43  4978.0  457.52  4978.4  457.02
  4982.4  457.02  4982.7  457.52  4990.5  458.03  4998.4  462.35  5020.9  463.63
  5061.5  462.83  5070.2  463.40  5081.8  462.35  5091.9  462.46  5112.2  464.68
  5122.4  465.05  5142.7  464.67  5183.3  465.72  5194.2  465.27  5223.9  464.53
  5274.6  465.95  5304.6  465.24  5457.2  466.42  5549.1  467.90  5564.3  468.66
#Mann=5,-1,0
  4818.2    0.05       0  4833.9    0.16       0  4978.0    0.07       0
  4982.7    0.16       0  5194.2    0.05       0
Bank Sta=4978,4982.7
Exp/Cntr=0.3,0.1

Type RM Length L Ch R = 1,31524,103,103,103
BEGIN DESCRIPTION:
Purtis Creek31523.54
END DESCRIPTION:
XS GIS Cut Line= 3
      2756518.47      6834863.95      2756494.50      6835064.25
      2756431.89      6835526.39
#Sta/Elev= 30
  4801.2  473.33  4807.5  473.28  4828.4  473.14  4848.6  473.73  4868.9  473.18
  4878.8  471.74  4898.9  463.61  4909.0  462.32  4919.1  461.85  4929.2  462.40
  4979.5  462.92  5009.7  462.73  5019.8  461.43  5024.6  456.47  5024.9  455.97
  5029.0  455.97  5029.3  456.47  5040.0  457.95  5050.1  462.48  5080.4  461.04
  5090.5  461.60  5110.7  465.31  5130.8  465.31  5139.2  464.59  5201.5  464.39
  5292.3  465.39  5342.8  465.40  5393.2  466.06  5404.9  466.89  5469.3  468.80
#Mann=5,-1,0
  4801.2    0.05       0  4807.5    0.16       0  5024.6    0.07       0
  5029.3    0.16       0  5139.2    0.05       0
Bank Sta=5024.6,5029.3
Exp/Cntr=0.3,0.1

Type RM Length L Ch R = 1,31421,117,117,117
BEGIN DESCRIPTION:
Purtis Creek31421.27
END DESCRIPTION:
XS GIS Cut Line= 3
      2756485.81      6834877.02      2756412.14      6835006.83
      2756202.19      6835422.57
#Sta/Elev= 30
  4857.7  472.62  4873.8  471.95  4883.6  472.49  4905.2  470.39  4911.0  467.87
  4919.8  467.13  4926.9  465.77  4932.6  462.95  4942.7  462.66  4948.5  461.87
  4977.3  461.92  4986.0  461.06  4991.8  458.00  4997.9  455.80  4998.2  455.30
  5002.3  455.30  5002.6  455.80  5006.5  458.08  5013.4  460.83  5022.8  461.31
  5035.6  463.69  5052.3  464.34  5090.0  464.78  5169.4  463.19  5218.3  463.66
  5336.5  463.85  5381.2  464.43  5453.6  466.70  5459.7  467.27  5472.7  467.31
#Mann=4,-1,0
  4857.7    0.16       0  4997.9    0.07       0  5002.6    0.16       0
  5218.3    0.05       0
Bank Sta=4997.9,5002.6
Exp/Cntr=0.3,0.1

Type RM Length L Ch R = 1,31304,168,168,168
BEGIN DESCRIPTION:
Purtis Creek31303.61
END DESCRIPTION:
XS GIS Cut Line= 6
      2756442.79      6834854.17      2756364.78      6834888.01
      2756343.28      6834903.73      2756330.01      6834920.72
      2756284.90      6835000.81      2756014.07      6835310.42
#Sta/Elev= 30
  4868.4  470.96  4877.1  470.02  4900.6  469.19  4908.5  468.02  4918.6  464.67
  4930.3  462.61  4958.1  461.75  4968.7  460.88  4989.7  461.15  5000.8  456.30
  5011.1  455.74  5011.4  455.24  5015.5  455.24  5015.8  455.74  5019.6  456.54
  5025.3  459.88  5035.5  460.01  5041.2  458.14  5062.9  460.98  5070.8  462.43
  5120.8  461.02  5142.7  463.44  5149.3  463.02  5156.9  463.37  5206.3  462.99
  5255.6  461.70  5345.9  462.80  5390.4  462.99  5404.6  463.72  5504.9  465.64
#Mann=5,-1,0
  4868.4    0.05       0  4958.1    0.16       0  5011.1    0.07       0
  5015.8    0.16       0  5345.9    0.05       0
Bank Sta=5011.1,5015.8
Exp/Cntr=0.3,0.1

Type RM Length L Ch R = 1,31136,105,105,105
BEGIN DESCRIPTION:
Purtis Creek31135.83
END DESCRIPTION:
XS GIS Cut Line= 5
      2756350.39      6834763.16      2756245.81      6834871.05
      2756195.56      6834935.86      2756176.63      6834959.21
      2755949.94      6835270.99
#Sta/Elev= 30
  4739.9  467.32  4798.0  464.04  4805.2  464.94  4812.2  463.97  4861.9  461.76
  4886.6  460.83  4926.2  460.98  4961.5  461.82  4972.2  461.20  4982.3  457.61
  4991.0  455.84  4994.3  455.38  4994.6  454.88  4999.0  455.38  5000.2  458.64
  5006.4  458.64  5025.9  462.20  5047.3  461.99  5061.4  461.20  5067.6  462.11
  5076.1  461.17  5082.3  462.15  5103.4  461.05  5147.2  461.67  5168.1  461.14
  5226.8  462.07  5268.6  461.38  5285.3  462.48  5348.2  464.33  5387.7  464.22
#Mann=8,-1,0
  4739.9    0.05       0  4861.9    0.16       0  4926.2   0.035       0
  4991.0    0.16       0  4994.3    0.07       0  4999.0    0.16       0
  5047.3   0.035       0  5285.3    0.05       0
Bank Sta=4994.3,4999
Exp/Cntr=0.3,0.1

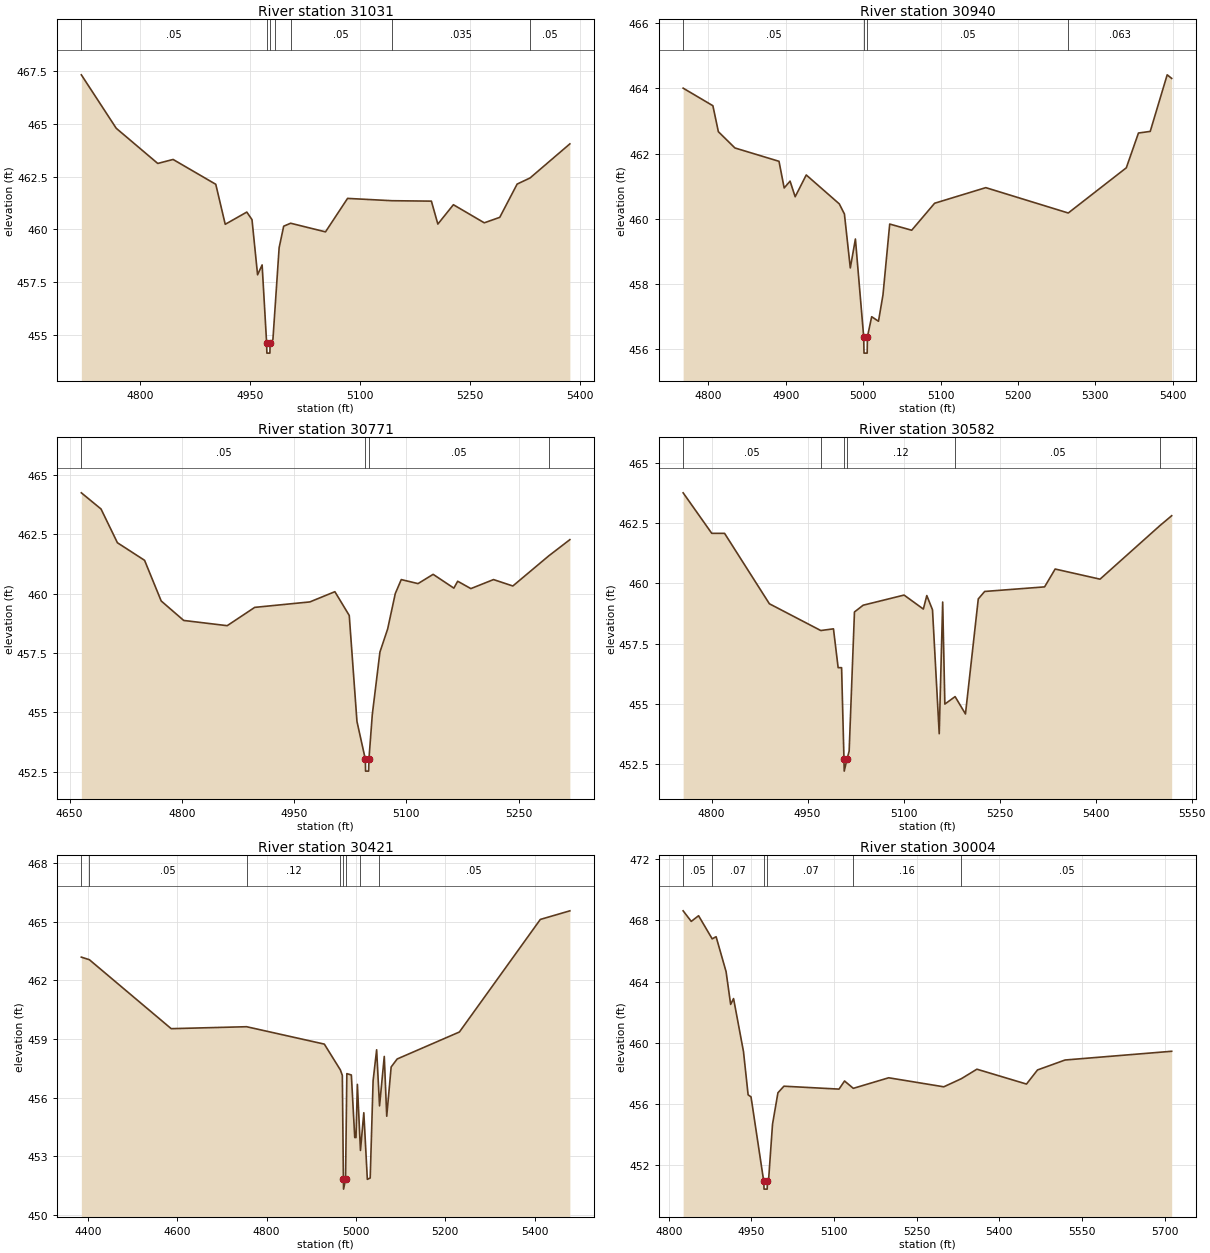
Type RM Length L Ch R = 1,31031,91,91,91
BEGIN DESCRIPTION:
Purtis Creek31030.68
END DESCRIPTION:
XS GIS Cut Line= 3
      2756252.64      6834682.41      2756087.81      6834910.51
      2755874.90      6835230.90
#Sta/Elev= 30
  4719.7  467.34  4767.3  464.80  4823.9  463.13  4844.8  463.32  4903.0  462.14
  4915.9  460.24  4945.3  460.82  4952.4  460.46  4960.0  457.84  4966.2  458.31
  4972.3  454.62  4972.7  454.12  4976.8  454.12  4977.1  454.62  4980.9  454.76
  4983.9  456.30  4989.4  459.13  4995.6  460.15  5005.1  460.29  5052.6  459.88
  5082.7  461.47  5143.1  461.36  5197.0  461.34  5205.8  460.25  5227.0  461.17
  5269.1  460.31  5290.2  460.57  5313.9  462.15  5331.5  462.44  5385.8  464.06
#Mann=7,-1,0
  4719.7    0.05       0  4972.3    0.07       0  4977.1    0.05       0
  4983.9    0.16       0  5005.1    0.05       0  5143.1   0.035       0
  5331.5    0.05       0
Bank Sta=4972.3,4977.1
Exp/Cntr=0.3,0.1

Type RM Length L Ch R = 1,30940,169,169,169
BEGIN DESCRIPTION:
Purtis Creek30939.11
END DESCRIPTION:
XS GIS Cut Line= 3
      2756165.99      6834686.77      2756010.87      6834864.26
      2755810.37      6835204.91
#Sta/Elev= 30
  4767.5  464.01  4805.9  463.47  4813.0  462.67  4834.4  462.17  4891.3  461.76
  4898.0  460.94  4905.6  461.15  4912.2  460.67  4926.5  461.34  4969.2  460.45
  4975.8  460.14  4983.4  458.48  4990.0  459.37  5000.7  456.36  5001.1  455.86
  5005.2  455.86  5005.5  456.36  5011.0  456.98  5019.8  456.84  5025.6  457.65
  5034.3  459.83  5062.7  459.64  5092.3  460.47  5158.4  460.95  5264.9  460.17
  5339.9  461.56  5355.6  462.63  5370.8  462.68  5392.7  464.42  5398.5  464.31
#Mann=4,-1,0
  4767.5    0.05       0  5000.7    0.05       0  5005.5    0.05       0
  5264.9   0.063       0
Bank Sta=5000.7,5005.5
Exp/Cntr=0.3,0.1

Type RM Length L Ch R = 1,30771,189,189,189
BEGIN DESCRIPTION:
Purtis Creek30770.81
END DESCRIPTION:
XS GIS Cut Line= 4
      2756137.19      6834664.56      2755851.03      6834838.37
      2755830.47      6834928.79      2755801.17      6835152.14
#Sta/Elev= 30
  4665.7  464.24  4692.0  463.56  4713.9  462.14  4750.2  461.40  4772.4  459.69
  4802.5  458.87  4860.6  458.65  4897.4  459.42  4971.1  459.65  5004.5  460.08
  5023.7  459.08  5034.0  454.62  5045.2  453.03  5045.5  452.53  5049.6  452.53
  5050.0  453.03  5054.5  454.91  5064.7  457.54  5075.0  458.51  5085.2  460.00
  5093.2  460.59  5115.6  460.42  5135.8  460.81  5163.5  460.23  5168.6  460.52
  5186.2  460.21  5216.5  460.59  5242.3  460.32  5290.0  461.58  5318.5  462.27
#Mann=4,-1,0
  4665.7    0.05       0  5045.2    0.05       0  5050.0    0.05       0
  5290.0   0.063       0
Bank Sta=5045.2,5050
Exp/Cntr=0.3,0.1

Type RM Length L Ch R = 1,30582,161,161,161
BEGIN DESCRIPTION:
Purtis Creek30582.4
END DESCRIPTION:
XS GIS Cut Line= 6
      2756120.67      6834663.08      2755876.24      6834670.13
      2755828.77      6834696.04      2755788.54      6834802.22
      2755777.83      6835016.27      2755782.78      6835152.81
#Sta/Elev= 30
  4755.7  463.75  4800.4  462.07  4820.4  462.07  4890.4  459.15  4970.7  458.04
  4990.5  458.11  4997.8  456.50  5003.2  456.50  5006.9  452.71  5007.3  452.21
  5011.7  452.71  5015.0  453.04  5023.3  458.81  5036.9  459.09  5100.8  459.51
  5130.9  458.93  5136.3  459.49  5145.2  458.90  5155.7  453.76  5161.1  459.22
  5164.5  454.99  5180.5  455.30  5196.7  454.58  5216.7  459.35  5226.7  459.66
  5320.3  459.85  5336.8  460.59  5406.9  460.17  5500.4  462.39  5518.8  462.80
#Mann=6,-1,0
  4755.7    0.05       0  4970.7    0.12       0  5006.9    0.07       0
  5011.7    0.12       0  5180.5    0.05       0  5500.4   0.063       0
Bank Sta=5006.9,5011.7
Exp/Cntr=0.3,0.1

Type RM Length L Ch R = 1,30421,417,417,417
BEGIN DESCRIPTION:
Purtis Creek30421.306
END DESCRIPTION:
XS GIS Cut Line= 5
      2755739.57      6835172.19      2755738.53      6834961.48
      2755790.81      6834560.89      2755828.73      6834514.26
      2756212.57      6834682.05
#Sta/Elev= 30
  4385.3  463.19  4403.2  463.06  4586.5  459.53  4755.3  459.63  4929.3  458.74
  4965.2  457.42  4969.6  457.14  4972.0  451.82  4972.4  451.32  4976.8  451.82
  4979.7  457.23  4989.8  457.16  4997.4  453.96  5000.2  453.96  5003.3  456.68
  5010.2  453.30  5017.7  455.23  5025.6  451.82  5032.0  451.89  5038.5  456.87
  5046.4  458.45  5051.1  456.37  5052.9  455.58  5063.5  458.11  5069.0  455.05
  5078.9  457.57  5092.4  457.98  5231.7  459.36  5412.9  465.12  5479.0  465.56
#Mann=8,-1,0
  4385.3   0.063       0  4403.2    0.05       0  4755.3    0.12       0
  4965.2    0.16       0  4972.0    0.07       0  4976.8    0.16       0
  5010.2    0.12       0  5051.1    0.05       0
Bank Sta=4972,4976.8
Exp/Cntr=0.3,0.1

Type RM Length L Ch R = 1,30004,132,132,132
BEGIN DESCRIPTION:
Purtis Creek30003.85
END DESCRIPTION:
XS GIS Cut Line= 3
      2755612.97      6834097.04      2755668.40      6834264.62
      2755690.84      6834974.36
#Sta/Elev= 30
  4826.0  468.62  4840.7  467.93  4854.0  468.30  4878.7  466.79  4885.8  466.93
  4903.9  464.65  4912.2  462.51  4917.5  462.89  4935.5  459.43  4943.9  456.61
  4949.2  456.47  4972.3  450.95  4972.8  450.45  4978.5  450.45  4979.0  450.95
  4980.9  450.97  4988.2  454.69  4998.0  456.74  5008.9  457.17  5108.9  456.98
  5118.9  457.51  5134.8  457.03  5199.0  457.72  5299.0  457.13  5330.9  457.66
  5359.1  458.28  5449.1  457.31  5469.1  458.23  5519.1  458.88  5712.6  459.45
#Mann=6,-1,0
  4826.0    0.05       0  4878.7    0.07       0  4972.3    0.07       0
  4979.0    0.07       0  5134.8    0.16       0  5330.9    0.05       0
Bank Sta=4972.3,4979
Exp/Cntr=0.3,0.1

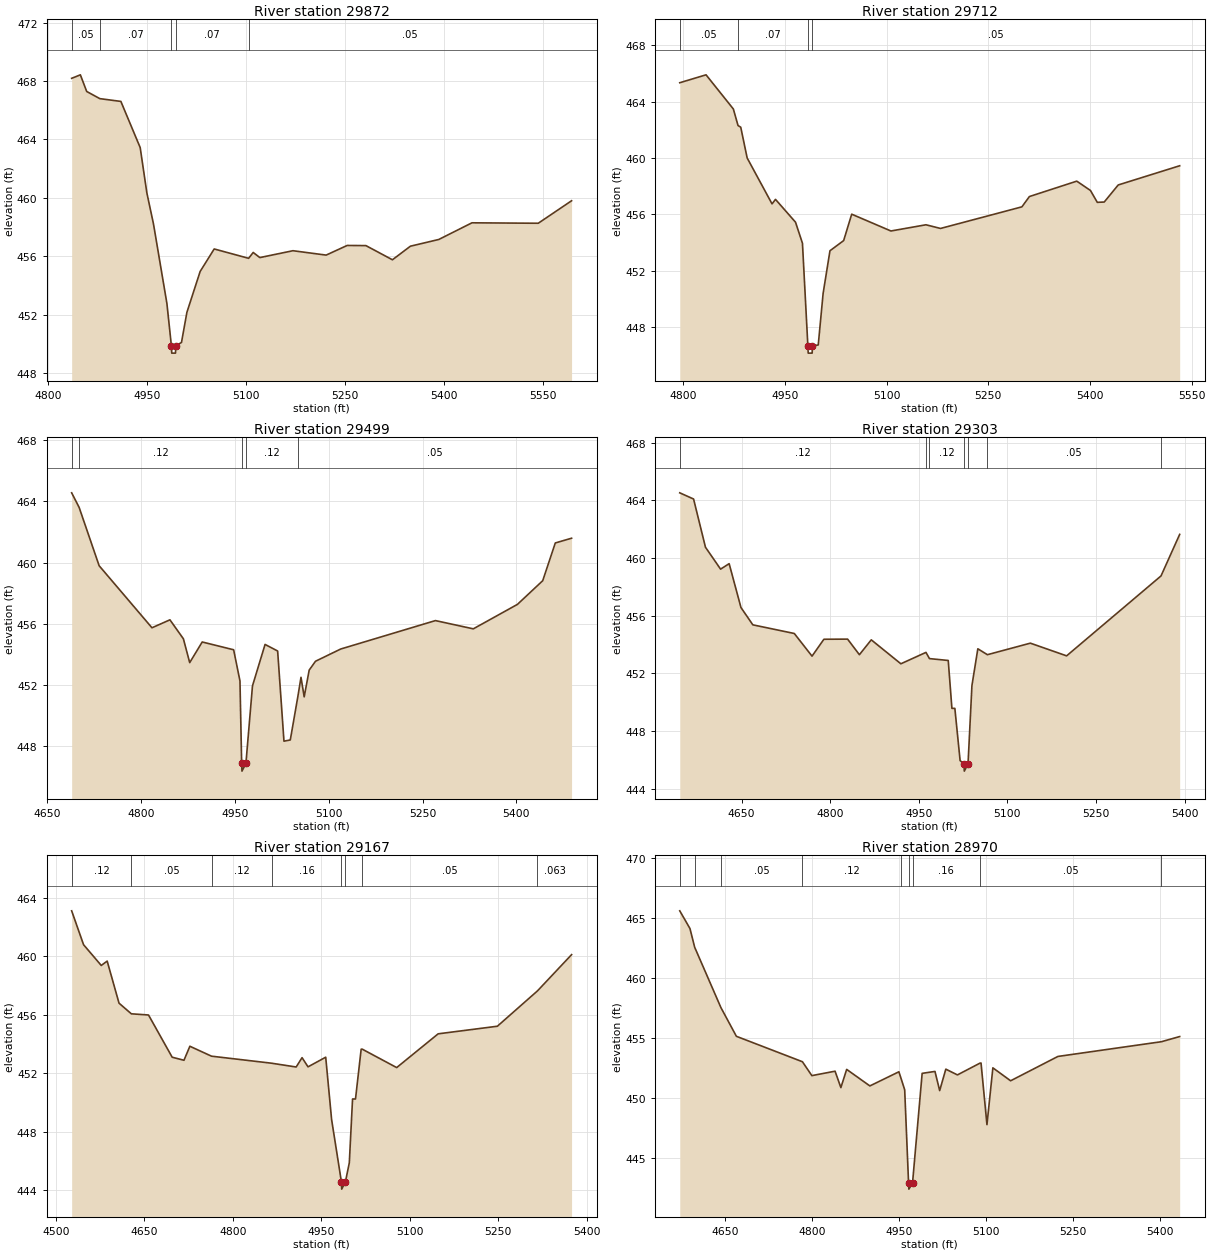
Type RM Length L Ch R = 1,29872,160,160,160
BEGIN DESCRIPTION:
Purtis Creek29872.29
END DESCRIPTION:
XS GIS Cut Line= 3
      2755519.61      6834128.48      2755546.49      6834292.83
      2755604.93      6834881.30
#Sta/Elev= 30
  4836.1  468.18  4849.3  468.42  4858.9  467.28  4878.8  466.79  4910.7  466.60
  4940.0  463.44  4950.1  460.34  4960.2  458.20  4980.5  452.77  4987.3  449.87
  4987.8  449.37  4993.5  449.37  4994.0  449.87  5002.6  450.10  5010.8  452.16
  5030.9  454.96  5052.2  456.50  5104.4  455.86  5111.3  456.26  5121.4  455.91
  5171.6  456.38  5221.9  456.08  5253.8  456.74  5282.2  456.73  5322.4  455.76
  5349.7  456.69  5392.7  457.15  5443.0  458.29  5543.5  458.26  5594.0  459.80
#Mann=5,-1,0
  4836.1    0.05       0  4878.8    0.07       0  4987.3    0.07       0
  4994.0    0.07       0  5104.4    0.05       0
Bank Sta=4987.3,4994
Exp/Cntr=0.3,0.1

Type RM Length L Ch R = 1,29712,213,213,213
BEGIN DESCRIPTION:
Purtis Creek29711.89
END DESCRIPTION:
XS GIS Cut Line= 3
      2755394.37      6834203.38      2755433.64      6834401.79
      2755515.57      6834931.13
#Sta/Elev= 30
  4794.5  465.33  4833.3  465.89  4873.6  463.47  4880.5  462.30  4884.5  462.18
  4894.0  460.00  4930.7  456.75  4935.8  457.07  4965.4  455.45  4975.6  453.96
  4983.6  446.68  4984.1  446.18  4989.9  446.18  4990.4  446.68  4998.9  446.76
  5006.1  450.41  5016.2  453.43  5036.4  454.15  5048.3  456.02  5106.2  454.83
  5157.9  455.27  5179.4  455.01  5299.5  456.54  5310.6  457.27  5380.5  458.36
  5400.7  457.70  5410.8  456.86  5421.0  456.88  5441.7  458.09  5532.4  459.45
#Mann=4,-1,0
  4794.5    0.05       0  4880.5    0.07       0  4983.6    0.05       0
  4990.4    0.05       0
Bank Sta=4983.6,4990.4
Exp/Cntr=0.3,0.1

Type RM Length L Ch R = 1,29499,196,196,196
BEGIN DESCRIPTION:
Purtis Creek29498.67
END DESCRIPTION:
XS GIS Cut Line= 3
      2755287.12      6834263.16      2755314.68      6834580.75
      2755375.73      6835056.76
#Sta/Elev= 30
  4689.4  464.56  4701.3  463.61  4733.3  459.79  4817.7  455.73  4846.4  456.25
  4867.9  455.01  4878.0  453.45  4898.0  454.80  4948.2  454.29  4958.3  452.25
  4961.0  446.85  4961.5  446.35  4967.8  446.85  4978.3  451.93  4998.4  454.64
  5018.5  454.21  5028.6  448.31  5038.7  448.39  5050.8  451.23  5055.8  452.49
  5060.9  451.21  5068.9  452.96  5079.0  453.54  5119.3  454.34  5270.6  456.20
  5331.1  455.66  5401.6  457.26  5442.0  458.81  5462.1  461.28  5488.1  461.59
#Mann=5,-1,0
  4689.4    0.05       0  4701.3    0.12       0  4961.0    0.07       0
  4967.8    0.12       0  5050.8    0.05       0
Bank Sta=4961,4967.8
Exp/Cntr=0.3,0.1

Type RM Length L Ch R = 1,29303,136,136,136
BEGIN DESCRIPTION:
Purtis Creek29303.04
END DESCRIPTION:
XS GIS Cut Line= 3
      2755166.03      6834257.63      2755198.94      6834718.22
      2755176.40      6835102.09
#Sta/Elev= 30
  4545.3  464.52  4568.7  464.09  4588.8  460.75  4614.4  459.23  4628.9  459.61
  4648.9  456.57  4669.0  455.37  4739.2  454.77  4769.2  453.20  4789.3  454.37
  4829.4  454.38  4849.4  453.30  4869.5  454.33  4919.6  452.67  4962.1  453.46
  4968.0  453.03  4999.8  452.90  5006.0  449.58  5011.0  449.58  5019.9  445.96
  5026.5  445.73  5027.0  445.23  5033.3  445.73  5039.9  451.16  5049.9  453.71
  5066.1  453.30  5138.8  454.10  5200.2  453.22  5360.0  458.76  5391.6  461.64
#Mann=7,-1,0
  4545.3    0.12       0  4962.1    0.16       0  4968.0    0.12       0
  5026.5    0.07       0  5033.3    0.12       0  5066.1    0.05       0
  5360.0   0.063       0
Bank Sta=5026.5,5033.3
Exp/Cntr=0.3,0.1

Type RM Length L Ch R = 1,29167,197,197,197
BEGIN DESCRIPTION:
Purtis Creek29167.17
END DESCRIPTION:
XS GIS Cut Line= 3
      2755053.06      6834280.84      2755076.78      6834756.81
      2755109.67      6835126.29
#Sta/Elev= 30
  4526.7  463.11  4546.9  460.79  4576.9  459.37  4586.9  459.67  4607.0  456.79
  4627.9  456.06  4657.0  455.98  4697.1  453.09  4717.1  452.88  4727.1  453.84
  4763.8  453.16  4865.5  452.68  4907.3  452.42  4917.3  453.06  4927.4  452.43
  4957.4  453.09  4967.4  448.82  4984.0  444.56  4984.5  444.06  4990.8  444.56
  4997.4  445.86  5002.9  450.23  5007.9  450.23  5017.5  453.64  5019.4  453.64
  5077.7  452.38  5148.0  454.69  5248.4  455.21  5316.4  457.63  5374.2  460.11
#Mann=8,-1,0
  4526.7    0.12       0  4627.9    0.05       0  4763.8    0.12       0
  4865.5    0.16       0  4984.0    0.07       0  4990.8    0.16       0
  5019.4    0.05       0  5316.4   0.063       0
Bank Sta=4984,4990.8
Exp/Cntr=0.3,0.1

Type RM Length L Ch R = 1,28970,189,189,189
BEGIN DESCRIPTION:
Purtis Creek28970.1
END DESCRIPTION:
XS GIS Cut Line= 3
      2754904.08      6834243.44      2754917.74      6834680.22
      2754999.98      6835096.89
#Sta/Elev= 30
  4572.4  465.62  4590.0  464.14  4598.1  462.58  4643.3  457.55  4670.0  455.15
  4783.8  453.03  4800.1  451.87  4840.1  452.24  4850.1  450.87  4860.1  452.39
  4900.1  451.01  4950.1  452.19  4954.2  451.58  4960.1  450.69  4966.8  442.90
  4967.3  442.40  4973.6  442.90  4990.2  452.06  5012.3  452.22  5020.4  450.62
  5031.0  452.41  5051.0  451.93  5089.8  452.91  5091.7  452.92  5101.9  447.78
  5112.1  452.52  5142.7  451.44  5224.2  453.47  5402.7  454.70  5434.1  455.13
#Mann=9,-1,0
  4572.4    0.05       0  4598.1    0.12       0  4643.3    0.05       0
  4783.8    0.12       0  4954.2    0.16       0  4966.8    0.07       0
  4973.6    0.16       0  5089.8    0.05       0  5402.7   0.063       0
Bank Sta=4966.8,4973.6
Exp/Cntr=0.3,0.1

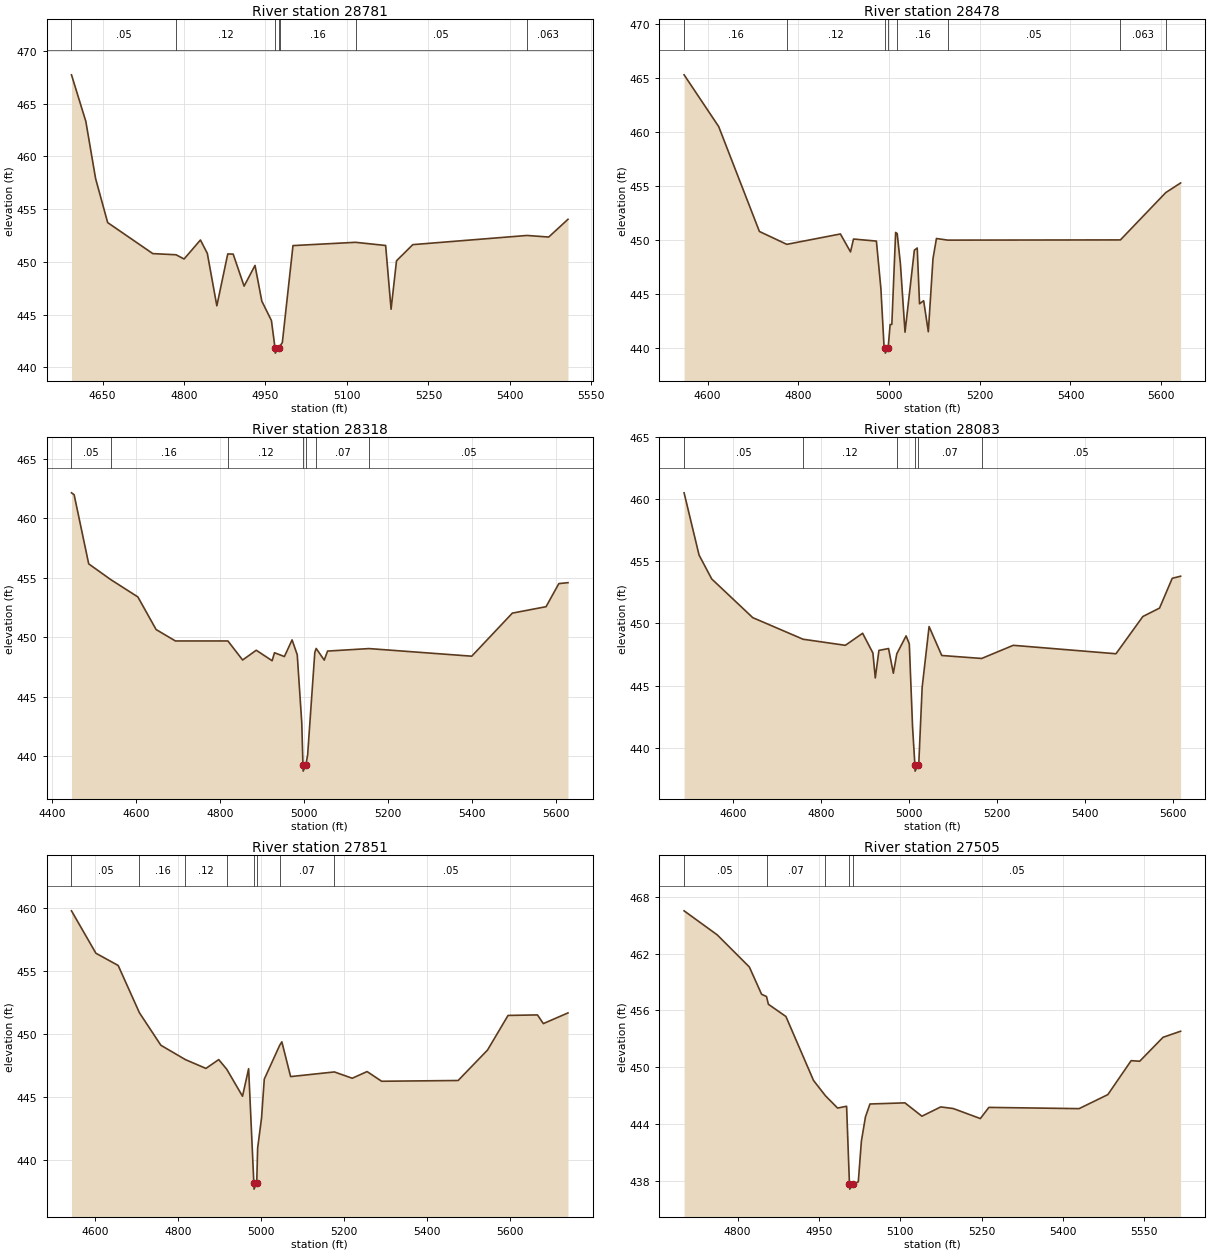
Type RM Length L Ch R = 1,28781,303,303,303
BEGIN DESCRIPTION:
Purtis Creek28781.37
END DESCRIPTION:
XS GIS Cut Line= 3
      2754835.72      6834224.76      2754794.54      6834635.09
      2754776.88      6835136.49
#Sta/Elev= 30
  4592.9  467.73  4619.3  463.32  4637.3  457.90  4659.5  453.73  4742.6  450.79
  4785.4  450.68  4800.2  450.28  4830.3  452.08  4843.0  450.81  4860.5  445.84
  4880.6  450.76  4890.6  450.74  4910.7  447.71  4930.8  449.67  4943.3  446.29
  4961.0  444.45  4967.6  441.86  4968.1  441.36  4974.4  441.86  4977.5  442.09
  4981.1  442.36  5000.7  451.55  5115.8  451.86  5171.3  451.56  5181.3  445.52
  5191.3  450.11  5221.3  451.64  5431.5  452.51  5471.5  452.36  5507.0  454.04
#Mann=7,-1,0
  4592.9    0.05       0  4785.4    0.12       0  4967.6    0.07       0
  4974.4    0.12       0  4977.5    0.16       0  5115.8    0.05       0
  5431.5   0.063       0
Bank Sta=4967.6,4974.4
Exp/Cntr=0.3,0.1

Type RM Length L Ch R = 1,28478,160,160,160
BEGIN DESCRIPTION:
Purtis Creek28478.46
END DESCRIPTION:
XS GIS Cut Line= 3
      2754776.89      6834151.89      2754574.06      6834562.64
      2754428.61      6835182.61
#Sta/Elev= 30
  4548.0  465.27  4624.3  460.48  4714.1  450.77  4774.5  449.58  4892.7  450.54
  4915.0  448.88  4921.6  450.07  4972.1  449.88  4982.0  445.48  4989.0  440.06
  4991.2  440.01  4991.7  439.51  4998.0  440.01  5002.4  442.16  5006.1  442.16
  5014.5  450.68  5017.9  450.58  5025.0  447.80  5035.2  441.45  5055.8  449.04
  5062.1  449.24  5067.2  444.08  5076.3  444.36  5086.6  441.49  5096.9  448.26
  5104.5  450.12  5129.4  449.97  5510.2  449.99  5610.2  454.37  5642.9  455.26
#Mann=8,-1,0
  4548.0    0.16       0  4774.5    0.12       0  4991.2    0.07       0
  4998.0    0.12       0  5017.9    0.16       0  5129.4    0.05       0
  5510.2   0.063       0  5610.2    0.05       0
Bank Sta=4991.2,4998
Exp/Cntr=0.3,0.1

Type RM Length L Ch R = 1,28318,235,235,235
BEGIN DESCRIPTION:
Purtis Creek28318.03
END DESCRIPTION:
XS GIS Cut Line= 3
      2754675.58      6833935.19      2754459.20      6834451.61
      2754242.99      6835035.23
#Sta/Elev= 30
  4446.1  462.12  4452.4  461.96  4487.1  456.15  4539.5  454.83  4604.2  453.37
  4647.6  450.63  4693.6  449.67  4818.6  449.67  4853.6  448.07  4886.1  448.89
  4923.9  448.01  4929.5  448.68  4953.1  448.36  4971.4  449.76  4983.7  448.51
  4994.5  442.77  4997.3  439.23  4997.8  438.73  5004.1  439.23  5008.4  440.08
  5025.5  448.70  5028.8  449.04  5048.0  448.06  5055.9  448.82  5154.5  449.03
  5399.2  448.39  5495.9  452.01  5576.2  452.55  5606.6  454.49  5628.4  454.57
#Mann=7,-1,0
  4446.1    0.05       0  4539.5    0.16       0  4818.6    0.12       0
  4997.3    0.07       0  5004.1    0.12       0  5028.8    0.07       0
  5154.5    0.05       0
Bank Sta=4997.3,5004.1
Exp/Cntr=0.3,0.1

Type RM Length L Ch R = 1,28083,232,232,232
BEGIN DESCRIPTION:
Purtis Creek28082.56
END DESCRIPTION:
XS GIS Cut Line= 3
      2754514.79      6833825.19      2754308.72      6834294.27
      2754061.76      6834859.75
#Sta/Elev= 30
  4488.1  460.53  4522.1  455.52  4550.9  453.59  4644.3  450.47  4758.8  448.73
  4854.9  448.24  4894.2  449.21  4917.6  447.62  4923.0  445.61  4931.3  447.83
  4953.2  447.98  4964.1  445.99  4971.9  447.55  4993.1  449.00  5000.4  448.35
  5007.8  441.67  5013.1  438.60  5013.6  438.10  5019.9  438.60  5021.9  438.66
  5029.6  444.84  5045.4  449.75  5074.2  447.42  5165.0  447.18  5236.9  448.24
  5470.5  447.56  5531.6  450.56  5569.6  451.24  5598.5  453.64  5617.5  453.81
#Mann=6,-1,0
  4488.1    0.05       0  4758.8    0.12       0  4971.9    0.07       0
  5013.1    0.07       0  5019.9    0.07       0  5165.0    0.05       0
Bank Sta=5013.1,5019.9
Exp/Cntr=0.3,0.1

Type RM Length L Ch R = 1,27851,346,346,346
BEGIN DESCRIPTION:
Purtis Creek27850.96
END DESCRIPTION:
XS GIS Cut Line= 3
      2754367.92      6833731.59      2754140.61      6834138.23
      2753640.43      6834669.31
#Sta/Elev= 30
  4543.5  459.76  4602.3  456.39  4655.9  455.42  4707.1  451.66  4758.7  449.08
  4817.8  447.94  4867.2  447.24  4898.0  447.94  4917.2  447.18  4955.3  445.03
  4970.0  447.22  4982.5  438.15  4983.0  437.65  4989.5  438.15  4991.7  440.91
  5001.1  443.31  5007.7  446.39  5044.8  449.08  5050.0  449.35  5071.1  446.59
  5176.4  446.96  5219.5  446.46  5255.2  446.99  5290.3  446.22  5474.4  446.28
  5545.2  448.70  5594.6  451.45  5665.4  451.49  5679.6  450.80  5738.9  451.65
#Mann=8,-1,0
  4543.5    0.05       0  4707.1    0.16       0  4817.8    0.12       0
  4917.2    0.16       0  4982.5    0.07       0  4989.5    0.16       0
  5044.8    0.07       0  5176.4    0.05       0
Bank Sta=4982.5,4989.5
Exp/Cntr=0.3,0.1

Type RM Length L Ch R = 1,27505,300,300,300
BEGIN DESCRIPTION:
Purtis Creek27504.77
END DESCRIPTION:
XS GIS Cut Line= 3
      2754049.95      6833633.85      2753908.07      6833910.92
      2753604.45      6834433.54
#Sta/Elev= 30
  4701.4  466.52  4762.5  463.98  4821.8  460.58  4844.3  457.70  4853.4  457.46
  4856.9  456.64  4889.2  455.35  4940.1  448.59  4962.1  446.97  4984.5  445.67
  5001.1  445.86  5006.4  437.60  5006.9  437.10  5013.4  437.60  5022.7  437.88
  5028.4  442.18  5035.9  444.74  5044.2  446.10  5108.7  446.22  5140.0  444.81
  5174.7  445.79  5197.8  445.62  5247.8  444.56  5263.5  445.74  5429.9  445.61
  5482.9  447.09  5525.9  450.68  5541.7  450.62  5584.7  453.15  5617.1  453.79
#Mann=5,-1,0
  4701.4    0.05       0  4853.4    0.07       0  4962.1    0.05       0
  5006.4    0.05       0  5013.4    0.05       0
Bank Sta=5006.4,5013.4
Exp/Cntr=0.3,0.1