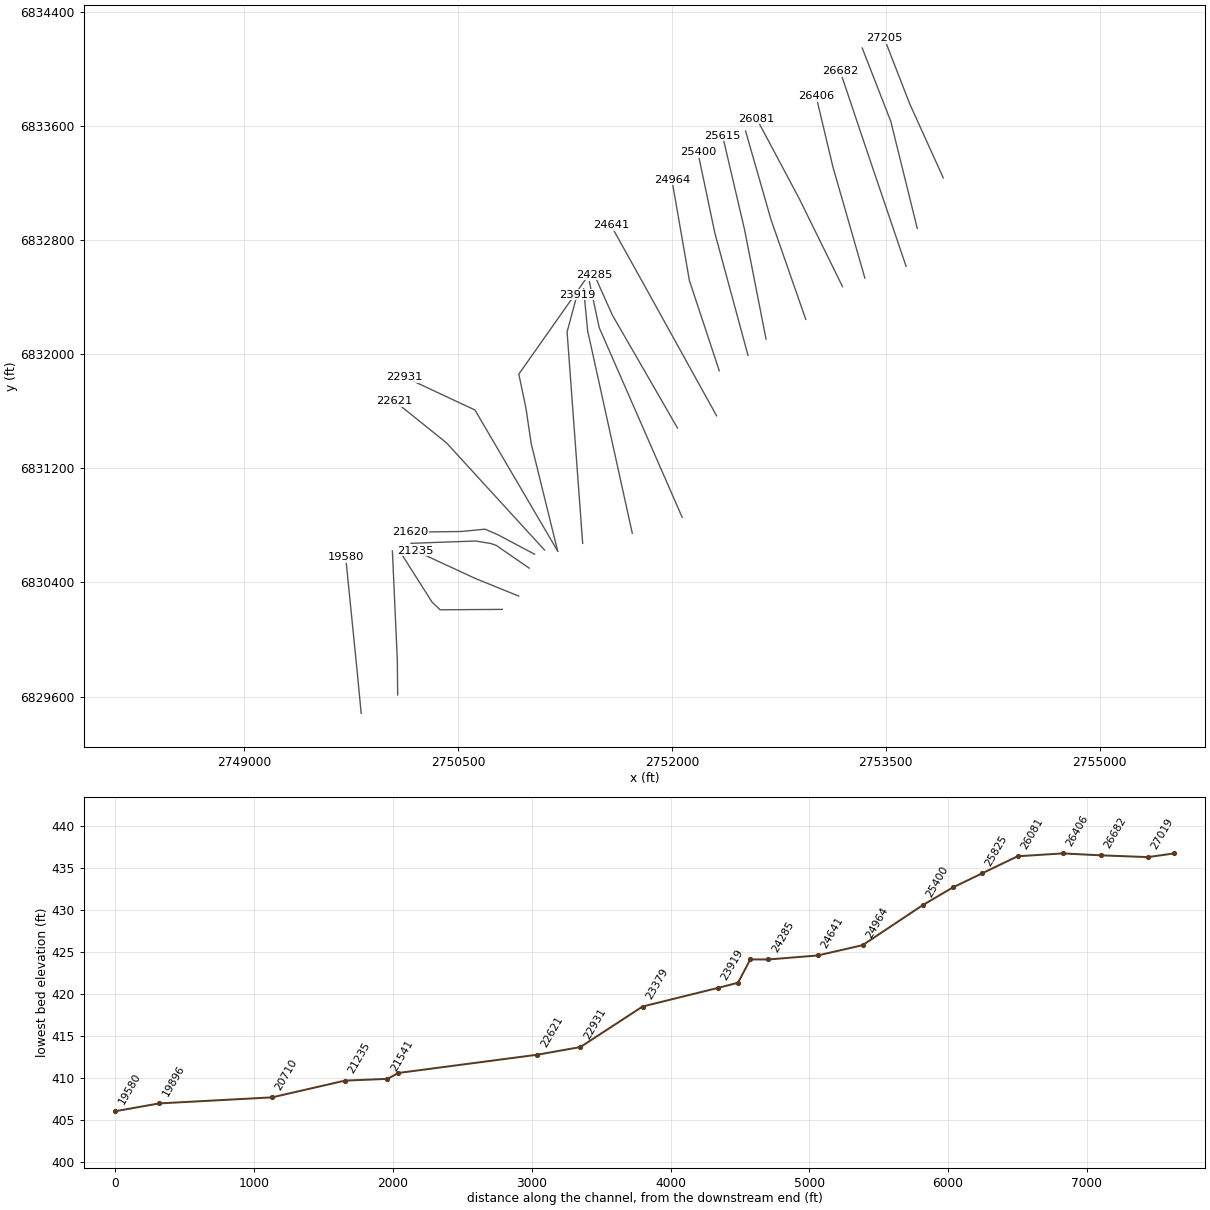
HEC-RAS study Purtis Creek.prj: Purtis Creek Base Level Engineering

--- Purtis Creek.g01 (geometry) --- (continued)

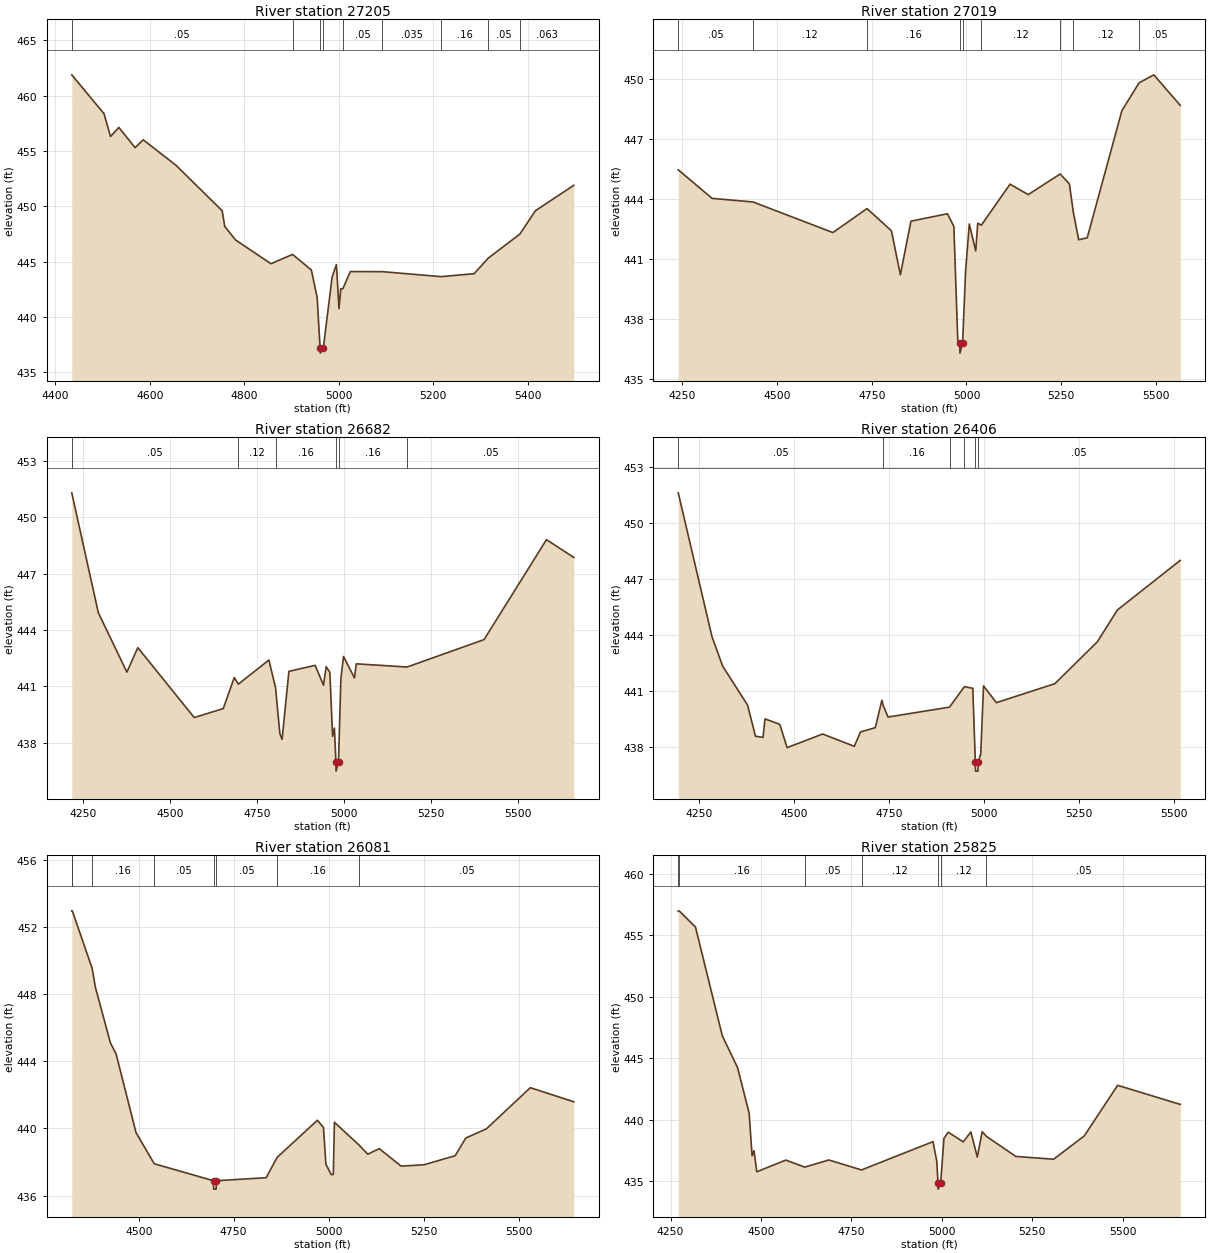
Type RM Length L Ch R = 1,27205,186,186,186
BEGIN DESCRIPTION:
Purtis Creek27204.55
END DESCRIPTION:
XS GIS Cut Line= 3
      2753903.78      6833238.86      2753667.81      6833759.63
      2753489.82      6834217.73
#Sta/Elev= 30
  4434.9  461.89  4503.1  458.38  4517.0  456.31  4534.6  457.13  4569.0  455.30
  4586.2  456.01  4655.5  453.71  4753.4  449.59  4758.9  448.17  4782.0  446.94
  4856.7  444.80  4902.5  445.64  4942.3  444.23  4954.6  441.73  4960.7  437.21
  4961.2  436.71  4967.7  437.21  4986.2  443.58  4995.3  444.72  5000.8  440.74
  5004.6  442.53  5008.8  442.53  5024.8  444.09  5092.7  444.08  5217.0  443.63
  5287.0  443.90  5316.7  445.30  5383.8  447.48  5416.6  449.59  5498.1  451.90
#Mann=9,-1,0
  4434.9    0.05       0  4902.5    0.07       0  4960.7    0.07       0
  4967.7    0.07       0  5008.8    0.05       0  5092.7   0.035       0
  5217.0    0.16       0  5316.7    0.05       0  5383.8   0.063       0
Bank Sta=4960.7,4967.7
Exp/Cntr=0.3,0.1

Type RM Length L Ch R = 1,27019,337,337,337
BEGIN DESCRIPTION:
Purtis Creek27019
END DESCRIPTION:
XS GIS Cut Line= 3
      2753721.33      6832884.61      2753535.63      6833635.20
      2753335.09      6834149.89
#Sta/Elev= 30
  4239.0  445.45  4328.4  444.02  4436.6  443.84  4647.3  442.31  4737.4  443.51
  4801.9  442.40  4825.5  440.20  4853.4  442.88  4949.7  443.25  4966.7  442.62
  4977.0  436.95  4982.3  436.78  4982.8  436.28  4989.8  436.78  4997.6  440.36
  5007.5  442.74  5024.4  441.39  5029.8  442.78  5039.3  442.68  5115.0  444.73
  5163.0  444.21  5247.5  445.24  5271.8  444.74  5282.3  443.31  5296.3  441.95
  5318.9  442.05  5410.4  448.41  5455.8  449.80  5494.6  450.20  5564.6  448.67
#Mann=9,-1,0
  4239.0    0.05       0  4436.6    0.12       0  4737.4    0.16       0
  4982.3    0.07       0  4989.8    0.16       0  5039.3    0.12       0
  5247.5    0.16       0  5282.3    0.12       0  5455.8    0.05       0
Bank Sta=4982.3,4989.8
Exp/Cntr=0.3,0.1

Type RM Length L Ch R = 1,26682,276,276,276
BEGIN DESCRIPTION:
Purtis Creek26681.58
END DESCRIPTION:
XS GIS Cut Line= 3
      2753642.86      6832618.72      2753389.71      6833364.16
      2753180.85      6833985.54
#Sta/Elev= 30
  4217.2  451.30  4293.5  444.92  4375.6  441.76  4407.0  443.06  4569.2  439.34
  4652.6  439.82  4684.2  441.47  4695.9  441.12  4783.7  442.40  4802.9  440.92
  4815.1  438.49  4821.6  438.18  4841.2  441.80  4916.6  442.12  4940.6  441.06
  4948.3  442.05  4958.9  441.74  4966.7  438.34  4972.0  438.78  4976.2  436.99
  4976.7  436.49  4983.7  436.99  4990.6  441.42  4998.1  442.59  5029.6  441.45
  5034.9  442.20  5180.8  442.03  5402.0  443.49  5581.4  448.81  5660.0  447.86
#Mann=6,-1,0
  4217.2    0.05       0  4695.9    0.12       0  4802.9    0.16       0
  4976.2    0.07       0  4983.7    0.16       0  5180.8    0.05       0
Bank Sta=4976.2,4983.7
Exp/Cntr=0.3,0.1

Type RM Length L Ch R = 1,26406,325,325,325
BEGIN DESCRIPTION:
Purtis Creek26405.9
END DESCRIPTION:
XS GIS Cut Line= 3
      2753353.93      6832535.50      2753129.30      6833316.29
      2753011.50      6833812.23
#Sta/Elev= 30
  4195.3  451.64  4284.3  443.92  4312.3  442.35  4377.9  440.26  4398.7  438.59
  4418.6  438.53  4423.8  439.52  4462.7  439.23  4482.0  437.98  4575.6  438.71
  4658.9  438.05  4675.3  438.82  4714.2  439.05  4731.7  440.52  4735.4  440.22
  4747.9  439.62  4909.7  440.15  4948.9  441.25  4971.0  441.16  4977.7  437.22
  4978.2  436.72  4984.7  436.72  4985.2  437.22  4991.9  437.63  4999.3  441.29
  5033.2  440.39  5187.3  441.41  5299.3  443.66  5351.8  445.36  5517.5  448.02
#Mann=6,-1,0
  4195.3    0.05       0  4735.4    0.16       0  4909.7    0.12       0
  4948.9    0.05       0  4977.7    0.05       0  4985.2    0.05       0
Bank Sta=4977.7,4985.2
Exp/Cntr=0.3,0.1

Type RM Length L Ch R = 1,26081,256,256,256
BEGIN DESCRIPTION:
Purtis Creek26080.6
END DESCRIPTION:
XS GIS Cut Line= 3
      2753196.64      6832476.31      2752893.73      6833092.38
      2752595.08      6833653.21
#Sta/Elev= 30
  4323.7  452.95  4325.1  452.95  4377.3  449.53  4386.0  448.39  4425.4  445.09
  4440.4  444.43  4492.8  439.75  4540.8  437.89  4696.9  436.88  4697.4  436.38
  4703.9  436.38  4704.4  436.88  4835.5  437.06  4864.4  438.27  4970.4  440.48
  4986.4  440.05  4992.8  437.86  5006.7  437.25  5012.3  437.25  5015.2  440.36
  5081.2  438.98  5103.0  438.46  5133.3  438.79  5190.9  437.75  5251.1  437.83
  5333.3  438.37  5361.0  439.42  5415.5  439.97  5531.0  442.42  5645.6  441.58
#Mann=8,-1,0
  4323.7    0.16       0  4325.1    0.05       0  4377.3    0.16       0
  4540.8    0.05       0  4696.9    0.07       0  4704.4    0.05       0
  4864.4    0.16       0  5081.2    0.05       0
Bank Sta=4696.9,4704.4
Exp/Cntr=0.3,0.1

Type RM Length L Ch R = 1,25825,210,210,210
BEGIN DESCRIPTION:
Purtis Creek25824.75
END DESCRIPTION:
XS GIS Cut Line= 3
      2752939.18      6832245.96      2752696.02      6832943.17
      2752516.78      6833567.56
#Sta/Elev= 30
  4271.2  456.95  4273.5  456.98  4318.9  455.66  4393.0  446.82  4435.4  444.22
  4467.2  440.52  4475.4  437.06  4480.6  437.48  4488.3  435.76  4568.6  436.71
  4621.0  436.14  4687.5  436.72  4777.9  435.91  4975.5  438.21  4986.1  436.60
  4989.2  434.85  4989.7  434.35  4996.7  434.85  5005.8  438.48  5017.7  438.98
  5059.1  438.19  5080.2  439.00  5098.0  436.96  5111.4  439.02  5123.3  438.64
  5204.4  437.01  5309.0  436.78  5393.8  438.68  5485.9  442.79  5659.2  441.24
#Mann=7,-1,0
  4271.2    0.05       0  4273.5    0.16       0  4621.0    0.05       0
  4777.9    0.12       0  4989.2    0.07       0  4996.7    0.12       0
  5123.3    0.05       0
Bank Sta=4989.2,4996.7
Exp/Cntr=0.3,0.1

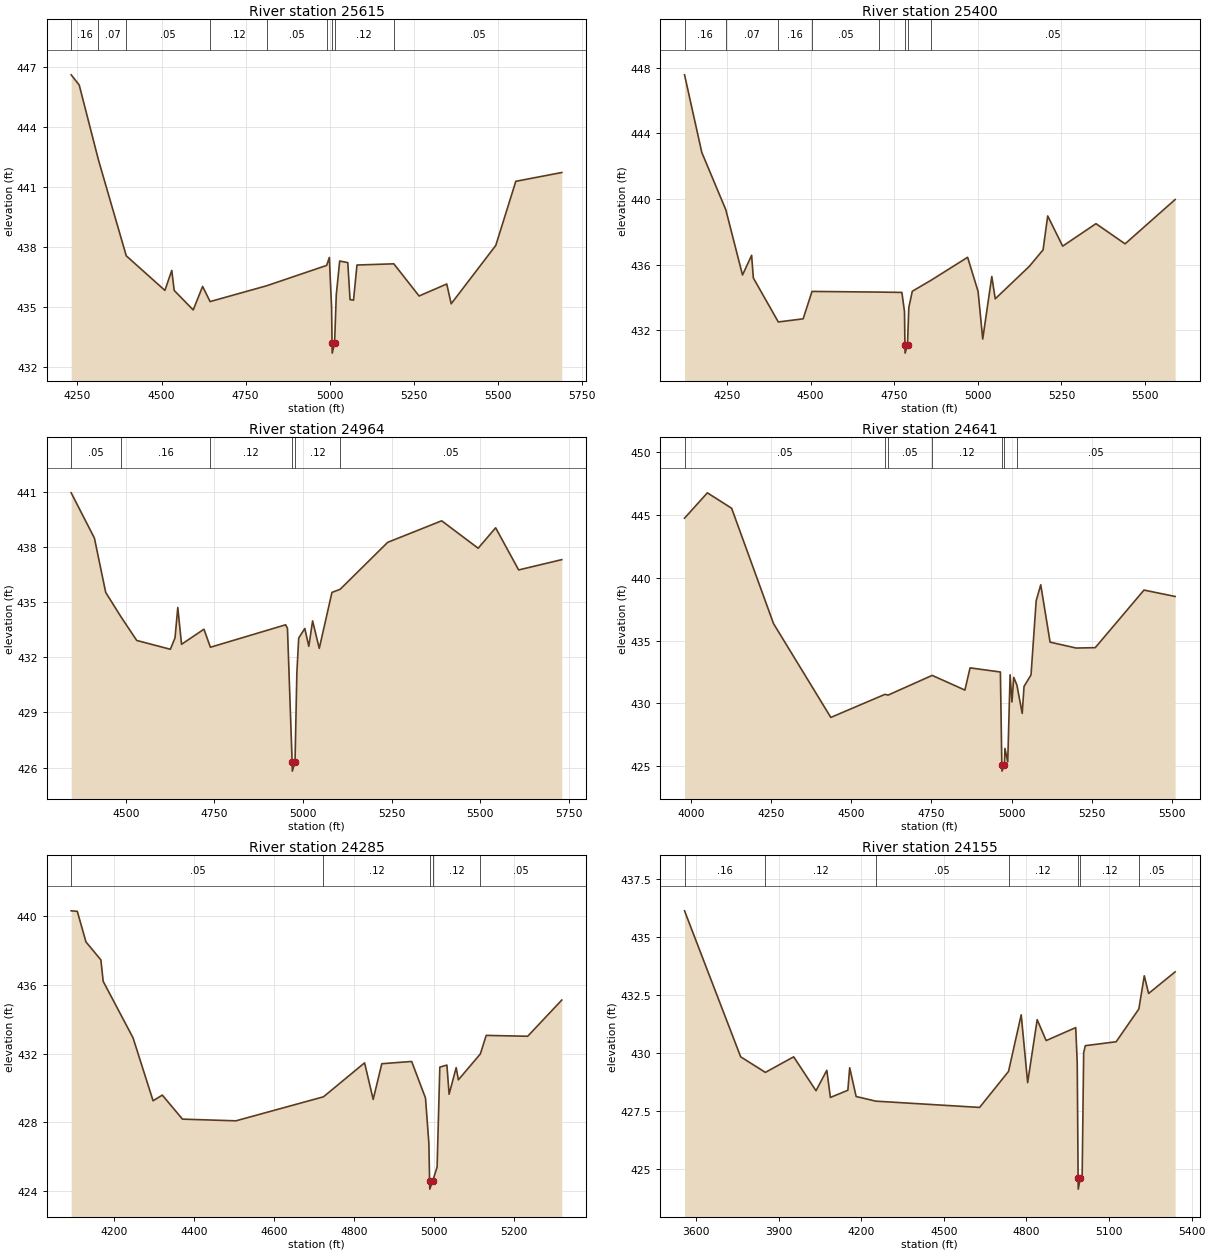
Type RM Length L Ch R = 1,25615,215,215,215
BEGIN DESCRIPTION:
Purtis Creek25614.73
END DESCRIPTION:
XS GIS Cut Line= 3
      2752660.40      6832107.54      2752509.55      6832876.31
      2752355.52      6833534.09
#Sta/Elev= 30
  4231.4  446.61  4255.3  446.10  4312.3  442.36  4395.2  437.55  4510.1  435.82
  4530.5  436.82  4537.7  435.82  4594.3  434.84  4622.2  436.02  4644.5  435.26
  4812.4  436.05  4991.1  437.07  4999.2  437.47  5005.8  434.95  5007.2  433.18
  5007.7  432.68  5014.7  433.18  5019.8  435.61  5029.9  437.29  5054.0  437.21
  5060.7  435.36  5071.0  435.33  5081.3  437.09  5190.9  437.15  5266.1  435.54
  5348.3  436.14  5361.5  435.15  5494.1  438.07  5553.7  441.28  5690.4  441.72
#Mann=9,-1,0
  4231.4    0.16       0  4312.3    0.07       0  4395.2    0.05       0
  4644.5    0.12       0  4812.4    0.05       0  4991.1    0.12       0
  5007.2    0.07       0  5014.7    0.12       0  5190.9    0.05       0
Bank Sta=5007.2,5014.7
Exp/Cntr=0.3,0.1

Type RM Length L Ch R = 1,25400,436,436,436
BEGIN DESCRIPTION:
Purtis Creek25400.23
END DESCRIPTION:
XS GIS Cut Line= 3
      2752533.84      6831993.66      2752301.51      6832850.50
      2752182.30      6833417.52
#Sta/Elev= 30
  4122.8  447.56  4174.4  442.83  4246.2  439.34  4296.2  435.36  4323.4  436.56
  4328.6  435.18  4403.2  432.50  4477.5  432.69  4504.0  434.36  4703.7  434.32
  4772.8  434.30  4780.6  433.14  4781.9  431.10  4782.4  430.60  4789.6  431.10
  4793.5  433.37  4803.9  434.37  4860.0  435.04  4969.4  436.44  5000.7  434.36
  5014.6  431.46  5041.7  435.27  5052.0  433.91  5154.0  435.89  5195.0  436.89
  5208.9  438.96  5253.7  437.12  5353.3  438.49  5440.3  437.26  5590.0  439.96
#Mann=8,-1,0
  4122.8    0.16       0  4246.2    0.07       0  4403.2    0.16       0
  4504.0    0.05       0  4703.7    0.12       0  4781.9    0.05       0
  4789.6    0.12       0  4860.0    0.05       0
Bank Sta=4781.9,4789.6
Exp/Cntr=0.3,0.1

Type RM Length L Ch R = 1,24964,323,323,323
BEGIN DESCRIPTION:
Purtis Creek24963.82
END DESCRIPTION:
XS GIS Cut Line= 3
      2752332.19      6831885.58      2752122.93      6832517.83
      2751999.99      6833224.74
#Sta/Elev= 30
  4346.2  440.93  4411.7  438.47  4443.5  435.52  4486.7  434.19  4531.0  432.91
  4625.8  432.43  4639.0  433.05  4646.8  434.70  4657.4  432.70  4720.6  433.52
  4738.8  432.54  4950.9  433.76  4956.1  433.57  4969.3  426.31  4969.8  425.81
  4977.4  426.31  4982.6  431.15  4987.8  433.04  5005.0  433.56  5016.3  432.59
  5027.0  433.97  5045.8  432.48  5081.6  435.52  5104.8  435.69  5238.7  438.24
  5391.0  439.41  5493.9  437.92  5543.2  439.03  5608.1  436.74  5729.7  437.30
#Mann=6,-1,0
  4346.2    0.05       0  4486.7    0.16       0  4738.8    0.12       0
  4969.3    0.07       0  4977.4    0.12       0  5104.8    0.05       0
Bank Sta=4969.3,4977.4
Exp/Cntr=0.3,0.1

Type RM Length L Ch R = 1,24641,356,356,356
BEGIN DESCRIPTION:
Purtis Creek24641.428
END DESCRIPTION:
XS GIS Cut Line= 3
      2752313.31      6831569.78      2751815.52      6832468.84
      2751571.74      6832906.91
#Sta/Elev= 30
  3980.8  444.75  4052.0  446.77  4127.6  445.54  4258.1  436.35  4436.7  428.87
  4605.5  430.71  4615.3  430.65  4752.6  432.22  4854.6  431.05  4870.7  432.82
  4965.2  432.49  4969.7  425.09  4970.2  424.59  4977.8  425.09  4979.4  426.40
  4988.1  425.33  4995.5  432.27  5001.2  430.10  5006.8  432.06  5016.7  431.45
  5033.2  429.19  5038.9  431.34  5060.7  432.26  5076.7  438.17  5091.0  439.44
  5120.1  434.87  5201.3  434.40  5260.8  434.43  5412.8  439.02  5509.8  438.51
#Mann=7,-1,0
  3980.8    0.05       0  4605.5    0.12       0  4615.3    0.05       0
  4752.6    0.12       0  4969.7    0.07       0  4977.8    0.12       0
  5016.7    0.05       0
Bank Sta=4969.7,4977.8
Exp/Cntr=0.3,0.1

Type RM Length L Ch R = 1,24285,130,130,130
BEGIN DESCRIPTION:
Purtis Creek24284.54
END DESCRIPTION:
XS GIS Cut Line= 3
      2752039.18      6831483.64      2751582.12      6832276.17
      2751454.75      6832560.57
#Sta/Elev= 30
  4092.1  440.33  4107.4  440.30  4129.0  438.52  4166.3  437.47  4172.1  436.22
  4246.7  432.93  4296.8  429.26  4319.9  429.59  4370.3  428.19  4503.8  428.09
  4722.8  429.49  4825.6  431.47  4847.1  429.34  4868.7  431.42  4943.3  431.55
  4977.9  429.42  4986.4  426.75  4988.1  424.61  4988.6  424.11  4996.3  424.61
  5006.9  425.40  5013.7  431.22  5031.4  431.34  5036.9  429.64  5054.6  431.19
  5060.1  430.48  5115.0  431.99  5129.7  433.07  5233.4  433.02  5318.6  435.13
#Mann=5,-1,0
  4092.1    0.05       0  4722.8    0.12       0  4988.1    0.07       0
  4996.3    0.12       0  5115.0    0.05       0
Bank Sta=4988.1,4996.3
Exp/Cntr=0.3,0.1

Type RM Length L Ch R = 1,24155,89,89,89
BEGIN DESCRIPTION:
Purtis Creek24155.09
END DESCRIPTION:
XS GIS Cut Line= 3
      2752071.96      6830857.51      2751490.21      6832187.36
      2751420.84      6832510.47
#Sta/Elev= 30
  3558.0  436.11  3761.9  429.82  3851.7  429.15  3954.4  429.82  4035.5  428.36
  4074.8  429.24  4087.8  428.07  4151.2  428.38  4157.9  429.35  4181.3  428.11
  4253.0  427.91  4629.7  427.64  4734.8  429.19  4780.9  431.63  4804.3  428.71
  4838.9  431.42  4871.6  430.52  4979.0  431.08  4984.4  429.56  4987.6  424.62
  4988.1  424.12  4995.8  424.62  5002.3  424.70  5007.8  430.00  5013.9  430.30
  5125.8  430.47  5208.2  431.88  5228.0  433.31  5243.7  432.55  5340.0  433.48
#Mann=7,-1,0
  3558.0    0.16       0  3851.7    0.12       0  4253.0    0.05       0
  4734.8    0.12       0  4987.6    0.07       0  4995.8    0.12       0
  5208.2    0.05       0
Bank Sta=4987.6,4995.8
Exp/Cntr=0.3,0.1

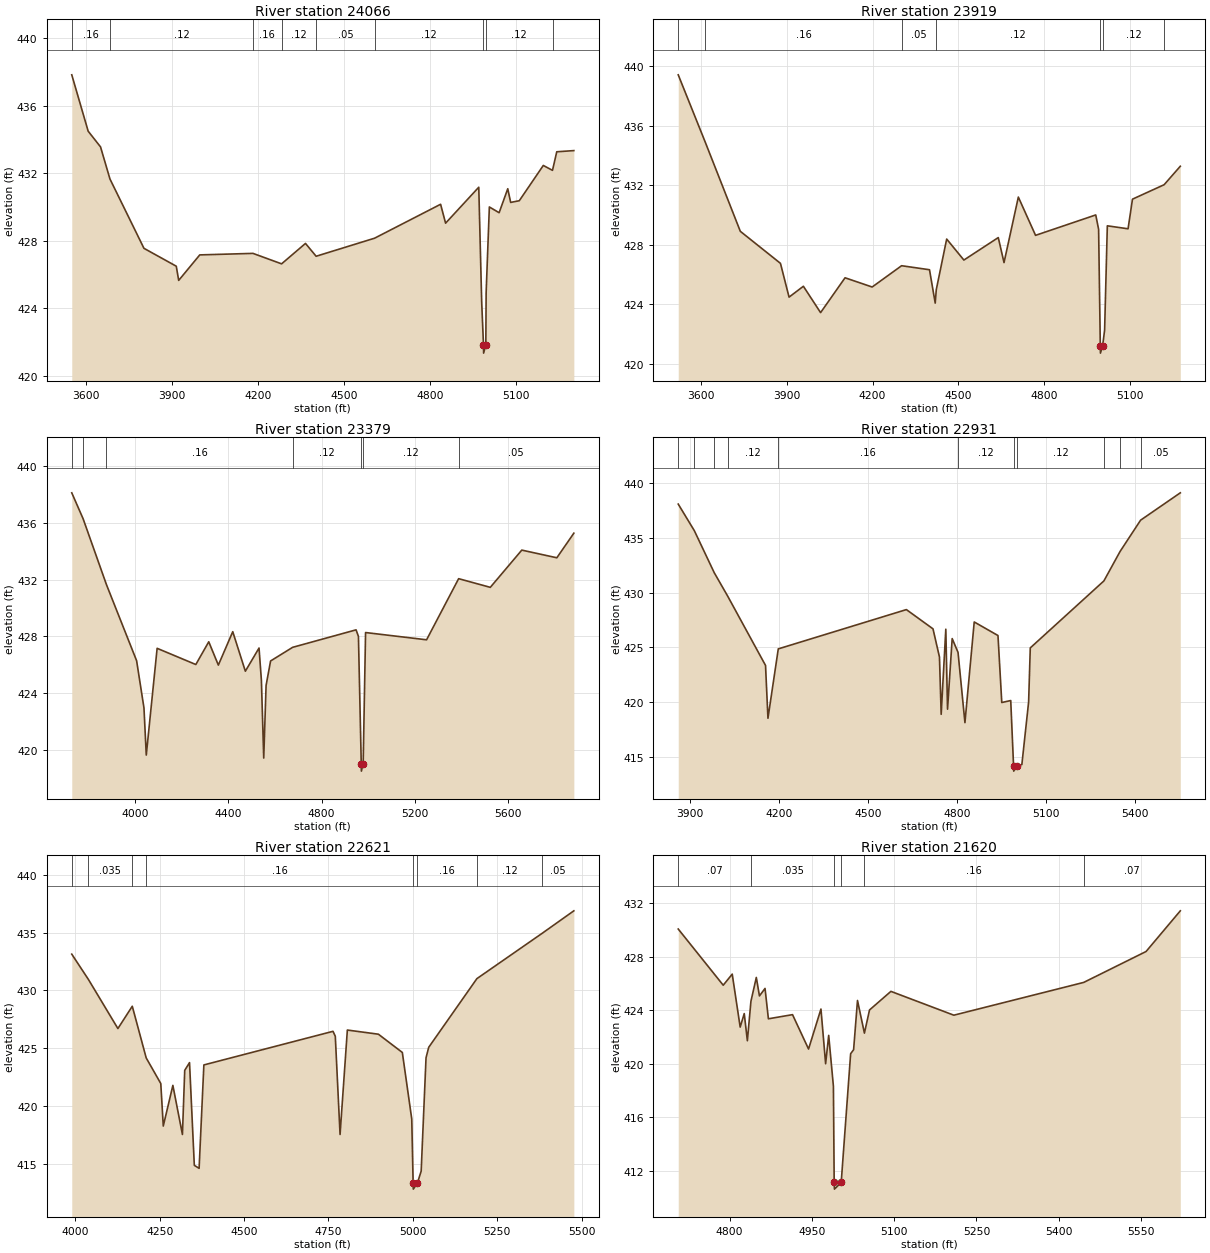
Type RM Length L Ch R = 1,24066,147,147,147
BEGIN DESCRIPTION:
Purtis Creek24065.96
END DESCRIPTION:
XS GIS Cut Line= 3
      2751721.96      6830745.18      2751408.39      6832168.06
      2751380.86      6832460.34
#Sta/Elev= 30
  3550.5  437.83  3607.7  434.49  3650.8  433.56  3683.6  431.66  3802.2  427.55
  3914.9  426.49  3923.3  425.65  3996.8  427.16  4182.3  427.25  4282.1  426.63
  4365.4  427.84  4402.5  427.08  4606.4  428.15  4836.5  430.16  4853.9  429.04
  4969.6  431.17  4979.8  424.36  4986.0  421.84  4986.5  421.34  4994.2  421.84
  4995.3  424.92  5006.5  430.00  5040.6  429.66  5070.7  431.08  5080.8  430.27
  5110.9  430.37  5194.6  432.46  5226.7  432.17  5241.5  433.27  5301.1  433.34
#Mann=9,-1,0
  3550.5    0.16       0  3683.6    0.12       0  4182.3    0.16       0
  4282.1    0.12       0  4402.5    0.05       0  4606.4    0.12       0
  4986.0    0.07       0  4994.2    0.12       0  5226.7    0.05       0
Bank Sta=4986,4994.2
Exp/Cntr=0.3,0.1

Type RM Length L Ch R = 1,23919,540,540,540
BEGIN DESCRIPTION:
Purtis Creek23918.55
END DESCRIPTION:
XS GIS Cut Line= 3
      2751373.92      6830674.39      2751264.63      6832157.67
      2751334.32      6832417.59
#Sta/Elev= 30
  3520.3  439.41  3615.6  434.85  3737.5  428.90  3877.9  426.75  3908.0  424.48
  3958.1  425.21  4018.3  423.44  4103.9  425.78  4198.7  425.16  4301.7  426.59
  4399.3  426.32  4419.3  424.08  4423.0  424.98  4459.4  428.38  4519.6  426.97
  4639.9  428.48  4660.0  426.80  4710.1  431.20  4770.3  428.63  4980.9  430.00
  4990.9  429.03  4996.8  421.22  4997.3  420.72  5005.0  421.22  5011.9  422.27
  5021.4  429.27  5093.9  429.07  5109.4  431.06  5220.1  432.03  5276.7  433.27
#Mann=7,-1,0
  3520.3   0.035       0  3615.6    0.16       0  4301.7    0.05       0
  4423.0    0.12       0  4996.8    0.07       0  5005.0    0.12       0
  5220.1    0.05       0
Bank Sta=4996.8,5005
Exp/Cntr=0.3,0.1

Type RM Length L Ch R = 1,23379,448,448,448
BEGIN DESCRIPTION:
Purtis Creek23379.194
END DESCRIPTION:
XS GIS Cut Line= 5
      2751198.61      6830620.06      2751012.89      6831374.08
      2750976.03      6831622.57      2750925.97      6831861.83
      2751434.45      6832583.61
#Sta/Elev= 30
  3727.8  438.10  3776.4  436.28  3876.7  431.64  4006.1  426.29  4037.7  422.97
  4047.6  419.65  4094.2  427.16  4260.3  426.02  4315.8  427.62  4357.0  425.98
  4418.8  428.33  4472.9  425.55  4531.6  427.18  4541.7  424.93  4551.8  419.44
  4561.9  424.55  4581.2  426.27  4675.9  427.23  4948.1  428.46  4958.3  428.00
  4970.4  419.02  4970.9  418.52  4978.6  419.02  4988.9  428.27  5250.8  427.76
  5388.4  432.06  5524.3  431.45  5659.5  434.07  5809.9  433.53  5882.9  435.26
#Mann=7,-1,0
  3727.8   0.035       0  3776.4    0.12       0  3876.7    0.16       0
  4675.9    0.12       0  4970.4    0.07       0  4978.6    0.12       0
  5388.4    0.05       0
Bank Sta=4970.4,4978.6
Exp/Cntr=0.3,0.1

Type RM Length L Ch R = 1,22931,310,310,310
BEGIN DESCRIPTION:
Purtis Creek22931.084
END DESCRIPTION:
XS GIS Cut Line= 3
      2751198.62      6830620.03      2750617.93      6831610.42
      2750124.51      6831840.97
#Sta/Elev= 30
  3859.7  438.10  3914.0  435.67  3981.1  431.83  4026.0  429.71  4154.0  423.36
  4162.2  418.53  4197.0  424.87  4628.9  428.46  4718.6  426.70  4740.4  424.13
  4746.2  418.89  4761.8  426.67  4767.6  419.36  4783.3  425.81  4803.0  424.55
  4826.3  418.13  4857.6  427.33  4937.7  426.09  4950.5  419.97  4980.7  420.15
  4990.2  414.20  4990.7  413.70  5002.6  414.20  5018.2  414.30  5041.0  420.02
  5046.6  424.96  5294.8  431.08  5349.3  433.77  5418.5  436.63  5552.4  439.13
#Mann=11,-1,0
  3859.7   0.035       0  3914.0    0.12       0  3981.1   0.035       0
  4026.0    0.12       0  4197.0    0.16       0  4803.0    0.12       0
  4990.2    0.07       0  5002.6    0.12       0  5294.8    0.05       0
  5349.3    0.12       0  5418.5    0.05       0
Bank Sta=4990.2,5002.6
Exp/Cntr=0.3,0.1

Type RM Length L Ch R = 1,22621,1001,1001,1001
BEGIN DESCRIPTION:
Purtis Creek22621.04
END DESCRIPTION:
XS GIS Cut Line= 3
      2751105.85      6830628.16      2750417.57      6831380.50
      2750053.41      6831673.06
#Sta/Elev= 30
  3989.8  433.13  4039.1  430.94  4126.4  426.69  4169.0  428.62  4210.2  424.15
  4253.4  421.93  4260.8  418.25  4289.2  421.77  4317.5  417.52  4324.3  423.07
  4338.5  423.74  4352.7  414.85  4366.9  414.59  4381.0  423.54  4763.4  426.45
  4770.2  426.02  4784.3  417.52  4805.9  426.56  4897.8  426.20  4968.7  424.62
  4996.6  418.86  5000.7  413.29  5001.2  412.79  5013.1  413.29  5024.5  414.35
  5038.9  424.16  5046.9  425.07  5189.5  431.01  5383.1  434.94  5476.6  436.88
#Mann=8,-1,0
  3989.8    0.12       0  4039.1   0.035       0  4169.0    0.12       0
  4210.2    0.16       0  5000.7    0.07       0  5013.1    0.16       0
  5189.5    0.12       0  5383.1    0.05       0
Bank Sta=5000.7,5013.1
Exp/Cntr=0.3,0.1

Type RM Length L Ch R = 1,21620,79,79,79
BEGIN DESCRIPTION:
Purtis Creek21619.79
END DESCRIPTION:
XS GIS Cut Line= 5
      2751035.75      6830598.75      2750776.76      6830736.23
      2750689.15      6830773.94      2750522.01      6830757.79
      2750163.57      6830752.61
#Sta/Elev= 30
  4706.5  430.06  4788.5  425.86  4804.9  426.69  4819.4  422.73  4826.8  423.74
  4832.5  421.71  4839.0  424.66  4848.8  426.44  4854.5  425.06  4864.7  425.62
  4870.8  423.35  4914.8  423.66  4944.0  421.09  4966.6  424.08  4975.1  419.99
  4980.7  422.11  4989.3  418.31  4990.7  411.12  4991.2  410.62  5003.5  411.12
  5020.7  420.74  5026.1  421.04  5033.2  424.72  5045.8  422.28  5055.1  424.01
  5094.1  425.40  5208.8  423.62  5445.5  426.07  5559.1  428.38  5621.5  431.42
#Mann=6,-1,0
  4706.5    0.07       0  4839.0   0.035       0  4990.7   0.035       0
  5003.5   0.035       0  5045.8    0.16       0  5445.5    0.07       0
Bank Sta=4990.7,5003.5
Exp/Cntr=0.3,0.1

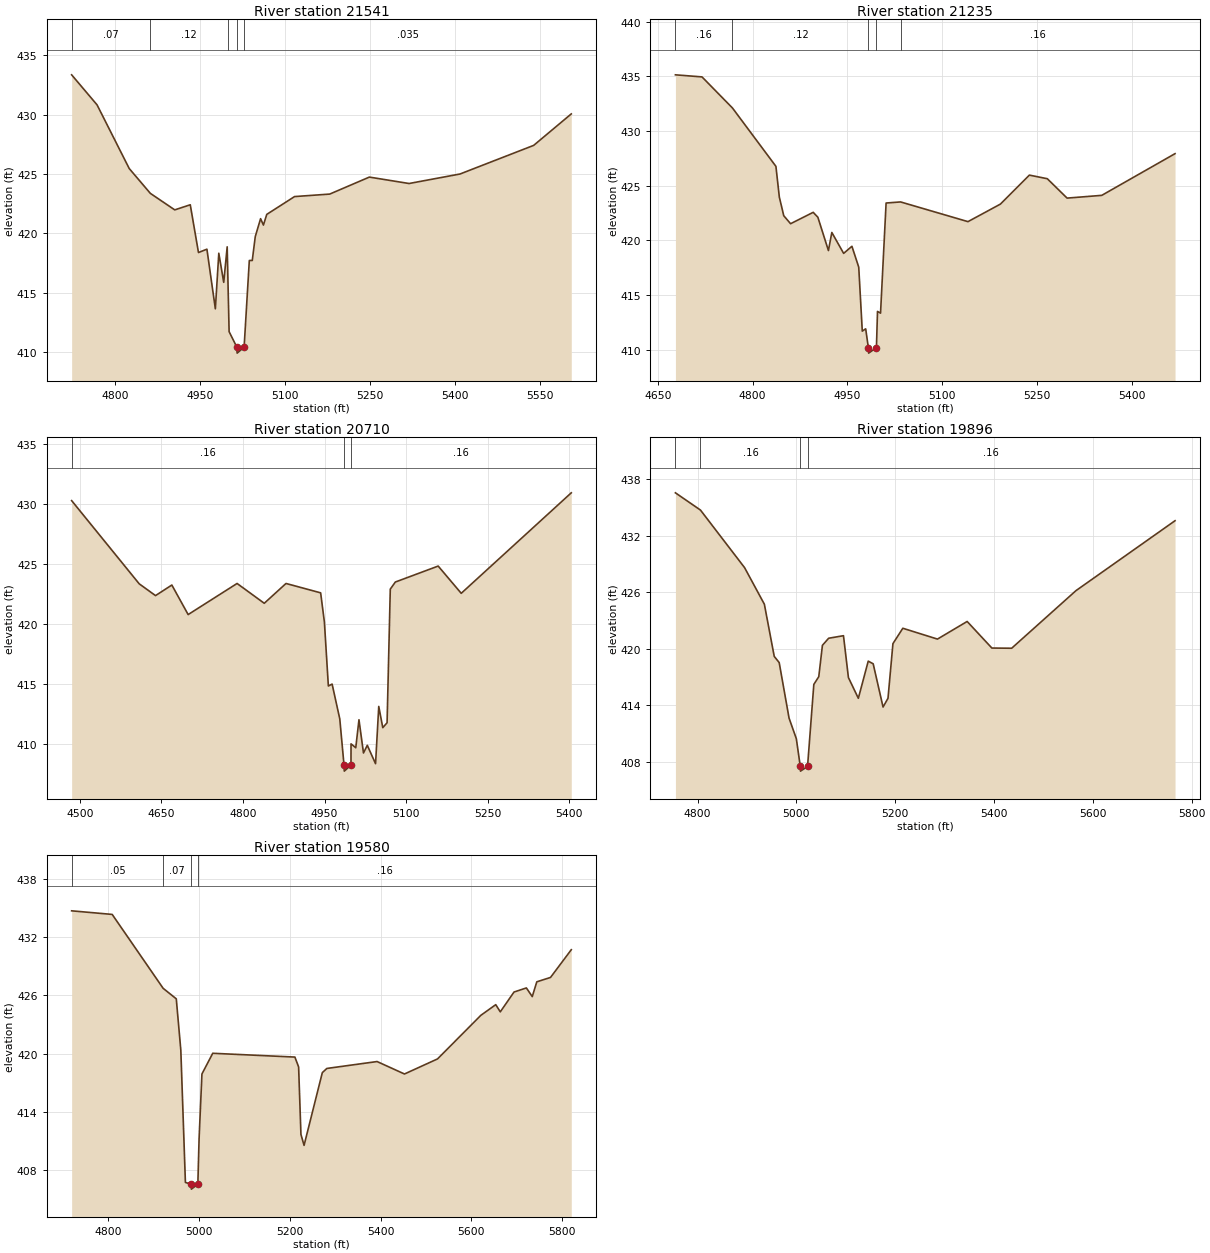
Type RM Length L Ch R = 1,21541,306,306,306
BEGIN DESCRIPTION:
Purtis Creek21540.97
END DESCRIPTION:
XS GIS Cut Line= 6
      2750998.46      6830500.86      2750831.09      6830616.31
      2750768.32      6830659.82      2750731.27      6830672.78
      2750625.02      6830691.00      2750169.66      6830674.84
#Sta/Elev= 30
  4722.6  433.35  4767.5  430.82  4824.3  425.46  4861.6  423.37  4904.7  421.98
  4932.1  422.41  4946.6  418.39  4961.5  418.67  4976.4  413.65  4982.5  418.33
  4991.2  415.88  4997.3  418.87  4998.0  417.40  5000.7  411.73  5014.4  410.42
  5014.9  409.92  5027.2  410.42  5036.4  417.72  5041.6  417.72  5046.9  419.73
  5056.3  421.24  5061.3  420.70  5067.2  421.60  5116.3  423.10  5178.4  423.31
  5248.4  424.74  5318.5  424.20  5408.5  425.00  5538.6  427.41  5605.0  430.06
#Mann=5,-1,0
  4722.6    0.07       0  4861.6    0.12       0  4998.0   0.035       0
  5014.4   0.035       0  5027.2   0.035       0
Bank Sta=5014.4,5027.2
Exp/Cntr=0.3,0.1

Type RM Length L Ch R = 1,21235,525,525,525
BEGIN DESCRIPTION:
Purtis Creek21235.22
END DESCRIPTION:
XS GIS Cut Line= 3
      2750924.98      6830304.89      2750622.19      6830427.48
      2750200.92      6830622.52
#Sta/Elev= 30
  4677.7  435.13  4719.8  434.94  4768.0  432.10  4836.8  426.77  4842.2  423.96
  4849.2  422.26  4860.0  421.53  4895.8  422.57  4903.2  422.12  4919.9  419.08
  4925.3  420.73  4944.0  418.82  4957.1  419.47  4967.9  417.56  4973.5  411.72
  4978.9  411.93  4983.1  410.21  4983.6  409.71  4995.9  410.21  4997.6  413.52
  5002.4  413.36  5011.2  423.42  5034.1  423.52  5140.8  421.72  5192.1  423.32
  5238.0  425.97  5266.4  425.64  5297.7  423.87  5352.6  424.12  5468.6  427.93
#Mann=5,-1,0
  4677.7    0.16       0  4768.0    0.12       0  4983.1    0.07       0
  4995.9    0.12       0  5034.1    0.16       0
Bank Sta=4983.1,4995.9
Exp/Cntr=0.3,0.1

Type RM Length L Ch R = 1,20710,814,814,814
BEGIN DESCRIPTION:
Purtis Creek20709.64
END DESCRIPTION:
XS GIS Cut Line= 4
      2750810.33      6830211.22      2750373.97      6830208.48
      2750317.58      6830261.68      2750100.44      6830603.68
#Sta/Elev= 30
  4484.9  430.25  4609.2  423.32  4639.2  422.34  4669.2  423.22  4699.2  420.76
  4789.2  423.35  4839.2  421.70  4879.2  423.35  4942.9  422.57  4949.8  420.14
  4957.1  414.81  4964.0  414.97  4978.1  412.07  4985.9  408.22  4986.4  407.72
  4998.7  408.22  4998.8  409.99  5007.5  409.67  5013.4  412.00  5021.7  409.23
  5028.7  409.87  5043.9  408.34  5049.8  413.11  5057.2  411.34  5065.1  411.75
  5071.0  422.88  5080.3  423.47  5159.1  424.80  5201.5  422.53  5403.9  430.90
#Mann=3,-1,0
  4484.9    0.16       0  4985.9    0.07       0  4998.7    0.16       0
Bank Sta=4985.9,4998.7
Exp/Cntr=0.3,0.1

Type RM Length L Ch R = 1,19896,316,316,316
BEGIN DESCRIPTION:
Purtis Creek19896.421
END DESCRIPTION:
XS GIS Cut Line= 3
      2750076.00      6829610.98      2750073.49      6829855.67
      2750038.94      6830621.29
#Sta/Elev= 30
  4755.3  436.53  4806.0  434.70  4895.3  428.59  4935.3  424.71  4955.3  419.17
  4965.3  418.52  4985.3  412.62  5000.0  410.44  5008.0  407.50  5008.5  407.00
  5022.7  407.50  5035.4  416.20  5045.4  417.02  5052.8  420.35  5065.4  421.10
  5095.4  421.37  5105.4  416.93  5125.5  414.73  5145.5  418.67  5155.5  418.39
  5175.5  413.80  5185.5  414.73  5195.5  420.53  5215.5  422.16  5285.6  421.01
  5345.7  422.88  5395.7  420.06  5435.8  420.04  5565.9  426.15  5766.4  433.57
#Mann=4,-1,0
  4755.3    0.05       0  4806.0    0.16       0  5008.0    0.07       0
  5022.7    0.16       0
Bank Sta=5008,5022.7
Exp/Cntr=0.3,0.1

Type RM Length L Ch R = 1,19580,391,391,391
BEGIN DESCRIPTION:
Purtis Creek19579.68
END DESCRIPTION:
XS GIS Cut Line= 3
      2749819.96      6829481.68      2749792.47      6829768.48
      2749711.32      6830576.50
#Sta/Elev= 30
  4719.7  434.69  4809.0  434.32  4921.2  426.72  4950.1  425.64  4960.1  420.37
  4970.2  406.76  4982.9  406.57  4983.4  406.07  4997.6  406.57  5000.3  411.22
  5006.6  417.91  5030.4  420.04  5211.3  419.65  5219.5  418.64  5224.6  411.70
  5231.5  410.57  5271.7  418.05  5281.7  418.48  5392.3  419.19  5452.6  417.91
  5525.4  419.46  5620.7  423.94  5653.6  425.04  5663.6  424.30  5693.8  426.34
  5721.0  426.76  5734.0  425.87  5744.0  427.39  5774.2  427.84  5819.9  430.69
#Mann=4,-1,0
  4719.7    0.05       0  4921.2    0.07       0  4982.9    0.07       0
  4997.6    0.16       0
Bank Sta=4982.9,4997.6
Exp/Cntr=0.3,0.1