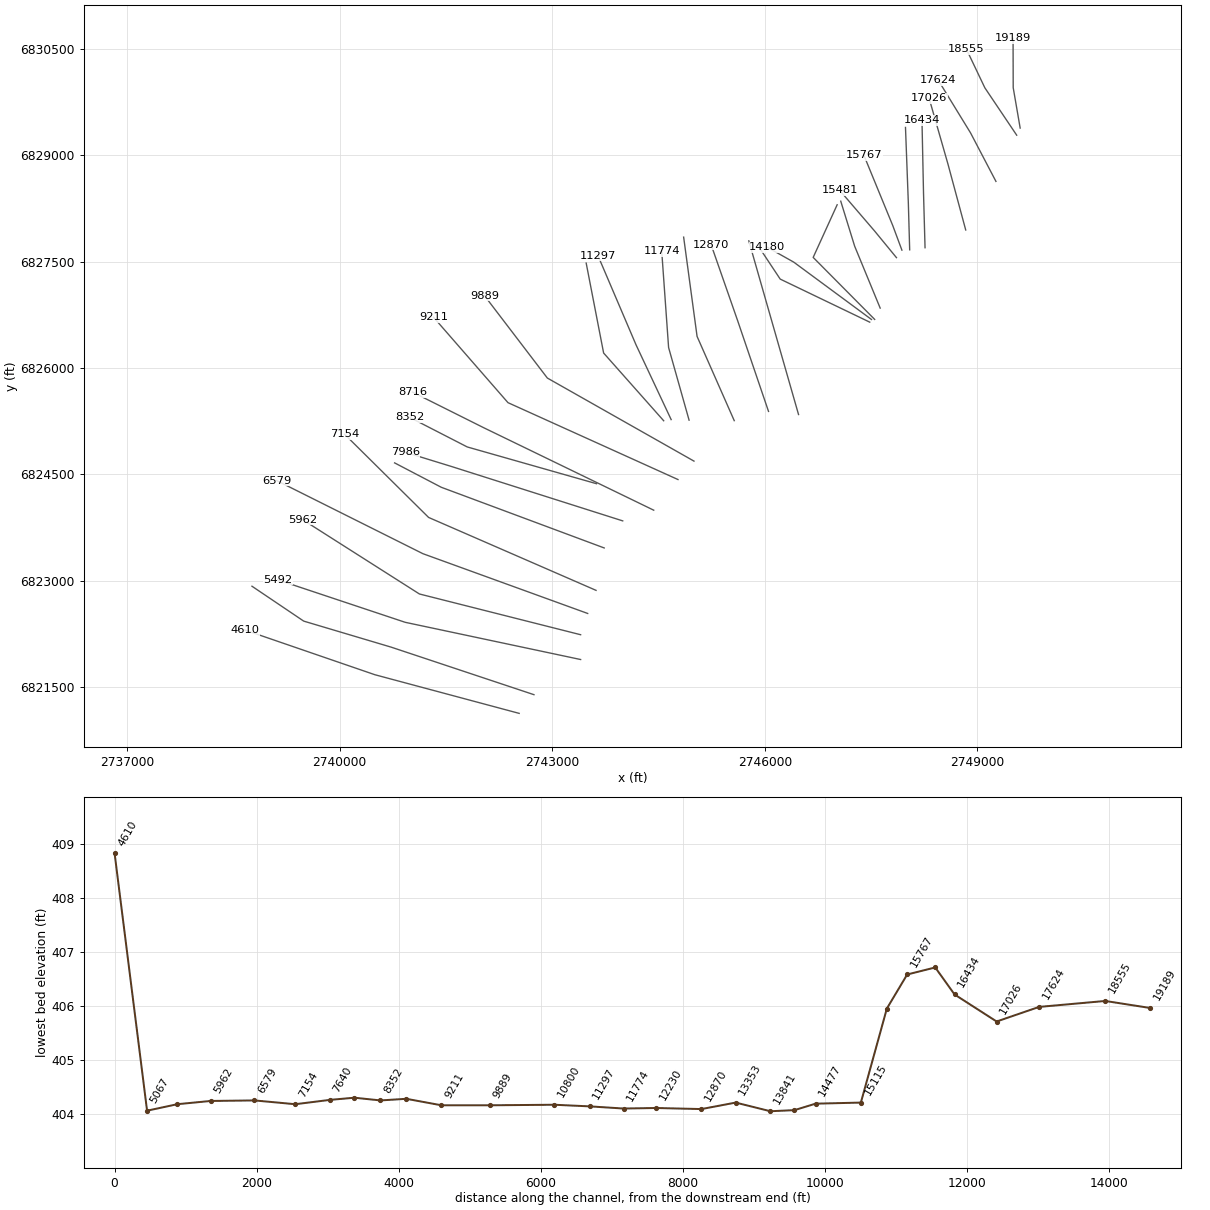
HEC-RAS study Purtis Creek.prj: Purtis Creek Base Level Engineering

--- Purtis Creek.g01 (geometry) --- (continued)

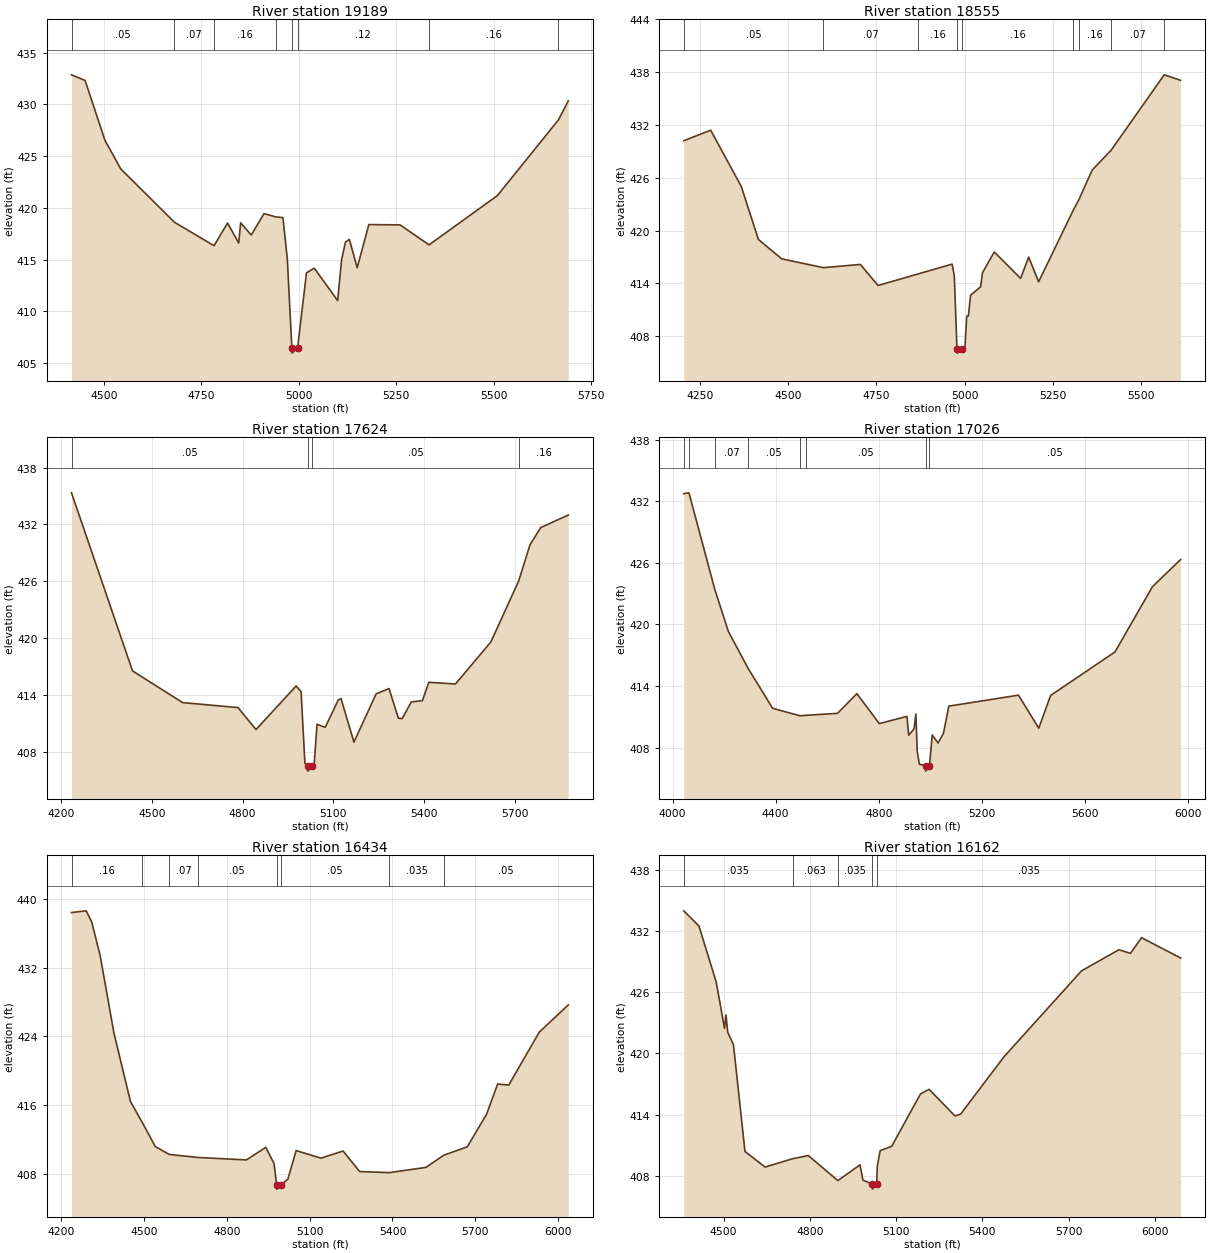
Type RM Length L Ch R = 1,19189,634,634,634
BEGIN DESCRIPTION:
Purtis Creek19189.32
END DESCRIPTION:
XS GIS Cut Line= 3
      2749604.51      6829386.54      2749506.29      6829955.70
      2749504.20      6830652.73
#Sta/Elev= 30
  4417.2  432.85  4452.2  432.30  4502.9  426.53  4543.5  423.76  4681.2  418.61
  4782.9  416.34  4817.5  418.53  4846.2  416.60  4851.2  418.55  4878.4  417.37
  4911.1  419.44  4940.6  419.13  4959.6  419.05  4970.9  415.06  4982.5  406.46
  4983.0  405.96  4997.2  406.46  5020.1  413.72  5040.1  414.17  5100.1  411.03
  5110.1  414.98  5120.1  416.69  5130.1  416.95  5150.1  414.21  5180.1  418.38
  5260.1  418.35  5334.6  416.42  5510.1  421.19  5666.3  428.49  5691.8  430.33
#Mann=8,-1,0
  4417.2    0.05       0  4681.2    0.07       0  4782.9    0.16       0
  4940.6    0.12       0  4982.5    0.07       0  4997.2    0.12       0
  5334.6    0.16       0  5666.3   0.035       0
Bank Sta=4982.5,4997.2
Exp/Cntr=0.3,0.1

Type RM Length L Ch R = 1,18555,931,931,931
BEGIN DESCRIPTION:
Purtis Creek18554.64
END DESCRIPTION:
XS GIS Cut Line= 3
      2749555.51      6829285.79      2749105.85      6829954.71
      2748847.15      6830497.18
#Sta/Elev= 30
  4204.5  430.21  4280.7  431.41  4367.4  425.02  4415.7  419.01  4481.7  416.80
  4599.6  415.80  4704.8  416.16  4754.7  413.77  4867.9  415.08  4964.6  416.20
  4970.7  414.86  4978.2  406.59  4978.7  406.09  4993.1  406.59  5000.6  406.63
  5005.9  410.30  5010.5  410.30  5016.9  412.68  5045.1  413.61  5050.7  415.24
  5083.9  417.58  5158.6  414.58  5181.3  417.00  5209.5  414.19  5307.8  422.34
  5323.1  423.48  5360.9  426.87  5415.1  429.15  5565.1  437.70  5611.5  437.08
#Mann=9,-1,0
  4204.5    0.05       0  4599.6    0.07       0  4867.9    0.16       0
  4978.2    0.07       0  4993.1    0.16       0  5307.8    0.07       0
  5323.1    0.16       0  5415.1    0.07       0  5565.1    0.16       0
Bank Sta=4978.2,4993.1
Exp/Cntr=0.3,0.1

Type RM Length L Ch R = 1,17624,598,598,598
BEGIN DESCRIPTION:
Purtis Creek17624.05
END DESCRIPTION:
XS GIS Cut Line= 3
      2749262.58      6828633.65      2748904.42      6829317.75
      2748450.16      6830058.81
#Sta/Elev= 30
  4234.7  435.33  4436.3  416.55  4601.6  413.21  4784.8  412.68  4844.3  410.36
  4976.7  414.96  4993.2  414.36  5005.9  406.81  5014.9  406.48  5015.4  405.98
  5030.0  406.48  5036.3  406.61  5045.9  410.92  5073.0  410.60  5116.3  413.50
  5125.2  413.63  5167.8  409.04  5241.2  414.13  5283.8  414.69  5314.7  411.55
  5327.4  411.52  5357.3  413.28  5394.0  413.41  5415.3  415.35  5503.3  415.17
  5620.2  419.60  5711.9  426.01  5749.6  429.85  5784.8  431.66  5876.1  432.99
#Mann=4,-1,0
  4234.7    0.05       0  5014.9    0.05       0  5030.0    0.05       0
  5711.9    0.16       0
Bank Sta=5014.9,5030
Exp/Cntr=0.3,0.1

Type RM Length L Ch R = 1,17026,592,592,592
BEGIN DESCRIPTION:
Purtis Creek17026.12
END DESCRIPTION:
XS GIS Cut Line= 3
      2748835.97      6827948.00      2748584.23      6828882.29
      2748319.53      6829805.90
#Sta/Elev= 30
  4043.4  432.74  4063.5  432.82  4164.3  423.37  4216.8  419.30  4293.7  415.70
  4388.3  411.83  4494.8  411.10  4517.7  411.15  4640.5  411.34  4715.2  413.26
  4802.5  410.34  4909.7  411.04  4916.5  409.22  4937.2  409.82  4944.5  411.28
  4949.6  407.62  4957.9  406.40  4982.0  406.21  4982.5  405.71  4997.1  406.21
  5007.8  409.23  5030.5  408.45  5051.3  409.38  5072.1  412.04  5342.6  413.11
  5421.3  409.89  5467.4  413.08  5717.3  417.32  5862.7  423.68  5971.8  426.32
#Mann=8,-1,0
  4043.4    0.07       0  4063.5   0.035       0  4164.3    0.07       0
  4293.7    0.05       0  4494.8    0.07       0  4517.7    0.05       0
  4982.0    0.05       0  4997.1    0.05       0
Bank Sta=4982,4997.1
Exp/Cntr=0.3,0.1

Type RM Length L Ch R = 1,16434,272,272,272
BEGIN DESCRIPTION:
Purtis Creek16433.54
END DESCRIPTION:
XS GIS Cut Line= 3
      2748261.96      6827697.59      2748240.46      6828469.50
      2748218.69      6829496.86
#Sta/Elev= 30
  4237.2  438.43  4290.6  438.63  4310.6  437.31  4340.7  433.46  4390.7  424.43
  4450.7  416.42  4493.4  413.99  4540.7  411.17  4591.3  410.25  4694.4  409.90
  4870.9  409.61  4940.9  411.08  4970.9  409.20  4980.3  406.71  4980.8  406.21
  4995.6  406.71  5020.9  407.36  5050.9  410.70  5140.9  409.82  5221.0  410.65
  5281.0  408.26  5388.1  408.13  5521.0  408.74  5585.8  410.16  5671.1  411.14
  5741.1  414.95  5781.1  418.46  5821.1  418.33  5932.1  424.51  6037.0  427.67
#Mann=8,-1,0
  4237.2    0.16       0  4493.4   0.035       0  4591.3    0.07       0
  4694.4    0.05       0  4980.3    0.05       0  4995.6    0.05       0
  5388.1   0.035       0  5585.8    0.05       0
Bank Sta=4980.3,4995.6
Exp/Cntr=0.3,0.1

Type RM Length L Ch R = 1,16162,395,395,395
BEGIN DESCRIPTION:
Purtis Creek16161.93
END DESCRIPTION:
XS GIS Cut Line= 3
      2748045.16      6827668.14      2748026.57      6828318.89
      2747986.00      6829395.11
#Sta/Elev= 30
  4361.2  433.98  4414.1  432.49  4474.1  426.99  4503.0  422.46  4508.0  423.78
  4514.1  422.08  4534.1  420.84  4574.1  410.40  4644.2  408.87  4739.6  409.69
  4794.2  410.00  4897.3  407.55  4974.3  409.09  4984.3  407.59  5016.7  407.21
  5017.2  406.71  5032.0  407.21  5034.3  408.95  5044.3  410.48  5084.4  410.91
  5184.4  416.03  5214.5  416.49  5304.5  413.88  5324.5  414.07  5474.7  419.67
  5744.8  428.10  5874.9  430.17  5915.0  429.81  5953.3  431.35  6089.2  429.36
#Mann=5,-1,0
  4361.2   0.035       0  4739.6   0.063       0  4897.3   0.035       0
  5016.7   0.035       0  5032.0   0.035       0
Bank Sta=5016.7,5032
Exp/Cntr=0.3,0.1

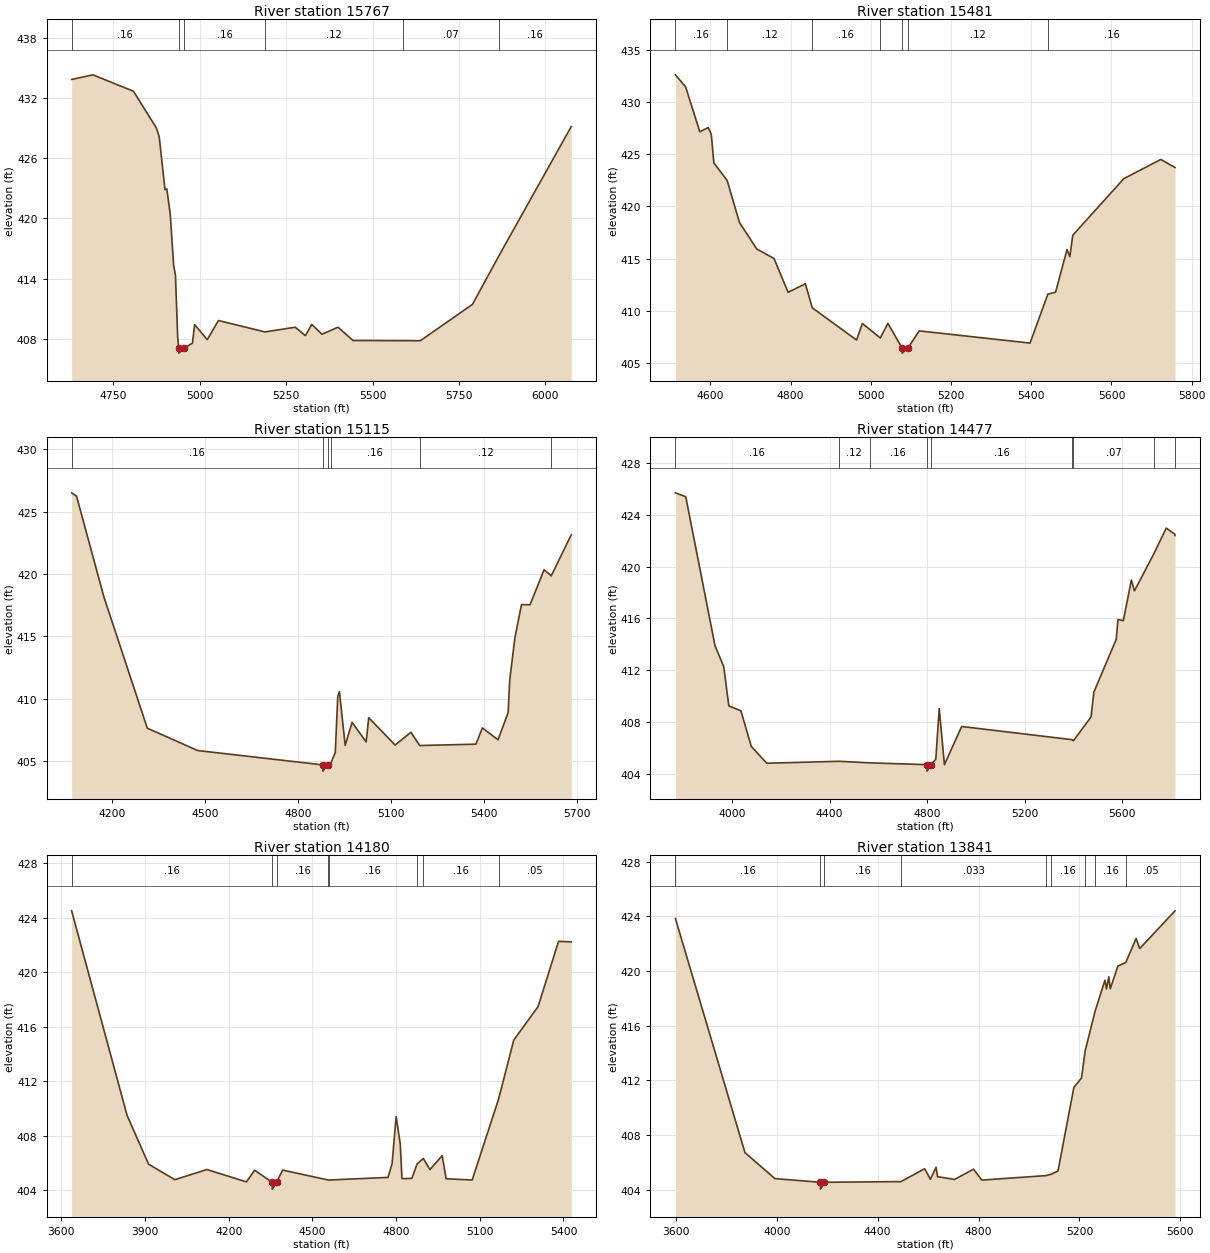
Type RM Length L Ch R = 1,15767,286,286,286
BEGIN DESCRIPTION:
Purtis Creek15704.11
END DESCRIPTION:
XS GIS Cut Line= 3
      2747935.41      6827663.49      2747806.13      6828010.91
      2747397.84      6829005.25
#Sta/Elev= 30
  4629.3  433.83  4690.7  434.29  4808.0  432.66  4874.4  429.01  4882.7  428.12
  4899.4  422.85  4904.7  422.94  4914.7  420.37  4924.4  415.32  4929.7  414.34
  4936.1  408.16  4939.1  407.08  4939.6  406.58  4954.4  407.08  4978.8  407.57
  4985.1  409.42  5021.7  407.92  5054.1  409.83  5188.4  408.69  5276.3  409.16
  5305.6  408.32  5324.2  409.44  5353.6  408.46  5400.1  409.16  5443.3  407.84
  5586.7  407.82  5637.9  407.81  5789.2  411.44  5864.6  416.21  6074.9  429.14
#Mann=6,-1,0
  4629.3    0.16       0  4939.1    0.07       0  4954.4    0.16       0
  5188.4    0.12       0  5586.7    0.07       0  5864.6    0.16       0
Bank Sta=4939.1,4954.4
Exp/Cntr=0.3,0.1

Type RM Length L Ch R = 1,15481,366,366,366
BEGIN DESCRIPTION:
Purtis Creek15173.91
END DESCRIPTION:
XS GIS Cut Line= 3
      2747858.56      6827557.79      2747549.31      6827934.39
      2747055.33      6828509.98
#Sta/Elev= 30
  4512.7  432.59  4538.3  431.43  4573.5  427.14  4594.5  427.54  4602.2  426.89
  4608.6  424.16  4641.6  422.49  4672.5  418.45  4715.6  415.92  4758.6  415.01
  4793.8  411.77  4836.8  412.59  4853.9  410.29  4964.5  407.20  4978.9  408.79
  5023.6  407.40  5042.6  408.80  5077.7  406.45  5078.2  405.95  5093.0  406.45
  5120.5  408.08  5397.0  406.91  5441.5  411.60  5460.7  411.78  5489.2  415.86
  5496.3  415.18  5503.5  417.23  5630.8  422.65  5723.0  424.49  5758.5  423.72
#Mann=7,-1,0
  4512.7    0.16       0  4641.6    0.12       0  4853.9    0.16       0
  5023.6    0.12       0  5077.7    0.07       0  5093.0    0.12       0
  5441.5    0.16       0
Bank Sta=5077.7,5093
Exp/Cntr=0.3,0.1

Type RM Length L Ch R = 1,15115,638,638,638
BEGIN DESCRIPTION:
Mapping XS f44284e3
END DESCRIPTION:
XS GIS Cut Line= 3
      2747628.79      6826845.64      2747268.27      6827720.22
      2747072.27      6828354.55
#Sta/Elev= 30
  4070.3  426.50  4086.1  426.23  4174.2  418.16  4314.1  407.65  4476.3  405.86
  4879.7  404.71  4880.2  404.21  4895.0  404.71  4904.6  404.80  4919.8  405.70
  4927.8  410.18  4933.2  410.57  4951.7  406.27  4973.9  408.12  5019.3  406.55
  5027.6  408.49  5112.6  406.30  5163.6  407.32  5191.9  406.26  5373.0  406.37
  5393.9  407.67  5444.2  406.72  5476.8  408.89  5482.0  411.51  5498.6  414.90
  5519.9  417.55  5547.3  417.53  5592.7  420.34  5615.8  419.85  5680.2  423.14
#Mann=6,-1,0
  4070.3    0.16       0  4879.7    0.07       0  4895.0    0.16       0
  4904.6    0.16       0  5191.9    0.12       0  5615.8    0.16       0
Bank Sta=4879.7,4895
Exp/Cntr=0.3,0.1

Type RM Length L Ch R = 1,14477,297,297,297
BEGIN DESCRIPTION:
Purtis Creek14476.526
END DESCRIPTION:
XS GIS Cut Line= 3
      2747550.97      6826686.03      2746683.21      6827560.98
      2747021.63      6828303.82
#Sta/Elev= 30
  3767.7  425.70  3810.1  425.40  3930.3  413.87  3965.7  412.28  3986.8  409.23
  4036.4  408.85  4078.8  406.10  4142.4  404.80  4438.9  404.95  4564.0  404.83
  4799.4  404.69  4799.9  404.19  4814.8  404.69  4835.4  405.10  4849.5  409.02
  4870.8  404.69  4941.5  407.64  5394.8  406.62  5399.4  406.53  5472.1  408.38
  5483.5  410.29  5575.3  414.38  5582.4  415.91  5604.4  415.82  5637.4  418.96
  5649.9  418.12  5729.9  421.00  5780.2  422.97  5815.1  422.51  5816.3  422.40
#Mann=9,-1,0
  3767.7    0.16       0  4438.9    0.12       0  4564.0    0.16       0
  4799.4    0.07       0  4814.8    0.16       0  5394.8    0.12       0
  5399.4    0.07       0  5729.9    0.12       0  5815.1    0.16       0
Bank Sta=4799.4,4814.8
Exp/Cntr=0.3,0.1

Type RM Length L Ch R = 1,14180,339,339,339
BEGIN DESCRIPTION:
Mapping XS 3ba58fb5
END DESCRIPTION:
XS GIS Cut Line= 3
      2747506.29      6826684.65      2746409.47      6827493.99
      2746036.34      6827703.65
#Sta/Elev= 30
  3636.9  424.50  3835.6  409.48  3912.8  405.90  4006.8  404.76  4121.7  405.51
  4263.6  404.60  4292.9  405.46  4355.8  404.57  4356.3  404.07  4371.9  404.57
  4393.1  405.47  4556.5  404.74  4560.1  404.74  4771.0  404.93  4785.6  405.93
  4800.3  409.40  4814.9  407.39  4821.1  404.84  4856.6  404.86  4875.3  405.92
  4897.7  406.32  4921.4  405.50  4965.3  406.53  4979.5  404.83  5072.8  404.74
  5167.8  410.70  5221.9  415.01  5309.1  417.47  5382.5  422.26  5428.0  422.22
#Mann=8,-1,0
  3636.9    0.16       0  4355.8    0.07       0  4371.9    0.16       0
  4556.5   0.033       0  4560.1    0.16       0  4875.3    0.12       0
  4897.7    0.16       0  5167.8    0.05       0
Bank Sta=4355.8,4371.9
Exp/Cntr=0.3,0.1

Type RM Length L Ch R = 1,13841,488,488,488
BEGIN DESCRIPTION:
Mapping XS 19bce363
END DESCRIPTION:
XS GIS Cut Line= 3
      2747481.39      6826647.32      2746217.81      6827254.97
      2745897.66      6827737.65
#Sta/Elev= 30
  3597.9  423.84  3873.7  406.72  3992.5  404.82  4172.8  404.55  4173.3  404.05
  4189.0  404.55  4492.2  404.60  4586.5  405.54  4609.1  404.77  4631.7  405.65
  4637.3  404.96  4705.2  404.76  4780.1  405.51  4812.8  404.71  5068.7  405.04
  5086.2  405.13  5115.1  405.37  5178.2  411.49  5208.3  412.17  5223.2  414.19
  5262.6  417.08  5301.5  419.33  5307.5  418.69  5316.6  419.58  5322.6  418.70
  5352.6  420.36  5384.0  420.62  5424.8  422.38  5439.2  421.64  5579.2  424.40
#Mann=9,-1,0
  3597.9    0.16       0  4172.8   0.033       0  4189.0    0.16       0
  4492.2   0.033       0  5068.7    0.05       0  5086.2    0.16       0
  5223.2    0.05       0  5262.6    0.16       0  5384.0    0.05       0
Bank Sta=4172.8,4189
Exp/Cntr=0.3,0.1

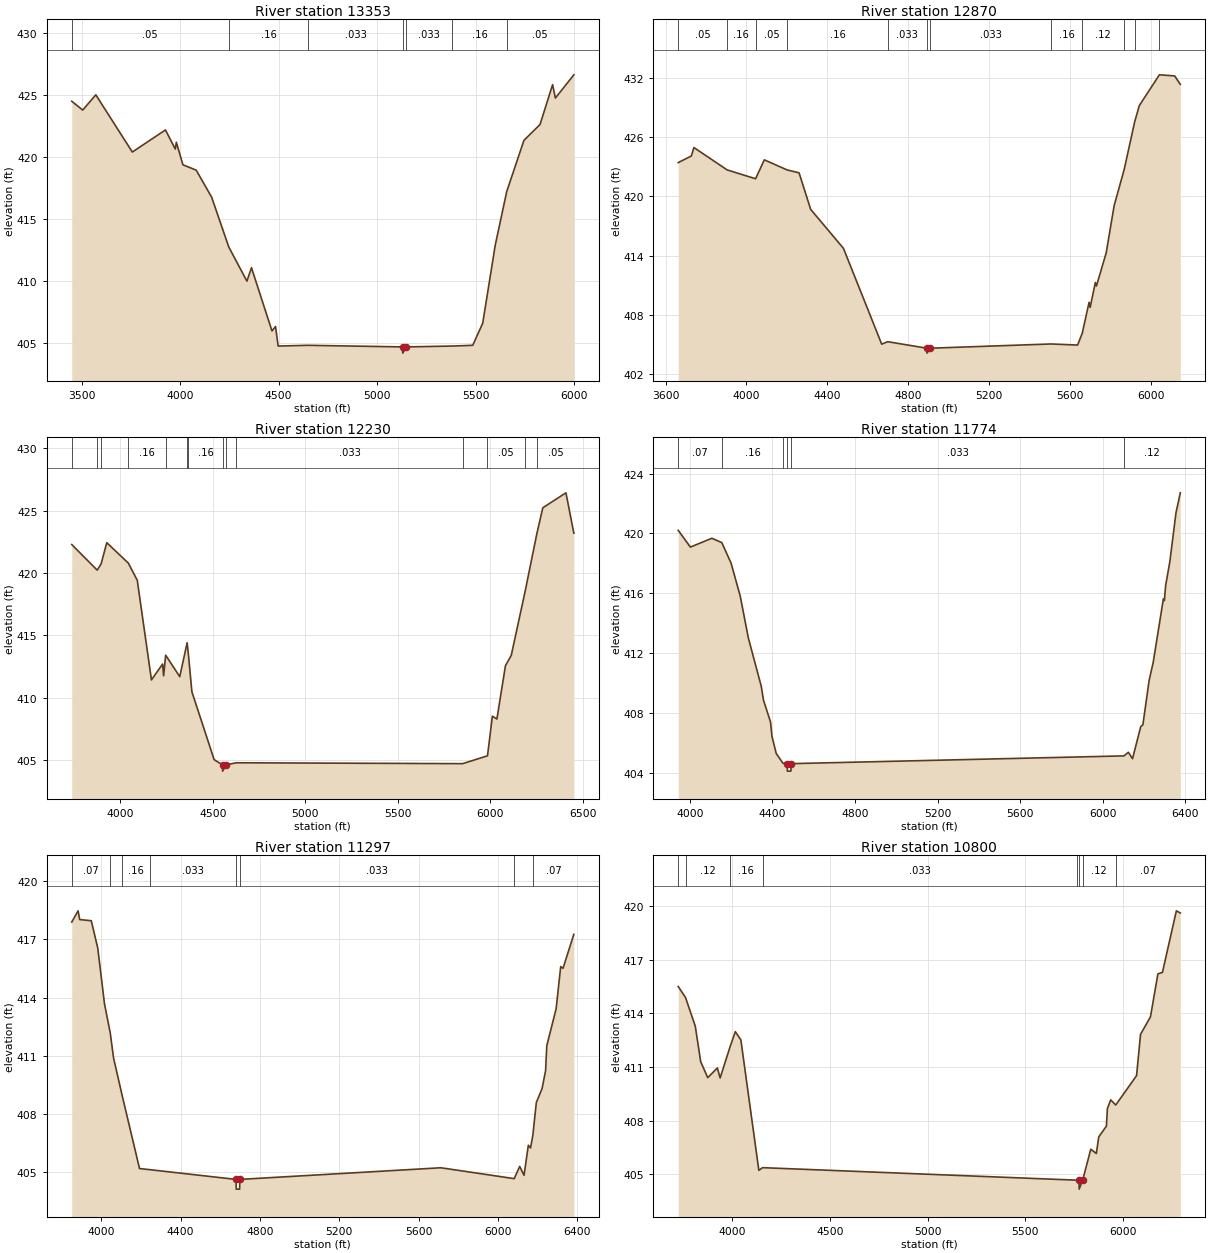
Type RM Length L Ch R = 1,13353,483,483,483
BEGIN DESCRIPTION:
Purtis Creek13353.26
END DESCRIPTION:
XS GIS Cut Line= 3
      2746476.61      6825343.66      2746045.51      6826848.69
      2745774.82      6827794.67
#Sta/Elev= 30
  3449.5  424.50  3505.1  423.79  3571.6  425.02  3757.0  420.41  3925.2  422.19
  3975.2  420.65  3980.4  421.20  4014.1  419.38  4081.3  418.95  4159.6  416.78
  4246.8  412.76  4338.8  410.01  4362.1  411.09  4466.1  406.00  4484.2  406.35
  4497.4  404.78  4650.1  404.84  5129.8  404.71  5130.3  404.21  5147.8  404.71
  5382.0  404.78  5485.5  404.84  5536.3  406.62  5599.9  412.91  5658.4  417.24
  5745.6  421.35  5827.3  422.63  5891.2  425.84  5905.3  424.76  5999.0  426.63
#Mann=7,-1,0
  3449.5    0.05       0  4246.8    0.16       0  4650.1   0.033       0
  5129.8   0.033       0  5147.8   0.033       0  5382.0    0.16       0
  5658.4    0.05       0
Bank Sta=5129.8,5147.8
Exp/Cntr=0.3,0.1

Type RM Length L Ch R = 1,12870,640,640,640
BEGIN DESCRIPTION:
Purtis Creek12870.27
END DESCRIPTION:
XS GIS Cut Line= 3
      2746052.99      6825387.63      2745618.17      6826665.27
      2745243.87      6827737.30
#Sta/Elev= 30
  3662.2  423.43  3727.2  424.10  3739.7  424.96  3904.1  422.69  4045.1  421.79
  4088.3  423.71  4200.7  422.69  4260.3  422.39  4317.8  418.68  4479.9  414.73
  4669.3  405.00  4699.1  405.25  4892.7  404.59  4893.2  404.09  4910.7  404.59
  5507.4  405.02  5638.9  404.91  5662.0  406.11  5695.7  409.25  5701.0  408.73
  5726.8  411.26  5732.1  410.90  5780.5  414.27  5819.9  419.07  5869.5  422.73
  5921.2  427.55  5944.2  429.21  6043.7  432.34  6119.4  432.23  6147.3  431.37
#Mann=12,-1,0
  3662.2    0.05       0  3904.1    0.16       0  4045.1    0.05       0
  4200.7    0.16       0  4699.1   0.033       0  4892.7   0.033       0
  4910.7   0.033       0  5507.4    0.16       0  5662.0    0.12       0
  5869.5    0.16       0  5921.2    0.12       0  6043.7    0.05       0
Bank Sta=4892.7,4910.7
Exp/Cntr=0.3,0.1

Type RM Length L Ch R = 1,12230,456,456,456
BEGIN DESCRIPTION:
Purtis Creek12230.19
END DESCRIPTION:
XS GIS Cut Line= 3
      2745569.23      6825257.04      2745044.71      6826445.88
      2744855.14      6827847.21
#Sta/Elev= 30
  3738.1  422.29  3875.4  420.24  3896.5  420.73  3927.3  422.44  4043.9  420.80
  4092.2  419.42  4168.7  411.43  4229.0  412.70  4234.5  411.76  4245.6  413.41
  4321.7  411.69  4361.6  414.41  4368.2  413.52  4387.3  410.48  4507.5  405.03
  4553.1  404.61  4553.6  404.11  4571.3  404.61  4626.9  404.78  5850.9  404.71
  5984.9  405.34  6011.4  408.52  6035.8  408.29  6082.0  412.57  6113.4  413.40
  6188.3  418.53  6251.9  423.18  6283.9  425.24  6408.9  426.44  6451.6  423.20
#Mann=14,-1,0
  3738.1    0.12       0  3875.4    0.16       0  3896.5    0.12       0
  4043.9    0.16       0  4245.6    0.05       0  4361.6    0.07       0
  4368.2    0.16       0  4553.1   0.033       0  4571.3    0.16       0
  4626.9   0.033       0  5850.9    0.16       0  5984.9    0.05       0
  6188.3    0.12       0  6251.9    0.05       0
Bank Sta=4553.1,4571.3
Exp/Cntr=0.3,0.1

Type RM Length L Ch R = 1,11774,477,477,477
BEGIN DESCRIPTION:
Purtis Creek11773.57
END DESCRIPTION:
XS GIS Cut Line= 3
      2744931.81      6825264.28      2744642.72      6826289.46
      2744545.44      6827651.83
#Sta/Elev= 30
  3944.3  420.21  4003.2  419.09  4107.1  419.68  4155.3  419.39  4200.3  418.01
  4244.7  415.80  4283.9  413.00  4346.1  409.79  4357.1  408.85  4391.1  407.39
  4398.1  406.43  4418.8  405.28  4451.3  404.63  4472.1  404.60  4472.6  404.10
  4489.8  404.10  4490.3  404.60  6102.3  405.12  6123.8  405.36  6143.9  404.93
  6184.0  407.09  6194.0  407.19  6224.1  410.15  6244.1  411.38  6293.3  415.62
  6298.3  415.51  6304.3  416.52  6324.3  418.08  6354.4  421.39  6375.3  422.72
#Mann=6,-1,0
  3944.3    0.07       0  4155.3    0.16       0  4451.3   0.033       0
  4472.1   0.033       0  4490.3   0.033       0  6102.3    0.12       0
Bank Sta=4472.1,4490.3
Exp/Cntr=0.3,0.1

Type RM Length L Ch R = 1,11297,497,497,497
BEGIN DESCRIPTION:
Purtis Creek11296.71
END DESCRIPTION:
XS GIS Cut Line= 3
      2744678.85      6825272.00      2744183.26      6826326.96
      2743647.65      6827581.87
#Sta/Elev= 30
  3852.0  417.89  3884.0  418.47  3891.8  418.02  3950.3  417.96  3983.0  416.55
  4016.9  413.68  4045.8  412.19  4062.5  410.90  4105.5  408.98  4193.4  405.20
  4246.4  405.14  4680.2  404.64  4680.7  404.14  4697.9  404.14  4698.4  404.64
  5711.8  405.24  6081.5  404.68  6109.2  405.31  6131.0  404.85  6152.7  406.40
  6163.6  406.26  6175.4  406.91  6193.0  408.60  6222.0  409.32  6239.7  410.25
  6245.6  411.52  6292.8  413.43  6315.8  415.60  6327.3  415.51  6382.0  417.26
#Mann=8,-1,0
  3852.0    0.07       0  4045.8    0.12       0  4105.5    0.16       0
  4246.4   0.033       0  4680.2   0.033       0  4698.4   0.033       0
  6081.5    0.12       0  6175.4    0.07       0
Bank Sta=4680.2,4698.4
Exp/Cntr=0.3,0.1

Type RM Length L Ch R = 1,10800,911,911,911
BEGIN DESCRIPTION:
Purtis Creek10799.579
END DESCRIPTION:
XS GIS Cut Line= 3
      2744573.43      6825255.62      2743725.86      6826211.33
      2743479.59      6827480.87
#Sta/Elev= 30
  3722.6  415.49  3759.8  414.88  3810.0  413.27  3837.6  411.29  3873.6  410.40
  3922.9  410.94  3937.1  410.38  3987.9  412.12  4014.9  412.97  4043.3  412.51
  4135.3  405.22  4154.3  405.37  5763.9  404.67  5774.9  404.67  5775.4  404.17
  5793.1  404.67  5834.9  406.40  5863.1  406.16  5875.7  407.09  5914.8  407.69
  5919.9  408.67  5936.8  409.16  5962.5  408.87  6069.2  410.51  6089.6  412.82
  6140.5  413.80  6178.5  416.20  6201.7  416.28  6273.0  419.72  6293.2  419.60
#Mann=8,-1,0
  3722.6    0.07       0  3759.8    0.12       0  3987.9    0.16       0
  4154.3   0.033       0  5763.9    0.12       0  5774.9   0.033       0
  5793.1    0.12       0  5962.5    0.07       0
Bank Sta=5774.9,5793.1
Exp/Cntr=0.3,0.1

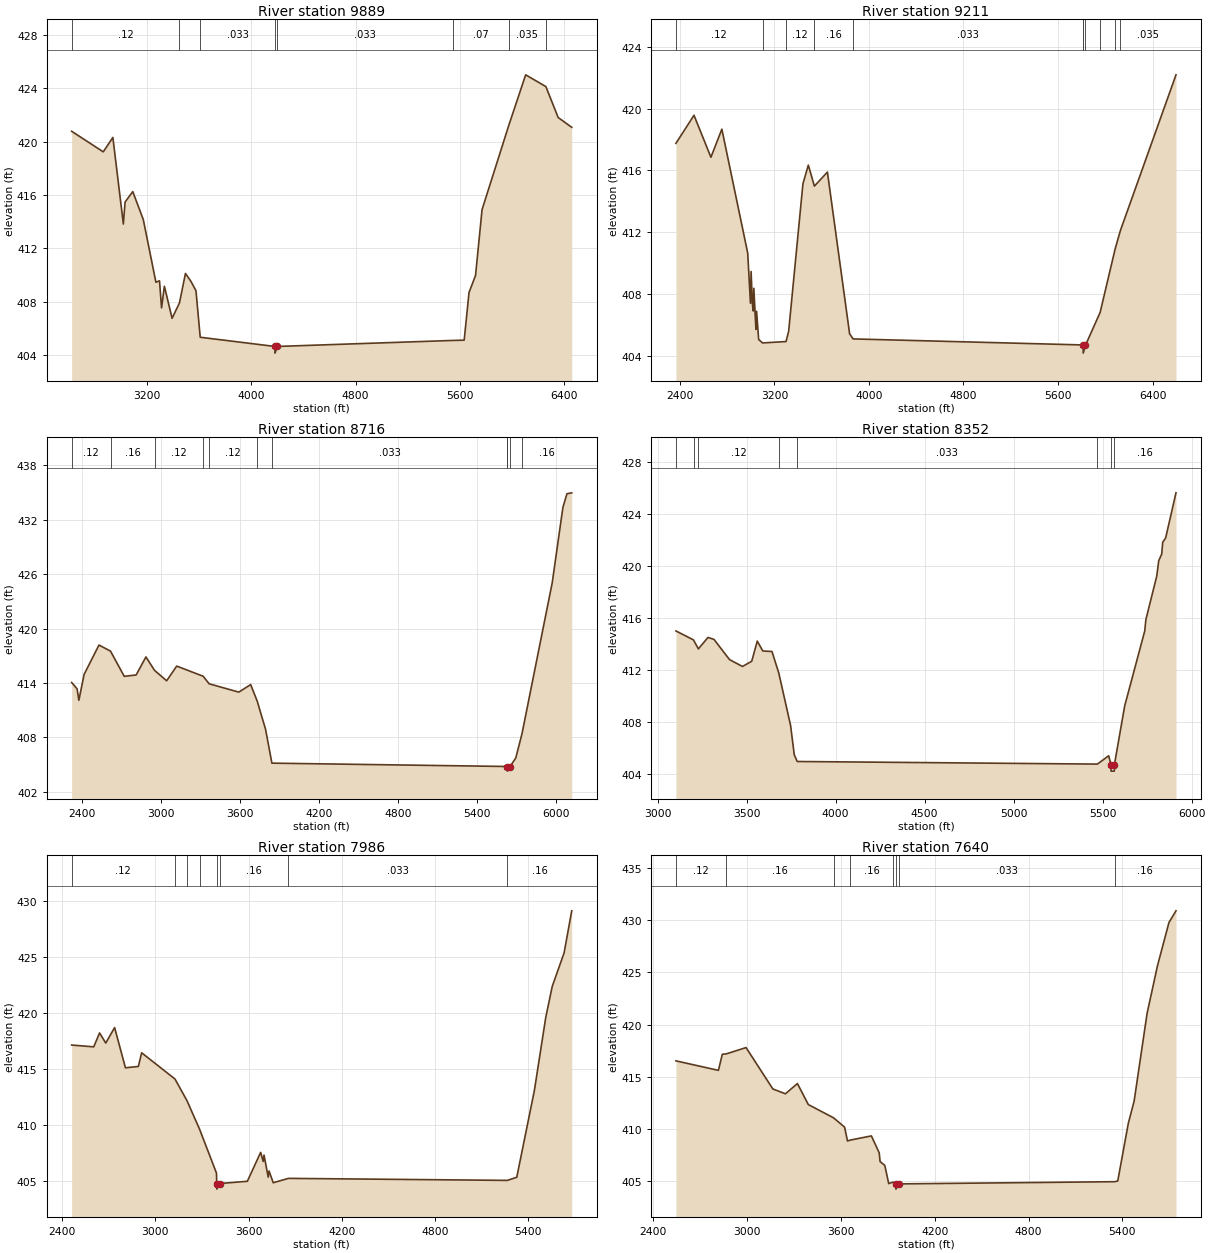
Type RM Length L Ch R = 1,9889,678,678,678
BEGIN DESCRIPTION:
Purtis Creek9888.62
END DESCRIPTION:
XS GIS Cut Line= 3
      2745001.03      6824685.98      2742931.64      6825858.35
      2742046.92      6827017.49
#Sta/Elev= 30
  2621.6  420.78  2864.0  419.24  2937.7  420.32  3018.2  413.83  3031.4  415.48
  3090.5  416.26  3171.3  414.16  3268.0  409.47  3295.4  409.58  3311.3  407.55
  3333.0  409.17  3392.1  406.77  3448.6  407.92  3494.6  410.13  3537.8  409.52
  3575.4  408.83  3607.9  405.35  4180.9  404.66  4181.4  404.16  4200.0  404.66
  5544.0  405.11  5633.0  405.13  5670.1  408.70  5720.2  409.98  5770.1  414.91
  5975.5  421.23  6104.7  425.01  6259.8  424.13  6354.1  421.81  6458.2  421.08
#Mann=8,-1,0
  2621.6    0.12       0  3448.6    0.16       0  3607.9   0.033       0
  4180.9   0.033       0  4200.0   0.033       0  5544.0    0.07       0
  5975.5   0.035       0  6259.8    0.07       0
Bank Sta=4180.9,4200
Exp/Cntr=0.3,0.1

Type RM Length L Ch R = 1,9211,495,495,495
BEGIN DESCRIPTION:
Purtis Creek9210.979
END DESCRIPTION:
XS GIS Cut Line= 3
      2744775.35      6824425.94      2742376.00      6825511.00
      2741325.54      6826716.02
#Sta/Elev= 30
  2366.7  417.75  2519.6  419.57  2662.9  416.85  2755.4  418.67  2974.3  410.64
  2997.4  407.39  3002.9  409.45  3013.5  407.37  3020.6  406.89  3026.0  408.36
  3043.7  405.70  3049.2  406.87  3066.8  405.04  3100.1  404.82  3298.3  404.91
  3320.8  405.58  3441.5  415.13  3487.1  416.34  3538.5  414.98  3648.8  415.89
  3836.6  405.41  3866.0  405.08  5809.8  404.69  5813.0  404.66  5813.5  404.16
  5832.1  404.66  5956.7  406.80  6084.0  410.92  6128.4  412.11  6598.6  422.19
#Mann=11,-1,0
  2366.7    0.12       0  3100.1    0.16       0  3298.3    0.12       0
  3538.5    0.16       0  3866.0   0.033       0  5809.8    0.07       0
  5813.0   0.033       0  5832.1    0.07       0  5956.7    0.12       0
  6084.0    0.07       0  6128.4   0.035       0
Bank Sta=5813,5832.1
Exp/Cntr=0.3,0.1

Type RM Length L Ch R = 1,8716,364,364,364
BEGIN DESCRIPTION:
Purtis Creek8716
END DESCRIPTION:
XS GIS Cut Line= 3
      2744432.95      6823993.45      2742026.00      6825161.00
      2741026.01      6825660.99
#Sta/Elev= 30
  2324.8  414.05  2365.9  413.35  2379.5  412.09  2419.1  414.94  2531.9  418.18
  2619.4  417.51  2723.6  414.73  2813.9  414.88  2888.2  416.87  2953.3  415.39
  3045.2  414.24  3121.6  415.86  3322.2  414.74  3367.4  413.91  3592.4  412.99
  3682.7  413.82  3732.3  411.99  3795.6  408.89  3843.6  405.16  5628.2  404.79
  5628.5  404.79  5630.5  404.78  5631.0  404.28  5649.6  404.78  5693.2  405.72
  5740.2  408.37  5969.9  425.04  6050.9  433.34  6081.7  434.86  6118.0  434.96
#Mann=12,-1,0
  2324.8    0.12       0  2619.4    0.16       0  2953.3    0.12       0
  3322.2    0.16       0  3367.4    0.12       0  3732.3    0.16       0
  3843.6   0.033       0  5628.2    0.16       0  5628.5    0.12       0
  5630.5   0.033       0  5649.6    0.12       0  5740.2    0.16       0
Bank Sta=5630.5,5649.6
Exp/Cntr=0.3,0.1

Type RM Length L Ch R = 1,8352,366,366,366
BEGIN DESCRIPTION:
Purtis Creek8352.407
END DESCRIPTION:
XS GIS Cut Line= 3
      2743625.45      6824367.16      2741801.00      6824886.00
      2740989.68      6825302.78
#Sta/Elev= 30
  3103.2  415.02  3201.9  414.33  3229.4  413.64  3283.2  414.52  3317.0  414.37
  3404.1  412.82  3476.9  412.29  3528.9  412.69  3560.1  414.24  3591.3  413.48
  3642.7  413.44  3681.1  411.78  3747.2  407.76  3768.0  405.50  3784.7  404.99
  5470.7  404.79  5534.0  405.43  5546.8  404.75  5547.3  404.25  5565.7  404.25
  5566.2  404.75  5623.9  409.26  5736.4  415.01  5743.0  415.89  5803.8  419.22
  5815.2  420.42  5831.8  420.92  5837.5  421.83  5853.9  422.16  5912.1  425.63
#Mann=8,-1,0
  3103.2    0.12       0  3201.9    0.16       0  3229.4    0.12       0
  3681.1    0.16       0  3784.7   0.033       0  5470.7    0.16       0
  5546.8   0.033       0  5566.2    0.16       0
Bank Sta=5546.8,5566.2
Exp/Cntr=0.3,0.1

Type RM Length L Ch R = 1,7986,346,346,346
BEGIN DESCRIPTION:
Purtis Creek7986.16
END DESCRIPTION:
XS GIS Cut Line= 3
      2743995.20      6823842.60      2741576.00      6824611.00
      2740925.97      6824811.01
#Sta/Elev= 30
  2461.7  417.16  2603.8  417.00  2641.3  418.24  2681.2  417.34  2738.1  418.72
  2807.8  415.13  2891.0  415.25  2912.0  416.47  3126.6  414.13  3203.3  412.21
  3284.9  409.65  3393.7  405.73  3395.4  404.80  3395.9  404.30  3414.9  404.80
  3592.4  405.00  3678.0  407.58  3694.4  406.77  3699.7  407.34  3726.7  405.37
  3731.9  405.92  3759.0  404.87  3857.0  405.26  5266.1  405.08  5326.3  405.36
  5439.4  413.08  5512.7  419.61  5554.5  422.39  5631.0  425.39  5680.1  429.14
#Mann=8,-1,0
  2461.7    0.12       0  3126.6    0.16       0  3203.3    0.12       0
  3284.9    0.16       0  3395.4   0.033       0  3414.9    0.16       0
  3857.0   0.033       0  5266.1    0.16       0
Bank Sta=3395.4,3414.9
Exp/Cntr=0.3,0.1

Type RM Length L Ch R = 1,7640,486,486,486
BEGIN DESCRIPTION:
Purtis Creek7640.083
END DESCRIPTION:
XS GIS Cut Line= 3
      2743733.82      6823460.57      2741434.13      6824317.06
      2740775.99      6824661.01
#Sta/Elev= 30
  2546.0  416.53  2817.6  415.62  2842.5  417.16  2868.9  417.20  2994.3  417.80
  3165.6  413.84  3245.9  413.38  3322.7  414.36  3392.2  412.35  3553.6  411.08
  3624.2  410.19  3642.8  408.86  3660.1  408.95  3795.5  409.35  3845.5  407.73
  3850.9  406.90  3881.2  406.53  3906.2  404.79  3934.1  404.93  3951.8  404.76
  3952.3  404.26  3971.3  404.76  5350.6  404.97  5370.3  405.04  5437.9  410.56
  5475.1  412.69  5557.7  421.06  5624.0  425.61  5697.5  429.76  5742.6  430.88
#Mann=8,-1,0
  2546.0    0.12       0  2868.9    0.16       0  3553.6    0.12       0
  3660.1    0.16       0  3934.1   0.033       0  3951.8   0.033       0
  3971.3   0.033       0  5350.6    0.16       0
Bank Sta=3951.8,3971.3
Exp/Cntr=0.3,0.1

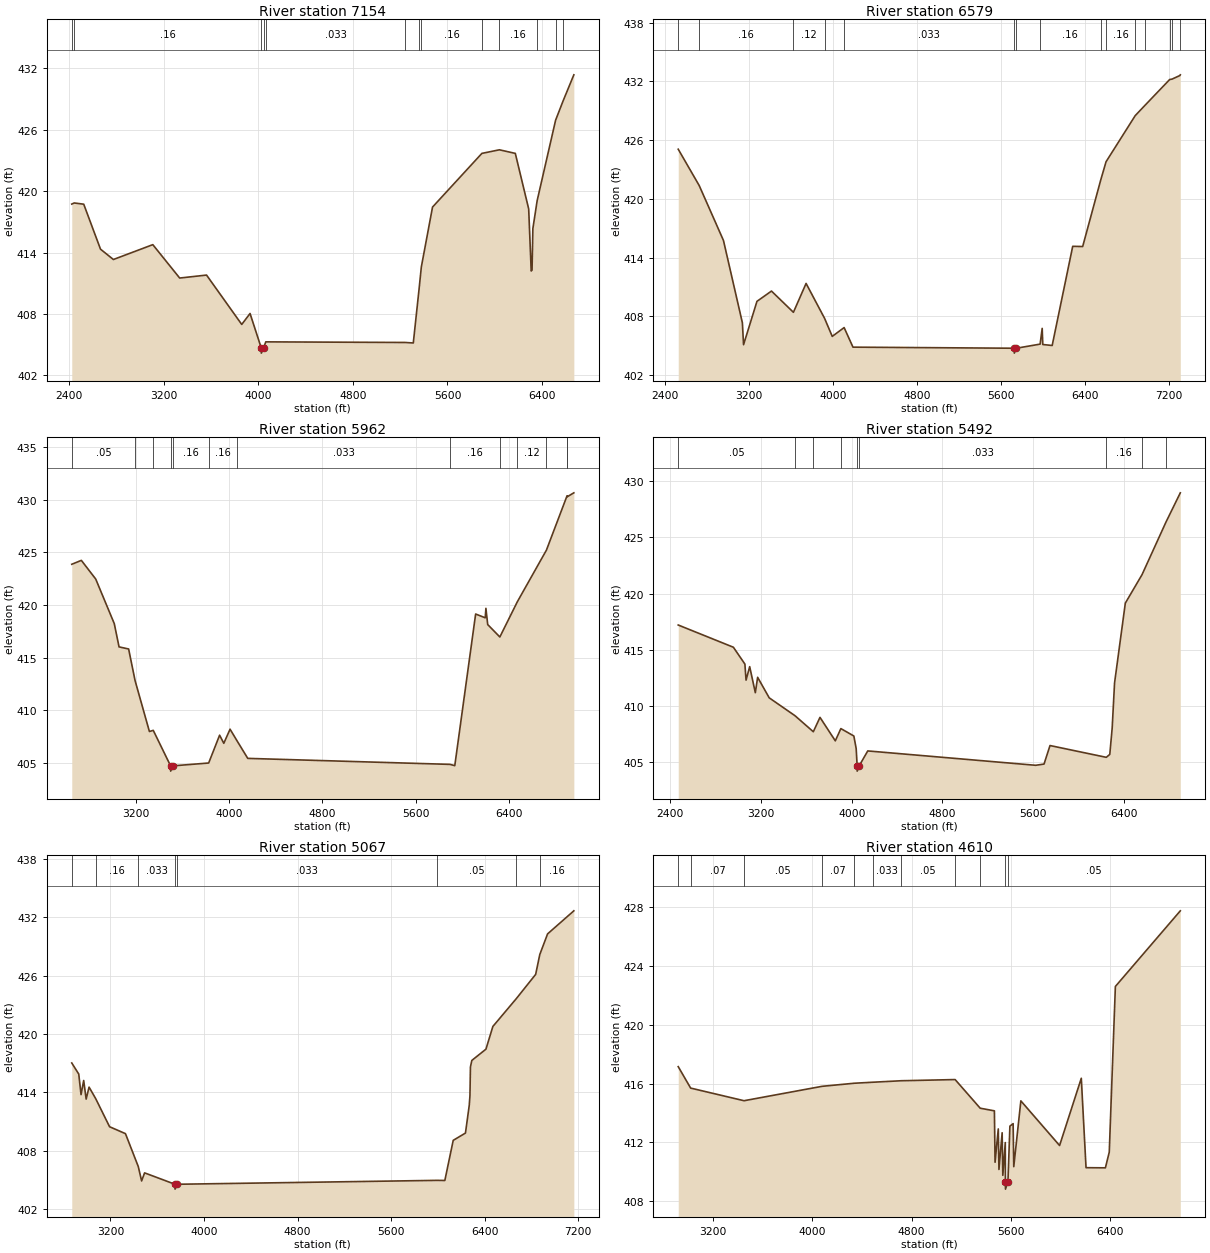
Type RM Length L Ch R = 1,7154,575,575,575
BEGIN DESCRIPTION:
Purtis Creek7153.878
END DESCRIPTION:
XS GIS Cut Line= 3
      2743618.76      6822862.09      2741255.70      6823891.13
      2740070.15      6825065.17
#Sta/Elev= 30
  2422.6  418.73  2442.9  418.84  2523.8  418.72  2665.6  414.33  2774.6  413.32
  3108.0  414.77  3335.2  411.51  3562.4  411.80  3860.0  406.98  3930.3  408.05
  4025.1  404.68  4025.6  404.18  4044.6  404.68  4063.2  405.28  5243.0  405.22
  5310.8  405.17  5359.7  410.44  5378.9  412.60  5473.5  418.44  5890.8  423.68
  6039.1  424.03  6173.5  423.68  6286.6  418.26  6307.9  412.20  6314.9  412.28
  6322.0  416.34  6358.3  419.07  6514.3  426.92  6577.2  428.79  6668.5  431.35
#Mann=13,-1,0
  2422.6    0.12       0  2442.9    0.16       0  4025.1   0.033       0
  4044.6    0.16       0  4063.2   0.033       0  5243.0    0.16       0
  5359.7    0.12       0  5378.9    0.16       0  5890.8    0.12       0
  6039.1    0.16       0  6358.3    0.12       0  6514.3    0.16       0
  6577.2    0.12       0
Bank Sta=4025.1,4044.6
Exp/Cntr=0.3,0.1

Type RM Length L Ch R = 1,6579,617,617,617
BEGIN DESCRIPTION:
Purtis Creek6579.012
END DESCRIPTION:
XS GIS Cut Line= 3
      2743501.04      6822535.99      2741175.96      6823379.33
      2739109.89      6824412.30
#Sta/Elev= 30
  2526.7  425.08  2726.5  421.37  2957.6  415.76  3137.8  407.35  3149.0  405.11
  3276.7  409.54  3415.0  410.59  3624.0  408.42  3744.7  411.37  3920.7  407.81
  3993.9  405.96  4107.1  406.86  4191.5  404.86  5728.0  404.75  5728.5  404.25
  5747.6  404.75  5974.4  405.17  5994.1  406.78  5999.7  405.13  6089.2  405.03
  6284.8  415.16  6379.8  415.14  6550.3  421.88  6602.4  423.80  6880.2  428.51
  6970.2  429.53  7208.6  432.20  7230.5  432.24  7306.1  432.61  7309.9  432.68
#Mann=15,-1,0
  2526.7    0.12       0  2726.5    0.16       0  3624.0    0.12       0
  3920.7    0.16       0  4107.1   0.033       0  5728.0   0.033       0
  5747.6   0.033       0  5974.4    0.16       0  6550.3    0.07       0
  6602.4    0.16       0  6880.2    0.07       0  6970.2    0.16       0
  7208.6    0.07       0  7230.5    0.16       0  7306.1    0.07       0
Bank Sta=5728,5747.6
Exp/Cntr=0.3,0.1

Type RM Length L Ch R = 1,5962,470,470,470
BEGIN DESCRIPTION:
Purtis Creek5962.422
END DESCRIPTION:
XS GIS Cut Line= 3
      2743401.04      6822235.99      2741126.00      6822811.00
      2739476.03      6823860.98
#Sta/Elev= 30
  2653.5  423.87  2735.6  424.24  2858.7  422.47  3017.7  418.24  3058.7  416.03
  3140.8  415.83  3195.8  412.84  3318.8  408.00  3351.8  408.11  3500.2  404.74
  3500.7  404.24  3519.9  404.74  3826.6  405.01  3920.4  407.65  3956.3  406.88
  4009.9  408.22  4070.7  407.10  4161.5  405.45  5895.0  404.88  5935.6  404.76
  6114.3  419.15  6196.4  418.79  6202.3  419.69  6217.6  418.15  6321.7  416.97
  6472.0  420.32  6720.8  425.21  6897.7  430.37  6899.6  430.28  6955.8  430.65
#Mann=13,-1,0
  2653.5    0.05       0  3195.8    0.12       0  3351.8    0.16       0
  3500.2   0.033       0  3519.9    0.16       0  3826.6    0.16       0
  4070.7   0.033       0  5895.0    0.16       0  6321.7    0.07       0
  6472.0    0.12       0  6720.8    0.16       0  6897.7    0.07       0
  6899.6    0.16       0
Bank Sta=3500.2,3519.9
Exp/Cntr=0.3,0.1

Type RM Length L Ch R = 1,5492,425,425,425
BEGIN DESCRIPTION:
Purtis Creek5491.959
END DESCRIPTION:
XS GIS Cut Line= 3
      2743400.96      6821886.01      2740926.00      6822411.00
      2739125.99      6823011.00
#Sta/Elev= 30
  2470.0  417.20  2956.3  415.22  3057.8  413.72  3068.0  412.29  3100.1  413.49
  3149.8  411.17  3170.2  412.54  3272.4  410.71  3499.5  409.12  3661.2  407.69
  3720.0  408.97  3855.1  406.88  3904.2  407.97  4018.7  407.31  4039.1  406.19
  4047.5  404.68  4048.0  404.18  4067.2  404.68  4141.3  405.98  5621.9  404.70
  5695.7  404.81  5748.4  406.46  6244.5  405.41  6275.5  405.67  6296.6  408.02
  6317.6  412.04  6412.5  419.15  6560.0  421.69  6770.4  426.36  6897.4  428.98
#Mann=9,-1,0
  2470.0    0.05       0  3499.5    0.07       0  3661.2    0.05       0
  3904.2   0.033       0  4047.5   0.033       0  4067.2   0.033       0
  6244.5    0.16       0  6560.0    0.12       0  6770.4    0.16       0
Bank Sta=4047.5,4067.2
Exp/Cntr=0.3,0.1

Type RM Length L Ch R = 1,5067,457,457,457
BEGIN DESCRIPTION:
Purtis Creek5066.947
END DESCRIPTION:
XS GIS Cut Line= 4
      2742742.67      6821389.76      2740726.00      6822061.00
      2739493.17      6822427.94      2738762.97      6822920.27
#Sta/Elev= 30
  2870.0  417.02  2929.7  415.88  2949.3  413.77  2971.9  415.22  2993.0  413.31
  3017.9  414.54  3074.4  413.36  3193.2  410.47  3329.0  409.76  3438.6  406.38
  3467.2  404.90  3492.5  405.73  3752.5  404.56  3753.0  404.06  3772.2  404.56
  5990.4  404.96  6059.5  404.95  6131.1  409.07  6235.8  409.82  6268.3  412.68
  6274.2  413.66  6278.3  416.60  6290.2  417.28  6411.0  418.44  6470.1  420.77
  6671.2  423.64  6836.0  426.12  6871.2  428.16  6937.9  430.28  7162.4  432.65
#Mann=8,-1,0
  2870.0    0.05       0  3074.4    0.16       0  3438.6   0.033       0
  3752.5   0.033       0  3772.2   0.033       0  5990.4    0.05       0
  6671.2    0.07       0  6871.2    0.16       0
Bank Sta=3752.5,3772.2
Exp/Cntr=0.3,0.1

Type RM Length L Ch R = 1,4610,271,271,271
BEGIN DESCRIPTION:
Purtis Creek4609.56
END DESCRIPTION:
XS GIS Cut Line= 3
      2742534.06      6821125.91      2740497.77      6821671.34
      2738660.55      6822302.86
#Sta/Elev= 30
  2917.7  417.16  3017.8  415.70  3448.5  414.84  4077.8  415.82  4337.9  416.03
  4490.0  416.10  4717.0  416.20  5151.7  416.28  5354.0  414.33  5468.6  414.15
  5473.9  410.65  5499.9  412.92  5505.2  410.16  5531.1  412.66  5536.4  409.76
  5556.4  411.99  5557.4  409.32  5557.9  408.82  5577.8  409.32  5593.6  413.11
  5619.6  413.28  5624.8  410.35  5682.0  414.83  5994.5  411.79  6169.7  416.37
  6207.9  410.28  6364.1  410.27  6395.3  411.34  6444.6  422.62  6968.5  427.77
#Mann=11,-1,0
  2917.7    0.05       0  3017.8    0.07       0  3448.5    0.05       0
  4077.8    0.07       0  4337.9    0.05       0  4490.0   0.033       0
  4717.0    0.05       0  5151.7   0.033       0  5354.0    0.05       0
  5557.4    0.05       0  5577.8    0.05       0
Bank Sta=5557.4,5577.8
Exp/Cntr=0.3,0.1