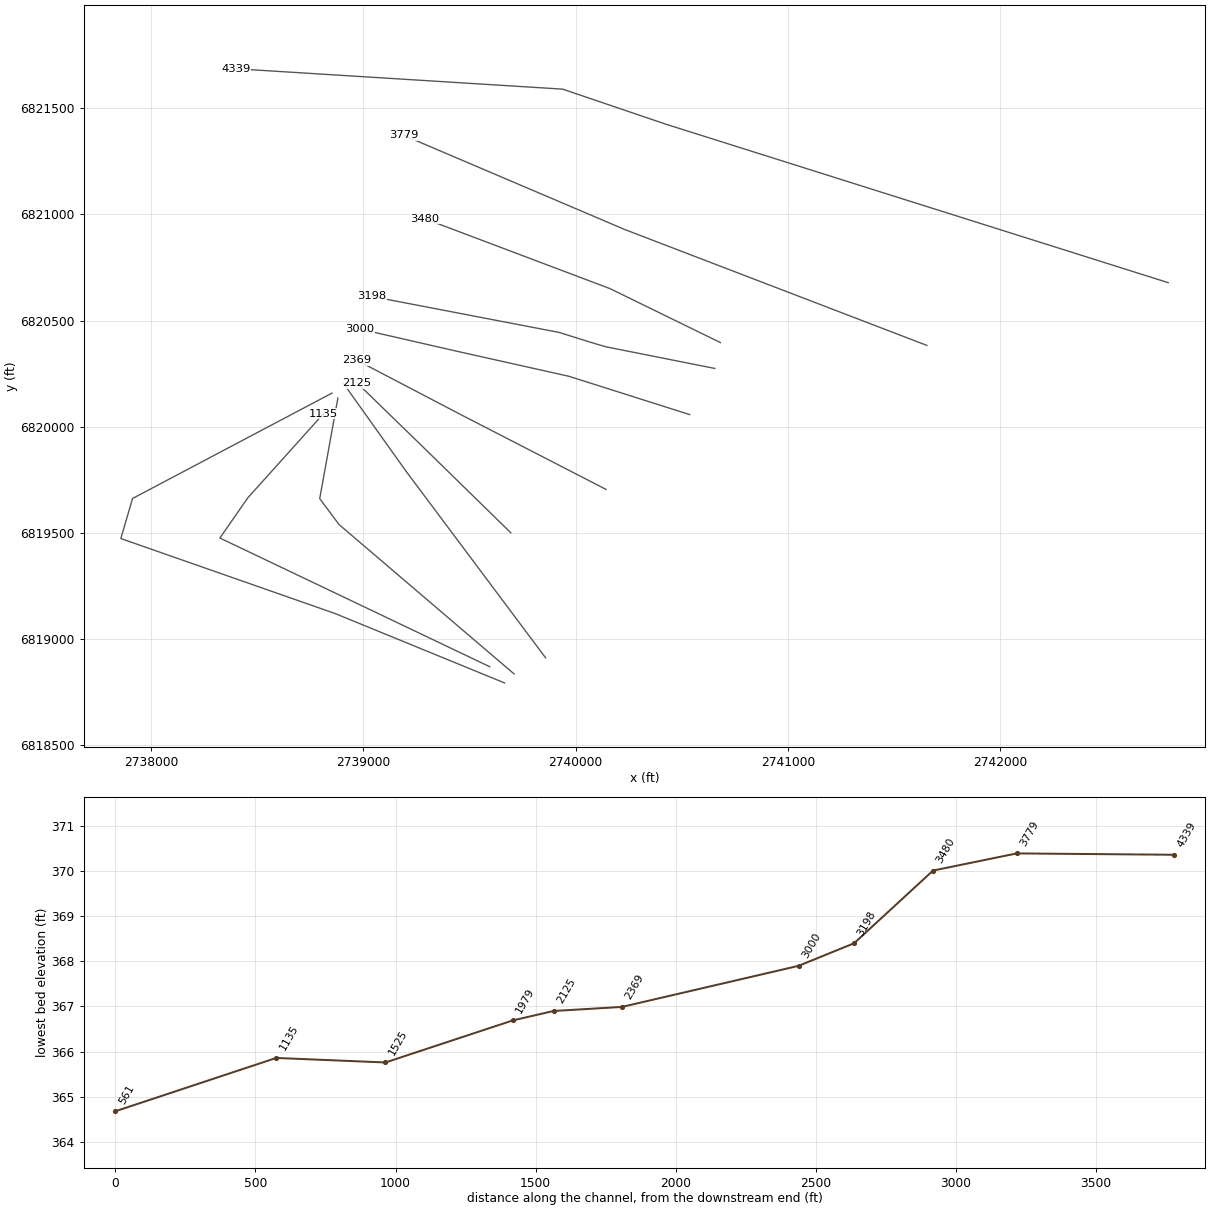
HEC-RAS study Purtis Creek.prj: Purtis Creek Base Level Engineering

--- Purtis Creek.g01 (geometry) --- (continued)

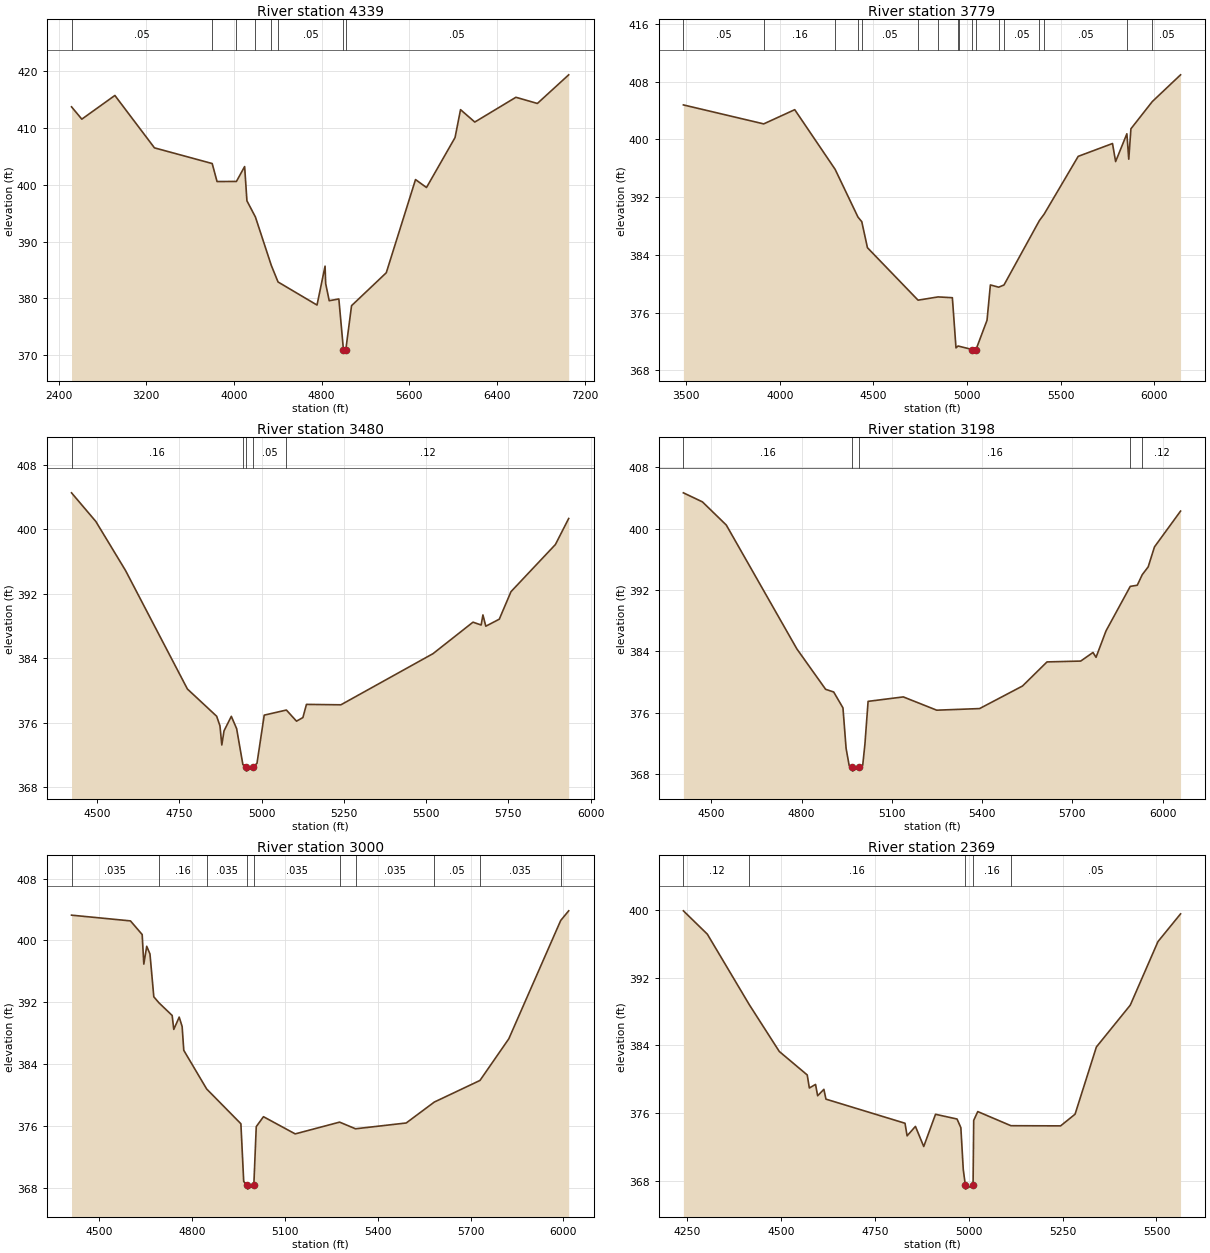
Type RM Length L Ch R = 1,4339,560,560,560
BEGIN DESCRIPTION:
Purtis Creek4338.668
END DESCRIPTION:
XS GIS Cut Line= 4
      2742792.54      6820678.31      2740425.20      6821424.97
      2739939.19      6821590.14      2738400.99      6821686.00
#Sta/Elev= 30
  2517.7  413.70  2611.7  411.53  2913.4  415.70  3274.5  406.48  3801.4  403.72
  3845.7  400.55  4022.5  400.57  4097.4  403.19  4118.4  397.16  4195.7  394.32
  4340.9  385.79  4402.3  382.88  4758.0  378.82  4831.4  385.67  4836.9  382.60
  4869.3  379.58  4957.2  379.89  4999.5  370.86  5000.0  370.36  5020.0  370.86
  5073.1  378.71  5389.9  384.50  5656.8  400.90  5757.0  399.50  6017.5  408.29
  6067.6  413.20  6197.8  411.02  6572.9  415.38  6768.9  414.29  7054.5  419.33
#Mann=8,-1,0
  2517.7    0.05       0  3801.4   0.033       0  4022.5    0.07       0
  4195.7    0.05       0  4340.9    0.07       0  4402.3    0.05       0
  4999.5    0.05       0  5020.0    0.05       0
Bank Sta=4999.5,5020
Exp/Cntr=0.3,0.1

Type RM Length L Ch R = 1,3779,299,299,299
BEGIN DESCRIPTION:
Purtis Creek3779.13
END DESCRIPTION:
XS GIS Cut Line= 3
      2741655.31      6820382.68      2740231.07      6820928.92
      2739191.57      6821371.78
#Sta/Elev= 30
  3485.0  404.79  3914.0  402.16  4079.7  404.13  4295.5  395.86  4417.3  389.25
  4437.7  388.61  4468.0  385.00  4738.3  377.73  4845.3  378.18  4921.6  378.07
  4940.9  371.12  4952.3  371.38  4956.2  371.35  5027.4  370.89  5027.9  370.39
  5047.9  370.89  5106.7  374.95  5124.6  379.84  5168.7  379.53  5197.2  379.83
  5386.1  388.75  5411.9  389.66  5593.6  397.66  5776.8  399.44  5793.5  396.94
  5853.6  400.79  5863.7  397.27  5875.2  401.48  5989.2  405.25  6140.3  408.96
#Mann=17,-1,0
  3485.0    0.05       0  3914.0    0.16       0  4295.5    0.12       0
  4417.3    0.16       0  4437.7    0.05       0  4738.3    0.07       0
  4845.3    0.16       0  4952.3    0.12       0  4956.2    0.16       0
  5027.4    0.07       0  5047.9    0.16       0  5168.7    0.12       0
  5197.2    0.05       0  5386.1    0.16       0  5411.9    0.05       0
  5853.6    0.07       0  5989.2    0.05       0
Bank Sta=5027.4,5047.9
Exp/Cntr=0.3,0.1

Type RM Length L Ch R = 1,3480,282,282,282
BEGIN DESCRIPTION:
Mapping XS e93389c7
END DESCRIPTION:
XS GIS Cut Line= 3
      2740682.36      6820396.07      2740161.77      6820650.39
      2739290.33      6820979.20
#Sta/Elev= 30
  4422.6  404.50  4496.5  400.95  4586.5  394.89  4774.7  380.19  4863.7  376.81
  4873.7  375.62  4879.3  373.25  4886.0  375.00  4908.2  376.80  4924.3  375.28
  4943.3  370.83  4953.5  370.51  4954.0  370.01  4974.0  370.51  4986.2  370.98
  5008.2  376.95  5075.6  377.58  5106.3  376.20  5125.7  376.65  5136.5  378.28
  5241.2  378.23  5521.2  384.57  5642.6  388.47  5667.4  388.12  5672.8  389.37
  5681.5  387.97  5722.5  388.84  5758.0  392.25  5893.0  398.09  5933.4  401.32
#Mann=5,-1,0
  4422.6    0.16       0  4943.3    0.05       0  4953.5    0.07       0
  4974.0    0.05       0  5075.6    0.12       0
Bank Sta=4953.5,4974
Exp/Cntr=0.3,0.1

Type RM Length L Ch R = 1,3198,198,198,198
BEGIN DESCRIPTION:
Mapping XS f7e99890
END DESCRIPTION:
XS GIS Cut Line= 5
      2740655.87      6820274.22      2740141.83      6820376.29
      2740076.69      6820395.53      2739922.66      6820443.82
      2739040.28      6820613.18
#Sta/Elev= 30
  4407.5  404.66  4470.8  403.48  4550.1  400.46  4784.6  384.32  4880.1  379.06
  4906.9  378.71  4937.7  376.64  4948.1  371.37  4958.5  369.09  4969.1  368.90
  4969.6  368.40  4989.7  368.90  5003.3  369.15  5010.7  371.93  5021.2  377.49
  5138.2  378.07  5249.2  376.34  5391.7  376.55  5534.3  379.49  5615.7  382.63
  5727.7  382.74  5768.5  383.86  5778.6  383.23  5811.7  386.67  5892.3  392.47
  5915.6  392.62  5932.0  393.99  5951.8  395.01  5972.7  397.61  6059.4  402.28
#Mann=5,-1,0
  4407.5    0.16       0  4969.1    0.07       0  4989.7    0.16       0
  5892.3    0.05       0  5932.0    0.12       0
Bank Sta=4969.1,4989.7
Exp/Cntr=0.3,0.1

Type RM Length L Ch R = 1,3000,631,631,631
BEGIN DESCRIPTION:
Mapping XS ca8ec9e4
END DESCRIPTION:
XS GIS Cut Line= 4
      2740537.53      6820056.67      2739968.74      6820237.10
      2739436.71      6820356.06      2738984.41      6820459.62
#Sta/Elev= 30
  4410.9  403.27  4601.3  402.53  4639.1  400.77  4644.4  396.95  4653.8  399.25
  4664.3  398.26  4676.7  392.73  4693.4  391.95  4736.0  390.32  4741.2  388.52
  4758.7  390.11  4768.2  388.89  4773.5  385.82  4847.4  380.83  4958.0  376.34
  4967.1  368.88  4979.2  368.40  4979.7  367.90  4999.8  368.40  5007.6  375.97
  5030.9  377.25  5133.4  375.03  5276.8  376.55  5328.3  375.69  5492.0  376.44
  5582.7  379.14  5730.2  381.93  5823.4  387.31  5991.0  402.58  6016.8  403.83
#Mann=10,-1,0
  4410.9   0.035       0  4693.4    0.16       0  4847.4   0.035       0
  4979.2   0.035       0  4999.8   0.035       0  5276.8    0.05       0
  5328.3   0.035       0  5582.7    0.05       0  5730.2   0.035       0
  5991.0    0.05       0
Bank Sta=4979.2,4999.8
Exp/Cntr=0.3,0.1

Type RM Length L Ch R = 1,2369,244,244,244
BEGIN DESCRIPTION:
Mapping XS 6d77c6a5
END DESCRIPTION:
XS GIS Cut Line= 3
      2740143.09      6819704.40      2739461.50      6820055.32
      2738967.30      6820313.74
#Sta/Elev= 30
  4239.9  399.90  4303.7  397.14  4415.6  388.79  4495.3  383.27  4569.8  380.49
  4575.4  378.95  4591.9  379.37  4597.5  378.03  4614.1  378.79  4619.7  377.63
  4830.2  374.78  4835.8  373.29  4858.0  374.41  4880.1  372.03  4911.5  375.84
  4968.8  375.28  4979.0  374.26  4985.4  369.32  4990.8  367.49  4991.3  366.99
  5011.5  367.49  5013.2  375.12  5024.0  376.16  5112.3  374.49  5244.7  374.47
  5283.2  375.85  5340.0  383.80  5430.3  388.75  5504.0  396.26  5564.2  399.54
#Mann=5,-1,0
  4239.9    0.12       0  4415.6    0.16       0  4990.8    0.07       0
  5011.5    0.16       0  5112.3    0.05       0
Bank Sta=4990.8,5011.5
Exp/Cntr=0.3,0.1

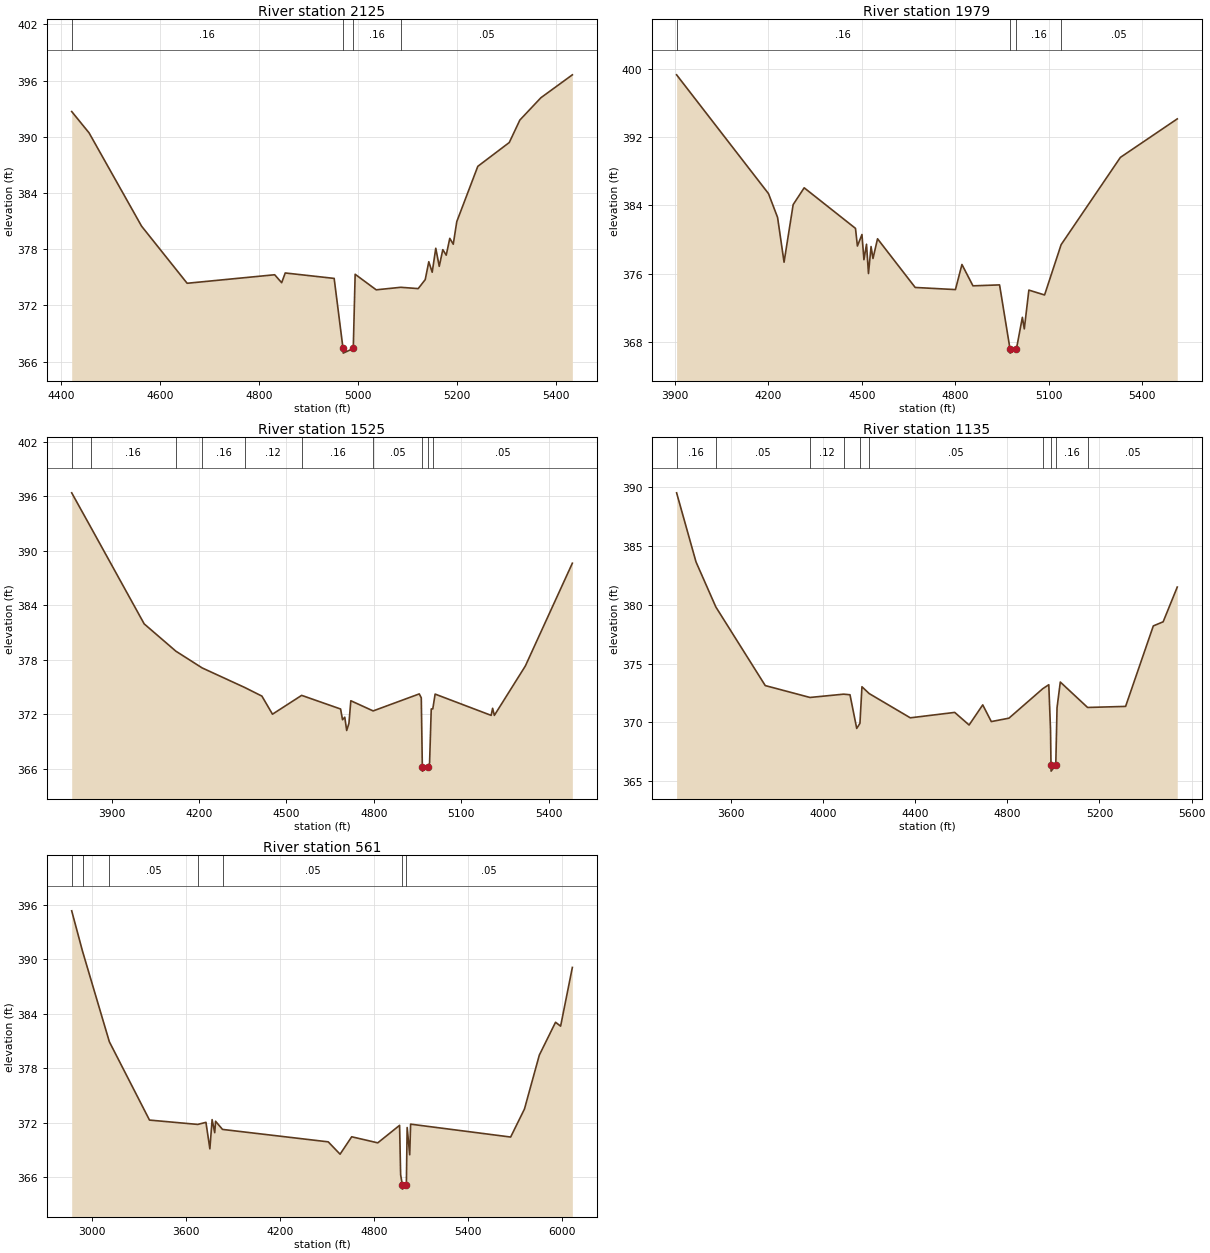
Type RM Length L Ch R = 1,2125,146,146,146
BEGIN DESCRIPTION:
Mapping XS 9c612a88
END DESCRIPTION:
XS GIS Cut Line= 3
      2739694.56      6819499.97      2739275.05      6819909.95
      2738970.67      6820205.74
#Sta/Elev= 30
  4421.5  392.70  4456.6  390.42  4562.6  380.46  4654.6  374.36  4831.4  375.27
  4845.5  374.42  4852.7  375.46  4951.5  374.88  4969.4  367.40  4969.9  366.90
  4990.1  367.40  4993.9  375.32  5036.4  373.66  5086.1  373.93  5121.2  373.79
  5135.4  374.75  5142.6  376.66  5149.5  375.54  5156.7  378.10  5163.7  376.17
  5170.9  377.95  5177.8  377.36  5185.0  379.16  5192.0  378.53  5199.1  380.94
  5241.6  386.85  5305.1  389.39  5326.5  391.79  5368.9  394.17  5432.5  396.62
#Mann=4,-1,0
  4421.5    0.16       0  4969.4    0.07       0  4990.1    0.16       0
  5086.1    0.05       0
Bank Sta=4969.4,4990.1
Exp/Cntr=0.3,0.1

Type RM Length L Ch R = 1,1979,454,454,454
BEGIN DESCRIPTION:
Mapping XS eee82590
END DESCRIPTION:
XS GIS Cut Line= 3
      2739858.54      6818910.85      2739202.93      6819787.15
      2738905.20      6820204.91
#Sta/Elev= 30
  3905.6  399.28  4200.6  385.37  4229.8  382.58  4250.6  377.34  4279.8  384.08
  4315.2  386.05  4479.9  381.30  4486.1  379.23  4500.7  380.58  4507.0  377.63
  4515.3  379.44  4521.6  376.01  4529.9  379.17  4536.1  377.77  4550.7  380.08
  4671.6  374.38  4800.8  374.13  4821.7  377.07  4857.1  374.57  4942.5  374.68
  4976.0  367.19  4976.5  366.69  4996.7  367.19  5015.7  370.88  5021.9  369.53
  5036.6  374.07  5087.0  373.50  5140.1  379.39  5330.4  389.61  5513.0  394.12
#Mann=4,-1,0
  3905.6    0.16       0  4976.0    0.07       0  4996.7    0.16       0
  5140.1    0.05       0
Bank Sta=4976,4996.7
Exp/Cntr=0.3,0.1

Type RM Length L Ch R = 1,1525,390,390,390
BEGIN DESCRIPTION:
Mapping XS b48ec383
END DESCRIPTION:
XS GIS Cut Line= 4
      2739710.37      6818834.62      2738885.12      6819538.88
      2738794.25      6819660.84      2738879.79      6820134.48
#Sta/Elev= 30
  3763.0  396.36  3828.3  392.59  4011.8  381.95  4120.5  378.95  4210.6  377.11
  4357.3  374.95  4415.8  374.01  4452.1  372.02  4552.2  374.09  4685.9  372.59
  4692.5  371.41  4700.2  371.69  4706.8  370.23  4714.5  371.01  4721.0  373.50
  4797.6  372.38  4955.9  374.25  4962.8  373.82  4966.4  366.26  4966.9  365.76
  4987.1  366.26  4991.3  366.68  4997.0  372.60  5002.3  372.60  5010.3  374.23
  5202.6  371.89  5207.6  372.67  5213.6  371.89  5319.8  377.31  5481.3  388.62
#Mann=10,-1,0
  3763.0    0.12       0  3828.3    0.16       0  4120.5    0.05       0
  4210.6    0.16       0  4357.3    0.12       0  4552.2    0.16       0
  4797.6    0.05       0  4966.4    0.07       0  4987.1    0.05       0
  5002.3    0.05       0
Bank Sta=4966.4,4987.1
Exp/Cntr=0.3,0.1

Type RM Length L Ch R = 1,1135,574,574,574
BEGIN DESCRIPTION:
Mapping XS 2c45055d
END DESCRIPTION:
XS GIS Cut Line= 5
      2739595.14      6818868.91      2738323.85      6819475.14
      2738455.34      6819664.42      2738584.71      6819808.29
      2738812.21      6820061.26
#Sta/Elev= 30
  3365.0  389.51  3449.2  383.64  3535.3  379.81  3749.7  373.13  3943.9  372.12
  4089.9  372.40  4117.4  372.35  4146.6  369.49  4160.6  369.92  4169.3  373.03
  4200.8  372.45  4379.1  370.39  4571.8  370.85  4634.3  369.78  4693.5  371.49
  4730.6  370.07  4807.2  370.36  4954.3  372.87  4980.1  373.20  4987.6  369.39
  4989.7  366.36  4990.2  365.86  5010.4  366.36  5015.9  371.25  5030.1  373.43
  5148.5  371.27  5313.4  371.36  5433.7  378.20  5476.4  378.55  5537.6  381.50
#Mann=10,-1,0
  3365.0    0.16       0  3535.3    0.05       0  3943.9    0.12       0
  4089.9    0.16       0  4160.6    0.12       0  4200.8    0.05       0
  4954.3    0.16       0  4989.7    0.07       0  5010.4    0.16       0
  5148.5    0.05       0
Bank Sta=4989.7,5010.4
Exp/Cntr=0.3,0.1

Type RM Length L Ch R = 1,561,0,0,0
BEGIN DESCRIPTION:
Purtis Creek2277.227
END DESCRIPTION:
XS GIS Cut Line= 5
      2739665.01      6818792.47      2738865.18      6819119.98
      2737857.17      6819472.72      2737912.18      6819661.43
      2738852.19      6820157.99
#Sta/Elev= 30
  2871.2  395.35  2940.2  390.90  3111.3  380.92  3367.2  372.29  3674.7  371.81
  3727.1  372.04  3752.1  369.12  3766.4  372.34  3783.1  370.90  3788.4  372.16
  3832.7  371.26  4506.7  369.89  4582.2  368.53  4656.3  370.45  4822.5  369.78
  4961.6  371.71  4968.3  366.27  4978.8  365.18  4979.3  364.68  4999.5  365.18
  5004.9  365.29  5009.9  371.47  5026.2  368.47  5031.9  371.84  5669.7  370.42
  5757.8  373.51  5852.5  379.45  5955.9  383.07  5988.2  382.64  6063.1  389.11
#Mann=7,-1,0
  2871.2    0.12       0  2940.2    0.16       0  3111.3    0.05       0
  3674.7    0.16       0  3832.7    0.05       0  4978.8    0.05       0
  4999.5    0.05       0
Bank Sta=4978.8,4999.5
Exp/Cntr=0.3,0.1

Chan Stop Cuts=-1