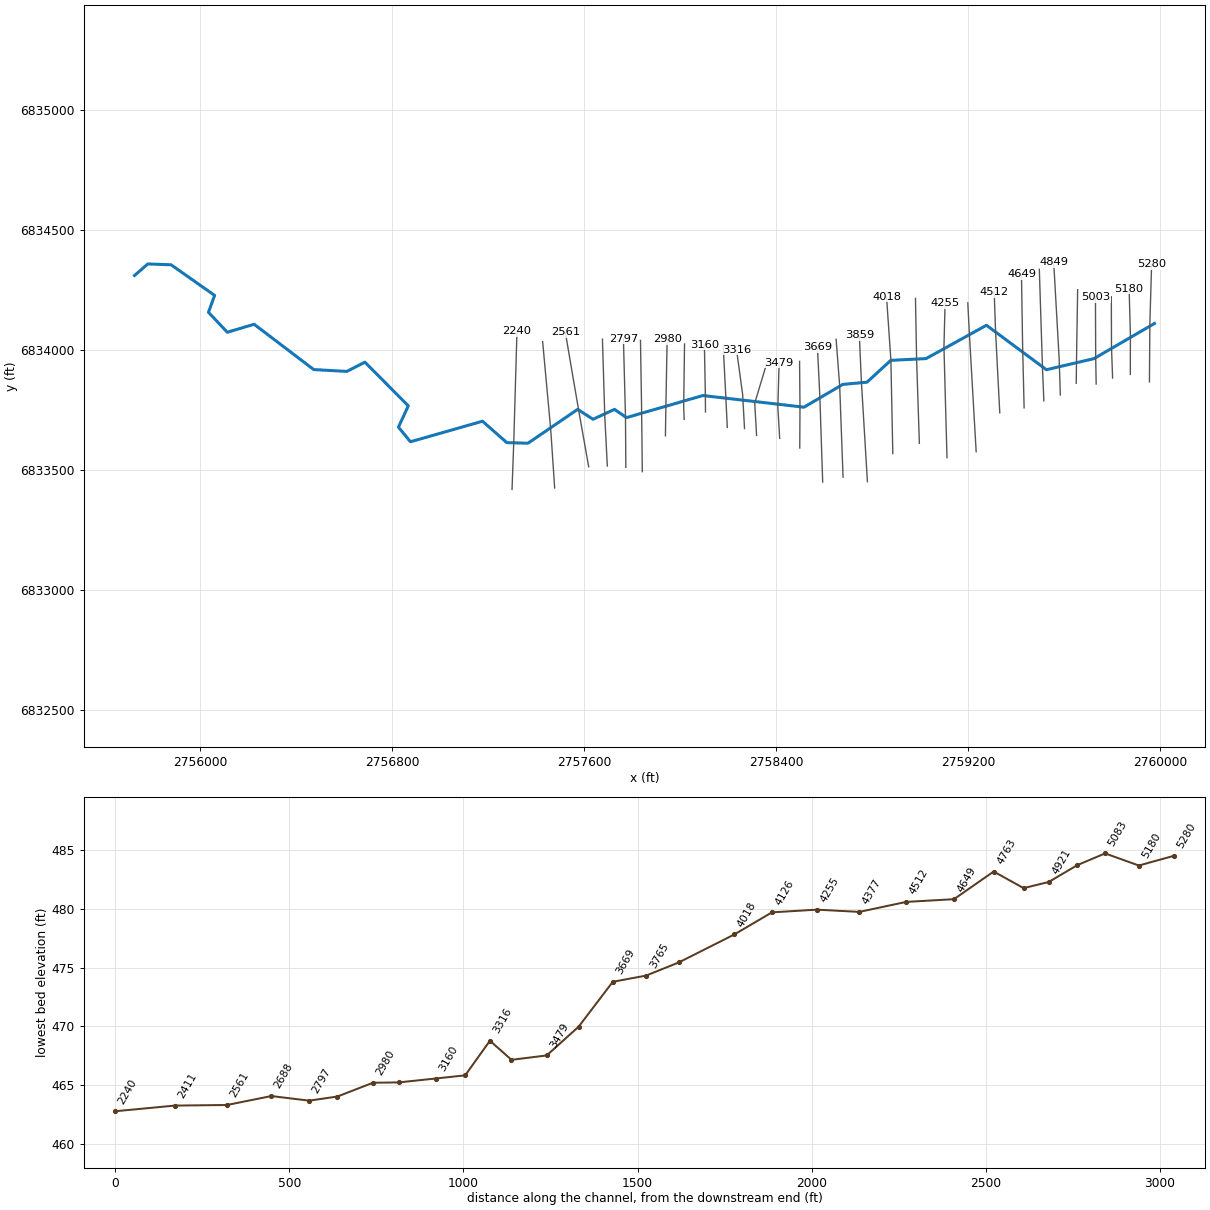
--- Purtis Creek Trib A.prj (project) ---

Proj Title=Purtis Creek Trib A Base Level Engineering
Current Plan=p01
Default Exp/Contr=0.3,0.1
English Units
Geom File=g01
Flow File=f01
Plan File=p01
BEGIN DESCRIPTION:
Purtis Creek Trib A
END DESCRIPTION:

--- Purtis Creek Trib A.p01 (plan) ---

Plan Title=Multiple Run
Short Identifier=Multiple
Geom File=g01
Flow File=f01
Subcritical Flow
K Sum by GR= 0
Std Step Tol= 0.01
Critical Tol= 0.01
Num of Std Step Trials= 20
Max Error Tol= 0.3
Flow Tol Ratio= 0.001
Split Flow NTrial= 30
Split Flow Tol= 0.02
Split Flow Ratio= 0.02
Log Output Level= 0
Friction Slope Method= 1
Unsteady Friction Slope Method= 2
Unsteady Bridges Friction Slope Method= 1
Parabolic Critical Depth
Global Vel Dist=  1 , 1 , 1
Global Log Level= 0
CheckData=True
Encroach Param= -1, 0, 0, 0
BEGIN DESCRIPTION:
Multiple Run
END DESCRIPTION:

--- Purtis Creek Trib A.f01 (steady flow) ---

Flow Title=Multiple
Number of Profiles=7
Profile Names=10-year,25-year,50-year,1pct_min,100-year,1pct_plu,500-year
River Rch & RM= Purtis Creek Tri,Reach-1,5280
     507     678     816     489     975    1945    1395
Boundary for River Rch & Prof#=Purtis Creek Tri,Reach-1,1
Up Type=0
Dn Type=3
Dn Slope=0.005
Boundary for River Rch & Prof#=Purtis Creek Tri,Reach-1,2
Up Type=0
Dn Type=3
Dn Slope=0.005
Boundary for River Rch & Prof#=Purtis Creek Tri,Reach-1,3
Up Type=0
Dn Type=3
Dn Slope=0.005
Boundary for River Rch & Prof#=Purtis Creek Tri,Reach-1,4
Up Type=0
Dn Type=3
Dn Slope=0.005
Boundary for River Rch & Prof#=Purtis Creek Tri,Reach-1,5
Up Type=0
Dn Type=3
Dn Slope=0.005
Boundary for River Rch & Prof#=Purtis Creek Tri,Reach-1,6
Up Type=0
Dn Type=3
Dn Slope=0.005
Boundary for River Rch & Prof#=Purtis Creek Tri,Reach-1,7
Up Type=0
Dn Type=3
Dn Slope=0.005

--- Purtis Creek Trib A.g01 (geometry) ---

Geom Title=Existing Conditions

River Reach=Purtis Creek Tri,Reach-1
Reach XY= 30
      2759976.00      6834111.00      2759724.44      6833964.76
      2759525.90      6833918.33      2759276.08      6834103.70
      2759024.44      6833964.76      2758877.47      6833957.44
      2758778.42      6833866.54      2758677.59      6833857.17
      2758515.50      6833762.20      2758094.27      6833810.79
      2757775.90      6833718.79      2757726.08      6833753.18
      2757636.64      6833711.99      2757572.60      6833753.17
      2757365.45      6833612.08      2757277.50      6833614.48
      2757176.10      6833703.67      2756875.62      6833618.23
      2756825.77      6833679.17      2756866.85      6833767.73
      2756686.05      6833949.89      2756610.64      6833911.29
      2756472.67      6833919.01      2756224.35      6834107.83
      2756112.57      6834074.54      2756034.01      6834157.65
      2756059.76      6834228.04      2755878.43      6834355.60
      2755781.42      6834359.13      2755726.00      6834311.00

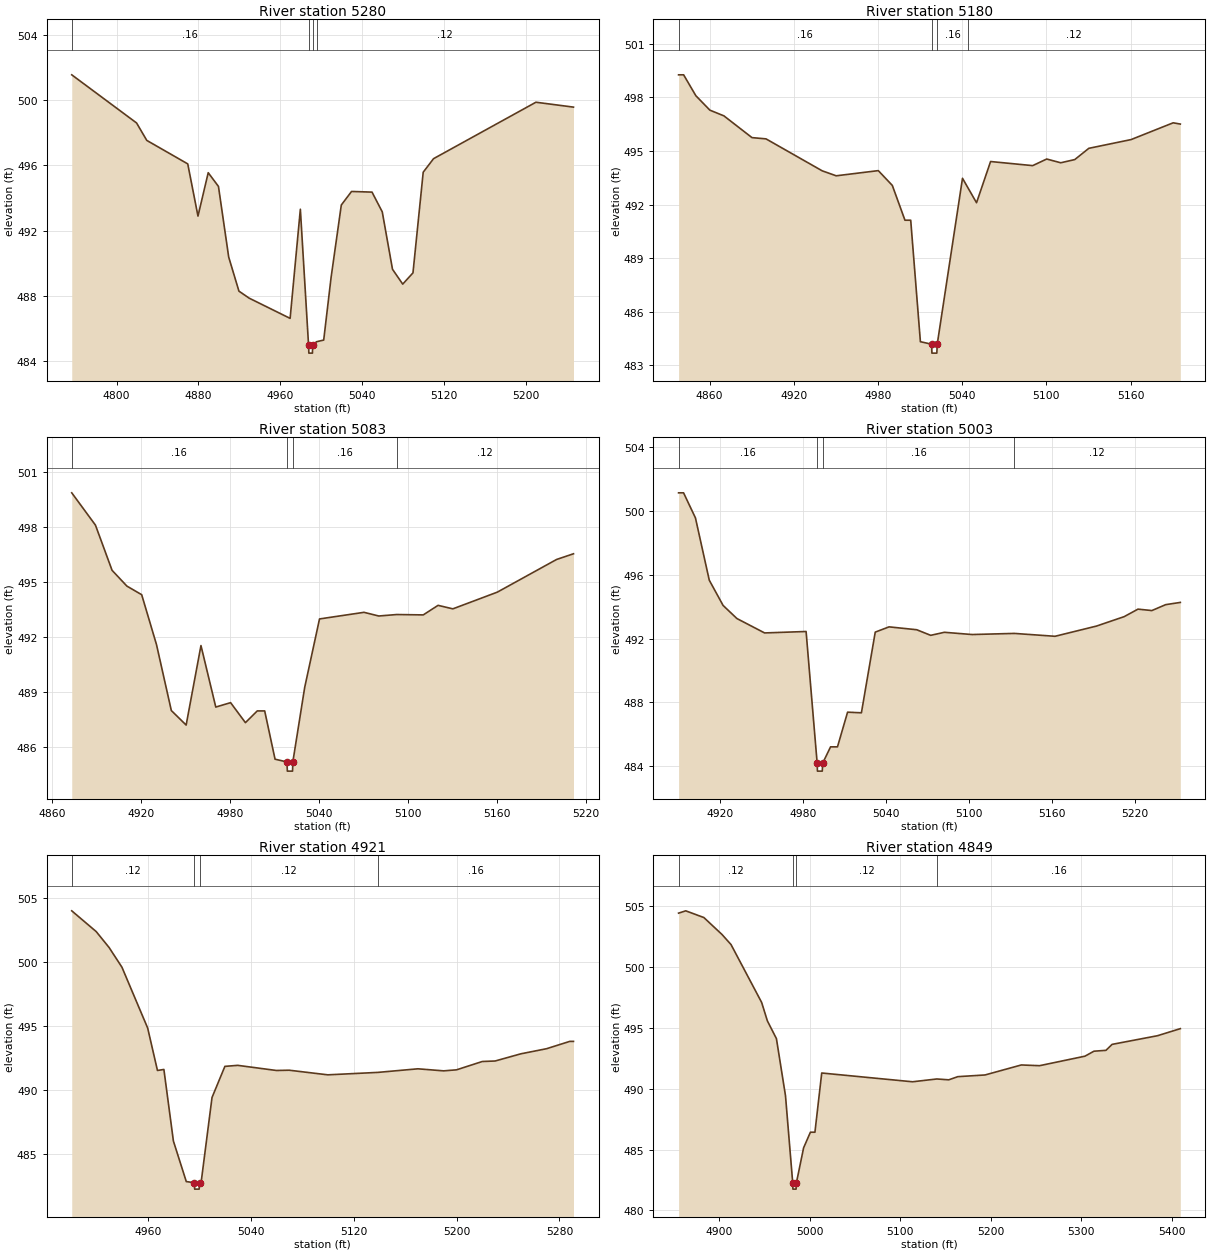
Type RM Length L Ch R = 1,5280,100,100,100
BEGIN DESCRIPTION:
Purtis Creek Trib A5279.939
END DESCRIPTION:
XS GIS Cut Line= 3
      2759955.24      6833867.70      2759957.04      6834111.50
      2759964.31      6834357.69
#Sta/Elev= 30
  4756.2  501.55  4819.5  498.60  4829.5  497.53  4869.5  496.09  4879.5  492.89
  4889.5  495.55  4899.5  494.71  4909.5  490.38  4919.5  488.29  4929.5  487.86
  4969.5  486.62  4979.5  493.31  4987.5  484.99  4987.8  484.49  4991.3  484.49
  4991.5  484.99  4995.4  485.19  5002.3  485.29  5009.5  489.12  5019.5  493.57
  5029.5  494.40  5049.5  494.36  5059.5  493.15  5069.5  489.63  5079.5  488.72
  5089.5  489.41  5099.5  495.58  5109.6  496.41  5209.6  499.87  5246.3  499.57
#Mann=4,-1,0
  4756.2    0.16       0  4987.5    0.07       0  4991.5    0.16       0
  4995.4    0.12       0
Bank Sta=4987.5,4991.5
Exp/Cntr=0.3,0.1

Type RM Length L Ch R = 1,5180,97,97,97
BEGIN DESCRIPTION:
Purtis Creek Trib A5179.96
END DESCRIPTION:
XS GIS Cut Line= 3
      2759875.56      6833898.71      2759875.93      6834064.09
      2759870.51      6834256.13
#Sta/Elev= 30
  4837.9  499.27  4841.5  499.27  4850.2  498.10  4860.2  497.29  4870.2  496.97
  4890.2  495.75  4900.2  495.68  4940.2  493.89  4950.2  493.61  4980.2  493.90
  4990.2  493.07  4999.2  491.12  5003.3  491.12  5010.2  484.31  5018.2  484.17
  5018.4  483.67  5021.9  483.67  5022.2  484.17  5040.2  493.47  5044.2  492.92
  5050.2  492.10  5060.2  494.41  5090.2  494.18  5100.2  494.55  5110.2  494.34
  5120.2  494.52  5130.2  495.15  5160.3  495.64  5190.3  496.58  5195.4  496.51
#Mann=4,-1,0
  4837.9    0.16       0  5018.2    0.07       0  5022.2    0.16       0
  5044.2    0.12       0
Bank Sta=5018.2,5022.2
Exp/Cntr=0.3,0.1

Type RM Length L Ch R = 1,5083,80,80,80
BEGIN DESCRIPTION:
Purtis Creek Trib A5082.97
END DESCRIPTION:
XS GIS Cut Line= 3
      2759801.71      6833883.86      2759797.12      6834011.94
      2759796.39      6834222.38
#Sta/Elev= 30
  4873.2  499.86  4889.2  498.10  4900.4  495.64  4910.4  494.78  4920.4  494.31
  4930.4  491.59  4940.4  488.00  4950.4  487.21  4960.4  491.54  4970.4  488.19
  4980.4  488.43  4990.4  487.34  4998.4  487.98  5003.4  487.98  5010.4  485.35
  5018.4  485.20  5018.7  484.70  5022.2  484.70  5022.4  485.20  5030.4  489.26
  5040.4  492.99  5070.4  493.35  5080.4  493.15  5092.5  493.23  5110.4  493.21
  5120.4  493.73  5130.4  493.54  5160.4  494.45  5200.4  496.23  5211.8  496.54
#Mann=4,-1,0
  4873.2    0.16       0  5018.4    0.07       0  5022.4    0.16       0
  5092.5    0.12       0
Bank Sta=5018.4,5022.4
Exp/Cntr=0.3,0.1

Type RM Length L Ch R = 1,5003,82,82,82
BEGIN DESCRIPTION:
Purtis Creek Trib A5002.74
END DESCRIPTION:
XS GIS Cut Line= 3
      2759733.26      6833858.82      2759731.25      6833971.37
      2759730.29      6834221.60
#Sta/Elev= 30
  4890.2  501.12  4893.8  501.12  4902.4  499.55  4912.4  495.65  4922.4  494.07
  4932.4  493.25  4952.4  492.35  4982.4  492.44  4990.4  484.20  4990.6  483.70
  4994.1  483.70  4994.4  484.20  5000.1  485.22  5005.1  485.22  5012.4  487.39
  5022.4  487.35  5032.4  492.40  5042.4  492.73  5062.4  492.55  5072.5  492.20
  5082.4  492.39  5102.4  492.25  5133.0  492.32  5162.4  492.14  5192.4  492.78
  5212.4  493.37  5222.4  493.84  5232.4  493.75  5242.4  494.12  5253.0  494.26
#Mann=4,-1,0
  4890.2    0.16       0  4990.4    0.07       0  4994.4    0.16       0
  5133.0    0.12       0
Bank Sta=4990.4,4994.4
Exp/Cntr=0.3,0.1

Type RM Length L Ch R = 1,4921,72,72,72
BEGIN DESCRIPTION:
Purtis Creek Trib A4921.34
END DESCRIPTION:
XS GIS Cut Line= 3
      2759650.16      6833862.00      2759651.38      6833962.49
      2759656.08      6834251.85
#Sta/Elev= 30
  4901.0  503.99  4920.0  502.37  4930.0  501.13  4940.0  499.59  4960.0  494.84
  4967.6  491.53  4972.6  491.61  4980.0  486.02  4990.0  482.86  4996.3  482.77
  4996.5  482.27  5000.0  482.27  5000.3  482.77  5001.5  482.77  5010.0  489.42
  5020.0  491.85  5030.0  491.93  5060.0  491.53  5070.0  491.55  5100.0  491.19
  5138.8  491.38  5170.0  491.66  5190.0  491.50  5200.0  491.58  5220.0  492.23
  5230.0  492.27  5250.0  492.83  5270.0  493.23  5288.0  493.80  5290.9  493.80
#Mann=4,-1,0
  4901.0    0.12       0  4996.3    0.07       0  5000.3    0.12       0
  5138.8    0.16       0
Bank Sta=4996.3,5000.3
Exp/Cntr=0.3,0.1

Type RM Length L Ch R = 1,4849,86,86,86
BEGIN DESCRIPTION:
Purtis Creek Trib A4848.89
END DESCRIPTION:
XS GIS Cut Line= 3
      2759583.88      6833813.09      2759579.17      6833961.02
      2759556.26      6834366.17
#Sta/Elev= 30
  4855.4  504.40  4863.3  504.59  4883.3  504.04  4903.3  502.65  4913.3  501.82
  4947.1  497.07  4953.4  495.56  4963.4  494.10  4973.4  489.42  4981.4  482.25
  4981.6  481.75  4985.1  481.75  4985.4  482.25  4993.4  485.14  5000.9  486.42
  5005.9  486.42  5013.4  491.28  5113.6  490.56  5140.4  490.79  5153.6  490.72
  5163.6  490.98  5193.7  491.12  5233.7  491.94  5253.8  491.88  5303.9  492.66
  5313.9  493.07  5327.1  493.14  5333.9  493.63  5384.0  494.34  5409.2  494.92
#Mann=4,-1,0
  4855.4    0.12       0  4981.4    0.07       0  4985.4    0.12       0
  5140.4    0.16       0
Bank Sta=4981.4,4985.4
Exp/Cntr=0.3,0.1

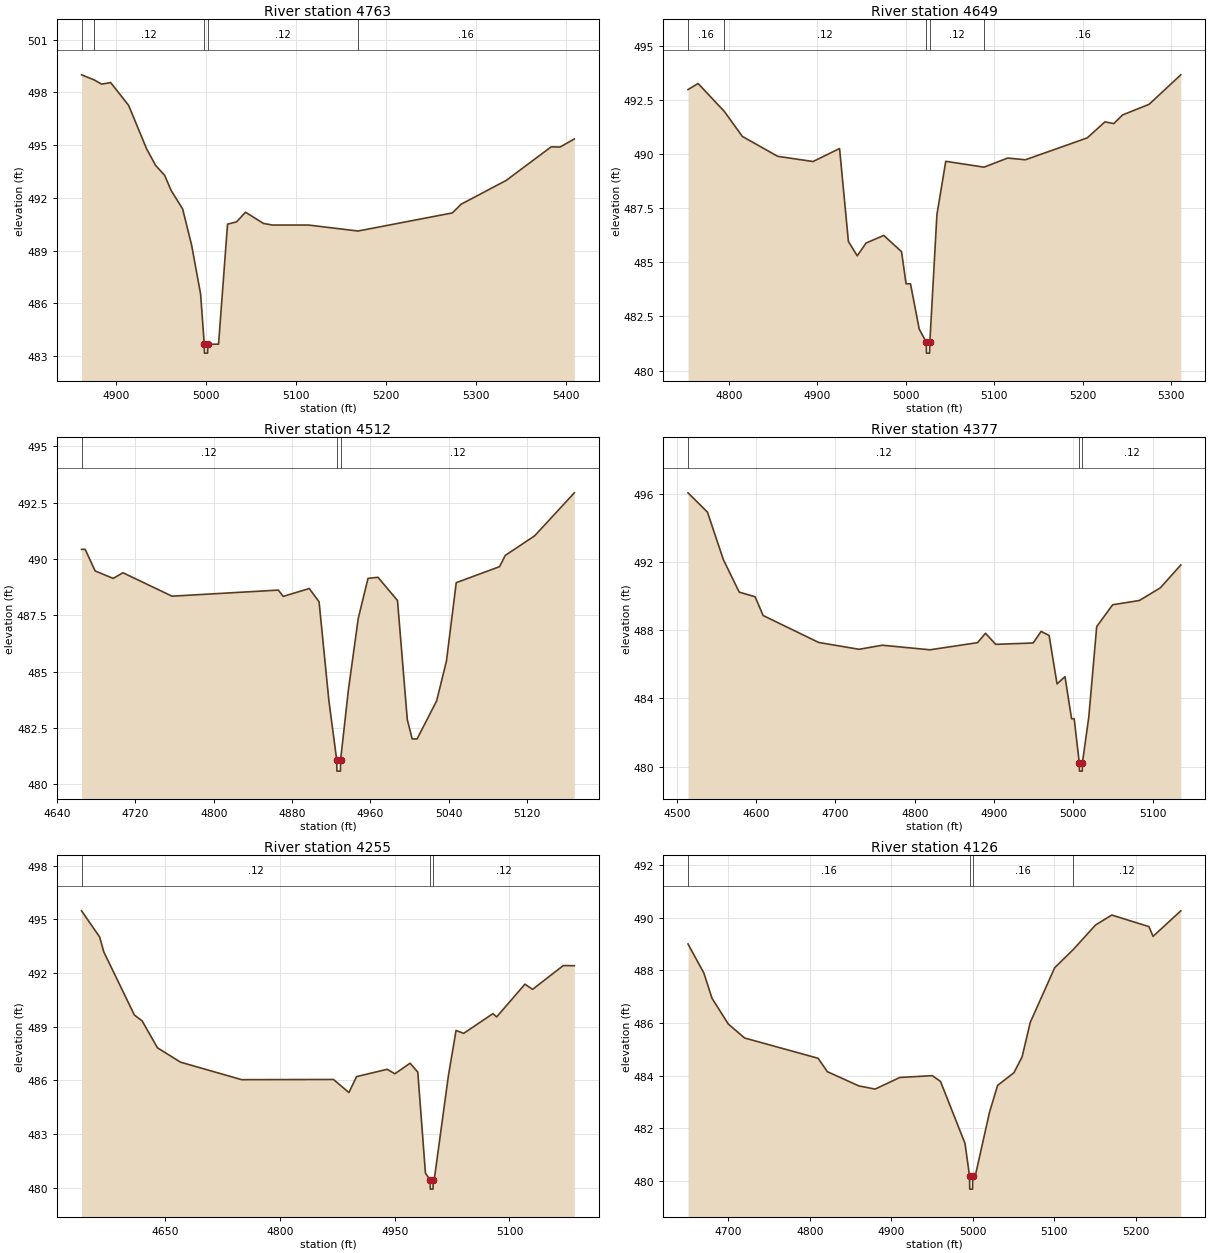
Type RM Length L Ch R = 1,4763,114,114,114
BEGIN DESCRIPTION:
Purtis Creek Trib A4762.62
END DESCRIPTION:
XS GIS Cut Line= 3
      2759515.24      6833788.60      2759509.44      6833928.15
      2759496.36      6834336.77
#Sta/Elev= 30
  4861.3  499.00  4875.4  498.71  4883.7  498.47  4893.7  498.56  4913.7  497.26
  4933.8  494.78  4943.8  493.84  4953.8  493.28  4961.1  492.41  4973.8  491.37
  4983.8  489.31  4993.8  486.53  4997.9  483.66  4998.1  483.16  5001.6  483.16
  5001.9  483.66  5013.8  483.67  5023.8  490.50  5033.8  490.63  5043.8  491.18
  5063.9  490.54  5073.9  490.45  5113.9  490.45  5169.1  490.11  5274.0  491.14
  5284.0  491.64  5334.0  492.99  5384.0  494.90  5394.0  494.89  5409.8  495.35
#Mann=5,-1,0
  4861.3    0.16       0  4875.4    0.12       0  4997.9    0.07       0
  5001.9    0.12       0  5169.1    0.16       0
Bank Sta=4997.9,5001.9
Exp/Cntr=0.3,0.1

Type RM Length L Ch R = 1,4649,137,137,137
BEGIN DESCRIPTION:
Purtis Creek Trib A4648.54
END DESCRIPTION:
XS GIS Cut Line= 3
      2759432.98      6833759.62      2759426.96      6834006.30
      2759421.90      6834316.81
#Sta/Elev= 30
  4753.8  492.97  4765.2  493.25  4794.9  491.96  4815.2  490.81  4855.2  489.89
  4895.2  489.65  4925.2  490.25  4935.2  485.96  4945.2  485.30  4955.2  485.89
  4975.2  486.24  4995.3  485.49  5000.4  484.01  5005.4  484.01  5015.3  481.92
  5023.3  481.31  5023.5  480.81  5027.0  480.81  5027.3  481.31  5035.3  487.20
  5045.3  489.66  5088.6  489.39  5115.3  489.81  5135.3  489.73  5205.3  490.74
  5225.3  491.48  5235.3  491.40  5245.3  491.80  5275.3  492.29  5311.1  493.65
#Mann=5,-1,0
  4753.8    0.16       0  4794.9    0.12       0  5023.3    0.07       0
  5027.3    0.12       0  5088.6    0.16       0
Bank Sta=5023.3,5027.3
Exp/Cntr=0.3,0.1

Type RM Length L Ch R = 1,4512,135,135,135
BEGIN DESCRIPTION:
Purtis Creek Trib A4511.57
END DESCRIPTION:
XS GIS Cut Line= 3
      2759331.55      6833738.75      2759314.13      6834076.07
      2759308.26      6834241.49
#Sta/Elev= 30
  4665.0  490.43  4668.7  490.43  4678.9  489.47  4697.3  489.14  4707.3  489.39
  4757.4  488.35  4866.0  488.62  4871.0  488.34  4897.6  488.69  4907.6  488.10
  4917.6  483.72  4925.6  481.08  4925.9  480.58  4929.4  480.58  4929.6  481.08
  4937.6  484.20  4947.6  487.36  4957.6  489.14  4967.7  489.19  4987.7  488.16
  4997.7  482.87  5002.7  482.01  5007.7  482.01  5027.7  483.70  5037.7  485.47
  5047.7  488.95  5091.9  489.66  5097.8  490.16  5127.8  491.03  5168.3  492.94
#Mann=3,-1,0
  4665.0    0.12       0  4925.6    0.07       0  4929.6    0.12       0
Bank Sta=4925.6,4929.6
Exp/Cntr=0.3,0.1

Type RM Length L Ch R = 1,4377,122,122,122
BEGIN DESCRIPTION:
Purtis Creek Trib A4377.22
END DESCRIPTION:
XS GIS Cut Line= 3
      2759233.18      6833576.50      2759205.17      6834062.59
      2759198.25      6834196.81
#Sta/Elev= 30
  4514.2  496.04  4538.7  494.91  4558.8  492.12  4578.8  490.22  4598.8  489.95
  4608.9  488.85  4679.0  487.27  4730.0  486.87  4759.1  487.11  4819.2  486.84
  4879.3  487.26  4889.3  487.81  4902.1  487.16  4949.4  487.24  4959.4  487.92
  4969.5  487.68  4979.5  484.84  4989.5  485.27  4997.8  482.80  5001.1  482.80
  5007.5  480.23  5007.8  479.73  5011.3  479.73  5011.5  480.23  5019.5  482.89
  5029.5  488.20  5049.6  489.48  5083.3  489.73  5109.7  490.47  5135.5  491.81
#Mann=3,-1,0
  4514.2    0.12       0  5007.5    0.07       0  5011.5    0.12       0
Bank Sta=5007.5,5011.5
Exp/Cntr=0.3,0.1

Type RM Length L Ch R = 1,4255,129,129,129
BEGIN DESCRIPTION:
Purtis Creek Trib A4255.33
END DESCRIPTION:
XS GIS Cut Line= 3
      2759111.64      6833551.88      2759098.94      6834012.37
      2759103.66      6834195.44
#Sta/Elev= 30
  4540.9  495.48  4564.5  494.02  4570.0  493.18  4610.0  489.65  4620.0  489.33
  4640.1  487.82  4670.1  487.02  4750.1  486.04  4870.1  486.05  4890.2  485.32
  4900.2  486.21  4940.2  486.62  4950.2  486.37  4970.2  486.96  4980.2  486.46
  4990.2  480.82  4996.4  480.42  4996.6  479.92  5000.1  479.92  5000.4  480.42
  5001.6  480.42  5020.2  486.26  5030.2  488.79  5040.2  488.63  5078.3  489.73
  5083.3  489.55  5120.2  491.38  5130.2  491.09  5170.3  492.42  5184.7  492.41
#Mann=3,-1,0
  4540.9    0.12       0  4996.4    0.07       0  5000.4    0.12       0
Bank Sta=4996.4,5000.4
Exp/Cntr=0.3,0.1

Type RM Length L Ch R = 1,4126,108,108,108
BEGIN DESCRIPTION:
Purtis Creek Trib A4125.51
END DESCRIPTION:
XS GIS Cut Line= 3
      2758996.48      6833611.59      2758985.02      6833961.14
      2758980.29      6834215.56
#Sta/Elev= 30
  4650.8  489.00  4670.2  487.90  4680.2  486.94  4700.2  485.96  4720.2  485.43
  4810.3  484.66  4821.7  484.15  4860.3  483.61  4880.3  483.49  4910.4  483.93
  4950.4  484.00  4960.4  483.78  4990.4  481.43  4996.0  480.19  4996.2  479.69
  4999.7  479.69  5000.0  480.19  5003.0  480.19  5020.4  482.60  5030.4  483.63
  5050.4  484.11  5060.4  484.71  5070.4  486.02  5100.4  488.10  5123.2  488.79
  5150.4  489.72  5170.4  490.10  5216.0  489.66  5221.0  489.29  5255.0  490.26
#Mann=4,-1,0
  4650.8    0.16       0  4996.0    0.07       0  5000.0    0.16       0
  5123.2    0.12       0
Bank Sta=4996,5000
Exp/Cntr=0.3,0.1

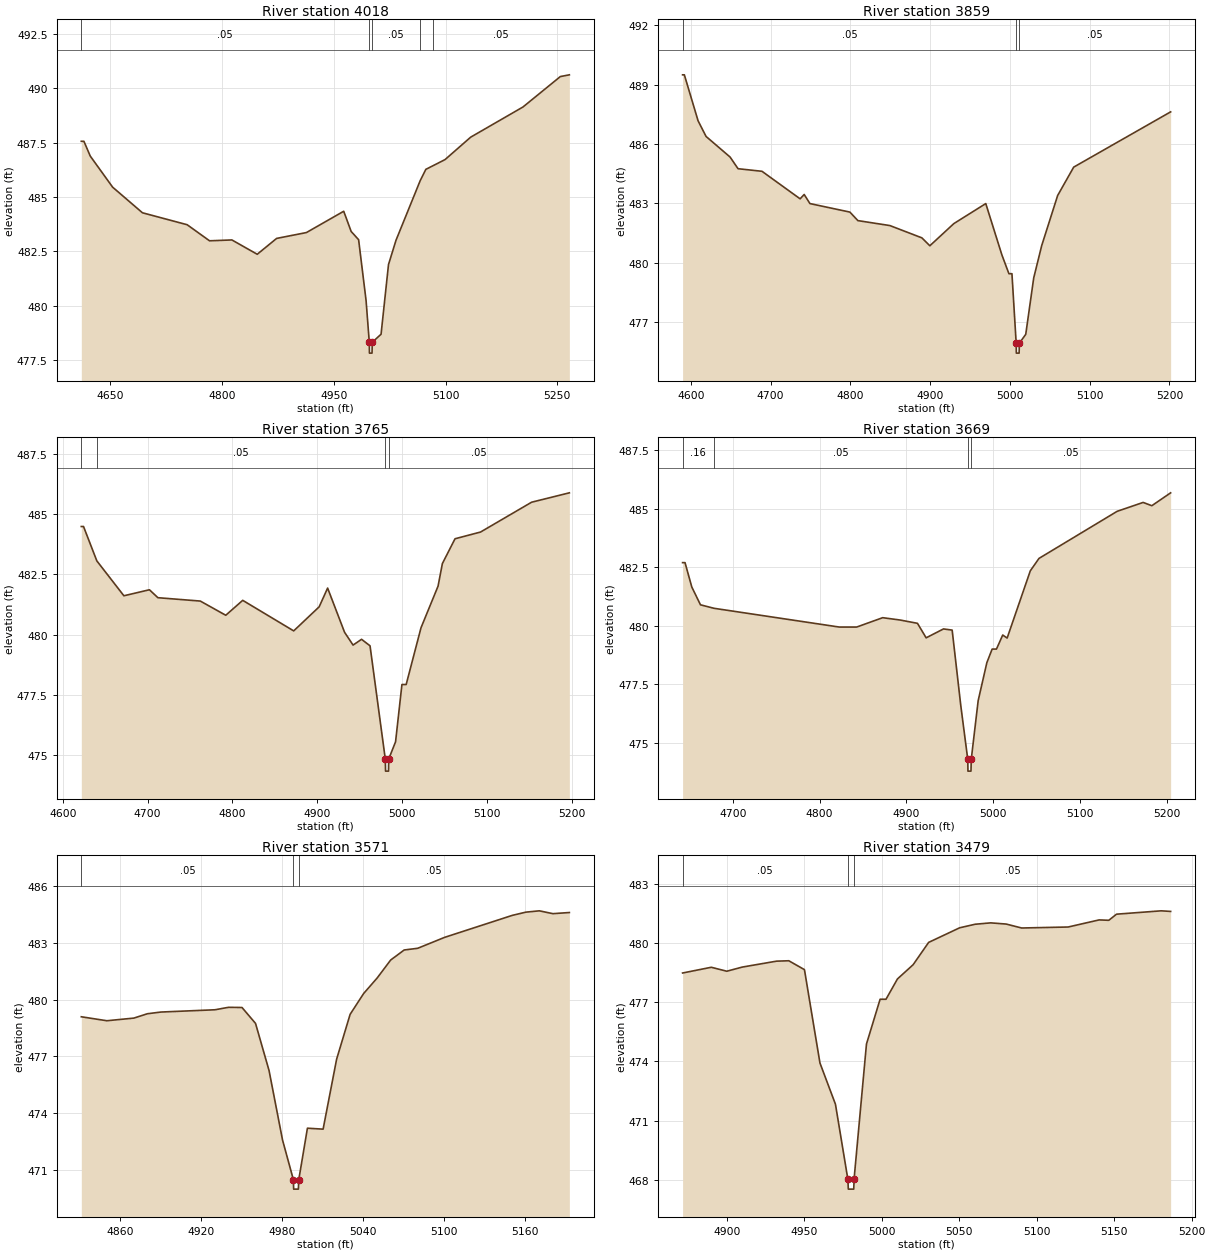
Type RM Length L Ch R = 1,4018,159,159,159
BEGIN DESCRIPTION:
Purtis Creek Trib A4017.9
END DESCRIPTION:
XS GIS Cut Line= 3
      2758885.84      6833569.05      2758877.82      6833958.53
      2758859.61      6834223.04
#Sta/Elev= 30
  4611.4  487.56  4614.9  487.56  4623.4  486.88  4653.4  485.45  4693.4  484.27
  4753.4  483.72  4783.4  482.98  4813.4  483.02  4847.4  482.36  4873.4  483.09
  4913.4  483.36  4963.4  484.34  4973.4  483.41  4983.4  483.03  4993.4  480.23
  4997.7  478.31  4997.9  477.81  5001.4  477.81  5001.7  478.31  5013.5  478.68
  5023.5  481.89  5033.5  483.00  5065.9  485.74  5073.6  486.27  5083.4  486.44
  5099.4  486.72  5133.7  487.75  5203.9  489.14  5254.0  490.54  5266.1  490.62
#Mann=5,-1,0
  4611.4    0.05       0  4997.7    0.05       0  5001.7    0.05       0
  5065.9    0.12       0  5083.4    0.05       0
Bank Sta=4997.7,5001.7
Exp/Cntr=0.3,0.1

Type RM Length L Ch R = 1,3859,94,94,94
BEGIN DESCRIPTION:
Purtis Creek Trib A3858.67
END DESCRIPTION:
XS GIS Cut Line= 3
      2758780.01      6833451.66      2758755.22      6833863.75
      2758746.34      6834062.41
#Sta/Elev= 30
  4589.8  489.49  4592.0  489.49  4609.2  487.17  4619.2  486.38  4649.3  485.34
  4659.3  484.75  4689.3  484.62  4737.1  483.23  4742.2  483.45  4749.4  482.99
  4799.5  482.56  4809.5  482.13  4849.6  481.88  4889.7  481.26  4899.7  480.86
  4929.8  481.98  4969.8  482.99  4989.9  480.41  4998.8  479.45  5002.6  479.45
  5007.9  475.94  5008.1  475.44  5011.6  475.44  5011.9  475.94  5019.9  476.39
  5029.9  479.24  5039.9  480.87  5059.9  483.40  5080.0  484.83  5201.5  487.62
#Mann=3,-1,0
  4589.8    0.05       0  5007.9    0.05       0  5011.9    0.05       0
Bank Sta=5007.9,5011.9
Exp/Cntr=0.3,0.1

Type RM Length L Ch R = 1,3765,96,96,96
BEGIN DESCRIPTION:
Purtis Creek Trib A3764.75
END DESCRIPTION:
XS GIS Cut Line= 3
      2758678.52      6833470.80      2758664.43      6833851.15
      2758649.63      6834045.37
#Sta/Elev= 30
  4621.9  484.49  4624.5  484.49  4640.2  483.06  4672.1  481.61  4702.2  481.86
  4712.2  481.53  4762.2  481.39  4792.2  480.80  4812.2  481.42  4872.3  480.15
  4902.3  481.15  4912.3  481.93  4932.3  480.09  4942.3  479.56  4952.3  479.80
  4962.3  479.53  4980.3  474.82  4980.6  474.32  4984.1  474.32  4984.3  474.82
  4992.4  475.54  4999.9  477.92  5004.9  477.92  5022.4  480.28  5042.5  482.01
  5047.6  482.95  5062.5  483.98  5092.6  484.26  5152.8  485.50  5197.3  485.89
#Mann=4,-1,0
  4621.9    0.12       0  4640.2    0.05       0  4980.3    0.05       0
  4984.3    0.05       0
Bank Sta=4980.3,4984.3
Exp/Cntr=0.3,0.1

Type RM Length L Ch R = 1,3669,98,98,98
BEGIN DESCRIPTION:
Purtis Creek Trib A3657.82
END DESCRIPTION:
XS GIS Cut Line= 3
      2758593.60      6833450.38      2758581.71      6833808.18
      2758571.64      6834012.64
#Sta/Elev= 30
  4642.0  482.69  4644.8  482.69  4652.6  481.65  4662.6  480.89  4678.3  480.74
  4822.7  479.94  4842.7  479.94  4872.7  480.34  4892.8  480.24  4912.8  480.10
  4922.8  479.48  4942.8  479.86  4952.8  479.81  4962.8  476.57  4970.8  474.29
  4971.0  473.79  4974.5  473.79  4974.8  474.29  4982.8  476.80  4992.8  478.42
  4998.9  479.00  5003.9  479.00  5011.1  479.60  5016.2  479.47  5042.9  482.34
  5052.9  482.87  5143.0  484.88  5173.0  485.26  5183.0  485.12  5204.7  485.67
#Mann=4,-1,0
  4642.0    0.16       0  4678.3    0.05       0  4970.8    0.05       0
  4974.8    0.05       0
Bank Sta=4970.8,4974.8
Exp/Cntr=0.3,0.1

Type RM Length L Ch R = 1,3571,92,92,92
BEGIN DESCRIPTION:
Purtis Creek Trib A3570.63
END DESCRIPTION:
XS GIS Cut Line= 3
      2758498.03      6833592.12      2758499.01      6833762.78
      2758497.31      6833953.21
#Sta/Elev= 30
  4831.4  479.09  4850.3  478.88  4870.3  479.02  4880.3  479.25  4890.3  479.34
  4930.3  479.46  4940.3  479.59  4950.3  479.58  4960.3  478.74  4970.3  476.25
  4980.3  472.57  4988.3  470.48  4988.5  469.98  4992.0  469.98  4992.3  470.48
  4998.7  473.20  5010.3  473.15  5020.3  476.85  5030.3  479.22  5040.3  480.32
  5050.3  481.14  5060.3  482.09  5070.3  482.62  5080.3  482.71  5100.3  483.29
  5150.3  484.45  5160.3  484.62  5170.3  484.69  5180.3  484.54  5192.5  484.60
#Mann=3,-1,0
  4831.4    0.05       0  4988.3    0.05       0  4992.3    0.05       0
Bank Sta=4988.3,4992.3
Exp/Cntr=0.3,0.1

Type RM Length L Ch R = 1,3479,101,101,101
BEGIN DESCRIPTION:
Purtis Creek Trib A3478.53
END DESCRIPTION:
XS GIS Cut Line= 3
      2758414.35      6833632.58      2758406.74      6833763.58
      2758412.13      6833947.08
#Sta/Elev= 30
  4871.6  478.48  4890.1  478.77  4900.1  478.57  4910.1  478.78  4932.2  479.08
  4940.1  479.10  4950.2  478.65  4960.2  473.92  4970.2  471.83  4978.2  468.03
  4978.5  467.53  4982.0  467.53  4982.2  468.03  4990.2  474.88  4999.0  477.15
  5002.8  477.15  5010.2  478.18  5020.3  478.90  5030.3  480.03  5050.3  480.77
  5060.3  480.95  5070.3  481.02  5080.3  480.96  5090.3  480.76  5120.3  480.81
  5140.3  481.17  5146.5  481.15  5151.5  481.46  5180.3  481.63  5186.4  481.60
#Mann=3,-1,0
  4871.6    0.05       0  4978.2    0.05       0  4982.2    0.05       0
Bank Sta=4978.2,4982.2
Exp/Cntr=0.3,0.1

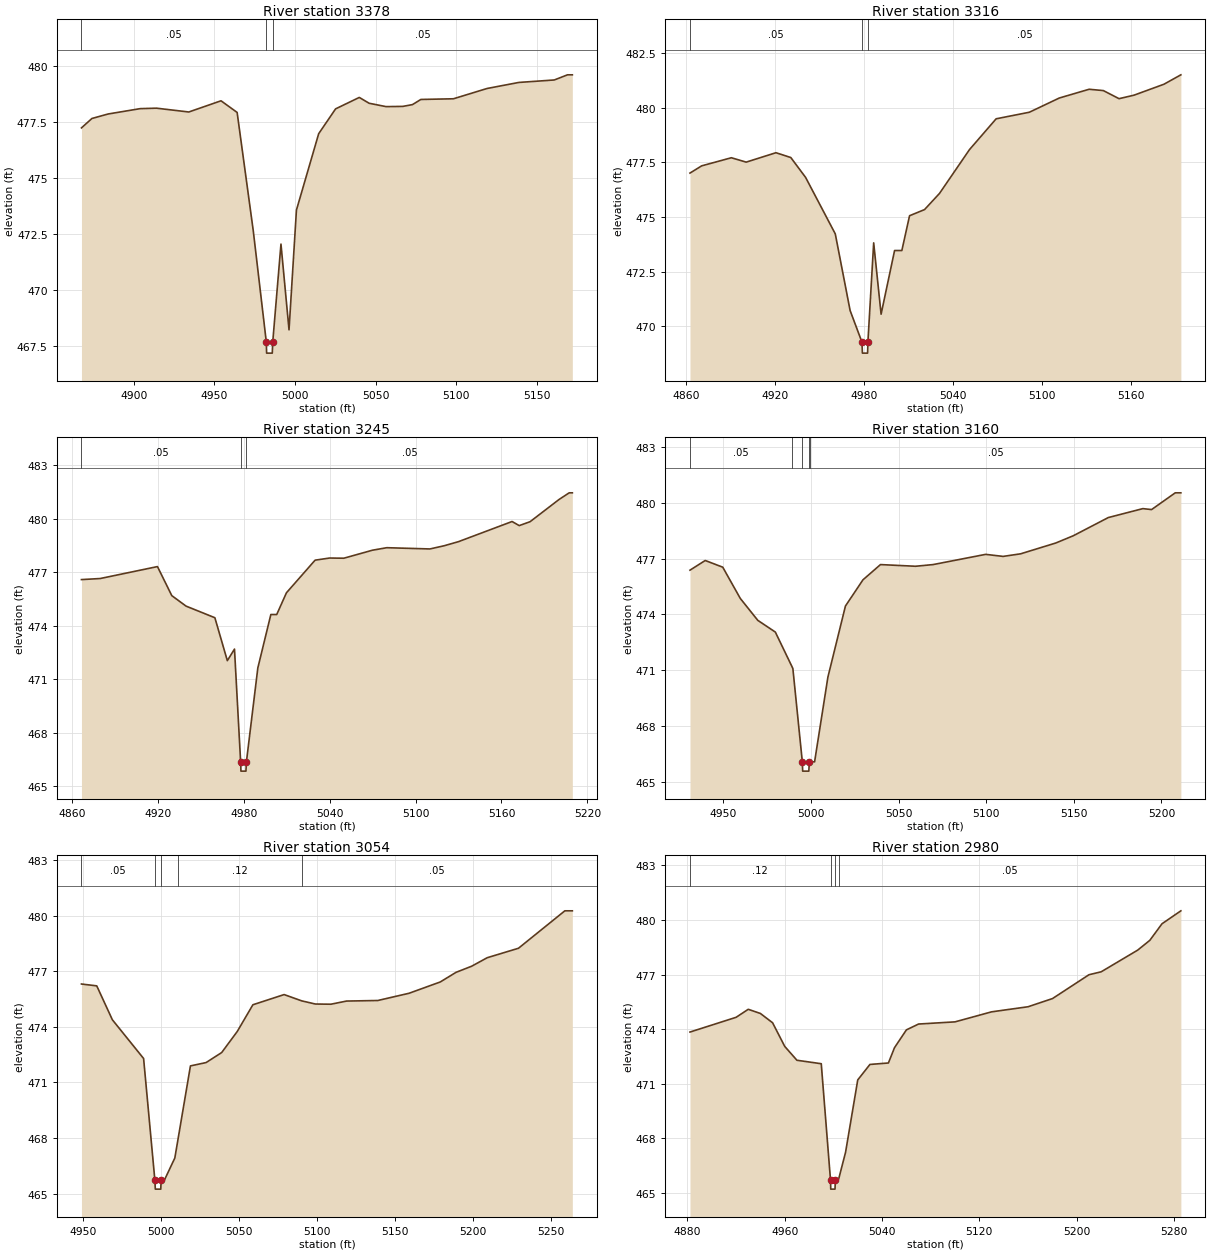
Type RM Length L Ch R = 1,3378,62,62,62
BEGIN DESCRIPTION:
Purtis Creek Trib A3377.87
END DESCRIPTION:
XS GIS Cut Line= 3
      2758318.17      6833644.52      2758310.48      6833779.42
      2758359.43      6833941.68
#Sta/Elev= 30
  4867.5  477.22  4874.0  477.64  4884.0  477.84  4904.0  478.08  4914.1  478.10
  4934.1  477.93  4954.1  478.43  4964.1  477.91  4974.1  472.63  4982.2  467.66
  4982.4  467.16  4985.9  467.16  4986.2  467.66  4991.3  472.03  4996.3  468.20
  5000.9  473.55  5014.7  476.96  5025.2  478.07  5039.9  478.58  5046.0  478.32
  5056.5  478.17  5066.9  478.18  5072.9  478.26  5078.1  478.49  5098.3  478.52
  5119.2  478.98  5138.9  479.25  5160.9  479.36  5169.1  479.59  5172.1  479.59
#Mann=3,-1,0
  4867.5    0.05       0  4982.2    0.05       0  4986.2    0.05       0
Bank Sta=4982.2,4986.2
Exp/Cntr=0.3,0.1

Type RM Length L Ch R = 1,3316,71,71,71
BEGIN DESCRIPTION:
Purtis Creek Trib A3315.81
END DESCRIPTION:
XS GIS Cut Line= 3
      2758267.88      6833673.13      2758260.00      6833815.86
      2758234.51      6834002.28
#Sta/Elev= 30
  4862.4  477.01  4870.3  477.34  4890.3  477.71  4900.3  477.51  4920.4  477.94
  4930.4  477.72  4940.4  476.81  4960.4  474.23  4970.4  470.73  4978.4  469.28
  4978.7  468.78  4982.2  468.78  4982.4  469.28  4986.3  473.82  4991.3  470.56
  5000.4  473.47  5005.3  473.47  5010.5  475.06  5020.6  475.34  5030.7  476.08
  5050.9  478.08  5068.9  479.49  5091.3  479.79  5111.5  480.44  5131.6  480.84
  5141.2  480.78  5151.8  480.41  5161.9  480.57  5182.1  481.07  5193.5  481.50
#Mann=3,-1,0
  4862.4    0.05       0  4978.4    0.05       0  4982.4    0.05       0
Bank Sta=4978.4,4982.4
Exp/Cntr=0.3,0.1

Type RM Length L Ch R = 1,3245,85,85,85
BEGIN DESCRIPTION:
Purtis Creek Trib A3245.13
END DESCRIPTION:
XS GIS Cut Line= 3
      2758196.13      6833677.95      2758189.51      6833814.14
      2758178.97      6834020.42
#Sta/Elev= 30
  4866.6  476.59  4879.7  476.65  4919.7  477.32  4929.7  475.69  4939.7  475.10
  4959.8  474.45  4968.5  472.04  4973.5  472.69  4977.8  466.34  4978.0  465.84
  4981.5  465.84  4981.8  466.34  4989.8  471.63  4998.9  474.63  5003.0  474.63
  5009.8  475.85  5029.8  477.68  5039.9  477.80  5049.9  477.79  5069.9  478.24
  5079.9  478.38  5110.0  478.31  5120.0  478.49  5130.0  478.72  5167.4  479.85
  5172.4  479.62  5180.0  479.84  5200.1  481.08  5207.3  481.46  5209.5  481.46
#Mann=3,-1,0
  4866.6    0.05       0  4977.8    0.05       0  4981.8    0.05       0
Bank Sta=4977.8,4981.8
Exp/Cntr=0.3,0.1

Type RM Length L Ch R = 1,3160,106,106,106
BEGIN DESCRIPTION:
Purtis Creek Trib A3160.2
END DESCRIPTION:
XS GIS Cut Line= 3
      2758105.18      6833742.32      2758104.73      6833810.78
      2758100.68      6834022.37
#Sta/Elev= 30
  4931.0  476.38  4939.7  476.90  4949.7  476.54  4959.7  474.86  4969.7  473.68
  4979.7  473.05  4989.0  471.23  4989.7  471.09  4995.1  466.07  4995.3  465.57
  4998.8  465.57  4999.1  466.07  4999.6  466.07  5002.1  466.07  5009.7  470.63
  5019.7  474.45  5029.7  475.86  5039.7  476.68  5059.7  476.59  5069.7  476.68
  5099.7  477.23  5109.7  477.12  5119.7  477.26  5139.7  477.84  5149.7  478.23
  5169.7  479.21  5189.4  479.69  5194.4  479.64  5207.9  480.54  5211.1  480.54
#Mann=5,-1,0
  4931.0    0.05       0  4989.0    0.12       0  4995.1    0.05       0
  4999.1    0.12       0  4999.6    0.05       0
Bank Sta=4995.1,4999.1
Exp/Cntr=0.3,0.1

Type RM Length L Ch R = 1,3054,74,74,74
BEGIN DESCRIPTION:
Purtis Creek Trib A3053.89
END DESCRIPTION:
XS GIS Cut Line= 3
      2758016.36      6833711.20      2758014.38      6833764.41
      2758017.94      6834025.54
#Sta/Elev= 30
  4949.1  476.31  4958.9  476.21  4968.9  474.38  4988.9  472.29  4996.1  465.74
  4996.4  465.24  4999.9  465.24  5000.1  465.74  5002.3  465.74  5008.9  466.92
  5010.9  467.91  5018.9  471.89  5028.9  472.07  5038.9  472.61  5048.9  473.75
  5058.9  475.19  5078.9  475.74  5090.2  475.40  5098.9  475.23  5108.9  475.22
  5118.9  475.39  5138.9  475.42  5158.9  475.81  5178.9  476.42  5189.0  476.94
  5199.0  477.27  5209.0  477.73  5229.0  478.24  5258.7  480.26  5263.5  480.26
#Mann=5,-1,0
  4949.1    0.05       0  4996.1    0.05       0  5000.1    0.05       0
  5010.9    0.12       0  5090.2    0.05       0
Bank Sta=4996.1,5000.1
Exp/Cntr=0.3,0.1

Type RM Length L Ch R = 1,2980,102,102,102
BEGIN DESCRIPTION:
Purtis Creek Trib A2979.31
END DESCRIPTION:
XS GIS Cut Line= 3
      2757938.28      6833643.09      2757940.23      6833765.12
      2757945.48      6834046.53
#Sta/Elev= 30
  4882.2  473.84  4920.1  474.65  4930.1  475.09  4940.1  474.86  4950.1  474.35
  4960.1  473.05  4970.1  472.29  4990.1  472.10  4997.7  465.71  4997.9  465.21
  5001.4  465.21  5001.7  465.71  5004.4  465.76  5010.1  467.24  5020.1  471.21
  5030.1  472.06  5045.3  472.14  5050.3  472.98  5060.1  473.96  5070.1  474.28
  5100.1  474.40  5130.1  474.95  5160.1  475.23  5180.2  475.68  5210.2  476.99
  5220.2  477.15  5250.2  478.34  5260.2  478.88  5270.2  479.79  5285.7  480.50
#Mann=4,-1,0
  4882.2    0.12       0  4997.7    0.07       0  5001.7    0.12       0
  5004.4    0.05       0
Bank Sta=4997.7,5001.7
Exp/Cntr=0.3,0.1

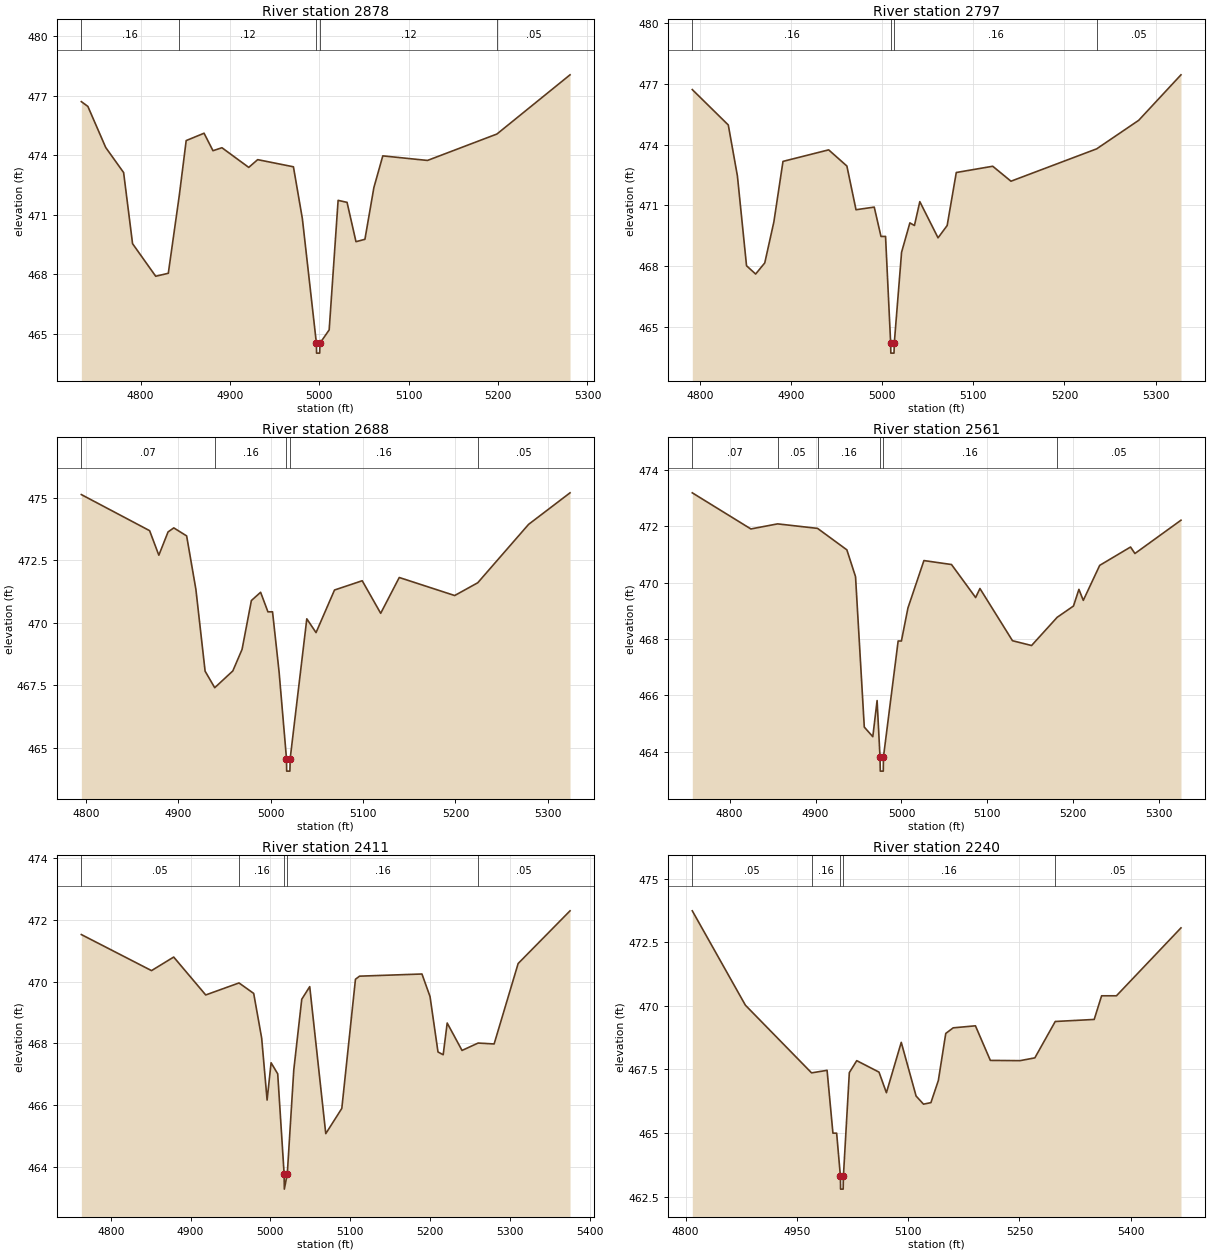
Type RM Length L Ch R = 1,2878,81,81,81
BEGIN DESCRIPTION:
Purtis Creek Trib A2878.2
END DESCRIPTION:
XS GIS Cut Line= 3
      2757841.95      6833493.73      2757838.93      6833761.35
      2757834.34      6834040.47
#Sta/Elev= 30
  4733.7  476.70  4741.0  476.46  4761.0  474.39  4781.0  473.13  4791.0  469.55
  4816.9  467.91  4831.0  468.06  4843.3  471.98  4851.0  474.74  4871.0  475.11
  4881.0  474.23  4891.0  474.38  4921.0  473.39  4931.0  473.78  4971.0  473.42
  4981.0  470.81  4996.7  464.54  4996.9  464.04  5000.4  464.04  5000.7  464.54
  5011.0  465.21  5021.0  471.73  5031.0  471.63  5041.0  469.65  5051.0  469.77
  5061.0  472.37  5071.0  473.97  5121.0  473.74  5198.7  475.07  5280.5  478.05
#Mann=5,-1,0
  4733.7    0.16       0  4843.3    0.12       0  4996.7    0.07       0
  5000.7    0.12       0  5198.7    0.05       0
Bank Sta=4996.7,5000.7
Exp/Cntr=0.3,0.1

Type RM Length L Ch R = 1,2797,109,109,109
BEGIN DESCRIPTION:
Purtis Creek Trib A2797.43
END DESCRIPTION:
XS GIS Cut Line= 3
      2757773.33      6833511.45      2757771.88      6833720.84
      2757763.23      6834047.43
#Sta/Elev= 30
  4791.8  476.72  4831.3  474.97  4841.3  472.45  4851.3  468.01  4861.3  467.60
  4871.3  468.15  4881.3  470.18  4891.3  473.17  4941.4  473.74  4961.4  472.94
  4971.4  470.78  4991.4  470.91  4998.8  469.46  5003.8  469.46  5009.4  464.19
  5009.6  463.69  5013.1  463.69  5013.4  464.19  5021.4  468.68  5030.5  470.13
  5035.5  470.00  5041.4  471.18  5061.4  469.39  5071.4  470.00  5081.4  472.62
  5121.4  472.93  5141.4  472.19  5235.4  473.79  5281.5  475.20  5327.9  477.45
#Mann=4,-1,0
  4791.8    0.16       0  5009.4    0.07       0  5013.4    0.16       0
  5235.4    0.05       0
Bank Sta=5009.4,5013.4
Exp/Cntr=0.3,0.1

Type RM Length L Ch R = 1,2688,127,127,127
BEGIN DESCRIPTION:
Purtis Creek Trib A2683.87
END DESCRIPTION:
XS GIS Cut Line= 3
      2757696.20      6833517.18      2757685.68      6833721.91
      2757675.81      6834045.86
#Sta/Elev= 30
  4795.0  475.12  4868.9  473.68  4878.9  472.70  4888.9  473.63  4895.1  473.79
  4909.0  473.47  4919.0  471.34  4929.0  468.07  4939.4  467.41  4959.0  468.08
  4969.0  468.94  4979.1  470.89  4989.1  471.22  4997.0  470.44  5002.0  470.44
  5009.1  468.04  5017.1  464.58  5017.3  464.08  5020.8  464.08  5021.1  464.58
  5039.1  470.16  5049.1  469.61  5069.1  471.31  5099.1  471.68  5119.1  470.38
  5139.2  471.81  5199.2  471.09  5224.2  471.60  5279.2  473.93  5324.1  475.19
#Mann=5,-1,0
  4795.0    0.07       0  4939.4    0.16       0  5017.1    0.07       0
  5021.1    0.16       0  5224.2    0.05       0
Bank Sta=5017.1,5021.1
Exp/Cntr=0.3,0.1

Type RM Length L Ch R = 1,2561,150,150,150
BEGIN DESCRIPTION:
Purtis Creek Trib A2561.27
END DESCRIPTION:
XS GIS Cut Line= 3
      2757618.57      6833513.88      2757576.00      6833753.55
      2757521.18      6834074.28
#Sta/Elev= 30
  4756.5  473.18  4824.7  471.90  4855.8  472.08  4902.3  471.92  4936.4  471.16
  4946.5  470.21  4956.7  464.88  4966.6  464.54  4971.6  465.82  4975.0  463.82
  4975.3  463.32  4978.8  463.32  4979.0  463.82  4996.1  467.93  4999.9  467.93
  5007.5  469.10  5026.1  470.78  5058.2  470.64  5086.3  469.47  5091.3  469.79
  5129.2  467.94  5151.4  467.77  5181.2  468.77  5200.2  469.17  5206.5  469.76
  5211.6  469.37  5230.7  470.61  5266.6  471.26  5271.7  471.03  5325.3  472.21
#Mann=6,-1,0
  4756.5    0.07       0  4855.8    0.05       0  4902.3    0.16       0
  4975.0    0.07       0  4979.0    0.16       0  5181.2    0.05       0
Bank Sta=4975,4979
Exp/Cntr=0.3,0.1

Type RM Length L Ch R = 1,2411,171,171,171
BEGIN DESCRIPTION:
Purtis Creek Trib A2411.17
END DESCRIPTION:
XS GIS Cut Line= 3
      2757476.71      6833425.59      2757460.58      6833665.88
      2757426.60      6834035.69
#Sta/Elev= 30
  4763.2  471.53  4851.1  470.36  4878.9  470.80  4919.0  469.57  4960.7  469.96
  4979.1  469.62  4989.1  468.17  4995.9  466.16  5000.9  467.37  5009.2  467.01
  5017.2  463.77  5017.5  463.27  5021.2  463.77  5029.3  467.13  5039.3  469.43
  5049.3  469.84  5069.4  465.07  5089.5  465.89  5106.6  470.08  5111.7  470.18
  5189.9  470.25  5200.0  469.52  5210.0  467.72  5216.5  467.63  5221.5  468.66
  5240.1  467.77  5260.3  468.01  5280.3  467.98  5310.4  470.59  5375.4  472.30
#Mann=5,-1,0
  4763.2    0.05       0  4960.7    0.16       0  5017.2    0.07       0
  5021.2    0.16       0  5260.3    0.05       0
Bank Sta=5017.2,5021.2
Exp/Cntr=0.3,0.1

Type RM Length L Ch R = 1,2240,164,164,164
BEGIN DESCRIPTION:
Purtis Creek Trib A2240.44
END DESCRIPTION:
XS GIS Cut Line= 3
      2757299.06      6833419.46      2757306.13      6833611.90
      2757319.67      6834077.93
#Sta/Elev= 30
  4809.0  473.73  4880.6  470.02  4969.8  467.36  4990.7  467.46  4998.6  464.99
  5003.6  464.99  5008.7  463.29  5008.9  462.79  5012.4  462.79  5012.7  463.29
  5020.7  467.37  5030.7  467.84  5060.7  467.39  5070.7  466.58  5090.7  468.56
  5110.7  466.45  5120.7  466.13  5130.7  466.19  5140.7  467.06  5150.7  468.91
  5160.7  469.13  5190.7  469.21  5210.8  467.85  5250.8  467.84  5270.8  467.95
  5298.3  469.38  5350.8  469.46  5360.8  470.39  5380.8  470.39  5467.8  473.06
#Mann=5,-1,0
  4809.0    0.05       0  4969.8    0.16       0  5008.7    0.07       0
  5012.7    0.16       0  5298.3    0.05       0
Bank Sta=5008.7,5012.7
Exp/Cntr=0.3,0.1