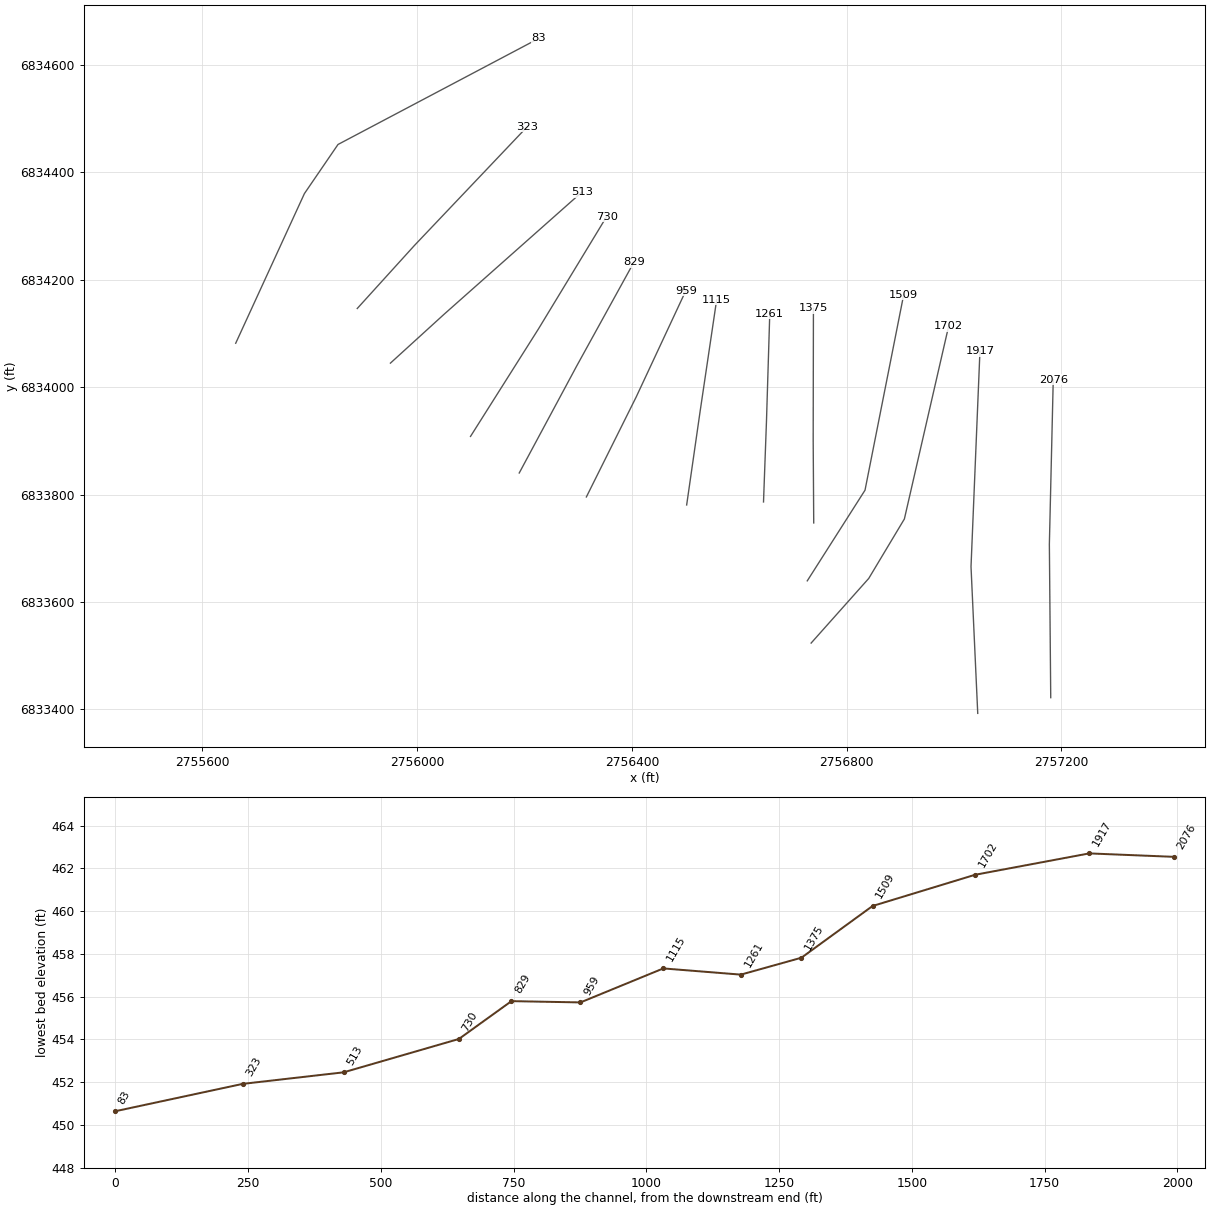
HEC-RAS study Purtis Creek Trib A.prj: Purtis Creek Trib A Base Level Engineering

--- Purtis Creek Trib A.g01 (geometry) --- (continued)

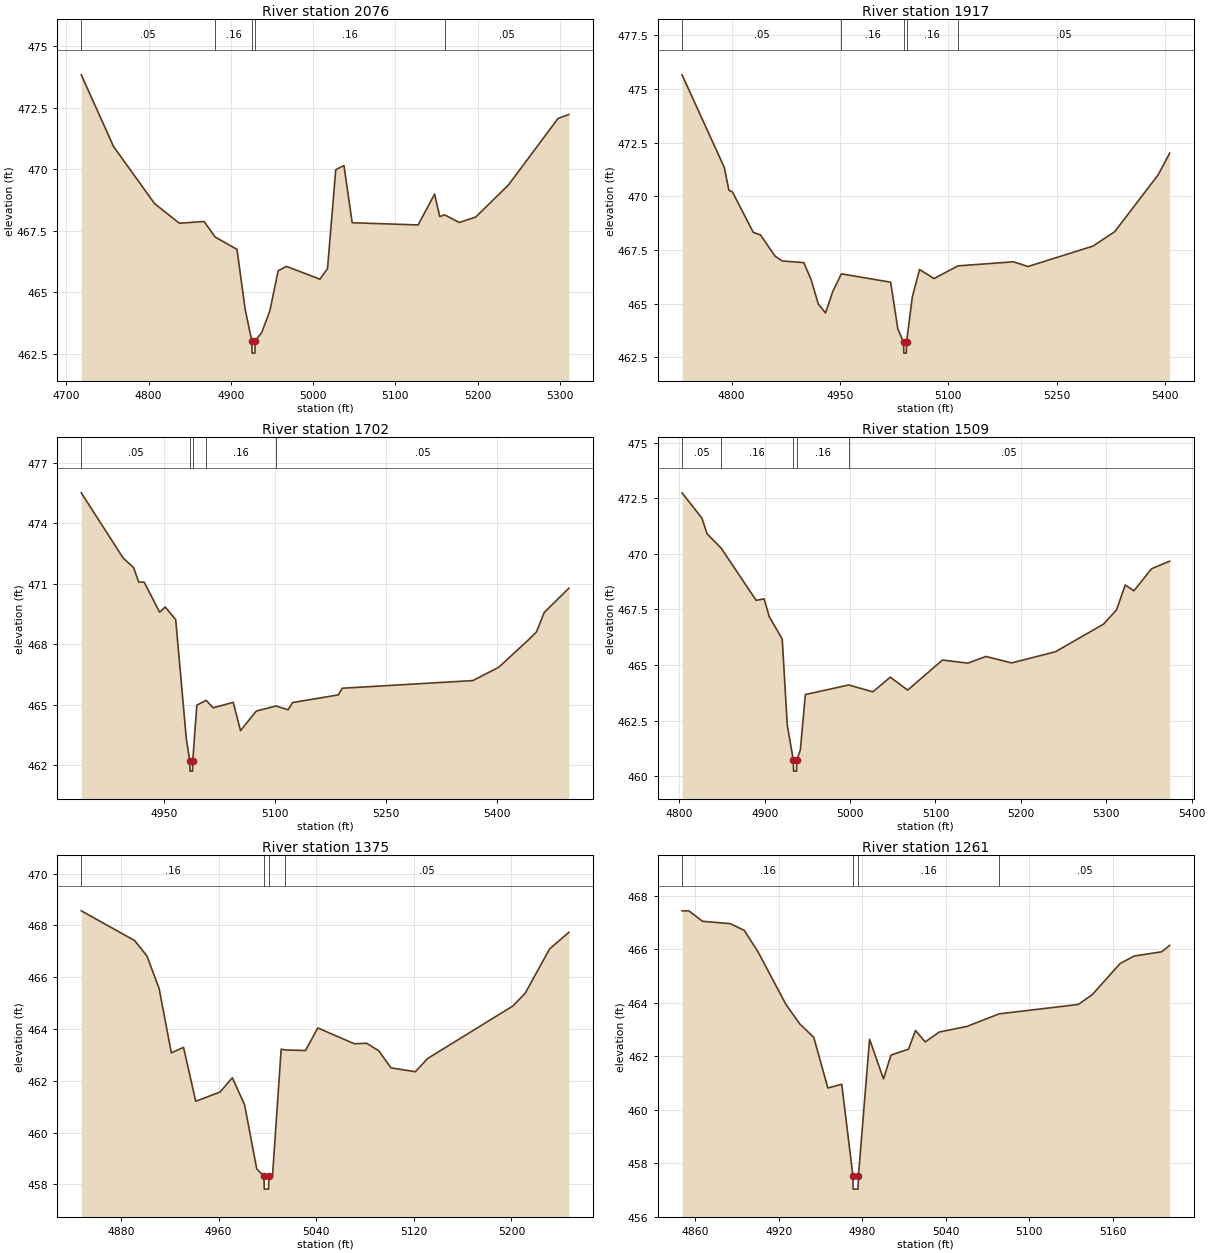
Type RM Length L Ch R = 1,2076,159,159,159
BEGIN DESCRIPTION:
Purtis Creek Trib A2076.47
END DESCRIPTION:
XS GIS Cut Line= 3
      2757179.98      6833421.78      2757177.44      6833707.48
      2757184.67      6834014.19
#Sta/Elev= 30
  4718.3  473.83  4757.5  470.92  4807.5  468.60  4837.5  467.81  4867.5  467.88
  4881.0  467.25  4907.5  466.75  4917.5  464.30  4925.5  463.04  4925.8  462.54
  4929.3  462.54  4929.5  463.04  4937.5  463.37  4947.5  464.26  4957.5  465.88
  4967.5  466.06  5008.3  465.54  5017.5  465.97  5027.5  469.98  5037.5  470.15
  5047.5  467.83  5127.6  467.74  5147.6  468.99  5153.9  468.08  5159.9  468.15
  5177.6  467.84  5197.6  468.06  5237.6  469.37  5297.6  472.06  5310.8  472.22
#Mann=5,-1,0
  4718.3    0.05       0  4881.0    0.16       0  4925.5    0.07       0
  4929.5    0.16       0  5159.9    0.05       0
Bank Sta=4925.5,4929.5
Exp/Cntr=0.3,0.1

Type RM Length L Ch R = 1,1917,215,215,215
BEGIN DESCRIPTION:
Purtis Creek Trib A1916.58
END DESCRIPTION:
XS GIS Cut Line= 3
      2757044.03      6833392.54      2757031.50      6833665.83
      2757048.13      6834067.01
#Sta/Elev= 30
  4731.3  475.65  4789.8  471.34  4796.1  470.28  4801.1  470.20  4829.9  468.32
  4839.9  468.20  4859.9  467.22  4869.9  466.99  4899.9  466.91  4909.9  466.13
  4920.0  464.98  4930.0  464.57  4940.0  465.57  4951.9  466.39  5020.1  466.00
  5030.1  463.82  5038.1  463.20  5038.3  462.70  5041.8  462.70  5042.1  463.20
  5050.1  465.31  5060.1  466.59  5080.1  466.17  5113.4  466.76  5190.2  466.95
  5210.2  466.73  5300.3  467.68  5330.3  468.35  5390.4  470.99  5406.4  472.00
#Mann=5,-1,0
  4731.3    0.05       0  4951.9    0.16       0  5038.1    0.07       0
  5042.1    0.16       0  5113.4    0.05       0
Bank Sta=5038.1,5042.1
Exp/Cntr=0.3,0.1

Type RM Length L Ch R = 1,1702,193,193,193
BEGIN DESCRIPTION:
Purtis Creek Trib A1702.35
END DESCRIPTION:
XS GIS Cut Line= 4
      2756733.72      6833523.50      2756841.01      6833643.88
      2756907.38      6833754.60      2756989.75      6834113.32
#Sta/Elev= 30
  4838.1  475.50  4894.6  472.27  4908.8  471.79  4915.5  471.08  4923.0  471.07
  4943.9  469.58  4951.4  469.84  4965.6  469.21  4979.9  463.31  4984.6  462.20
  4984.8  461.70  4988.3  461.70  4988.6  462.20  4994.1  464.97  5006.7  465.21
  5016.1  464.84  5043.3  465.11  5053.1  463.71  5074.5  464.68  5101.1  464.93
  5117.2  464.74  5123.4  465.10  5185.2  465.48  5190.4  465.81  5366.9  466.19
  5401.8  466.85  5442.8  468.24  5452.7  468.60  5463.3  469.57  5496.5  470.77
#Mann=5,-1,0
  4838.1    0.05       0  4984.6    0.05       0  4988.6    0.05       0
  5006.7    0.16       0  5101.1    0.05       0
Bank Sta=4984.6,4988.6
Exp/Cntr=0.3,0.1

Type RM Length L Ch R = 1,1509,134,134,134
BEGIN DESCRIPTION:
Purtis Creek Trib A1508.86
END DESCRIPTION:
XS GIS Cut Line= 3
      2756726.52      6833639.38      2756834.07      6833808.23
      2756906.06      6834171.98
#Sta/Elev= 30
  4803.2  472.74  4826.5  471.60  4832.5  470.90  4848.9  470.26  4890.0  467.91
  4899.3  467.98  4905.3  467.18  4920.5  466.17  4926.4  462.31  4933.5  460.74
  4933.8  460.24  4937.3  460.24  4937.5  460.74  4941.7  461.19  4947.6  463.68
  4998.4  464.11  5026.6  463.80  5047.0  464.46  5067.4  463.88  5108.2  465.23
  5137.9  465.09  5159.1  465.39  5189.1  465.10  5240.4  465.60  5296.7  466.84
  5312.0  467.48  5322.2  468.60  5332.4  468.34  5353.0  469.33  5374.2  469.67
#Mann=5,-1,0
  4803.2    0.05       0  4848.9    0.16       0  4933.5    0.05       0
  4937.5    0.16       0  4998.4    0.05       0
Bank Sta=4933.5,4937.5
Exp/Cntr=0.3,0.1

Type RM Length L Ch R = 1,1375,114,114,114
BEGIN DESCRIPTION:
Purtis Creek Trib A1375.17
END DESCRIPTION:
XS GIS Cut Line= 3
      2756738.54      6833747.23      2756737.53      6833901.96
      2756737.98      6834146.83
#Sta/Elev= 30
  4847.5  468.56  4891.3  467.41  4901.3  466.82  4911.3  465.56  4921.3  463.08
  4931.3  463.29  4941.3  461.21  4961.3  461.57  4971.3  462.12  4981.3  461.08
  4991.3  458.60  4997.2  458.32  4997.5  457.82  5001.0  457.82  5001.2  458.32
  5004.2  458.32  5011.3  463.22  5014.8  463.19  5031.3  463.17  5041.3  464.04
  5071.3  463.43  5081.3  463.45  5091.3  463.16  5101.3  462.50  5121.3  462.35
  5131.3  462.86  5201.3  464.89  5211.3  465.38  5231.3  467.09  5247.1  467.73
#Mann=4,-1,0
  4847.5    0.16       0  4997.2    0.07       0  5001.2    0.16       0
  5014.8    0.05       0
Bank Sta=4997.2,5001.2
Exp/Cntr=0.3,0.1

Type RM Length L Ch R = 1,1261,146,146,146
BEGIN DESCRIPTION:
Purtis Creek Trib A1260.6
END DESCRIPTION:
XS GIS Cut Line= 3
      2756645.01      6833786.32      2756650.54      6833936.93
      2756656.66      6834136.62
#Sta/Elev= 30
  4850.5  467.43  4855.4  467.43  4865.2  467.04  4885.2  466.95  4895.2  466.70
  4905.2  465.89  4925.2  463.93  4935.2  463.20  4945.2  462.70  4955.3  460.81
  4965.3  460.95  4973.3  457.53  4973.5  457.03  4977.0  457.03  4977.3  457.53
  4985.3  462.63  4995.3  461.15  5000.7  462.04  5013.3  462.26  5018.3  462.96
  5025.3  462.53  5035.3  462.90  5055.3  463.11  5078.4  463.58  5135.3  463.93
  5145.4  464.30  5165.4  465.46  5175.4  465.74  5195.4  465.90  5201.0  466.14
#Mann=4,-1,0
  4850.5    0.16       0  4973.3    0.07       0  4977.3    0.16       0
  5078.4    0.05       0
Bank Sta=4973.3,4977.3
Exp/Cntr=0.3,0.1

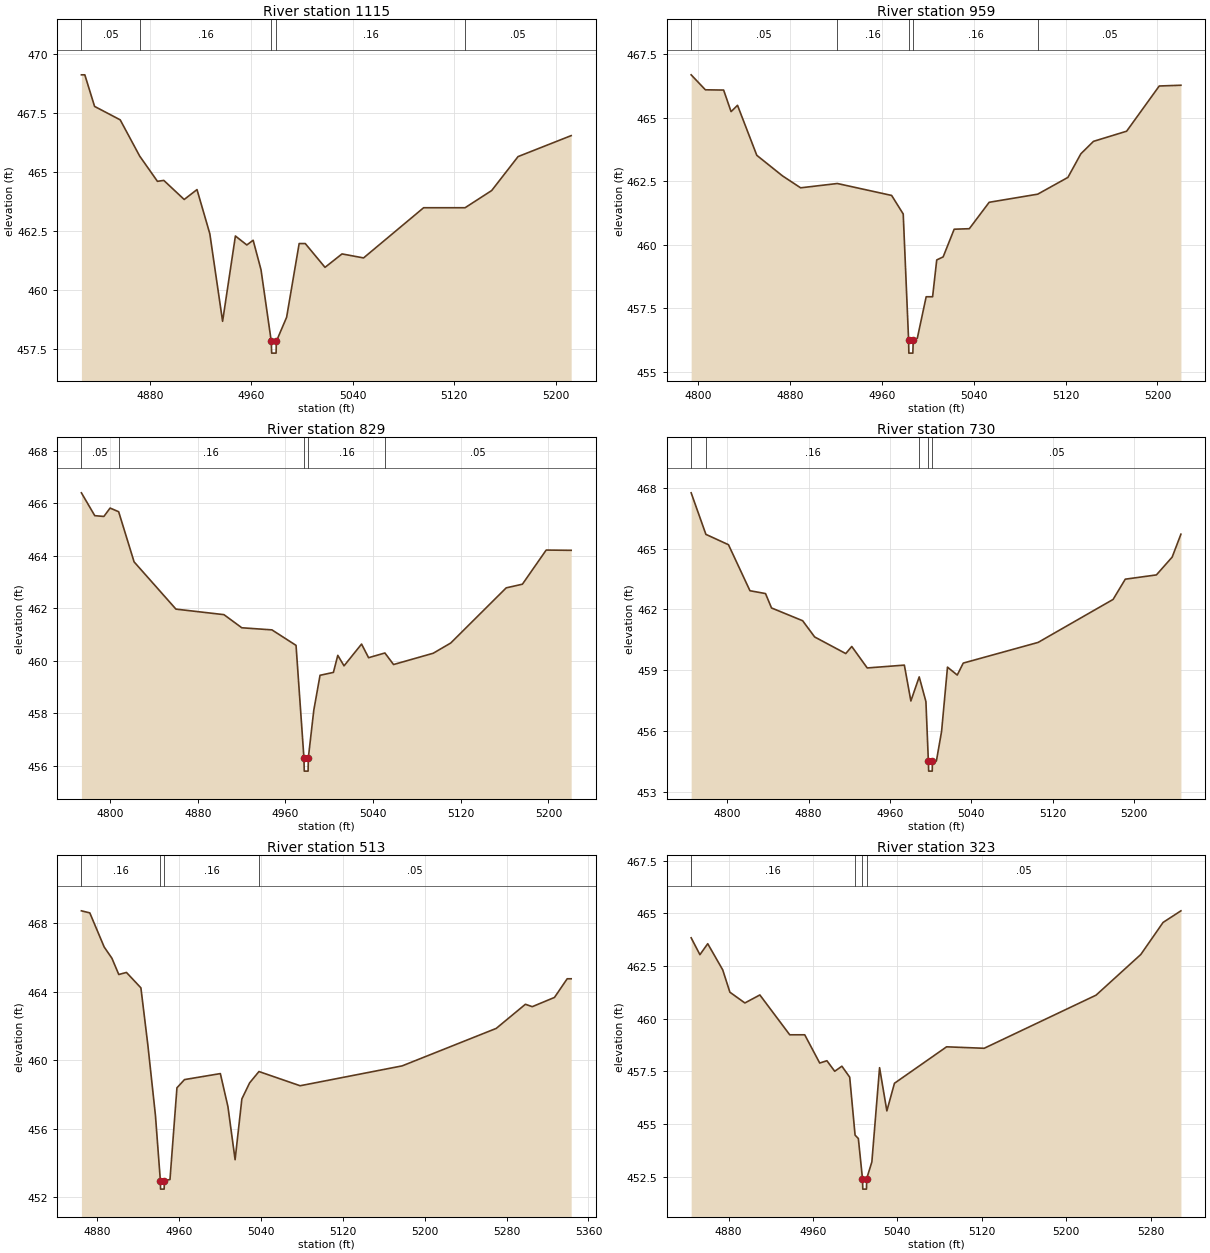
Type RM Length L Ch R = 1,1115,156,156,156
BEGIN DESCRIPTION:
Purtis Creek Trib A1114.65
END DESCRIPTION:
XS GIS Cut Line= 3
      2756501.88      6833780.73      2756527.02      6833955.58
      2756557.79      6834163.06
#Sta/Elev= 30
  4825.9  469.13  4828.6  469.13  4836.3  467.79  4856.5  467.22  4871.9  465.68
  4885.9  464.61  4890.9  464.65  4907.0  463.84  4917.1  464.26  4927.2  462.39
  4937.3  458.67  4947.4  462.29  4956.4  461.91  4961.4  462.11  4967.6  460.86
  4975.7  457.82  4976.0  457.32  4979.5  457.32  4979.7  457.82  4987.8  458.84
  4997.7  461.97  5002.5  461.97  5018.1  460.96  5031.5  461.53  5048.5  461.36
  5095.9  463.49  5128.6  463.49  5149.6  464.22  5170.4  465.66  5212.3  466.55
#Mann=5,-1,0
  4825.9    0.05       0  4871.9    0.16       0  4975.7    0.07       0
  4979.7    0.16       0  5128.6    0.05       0
Bank Sta=4975.7,4979.7
Exp/Cntr=0.3,0.1

Type RM Length L Ch R = 1,959,130,130,130
BEGIN DESCRIPTION:
Purtis Creek Trib A958.51
END DESCRIPTION:
XS GIS Cut Line= 3
      2756315.08      6833795.63      2756407.91      6833981.91
      2756500.43      6834180.05
#Sta/Elev= 30
  4793.7  466.69  4806.1  466.10  4822.0  466.09  4828.5  465.24  4834.1  465.49
  4850.9  463.52  4873.3  462.71  4889.1  462.24  4921.1  462.41  4968.4  461.94
  4978.5  461.21  4983.2  456.23  4983.4  455.73  4986.9  455.73  4987.2  456.23
  4990.8  456.32  4998.5  457.95  5004.1  457.95  5007.7  459.40  5013.3  459.52
  5022.9  460.61  5036.1  460.63  5053.4  461.67  5095.7  461.99  5122.0  462.65
  5133.3  463.58  5144.3  464.07  5173.2  464.47  5201.6  466.25  5220.5  466.28
#Mann=5,-1,0
  4793.7    0.05       0  4921.1    0.16       0  4983.2    0.07       0
  4987.2    0.16       0  5095.7    0.05       0
Bank Sta=4983.2,4987.2
Exp/Cntr=0.3,0.1

Type RM Length L Ch R = 1,829,99,99,99
BEGIN DESCRIPTION:
Purtis Creek Trib A828.98
END DESCRIPTION:
XS GIS Cut Line= 3
      2756190.04      6833840.27      2756297.21      6834039.83
      2756403.64      6834232.92
#Sta/Elev= 30
  4773.8  466.39  4786.0  465.52  4794.3  465.49  4800.0  465.81  4807.8  465.67
  4821.9  463.76  4860.1  461.96  4903.9  461.75  4920.2  461.25  4947.7  461.17
  4969.7  460.58  4976.9  456.29  4977.2  455.79  4980.7  455.79  4980.9  456.29
  4985.9  458.11  4991.6  459.44  5003.8  459.55  5007.8  460.20  5013.5  459.80
  5029.5  460.63  5035.9  460.11  5050.8  460.29  5058.7  459.85  5094.9  460.28
  5110.9  460.67  5161.5  462.77  5176.3  462.91  5198.0  464.21  5220.8  464.20
#Mann=5,-1,0
  4773.8    0.05       0  4807.8    0.16       0  4976.9    0.07       0
  4980.9    0.16       0  5050.8    0.05       0
Bank Sta=4976.9,4980.9
Exp/Cntr=0.3,0.1

Type RM Length L Ch R = 1,730,217,217,217
BEGIN DESCRIPTION:
Purtis Creek Trib A729.72
END DESCRIPTION:
XS GIS Cut Line= 3
      2756099.28      6833908.39      2756225.74      6834108.45
      2756352.78      6834317.73
#Sta/Elev= 30
  4764.5  467.75  4779.0  465.70  4801.2  465.19  4822.3  462.92  4837.6  462.78
  4843.5  462.07  4874.1  461.44  4885.9  460.64  4916.5  459.82  4922.4  460.17
  4937.6  459.11  4974.1  459.25  4980.5  457.48  4988.7  458.67  4995.3  457.45
  4997.7  454.52  4998.0  454.02  5001.5  454.02  5001.7  454.52  5005.6  454.52
  5010.7  455.98  5016.5  459.15  5026.1  458.76  5032.0  459.35  5105.6  460.37
  5179.3  462.49  5191.3  463.49  5221.9  463.70  5237.4  464.58  5246.0  465.71
#Mann=5,-1,0
  4764.5    0.05       0  4779.0    0.16       0  4988.7    0.05       0
  4997.7    0.05       0  5001.7    0.05       0
Bank Sta=4997.7,5001.7
Exp/Cntr=0.3,0.1

Type RM Length L Ch R = 1,513,190,190,190
BEGIN DESCRIPTION:
Purtis Creek Trib A513.1
END DESCRIPTION:
XS GIS Cut Line= 3
      2755950.14      6834044.91      2756050.75      6834136.52
      2756306.82      6834363.57
#Sta/Elev= 30
  4864.8  468.72  4873.0  468.60  4887.1  466.60  4894.6  465.95  4901.3  465.00
  4908.8  465.12  4922.9  464.22  4929.7  460.88  4937.1  456.77  4941.9  452.96
  4942.1  452.46  4945.6  452.46  4945.9  452.96  4951.3  453.02  4958.1  458.38
  4965.5  458.86  5000.5  459.21  5007.9  457.28  5014.9  454.18  5021.5  457.73
  5029.1  458.67  5038.2  459.33  5078.4  458.50  5178.0  459.66  5269.9  461.85
  5298.4  463.26  5305.1  463.12  5326.8  463.66  5339.2  464.75  5343.1  464.75
#Mann=4,-1,0
  4864.8    0.16       0  4941.9    0.07       0  4945.9    0.16       0
  5038.2    0.05       0
Bank Sta=4941.9,4945.9
Exp/Cntr=0.3,0.1

Type RM Length L Ch R = 1,323,240,240,240
BEGIN DESCRIPTION:
Purtis Creek Trib A322.63
END DESCRIPTION:
XS GIS Cut Line= 3
      2755888.34      6834146.66      2755994.81      6834264.01
      2756205.22      6834485.57
#Sta/Elev= 30
  4844.6  463.84  4852.9  463.04  4860.3  463.56  4874.5  462.32  4881.3  461.26
  4895.5  460.75  4909.7  461.13  4938.0  459.24  4952.2  459.24  4966.4  457.90
  4973.2  458.01  4980.6  457.51  4987.4  457.75  4994.8  457.23  4999.9  454.48
  5003.0  454.32  5006.9  452.42  5007.2  451.92  5010.7  451.92  5010.9  452.42
  5015.8  453.21  5023.1  457.68  5030.0  455.63  5037.2  456.94  5086.6  458.67
  5122.2  458.60  5228.2  461.12  5270.6  463.05  5291.7  464.57  5308.6  465.12
#Mann=4,-1,0
  4844.6    0.16       0  4999.9    0.05       0  5006.9    0.05       0
  5010.9    0.05       0
Bank Sta=5006.9,5010.9
Exp/Cntr=0.3,0.1

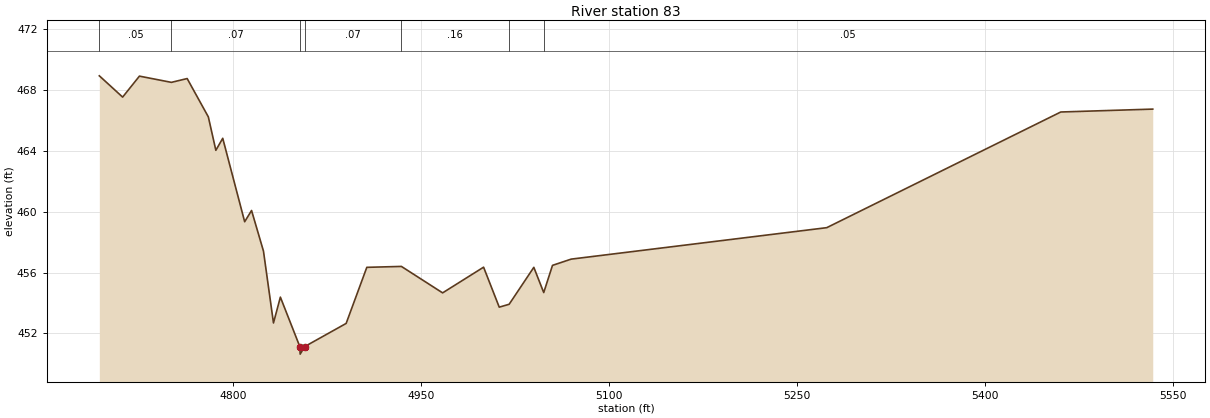
Type RM Length L Ch R = 1,83,0,0,0
BEGIN DESCRIPTION:
Purtis Creek Trib A82.799
END DESCRIPTION:
XS GIS Cut Line= 4
      2755661.95      6834081.94      2755789.91      6834360.67
      2755852.48      6834452.14      2756226.76      6834649.84
#Sta/Elev= 30
  4693.3  468.95  4711.9  467.55  4725.3  468.93  4750.8  468.52  4763.4  468.77
  4780.3  466.25  4786.3  464.05  4791.8  464.84  4809.3  459.35  4814.8  460.09
  4824.3  457.42  4832.3  452.69  4837.8  454.39  4853.3  451.14  4853.6  450.64
  4857.3  451.14  4890.3  452.66  4906.8  456.35  4934.4  456.41  4967.3  454.67
  5000.0  456.36  5012.5  453.73  5020.4  453.92  5040.1  456.35  5048.0  454.69
  5055.0  456.48  5069.9  456.89  5273.9  458.96  5460.7  466.57  5534.1  466.76
#Mann=7,-1,0
  4693.3    0.05       0  4750.8    0.07       0  4853.3    0.07       0
  4857.3    0.07       0  4934.4    0.16       0  5020.4    0.12       0
  5048.0    0.05       0
Bank Sta=4853.3,4857.3
Exp/Cntr=0.3,0.1

Chan Stop Cuts=-1