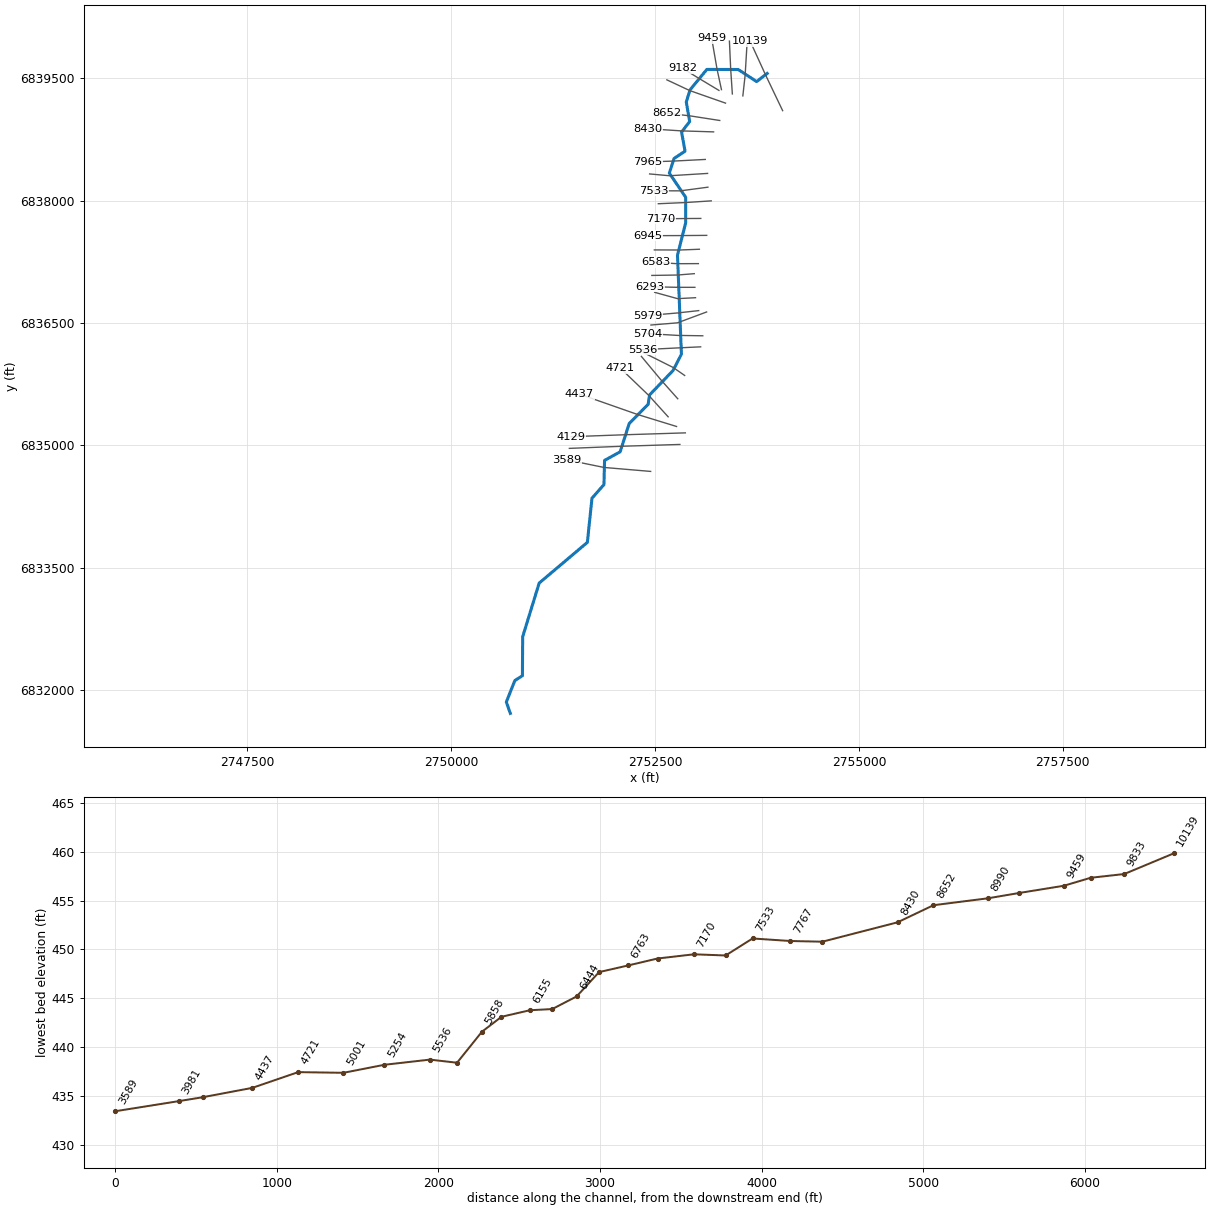
--- Purtis Creek Trib B.prj (project) ---

Proj Title=Purtis Creek Trib B Base Level Engineering
Current Plan=p01
Default Exp/Contr=0.3,0.1
English Units
Geom File=g01
Flow File=f01
Plan File=p01
BEGIN DESCRIPTION:
Purtis Creek Trib B
END DESCRIPTION:

--- Purtis Creek Trib B.p01 (plan) ---

Plan Title=Multiple Run
Short Identifier=Multiple
Geom File=g01
Flow File=f01
Subcritical Flow
K Sum by GR= 0
Std Step Tol= 0.01
Critical Tol= 0.01
Num of Std Step Trials= 20
Max Error Tol= 0.3
Flow Tol Ratio= 0.001
Split Flow NTrial= 30
Split Flow Tol= 0.02
Split Flow Ratio= 0.02
Log Output Level= 0
Friction Slope Method= 1
Unsteady Friction Slope Method= 2
Unsteady Bridges Friction Slope Method= 1
Parabolic Critical Depth
Global Vel Dist=  1 , 1 , 1
Global Log Level= 0
CheckData=True
Encroach Param= -1, 0, 0, 0
BEGIN DESCRIPTION:
Multiple Run
END DESCRIPTION:

--- Purtis Creek Trib B.f01 (steady flow) ---

Flow Title=Multiple
Number of Profiles=7
Profile Names=10-year,25-year,50-year,1pct_min,100-year,1pct_plu,500-year
River Rch & RM= Purtis Creek Tri,Reach-1,10139
     521     695     836     500     997    1990    1422
River Rch & RM= Purtis Creek Tri,Reach-1,6293
     798    1087    1326     802    1600    3193    2339
Boundary for River Rch & Prof#=Purtis Creek Tri,Reach-1,1
Up Type=0
Dn Type=3
Dn Slope=0.005
Boundary for River Rch & Prof#=Purtis Creek Tri,Reach-1,2
Up Type=0
Dn Type=3
Dn Slope=0.005
Boundary for River Rch & Prof#=Purtis Creek Tri,Reach-1,3
Up Type=0
Dn Type=3
Dn Slope=0.005
Boundary for River Rch & Prof#=Purtis Creek Tri,Reach-1,4
Up Type=0
Dn Type=3
Dn Slope=0.005
Boundary for River Rch & Prof#=Purtis Creek Tri,Reach-1,5
Up Type=0
Dn Type=3
Dn Slope=0.005
Boundary for River Rch & Prof#=Purtis Creek Tri,Reach-1,6
Up Type=0
Dn Type=3
Dn Slope=0.005
Boundary for River Rch & Prof#=Purtis Creek Tri,Reach-1,7
Up Type=0
Dn Type=3
Dn Slope=0.005

--- Purtis Creek Trib B.g01 (geometry) ---

Geom Title=Existing Conditions

River Reach=Purtis Creek Tri,Reach-1
Reach XY= 30
      2753876.00      6839561.00      2753746.20      6839460.61
      2753520.14      6839608.94      2753135.59      6839609.80
      2752929.82      6839359.41      2752883.56      6839211.00
      2752924.79      6838970.59      2752825.96      6838841.01
      2752868.31      6838607.33      2752733.75      6838517.45
      2752675.54      6838338.16      2752876.04      6838041.02
      2752875.48      6837726.22      2752775.64      6837331.15
      2752823.91      6836116.49      2752720.82      6835916.14
      2752433.79      6835617.43      2752415.48      6835501.22
      2752184.14      6835267.06      2752072.34      6834919.17
      2751881.36      6834813.70      2751873.83      6834516.44
      2751727.05      6834350.57      2751670.54      6833808.55
      2751079.81      6833309.44      2750877.22      6832650.50
      2750874.36      6832172.83      2750781.46      6832113.66
      2750676.72      6831850.32      2750726.00      6831711.00

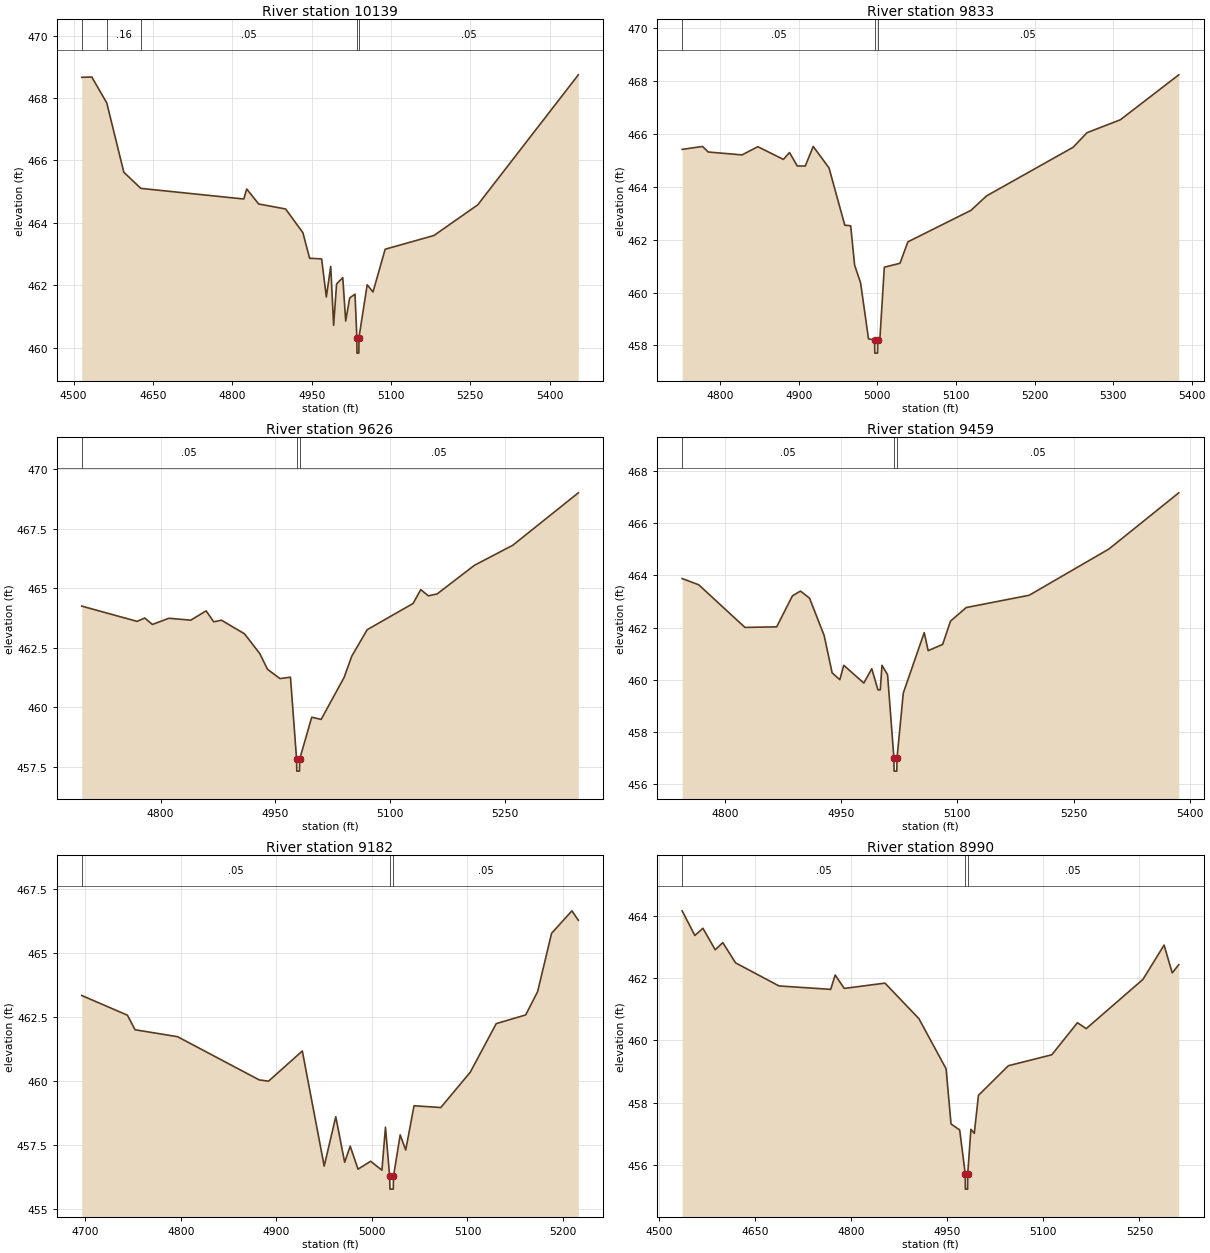
Type RM Length L Ch R = 1,10139,306,306,306
BEGIN DESCRIPTION:
Purtis Creek Trib B10138.605
END DESCRIPTION:
XS GIS Cut Line= 3
      2754065.08      6839103.87      2753856.15      6839541.01
      2753667.62      6839954.12
#Sta/Elev= 30
  4515.5  468.66  4534.5  468.67  4562.8  467.84  4595.0  465.62  4627.2  465.10
  4821.8  464.76  4827.3  465.08  4850.0  464.60  4900.9  464.44  4933.5  463.68
  4946.2  462.86  4968.9  462.84  4977.8  461.62  4986.1  462.60  4991.6  460.71
  4997.2  462.04  5008.9  462.24  5014.4  460.85  5022.0  461.59  5032.0  461.71
  5035.5  460.32  5035.7  459.82  5039.2  459.82  5039.5  460.32  5055.0  462.01
  5066.0  461.78  5089.0  463.15  5181.2  463.59  5263.8  464.57  5454.1  468.74
#Mann=5,-1,0
  4515.5    0.05       0  4562.8    0.16       0  4627.2    0.05       0
  5035.5    0.05       0  5039.5    0.05       0
Bank Sta=5035.5,5039.5
Exp/Cntr=0.3,0.1

Type RM Length L Ch R = 1,9833,207,207,207
BEGIN DESCRIPTION:
Purtis Creek Trib B9833.23
END DESCRIPTION:
XS GIS Cut Line= 3
      2753577.09      6839285.26      2753604.82      6839535.33
      2753627.94      6839915.13
#Sta/Elev= 30
  4751.5  465.42  4777.4  465.53  4784.7  465.32  4827.7  465.21  4847.8  465.52
  4880.4  465.04  4888.1  465.30  4898.1  464.79  4908.2  464.79  4918.3  465.53
  4938.4  464.72  4958.5  462.55  4966.0  462.53  4971.0  461.04  4978.6  460.37
  4988.7  458.25  4996.4  458.21  4996.7  457.71  5000.2  457.71  5000.4  458.21
  5003.1  458.21  5008.8  460.96  5028.8  461.11  5038.8  461.92  5119.0  463.11
  5139.0  463.66  5249.2  465.50  5266.8  466.05  5309.3  466.54  5383.6  468.24
#Mann=3,-1,0
  4751.5    0.05       0  4996.4    0.05       0  5000.4    0.05       0
Bank Sta=4996.4,5000.4
Exp/Cntr=0.3,0.1

Type RM Length L Ch R = 1,9626,167,167,167
BEGIN DESCRIPTION:
Purtis Creek Trib B9626.3
END DESCRIPTION:
XS GIS Cut Line= 3
      2753448.33      6839308.88      2753428.15      6839611.41
      2753412.46      6839956.65
#Sta/Elev= 30
  4697.1  464.25  4769.4  463.61  4779.4  463.75  4789.4  463.48  4810.9  463.74
  4839.5  463.66  4859.6  464.05  4869.6  463.59  4879.6  463.66  4909.7  463.09
  4929.7  462.26  4939.8  461.60  4956.1  461.21  4969.8  461.27  4977.8  457.83
  4978.1  457.33  4981.6  457.33  4981.8  457.83  4997.6  459.59  5009.9  459.50
  5039.9  461.26  5049.9  462.15  5070.0  463.26  5130.0  464.36  5140.0  464.94
  5150.0  464.68  5161.4  464.76  5210.1  465.96  5260.2  466.80  5345.9  469.00
#Mann=3,-1,0
  4697.1    0.05       0  4977.8    0.05       0  4981.8    0.05       0
Bank Sta=4977.8,4981.8
Exp/Cntr=0.3,0.1

Type RM Length L Ch R = 1,9459,277,277,277
BEGIN DESCRIPTION:
Purtis Creek Trib B9459.29
END DESCRIPTION:
XS GIS Cut Line= 3
      2753314.83      6839361.86      2753261.03      6839611.69
      2753194.91      6839991.12
#Sta/Elev= 30
  4745.1  463.88  4766.5  463.64  4826.1  462.01  4867.0  462.03  4887.4  463.22
  4897.7  463.40  4909.4  463.13  4928.3  461.70  4938.6  460.27  4948.5  460.01
  4953.6  460.56  4979.5  459.88  4989.7  460.43  4997.7  459.62  5000.7  459.62
  5002.9  460.56  5010.1  460.20  5018.3  457.01  5018.5  456.51  5022.0  456.51
  5022.3  457.01  5030.4  459.50  5057.4  461.81  5062.5  461.12  5081.2  461.36
  5091.3  462.25  5111.6  462.77  5192.8  463.24  5295.7  465.01  5385.8  467.16
#Mann=3,-1,0
  4745.1    0.05       0  5018.3    0.05       0  5022.3    0.05       0
Bank Sta=5018.3,5022.3
Exp/Cntr=0.3,0.1

Type RM Length L Ch R = 1,9182,192,192,192
BEGIN DESCRIPTION:
Purtis Creek Trib B9181.63
END DESCRIPTION:
XS GIS Cut Line= 3
      2753283.79      6839352.49      2753017.34      6839512.70
      2752839.72      6839622.27
#Sta/Elev= 30
  4696.4  463.34  4744.2  462.57  4752.2  462.00  4796.6  461.73  4882.1  460.04
  4891.8  459.99  4927.2  461.17  4950.1  456.67  4962.2  458.60  4971.5  456.82
  4977.3  457.45  4985.5  456.55  4998.7  456.86  5010.5  456.51  5014.2  458.19
  5018.6  456.27  5018.9  455.77  5022.4  455.77  5022.6  456.27  5029.6  457.89
  5035.4  457.30  5044.1  459.03  5072.1  458.96  5102.9  460.34  5130.1  462.24
  5160.9  462.58  5173.4  463.49  5188.0  465.77  5209.3  466.65  5216.0  466.28
#Mann=3,-1,0
  4696.4    0.05       0  5018.6    0.05       0  5022.6    0.05       0
Bank Sta=5018.6,5022.6
Exp/Cntr=0.3,0.1

Type RM Length L Ch R = 1,8990,338,338,338
BEGIN DESCRIPTION:
Purtis Creek Trib B8989.52
END DESCRIPTION:
XS GIS Cut Line= 3
      2753364.72      6839196.41      2752925.77      6839350.30
      2752645.31      6839482.04
#Sta/Elev= 30
  4536.4  464.16  4556.2  463.37  4568.8  463.60  4588.0  462.91  4599.8  463.14
  4619.8  462.49  4687.5  461.75  4768.2  461.64  4775.2  462.10  4789.4  461.67
  4852.9  461.84  4905.9  460.70  4948.3  459.09  4956.0  457.32  4969.5  457.13
  4978.1  455.73  4978.4  455.23  4981.9  455.23  4982.1  455.73  4987.0  457.15
  4992.3  457.02  4998.8  458.24  5045.5  459.19  5113.2  459.54  5153.3  460.57
  5167.0  460.38  5255.5  461.96  5288.5  463.06  5301.2  462.17  5311.4  462.43
#Mann=3,-1,0
  4536.4    0.05       0  4978.1    0.05       0  4982.1    0.05       0
Bank Sta=4978.1,4982.1
Exp/Cntr=0.3,0.1

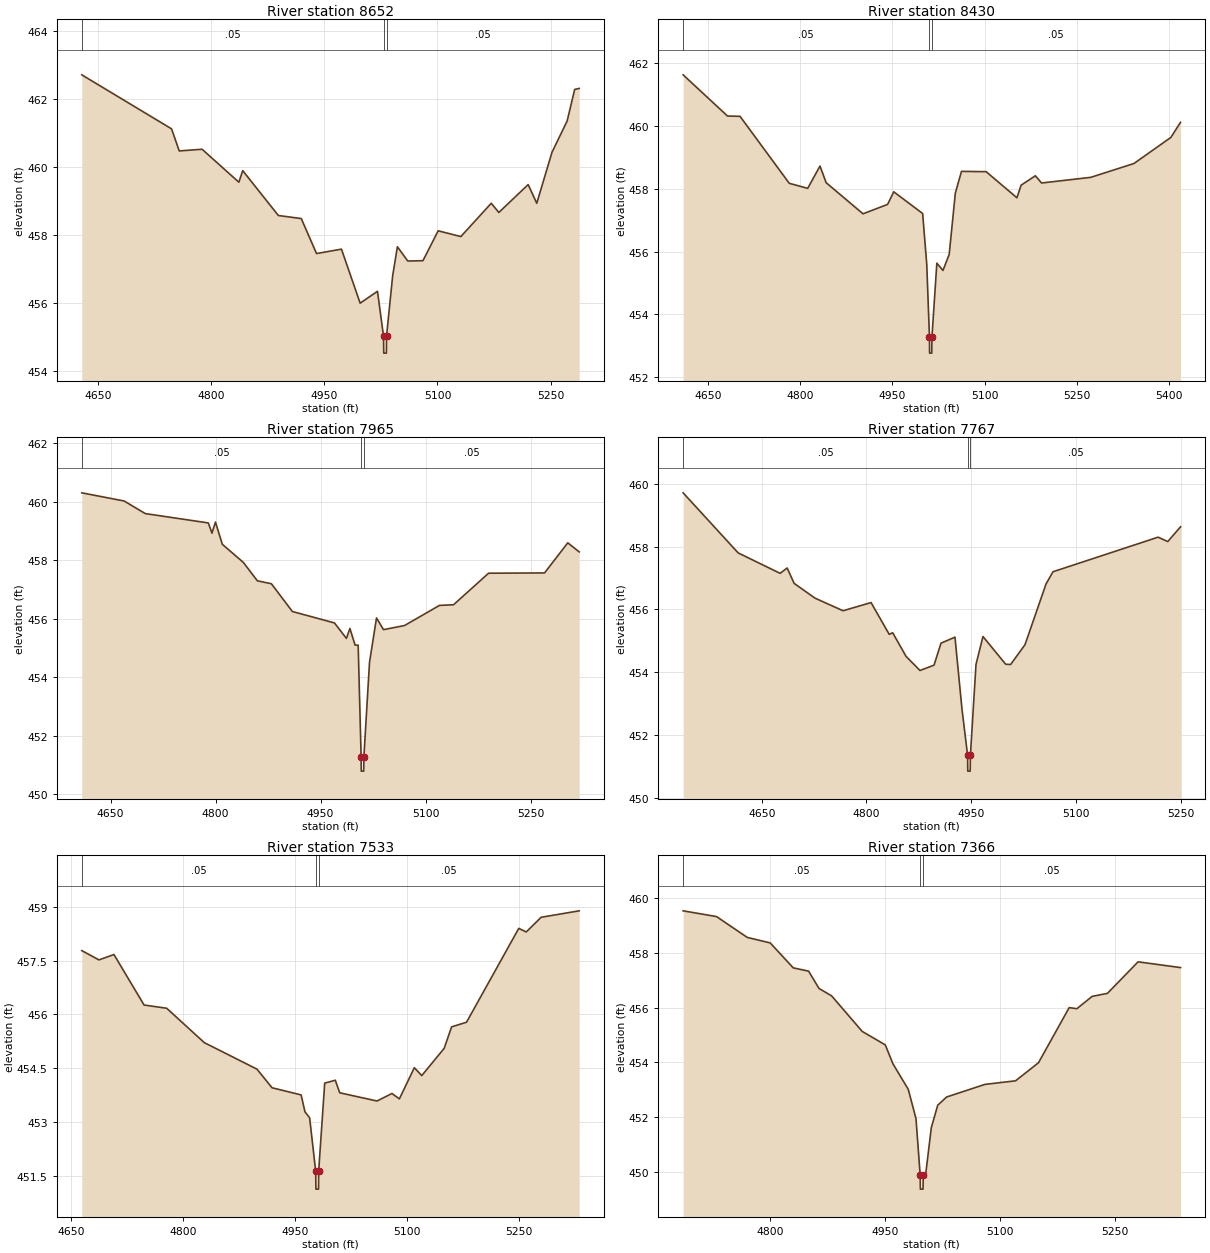
Type RM Length L Ch R = 1,8652,222,222,222
BEGIN DESCRIPTION:
Purtis Creek Trib B8652.2
END DESCRIPTION:
XS GIS Cut Line= 3
      2753293.73      6838983.58      2752926.53      6839040.49
      2752640.09      6839073.28
#Sta/Elev= 30
  4628.1  462.71  4747.2  461.12  4757.4  460.47  4787.7  460.52  4836.5  459.55
  4841.6  459.89  4888.9  458.57  4919.3  458.48  4939.5  457.45  4972.6  457.58
  4997.4  455.99  5020.4  456.34  5028.4  455.02  5028.7  454.52  5032.2  454.52
  5032.4  455.02  5040.5  456.79  5046.8  457.65  5060.6  457.23  5080.7  457.24
  5100.9  458.12  5131.0  457.95  5171.3  458.93  5181.4  458.66  5220.3  459.48
  5231.7  458.93  5251.9  460.43  5272.0  461.35  5282.0  462.28  5288.0  462.31
#Mann=3,-1,0
  4628.1    0.05       0  5028.4    0.05       0  5032.4    0.05       0
Bank Sta=5028.4,5032.4
Exp/Cntr=0.3,0.1

Type RM Length L Ch R = 1,8430,465,465,465
BEGIN DESCRIPTION:
Purtis Creek Trib B8430.39
END DESCRIPTION:
XS GIS Cut Line= 3
      2753218.58      6838843.61      2752827.09      6838855.79
      2752410.32      6838882.44
#Sta/Elev= 30
  4609.5  461.62  4681.7  460.31  4702.1  460.30  4782.2  458.17  4812.2  458.01
  4832.2  458.72  4842.2  458.19  4902.2  457.20  4942.2  457.50  4952.2  457.90
  4999.2  457.21  5005.9  455.59  5010.3  453.27  5010.5  452.77  5014.0  452.77
  5014.3  453.27  5022.3  455.63  5032.3  455.40  5042.4  455.91  5052.4  457.86
  5062.4  458.55  5102.5  458.54  5152.6  457.71  5159.4  458.11  5182.6  458.41
  5192.7  458.18  5272.8  458.36  5343.0  458.80  5403.1  459.63  5418.8  460.11
#Mann=3,-1,0
  4609.5    0.05       0  5010.3    0.05       0  5014.3    0.05       0
Bank Sta=5010.3,5014.3
Exp/Cntr=0.3,0.1

Type RM Length L Ch R = 1,7965,198,198,198
BEGIN DESCRIPTION:
Purtis Creek Trib B7964.59
END DESCRIPTION:
XS GIS Cut Line= 3
      2753116.54      6838505.61      2752722.19      6838485.24
      2752406.51      6838475.44
#Sta/Elev= 30
  4608.8  460.31  4669.4  460.03  4699.5  459.60  4789.6  459.28  4794.8  458.93
  4799.8  459.31  4809.6  458.55  4839.6  457.93  4859.7  457.30  4879.7  457.20
  4909.7  456.25  4969.8  455.86  4986.9  455.33  4991.9  455.67  4999.3  455.10
  5003.7  455.10  5007.9  451.29  5008.1  450.79  5011.6  450.79  5011.9  451.29
  5019.9  454.51  5029.9  456.03  5039.9  455.63  5069.9  455.77  5119.9  456.46
  5139.9  456.48  5190.0  457.56  5270.0  457.57  5303.2  458.60  5319.5  458.29
#Mann=3,-1,0
  4608.8    0.05       0  5007.9    0.05       0  5011.9    0.05       0
Bank Sta=5007.9,5011.9
Exp/Cntr=0.3,0.1

Type RM Length L Ch R = 1,7767,234,234,234
BEGIN DESCRIPTION:
Purtis Creek Trib B7767.25
END DESCRIPTION:
XS GIS Cut Line= 3
      2753144.69      6838334.15      2752678.91      6838305.56
      2752434.07      6838327.78
#Sta/Elev= 30
  4537.4  459.71  4616.2  457.80  4676.3  457.15  4686.4  457.32  4696.4  456.83
  4726.4  456.36  4766.5  455.96  4806.6  456.22  4832.6  455.21  4837.6  455.26
  4856.7  454.51  4876.7  454.06  4896.8  454.23  4906.8  454.93  4926.8  455.12
  4936.8  452.84  4944.9  451.36  4945.1  450.86  4948.6  450.86  4948.9  451.36
  4956.9  454.25  4966.9  455.14  4999.4  454.26  5006.5  454.25  5027.1  454.88
  5057.2  456.81  5067.2  457.20  5217.8  458.30  5231.6  458.16  5249.9  458.63
#Mann=3,-1,0
  4537.4    0.05       0  4944.9    0.05       0  4948.9    0.05       0
Bank Sta=4944.9,4948.9
Exp/Cntr=0.3,0.1

Type RM Length L Ch R = 1,7533,167,167,167
BEGIN DESCRIPTION:
Purtis Creek Trib B7532.68
END DESCRIPTION:
XS GIS Cut Line= 3
      2753148.76      6838165.39      2752811.94      6838120.44
      2752485.05      6838121.19
#Sta/Elev= 30
  4664.1  457.78  4687.1  457.52  4707.2  457.67  4747.6  456.26  4777.9  456.17
  4828.3  455.21  4898.9  454.47  4919.1  453.95  4958.1  453.75  4963.2  453.28
  4969.5  453.11  4977.6  451.62  4977.9  451.12  4981.4  451.12  4981.6  451.62
  4989.7  454.08  5003.9  454.16  5009.8  453.81  5059.8  453.58  5079.8  453.79
  5089.8  453.64  5109.8  454.51  5119.8  454.29  5149.8  455.05  5159.8  455.65
  5179.8  455.78  5249.8  458.40  5259.8  458.30  5279.8  458.71  5330.8  458.89
#Mann=3,-1,0
  4664.1    0.05       0  4977.6    0.05       0  4981.6    0.05       0
Bank Sta=4977.6,4981.6
Exp/Cntr=0.3,0.1

Type RM Length L Ch R = 1,7366,196,196,196
BEGIN DESCRIPTION:
Purtis Creek Trib B7365.77
END DESCRIPTION:
XS GIS Cut Line= 3
      2753189.60      6837997.53      2752876.02      6837976.95
      2752540.60      6837962.35
#Sta/Elev= 30
  4685.9  459.53  4729.6  459.32  4769.7  458.56  4799.7  458.36  4829.8  457.45
  4849.9  457.33  4863.4  456.70  4879.9  456.43  4920.0  455.13  4950.1  454.64
  4960.1  453.95  4980.1  453.02  4990.2  451.95  4995.7  449.88  4995.9  449.38
  4999.4  449.38  4999.7  449.88  5002.7  449.88  5010.2  451.62  5018.6  452.44
  5030.2  452.74  5080.3  453.20  5120.3  453.33  5150.3  453.99  5190.4  456.00
  5200.4  455.96  5220.4  456.41  5240.4  456.52  5280.4  457.67  5335.9  457.46
#Mann=3,-1,0
  4685.9    0.05       0  4995.7    0.05       0  4999.7    0.05       0
Bank Sta=4995.7,4999.7
Exp/Cntr=0.3,0.1

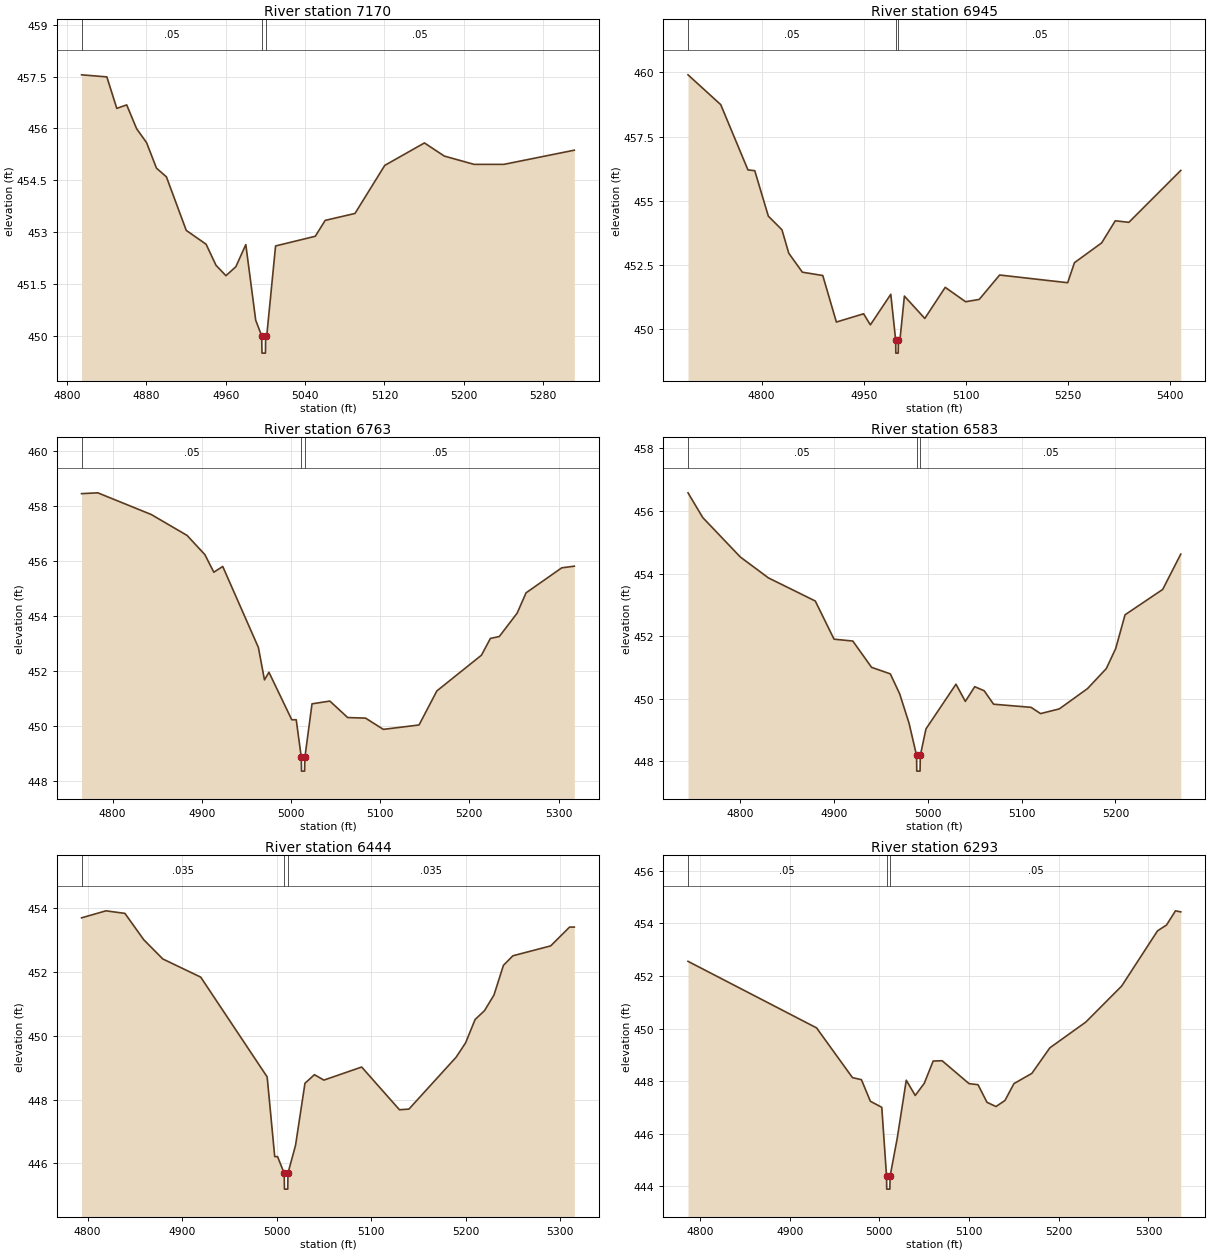
Type RM Length L Ch R = 1,7170,225,225,225
BEGIN DESCRIPTION:
Purtis Creek Trib B7169.73
END DESCRIPTION:
XS GIS Cut Line= 3
      2753061.46      6837781.97      2752874.86      6837780.92
      2752564.99      6837776.88
#Sta/Elev= 30
  4814.8  457.55  4840.3  457.49  4850.3  456.58  4860.3  456.68  4870.3  455.99
  4880.3  455.59  4890.3  454.85  4900.3  454.60  4920.3  453.05  4940.3  452.65
  4950.3  452.04  4960.3  451.74  4970.3  452.00  4980.3  452.64  4990.3  450.45
  4996.3  450.00  4996.6  449.50  5000.1  449.50  5000.3  450.00  5001.4  450.00
  5010.3  452.60  5050.3  452.88  5060.3  453.34  5090.3  453.54  5120.3  454.93
  5160.3  455.58  5180.3  455.20  5210.3  454.96  5240.3  454.96  5311.3  455.37
#Mann=3,-1,0
  4814.8    0.05       0  4996.3    0.05       0  5000.3    0.05       0
Bank Sta=4996.3,5000.3
Exp/Cntr=0.3,0.1

Type RM Length L Ch R = 1,6945,182,182,182
BEGIN DESCRIPTION:
Purtis Creek Trib B6944.52
END DESCRIPTION:
XS GIS Cut Line= 3
      2753134.07      6837574.18      2752822.62      6837571.83
      2752409.68      6837570.48
#Sta/Elev= 30
  4691.8  459.90  4739.9  458.74  4779.9  456.20  4789.9  456.17  4809.9  454.40
  4829.9  453.87  4839.9  452.96  4859.9  452.22  4889.9  452.09  4909.9  450.28
  4949.9  450.60  4959.9  450.17  4989.9  451.36  4997.1  449.57  4997.3  449.07
  5000.8  449.07  5001.1  449.57  5003.3  449.57  5009.9  451.29  5039.9  450.42
  5069.9  451.63  5099.9  451.07  5119.9  451.16  5149.9  452.11  5249.9  451.81
  5259.9  452.59  5299.9  453.36  5319.9  454.22  5339.9  454.16  5416.2  456.18
#Mann=3,-1,0
  4691.8    0.05       0  4997.1    0.05       0  5001.1    0.05       0
Bank Sta=4997.1,5001.1
Exp/Cntr=0.3,0.1

Type RM Length L Ch R = 1,6763,180,180,180
BEGIN DESCRIPTION:
Purtis Creek Trib B6762.95
END DESCRIPTION:
XS GIS Cut Line= 3
      2753044.18      6837404.02      2752806.33      6837394.80
      2752491.86      6837395.85
#Sta/Elev= 30
  4765.2  458.46  4783.4  458.49  4843.4  457.70  4883.5  456.94  4903.5  456.24
  4913.5  455.60  4923.5  455.81  4963.5  452.86  4970.3  451.68  4975.3  451.96
  5000.9  450.23  5005.9  450.23  5011.6  448.86  5011.8  448.36  5015.3  448.36
  5015.6  448.86  5023.6  450.81  5043.6  450.91  5063.6  450.31  5083.6  450.29
  5103.6  449.88  5143.6  450.04  5163.6  451.28  5213.6  452.58  5223.6  453.19
  5233.6  453.26  5253.6  454.11  5263.6  454.85  5303.6  455.76  5317.7  455.82
#Mann=3,-1,0
  4765.2    0.05       0  5011.6    0.05       0  5015.6    0.05       0
Bank Sta=5011.6,5015.6
Exp/Cntr=0.3,0.1

Type RM Length L Ch R = 1,6583,139,139,139
BEGIN DESCRIPTION:
Purtis Creek Trib B6583.33
END DESCRIPTION:
XS GIS Cut Line= 3
      2753031.66      6837227.81      2752774.92      6837226.80
      2752506.72      6837242.39
#Sta/Elev= 30
  4744.3  456.58  4760.0  455.79  4800.0  454.53  4830.0  453.86  4880.0  453.12
  4900.0  451.90  4920.0  451.84  4940.0  451.00  4960.0  450.79  4970.0  450.15
  4980.0  449.21  4988.0  448.18  4988.2  447.68  4991.7  447.68  4992.0  448.18
  4998.0  449.03  5030.0  450.46  5040.0  449.91  5050.0  450.38  5060.1  450.25
  5070.1  449.82  5110.1  449.72  5120.2  449.52  5140.2  449.67  5170.3  450.32
  5190.3  450.96  5200.3  451.60  5210.3  452.68  5250.4  453.49  5269.7  454.62
#Mann=3,-1,0
  4744.3    0.05       0  4988.0    0.05       0  4992.0    0.05       0
Bank Sta=4988,4992
Exp/Cntr=0.3,0.1

Type RM Length L Ch R = 1,6444,151,151,151
BEGIN DESCRIPTION:
Purtis Creek Trib B6444.43
END DESCRIPTION:
XS GIS Cut Line= 3
      2752981.73      6837104.51      2752774.97      6837087.82
      2752461.04      6837082.83
#Sta/Elev= 30
  4793.6  453.70  4819.4  453.92  4839.5  453.84  4859.5  453.01  4879.6  452.41
  4919.7  451.84  4990.0  448.71  4998.0  446.21  5001.0  446.21  5008.0  445.69
  5008.3  445.19  5011.8  445.19  5012.0  445.69  5020.0  446.56  5030.0  448.51
  5040.0  448.78  5050.0  448.61  5090.0  449.02  5130.0  447.68  5140.0  447.70
  5190.0  449.33  5200.0  449.78  5210.0  450.51  5220.0  450.79  5230.0  451.28
  5240.0  452.21  5250.0  452.51  5290.0  452.82  5310.0  453.41  5315.0  453.41
#Mann=3,-1,0
  4793.6   0.035       0  5008.0   0.035       0  5012.0   0.035       0
Bank Sta=5008,5012
Exp/Cntr=0.3,0.1

Type RM Length L Ch R = 1,6293,138,138,138
BEGIN DESCRIPTION:
Purtis Creek Trib B6293.47
END DESCRIPTION:
XS GIS Cut Line= 3
      2752989.30      6836936.93      2752775.50      6836936.95
      2752440.08      6836944.38
#Sta/Elev= 30
  4786.7  452.56  4930.0  450.03  4970.0  448.14  4980.0  448.06  4990.0  447.24
  5002.7  447.01  5008.0  444.40  5008.2  443.90  5011.7  443.90  5012.0  444.40
  5020.0  445.85  5030.0  448.04  5040.0  447.46  5050.0  447.92  5060.0  448.77
  5070.0  448.78  5100.0  447.91  5110.0  447.87  5120.0  447.20  5130.0  447.04
  5140.0  447.27  5150.0  447.91  5170.0  448.30  5190.0  449.27  5230.1  450.25
  5270.1  451.62  5310.1  453.72  5320.1  453.94  5330.1  454.48  5336.0  454.44
#Mann=3,-1,0
  4786.7    0.05       0  5008.0    0.05       0  5012.0    0.05       0
Bank Sta=5008,5012
Exp/Cntr=0.3,0.1

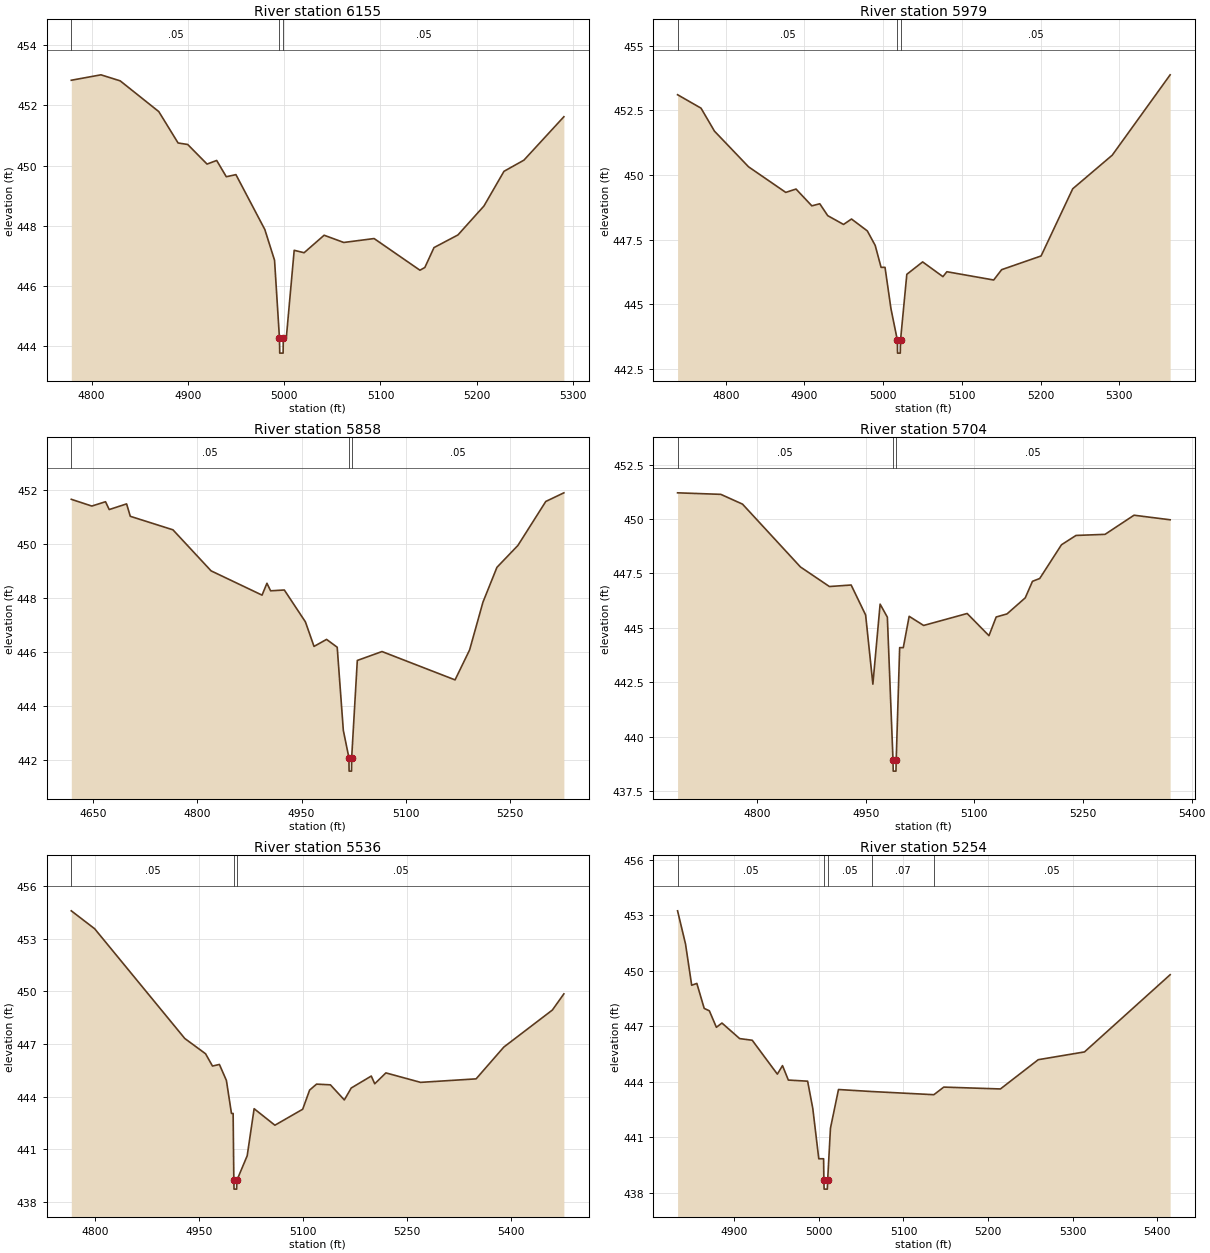
Type RM Length L Ch R = 1,6155,176,176,176
BEGIN DESCRIPTION:
Purtis Creek Trib B6154.71
END DESCRIPTION:
XS GIS Cut Line= 3
      2752996.75      6836809.82      2752776.66      6836798.00
      2752496.01      6836875.63
#Sta/Elev= 30
  4778.9  452.83  4809.7  453.01  4829.7  452.81  4869.8  451.79  4889.8  450.75
  4899.8  450.70  4919.9  450.05  4929.9  450.17  4939.9  449.63  4949.9  449.70
  4979.9  447.88  4990.0  446.86  4995.1  444.28  4995.4  443.78  4998.9  443.78
  4999.1  444.28  5002.2  444.28  5010.4  447.19  5020.7  447.11  5041.5  447.69
  5061.9  447.45  5093.4  447.58  5141.0  446.53  5146.1  446.62  5155.6  447.28
  5180.5  447.70  5207.5  448.66  5228.3  449.81  5249.0  450.18  5290.5  451.62
#Mann=3,-1,0
  4778.9    0.05       0  4995.1    0.05       0  4999.1    0.05       0
Bank Sta=4995.1,4999.1
Exp/Cntr=0.3,0.1

Type RM Length L Ch R = 1,5979,121,121,121
BEGIN DESCRIPTION:
Purtis Creek Trib B5979.11
END DESCRIPTION:
XS GIS Cut Line= 3
      2753035.60      6836651.39      2752776.24      6836622.61
      2752412.64      6836591.30
#Sta/Elev= 30
  4738.8  453.11  4768.6  452.59  4785.7  451.70  4829.0  450.32  4876.3  449.33
  4889.3  449.46  4909.4  448.81  4919.5  448.89  4929.6  448.43  4949.7  448.09
  4959.8  448.30  4979.9  447.84  4989.9  447.28  4997.4  446.43  5002.4  446.43
  5010.0  444.82  5018.1  443.61  5018.3  443.11  5021.8  443.11  5022.1  443.61
  5030.1  446.16  5050.2  446.64  5076.0  446.07  5081.0  446.26  5140.5  445.94
  5150.6  446.34  5200.7  446.87  5240.9  449.47  5291.1  450.77  5364.7  453.88
#Mann=3,-1,0
  4738.8    0.05       0  5018.1    0.05       0  5022.1    0.05       0
Bank Sta=5018.1,5022.1
Exp/Cntr=0.3,0.1

Type RM Length L Ch R = 1,5858,154,154,154
BEGIN DESCRIPTION:
Purtis Creek Trib B5858.33
END DESCRIPTION:
XS GIS Cut Line= 3
      2753132.96      6836634.69      2752774.76      6836501.34
      2752450.09      6836474.49
#Sta/Elev= 30
  4619.1  451.65  4648.6  451.40  4668.3  451.56  4673.6  451.27  4698.6  451.48
  4703.9  451.02  4765.2  450.52  4820.0  449.00  4893.3  448.10  4900.3  448.54
  4905.6  448.26  4925.3  448.29  4955.6  447.11  4968.0  446.20  4986.0  446.46
  5001.3  446.17  5010.1  443.09  5018.1  442.08  5018.4  441.58  5021.9  441.58
  5022.1  442.08  5030.2  445.68  5065.7  446.01  5170.7  444.96  5191.6  446.07
  5210.8  447.84  5230.9  449.13  5261.0  449.94  5301.1  451.57  5327.1  451.89
#Mann=3,-1,0
  4619.1    0.05       0  5018.1    0.05       0  5022.1    0.05       0
Bank Sta=5018.1,5022.1
Exp/Cntr=0.3,0.1

Type RM Length L Ch R = 1,5704,168,168,168
BEGIN DESCRIPTION:
Purtis Creek Trib B5703.86
END DESCRIPTION:
XS GIS Cut Line= 3
      2753085.71      6836342.61      2752777.02      6836347.27
      2752406.21      6836369.47
#Sta/Elev= 30
  4690.1  451.21  4749.8  451.14  4779.8  450.69  4859.8  447.80  4899.8  446.90
  4929.8  446.97  4949.8  445.59  4959.8  442.41  4969.8  446.09  4979.8  445.49
  4987.6  438.91  4987.9  438.41  4991.7  438.41  4992.0  438.91  4996.8  444.09
  5001.8  444.09  5009.9  445.53  5029.9  445.11  5090.0  445.66  5120.1  444.64
  5130.1  445.50  5145.0  445.64  5170.2  446.38  5180.2  447.14  5190.2  447.27
  5220.2  448.82  5240.3  449.25  5280.4  449.30  5320.4  450.18  5370.3  449.97
#Mann=3,-1,0
  4690.1    0.05       0  4987.6    0.05       0  4992.0    0.05       0
Bank Sta=4987.6,4992
Exp/Cntr=0.3,0.1

Type RM Length L Ch R = 1,5536,282,282,282
BEGIN DESCRIPTION:
Purtis Creek Trib B5536.39
END DESCRIPTION:
XS GIS Cut Line= 3
      2753059.61      6836206.90      2752826.23      6836196.06
      2752349.45      6836172.44
#Sta/Elev= 30
  4765.7  454.58  4799.4  453.56  4929.5  447.31  4959.5  446.44  4969.5  445.74
  4979.5  445.83  4989.6  444.92  4996.9  443.04  4999.3  443.04  5000.3  439.23
  5000.6  438.73  5004.4  438.73  5004.7  439.23  5019.6  440.63  5029.6  443.31
  5059.6  442.37  5099.7  443.28  5109.7  444.37  5119.7  444.71  5139.7  444.67
  5159.8  443.81  5169.8  444.49  5198.7  445.17  5203.7  444.73  5219.8  445.35
  5269.9  444.81  5350.0  445.01  5390.0  446.82  5460.1  448.93  5476.7  449.85
#Mann=3,-1,0
  4765.7    0.05       0  5000.3    0.05       0  5004.7    0.05       0
Bank Sta=5000.3,5004.7
Exp/Cntr=0.3,0.1

Type RM Length L Ch R = 1,5254,253,253,253
BEGIN DESCRIPTION:
Purtis Creek Trib B5254.07
END DESCRIPTION:
XS GIS Cut Line= 3
      2752863.71      6835855.81      2752721.76      6835954.11
      2752355.46      6836137.93
#Sta/Elev= 30
  4832.9  453.23  4842.3  451.44  4849.6  449.21  4855.7  449.31  4864.4  447.96
  4870.5  447.83  4878.8  446.94  4885.4  447.17  4906.3  446.33  4921.2  446.24
  4950.9  444.41  4957.0  444.87  4963.9  444.09  4986.7  444.03  4992.8  442.56
  4999.9  439.84  5005.6  439.84  5005.9  438.70  5006.2  438.20  5010.0  438.20
  5010.4  438.70  5013.7  441.49  5023.2  443.58  5062.9  443.47  5136.0  443.30
  5147.7  443.71  5214.7  443.61  5259.4  445.19  5314.1  445.61  5415.4  449.78
#Mann=5,-1,0
  4832.9    0.05       0  5005.9    0.05       0  5010.4    0.05       0
  5062.9    0.07       0  5136.0    0.05       0
Bank Sta=5005.9,5010.4
Exp/Cntr=0.3,0.1

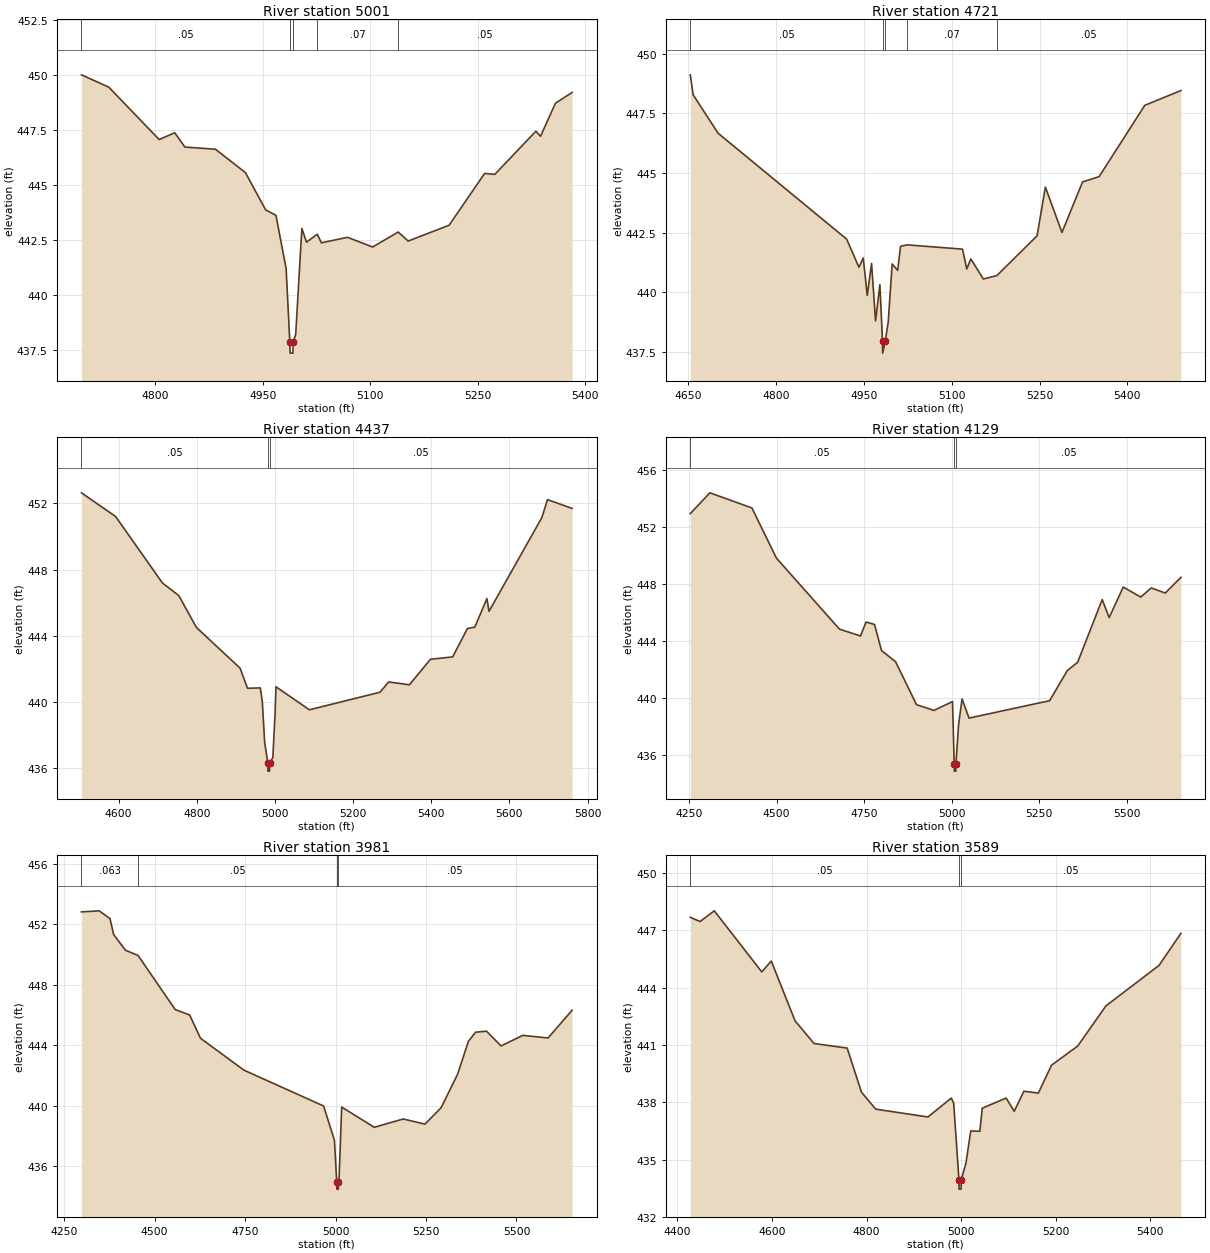
Type RM Length L Ch R = 1,5001,280,280,280
BEGIN DESCRIPTION:
Purtis Creek Trib B5001.17
END DESCRIPTION:
XS GIS Cut Line= 3
      2752778.82      6835570.14      2752578.68      6835794.78
      2752332.77      6836089.75
#Sta/Elev= 30
  4696.8  450.02  4735.0  449.46  4805.3  447.08  4827.0  447.39  4841.2  446.74
  4883.9  446.64  4925.7  445.58  4954.1  443.88  4968.3  443.64  4982.5  441.23
  4987.7  437.88  4988.1  437.38  4992.0  437.38  4992.3  437.88  4995.9  438.23
  5004.5  443.04  5011.0  442.42  5026.0  442.78  5031.8  442.39  5068.2  442.64
  5103.4  442.20  5139.0  442.88  5152.9  442.47  5210.1  443.19  5259.6  445.54
  5273.9  445.50  5331.2  447.46  5337.7  447.23  5358.5  448.73  5381.7  449.22
#Mann=5,-1,0
  4696.8    0.05       0  4987.7    0.05       0  4992.3    0.05       0
  5026.0    0.07       0  5139.0    0.05       0
Bank Sta=4987.7,4992.3
Exp/Cntr=0.3,0.1

Type RM Length L Ch R = 1,4721,284,284,284
BEGIN DESCRIPTION:
Purtis Creek Trib B4721.45
END DESCRIPTION:
XS GIS Cut Line= 3
      2752661.09      6835348.69      2752425.21      6835609.23
      2752074.16      6835946.55
#Sta/Elev= 30
  4653.1  449.12  4658.1  448.28  4700.7  446.67  4920.3  442.23  4941.3  441.05
  4948.7  441.44  4955.5  439.87  4962.9  441.21  4969.7  438.80  4977.1  440.32
  4981.6  437.95  4981.9  437.45  4986.2  437.95  4991.3  438.74  4998.1  441.19
  5007.5  440.92  5012.4  441.93  5023.9  441.99  5118.3  441.81  5125.6  440.98
  5132.5  441.40  5153.9  440.56  5176.9  440.70  5245.7  442.37  5259.9  444.41
  5288.2  442.51  5323.4  444.63  5351.7  444.85  5429.7  447.84  5491.4  448.46
#Mann=5,-1,0
  4653.1    0.05       0  4981.6    0.05       0  4986.2    0.05       0
  5023.9    0.07       0  5176.9    0.05       0
Bank Sta=4981.6,4986.2
Exp/Cntr=0.3,0.1

Type RM Length L Ch R = 1,4437,308,308,308
BEGIN DESCRIPTION:
Purtis Creek Trib B4437.29
END DESCRIPTION:
XS GIS Cut Line= 3
      2752764.15      6835230.09      2752286.70      6835377.01
      2751573.18      6835627.32
#Sta/Elev= 30
  4504.7  452.63  4592.2  451.20  4712.0  447.19  4753.9  446.43  4798.9  444.51
  4910.8  442.05  4929.7  440.84  4962.4  440.86  4967.6  440.05  4973.6  437.58
  4981.7  436.34  4982.0  435.84  4986.0  435.84  4986.3  436.34  4994.5  436.65
  5000.3  439.32  5002.5  440.93  5088.1  439.54  5268.8  440.60  5291.1  441.22
  5344.1  441.05  5398.1  442.59  5454.8  442.73  5492.5  444.44  5511.5  444.53
  5542.5  446.25  5547.8  445.48  5683.2  451.14  5697.6  452.22  5760.4  451.69
#Mann=3,-1,0
  4504.7    0.05       0  4981.7    0.05       0  4986.3    0.05       0
Bank Sta=4981.7,4986.3
Exp/Cntr=0.3,0.1

Type RM Length L Ch R = 1,4129,148,148,148
BEGIN DESCRIPTION:
Purtis Creek Trib B4128.95
END DESCRIPTION:
XS GIS Cut Line= 3
      2752871.99      6835151.66      2752125.42      6835128.41
      2751471.38      6835104.81
#Sta/Elev= 30
  4253.3  452.94  4309.3  454.40  4429.4  453.34  4499.4  449.82  4679.5  444.84
  4739.5  444.36  4755.4  445.34  4779.5  445.17  4799.6  443.34  4839.6  442.56
  4899.6  439.54  4949.6  439.14  5002.4  439.76  5007.2  435.38  5007.6  434.88
  5011.8  434.88  5012.1  435.38  5019.7  438.15  5029.7  439.94  5049.7  438.60
  5279.8  439.82  5329.9  441.92  5359.9  442.52  5429.9  446.91  5449.9  445.65
  5490.0  447.79  5540.0  447.09  5570.0  447.73  5610.0  447.37  5654.7  448.47
#Mann=3,-1,0
  4253.3    0.05       0  5007.2    0.05       0  5012.1    0.05       0
Bank Sta=5007.2,5012.1
Exp/Cntr=0.3,0.1

Type RM Length L Ch R = 1,3981,392,392,392
BEGIN DESCRIPTION:
Purtis Creek Trib B3980.94
END DESCRIPTION:
XS GIS Cut Line= 3
      2752804.97      6835009.76      2752093.57      6834987.36
      2751449.75      6834961.44
#Sta/Elev= 30
  4297.6  452.82  4346.6  452.89  4376.6  452.37  4386.6  451.32  4419.4  450.28
  4454.0  449.94  4556.7  446.36  4596.7  446.00  4626.7  444.46  4746.8  442.35
  4966.9  439.98  4996.9  437.71  5003.2  434.98  5003.5  434.48  5007.7  434.48
  5008.1  434.98  5009.4  434.98  5016.9  439.91  5107.0  438.57  5187.1  439.12
  5247.1  438.78  5291.9  439.87  5337.2  442.07  5367.2  444.26  5387.2  444.86
  5417.3  444.93  5457.3  443.95  5517.3  444.65  5587.4  444.48  5653.7  446.31
#Mann=4,-1,0
  4297.6   0.063       0  4454.0    0.05       0  5003.2    0.05       0
  5008.1    0.05       0
Bank Sta=5003.2,5008.1
Exp/Cntr=0.3,0.1

Type RM Length L Ch R = 1,3589,279,279,279
BEGIN DESCRIPTION:
Purtis Creek Trib B3589.13
END DESCRIPTION:
XS GIS Cut Line= 3
      2752446.66      6834678.90      2751875.32      6834727.44
      2751420.71      6834820.32
#Sta/Elev= 30
  4427.1  447.69  4447.8  447.47  4477.9  448.03  4578.3  444.83  4598.4  445.40
  4648.6  442.27  4688.7  441.08  4758.9  440.84  4789.1  438.53  4819.2  437.64
  4929.6  437.23  4979.1  438.22  4984.1  437.95  4995.2  433.95  4995.5  433.45
  4999.7  433.45  5000.1  433.95  5010.0  434.81  5020.2  436.50  5039.4  436.48
  5044.5  437.69  5095.0  438.22  5112.1  437.53  5132.5  438.58  5163.1  438.48
  5190.9  439.94  5246.5  440.95  5306.0  443.05  5418.3  445.17  5464.5  446.85
#Mann=3,-1,0
  4427.1    0.05       0  4995.2    0.05       0  5000.1    0.05       0
Bank Sta=4995.2,5000.1
Exp/Cntr=0.3,0.1