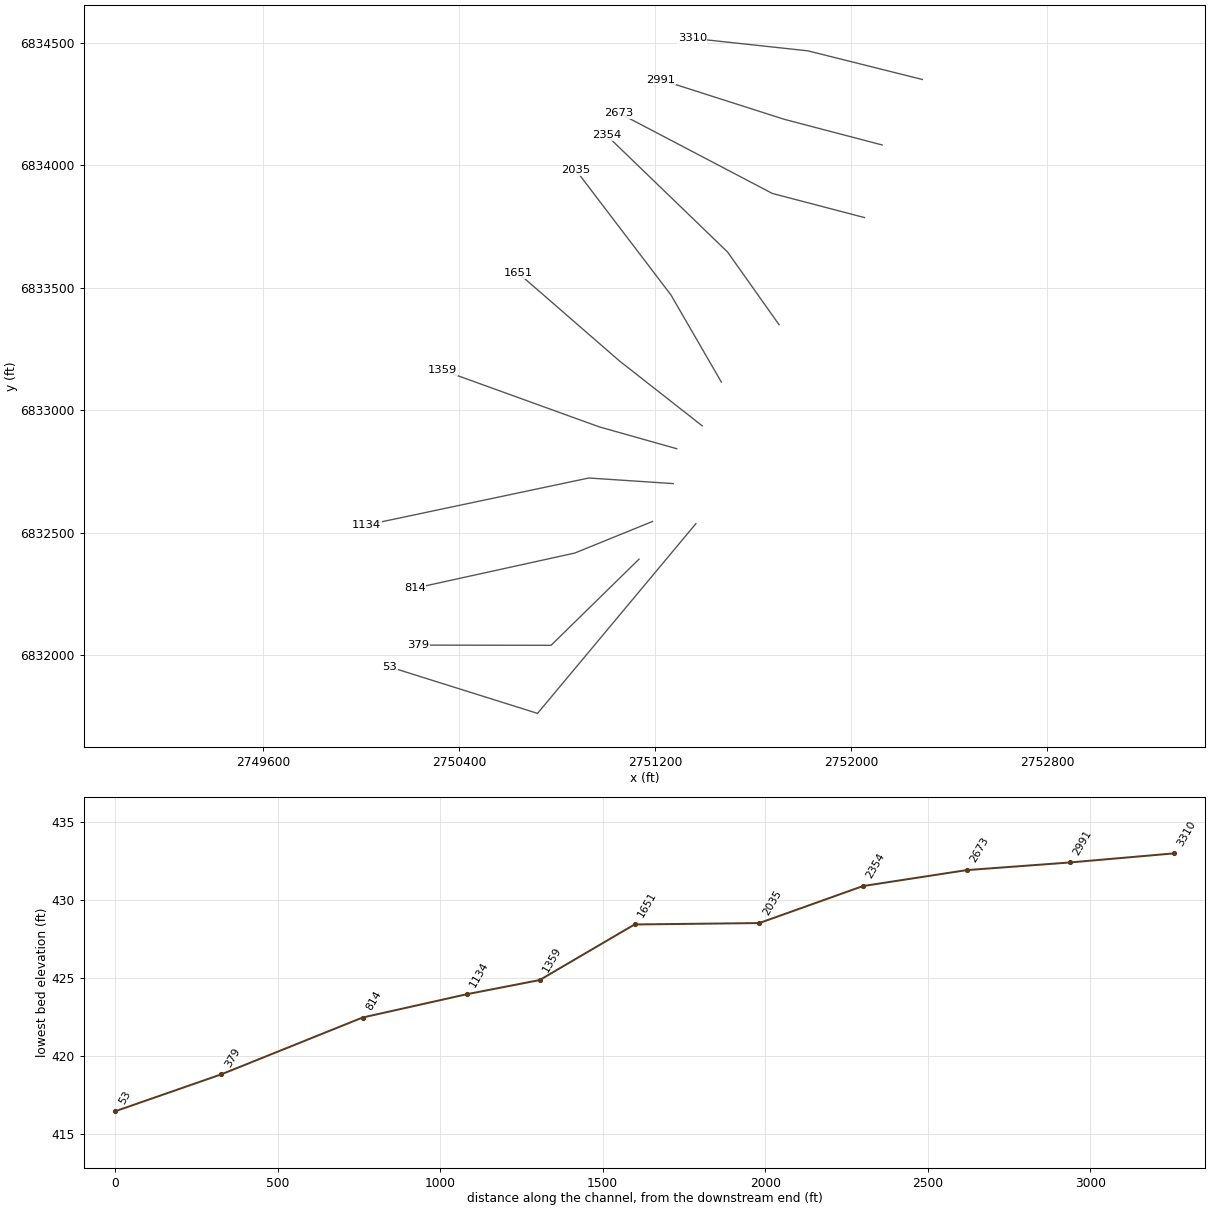
HEC-RAS study Purtis Creek Trib B.prj: Purtis Creek Trib B Base Level Engineering

--- Purtis Creek Trib B.g01 (geometry) --- (continued)

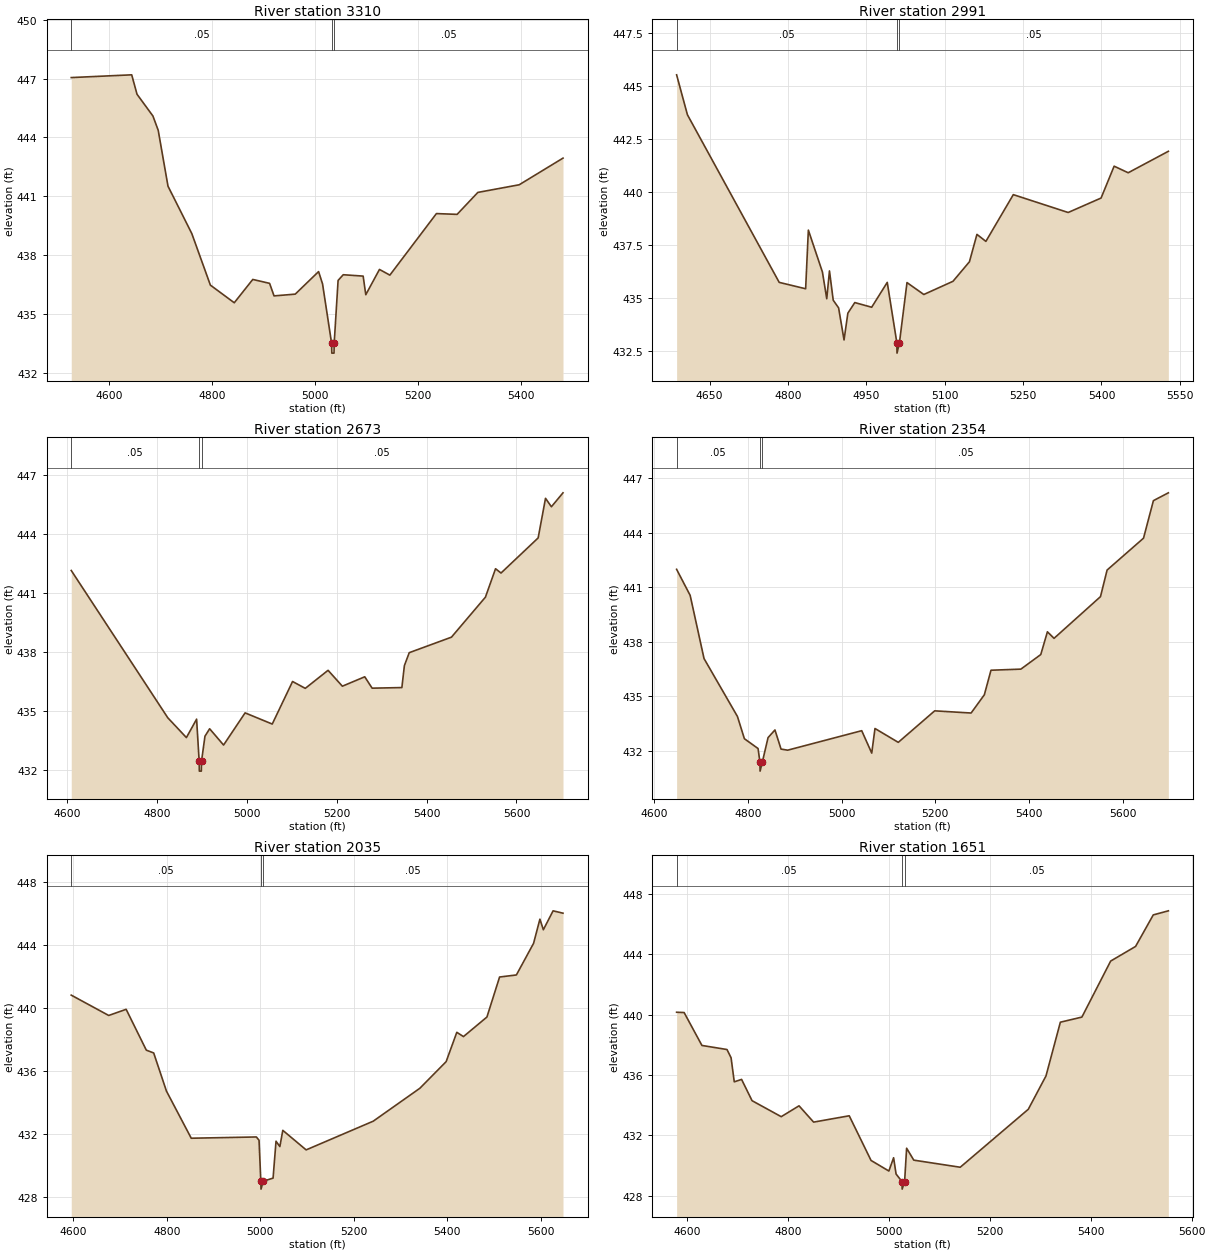
Type RM Length L Ch R = 1,3310,319,319,319
BEGIN DESCRIPTION:
Purtis Creek Trib B3309.5
END DESCRIPTION:
XS GIS Cut Line= 3
      2752289.97      6834349.54      2751822.85      6834466.40
      2751351.41      6834517.36
#Sta/Elev= 30
  4525.9  447.05  4643.4  447.19  4653.7  446.20  4684.6  445.09  4694.9  444.36
  4713.9  441.51  4760.2  439.09  4796.3  436.46  4842.7  435.56  4878.7  436.75
  4911.4  436.55  4920.0  435.91  4961.2  436.00  5006.6  437.15  5014.3  436.52
  5031.9  433.49  5032.3  432.99  5036.6  432.99  5036.9  433.49  5044.5  436.70
  5054.5  436.99  5093.2  436.92  5098.3  435.97  5124.9  437.26  5145.1  436.97
  5235.6  440.11  5275.8  440.07  5316.1  441.19  5396.5  441.58  5481.6  442.94
#Mann=3,-1,0
  4525.9    0.05       0  5031.9    0.05       0  5036.9    0.05       0
Bank Sta=5031.9,5036.9
Exp/Cntr=0.3,0.1

Type RM Length L Ch R = 1,2991,318,318,318
BEGIN DESCRIPTION:
Purtis Creek Trib B2990.91
END DESCRIPTION:
XS GIS Cut Line= 3
      2752125.99      6834082.34      2751726.74      6834186.99
      2751223.30      6834347.99
#Sta/Elev= 30
  4586.7  445.51  4607.4  443.63  4783.1  435.74  4833.7  435.44  4838.9  438.20
  4865.8  436.23  4874.1  434.97  4879.3  436.28  4886.5  434.90  4896.8  434.54
  4907.2  433.03  4914.5  434.29  4927.8  434.79  4960.1  434.57  4989.9  435.74
  5008.2  432.91  5008.6  432.41  5013.3  432.91  5027.7  435.73  5059.9  435.17
  5115.7  435.79  5147.2  436.71  5161.6  438.00  5178.7  437.67  5231.2  439.87
  5336.2  439.03  5399.2  439.71  5424.2  441.21  5451.1  440.90  5528.0  441.91
#Mann=3,-1,0
  4586.7    0.05       0  5008.2    0.05       0  5013.3    0.05       0
Bank Sta=5008.2,5013.3
Exp/Cntr=0.3,0.1

Type RM Length L Ch R = 1,2673,319,319,319
BEGIN DESCRIPTION:
Purtis Creek Trib B2673.13
END DESCRIPTION:
XS GIS Cut Line= 3
      2752053.82      6833786.18      2751678.21      6833884.48
      2751053.11      6834212.30
#Sta/Elev= 30
  4609.5  442.15  4824.3  434.64  4865.7  433.63  4888.4  434.57  4894.1  432.42
  4894.5  431.92  4898.9  431.92  4899.3  432.42  4907.0  433.70  4917.4  434.08
  4948.4  433.25  4996.3  434.89  5056.7  434.32  5101.9  436.49  5130.2  436.14
  5180.9  437.06  5212.7  436.25  5262.5  436.73  5278.9  436.15  5345.1  436.18
  5350.7  437.30  5361.5  437.96  5455.4  438.75  5531.0  440.79  5553.5  442.24
  5565.7  442.02  5648.3  443.81  5664.7  445.83  5677.8  445.40  5703.6  446.11
#Mann=3,-1,0
  4609.5    0.05       0  4894.1    0.05       0  4899.3    0.05       0
Bank Sta=4894.1,4899.3
Exp/Cntr=0.3,0.1

Type RM Length L Ch R = 1,2354,319,319,319
BEGIN DESCRIPTION:
Purtis Creek Trib B2354.12
END DESCRIPTION:
XS GIS Cut Line= 3
      2751705.45      6833349.20      2751495.51      6833645.47
      2751002.00      6834121.95
#Sta/Elev= 30
  4648.1  441.98  4677.0  440.55  4706.6  437.08  4777.9  433.90  4792.7  432.68
  4821.9  432.14  4825.8  431.40  4826.2  430.90  4831.0  431.40  4843.2  432.74
  4857.9  433.16  4870.9  432.11  4885.0  432.05  5043.0  433.12  5064.4  431.89
  5071.3  433.24  5121.0  432.48  5198.7  434.21  5276.4  434.09  5304.6  435.09
  5318.8  436.44  5382.6  436.50  5425.0  437.30  5439.2  438.55  5453.3  438.19
  5552.4  440.48  5566.5  441.94  5644.2  443.69  5665.3  445.75  5697.2  446.18
#Mann=3,-1,0
  4648.1    0.05       0  4825.8    0.05       0  4831.0    0.05       0
Bank Sta=4825.8,4831
Exp/Cntr=0.3,0.1

Type RM Length L Ch R = 1,2035,384,384,384
BEGIN DESCRIPTION:
Purtis Creek Trib B2034.52
END DESCRIPTION:
XS GIS Cut Line= 3
      2751470.12      6833114.92      2751264.63      6833470.17
      2750876.17      6833980.30
#Sta/Elev= 30
  4595.9  440.84  4676.0  439.55  4713.3  439.94  4756.4  437.35  4772.2  437.17
  4799.5  434.75  4852.5  431.76  4991.8  431.84  4997.5  431.63  5001.3  429.03
  5001.7  428.53  5006.5  429.03  5027.5  429.23  5033.8  431.57  5042.0  431.23
  5048.3  432.26  5098.2  431.02  5241.6  432.84  5341.4  434.93  5397.6  436.62
  5420.4  438.48  5434.7  438.21  5484.8  439.45  5511.9  441.99  5547.8  442.12
  5584.6  444.13  5598.1  445.66  5605.5  444.99  5626.3  446.19  5647.5  446.04
#Mann=3,-1,0
  4595.9    0.05       0  5001.3    0.05       0  5006.5    0.05       0
Bank Sta=5001.3,5006.5
Exp/Cntr=0.3,0.1

Type RM Length L Ch R = 1,1651,292,292,292
BEGIN DESCRIPTION:
Purtis Creek Trib B1651.3
END DESCRIPTION:
XS GIS Cut Line= 3
      2751392.16      6832936.37      2751053.63      6833201.84
      2750642.41      6833559.04
#Sta/Elev= 30
  4578.9  440.16  4593.8  440.14  4629.1  437.96  4678.8  437.69  4686.9  437.14
  4693.2  435.55  4707.7  435.71  4728.5  434.30  4786.3  433.24  4821.6  433.96
  4850.5  432.88  4921.1  433.30  4964.4  430.34  4999.7  429.64  5009.1  430.52
  5014.0  429.44  5025.7  428.94  5026.1  428.44  5030.9  428.94  5034.9  431.15
  5049.1  430.36  5141.2  429.89  5276.1  433.73  5311.2  435.94  5339.7  439.50
  5382.4  439.84  5439.4  443.55  5488.8  444.52  5523.9  446.61  5553.8  446.88
#Mann=3,-1,0
  4578.9    0.05       0  5025.7    0.05       0  5030.9    0.05       0
Bank Sta=5025.7,5030.9
Exp/Cntr=0.3,0.1

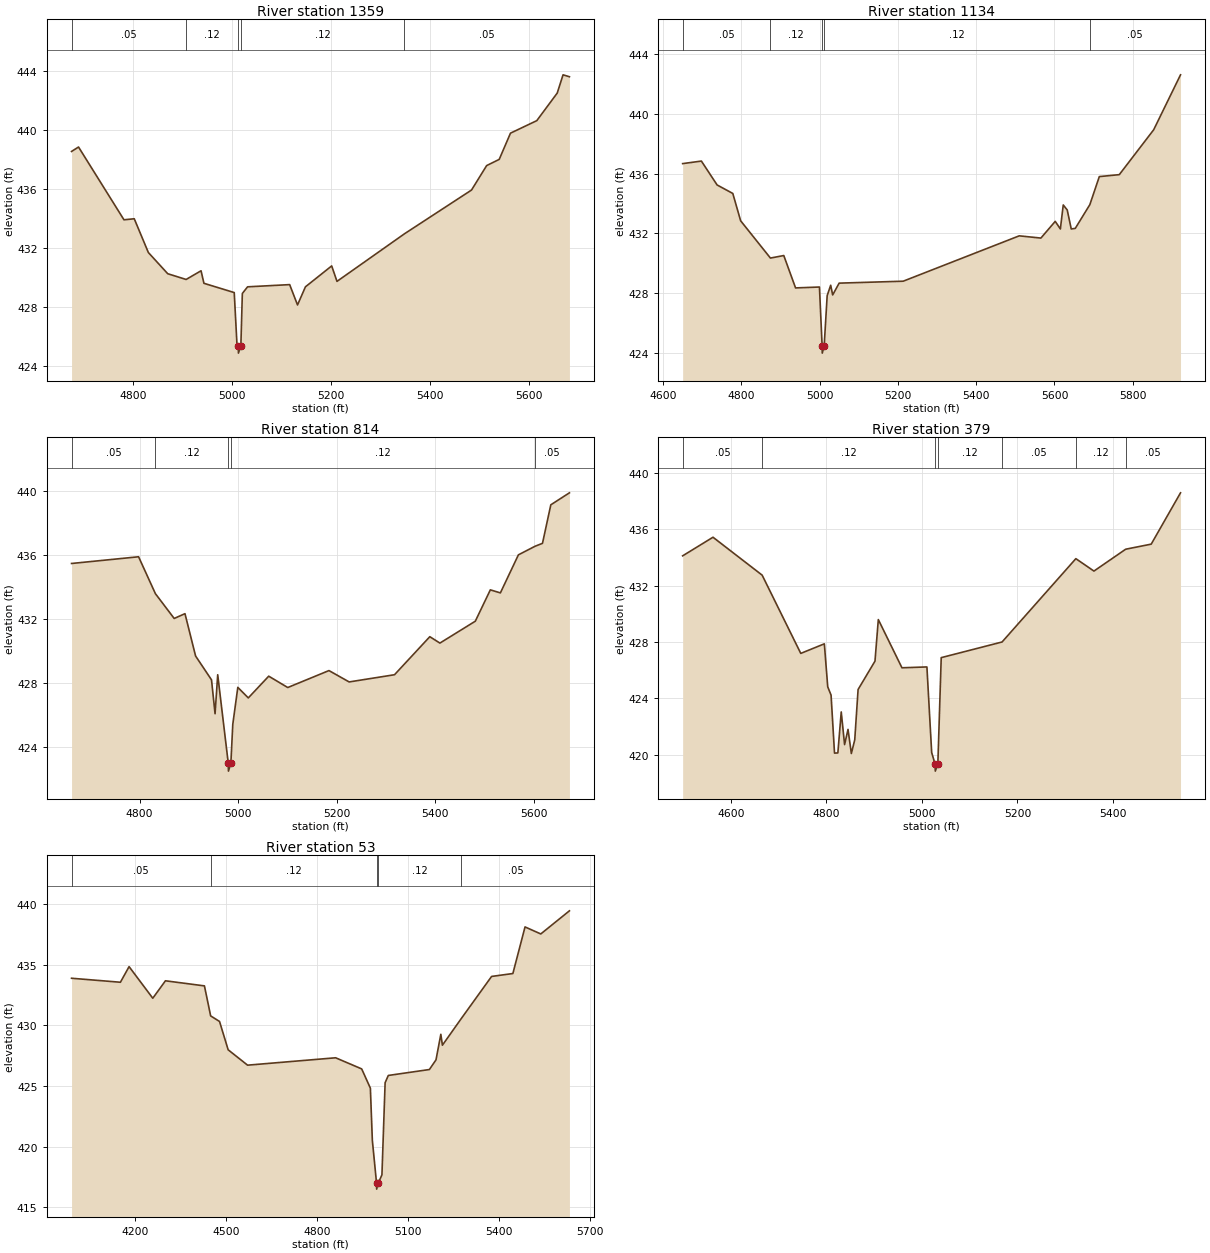
Type RM Length L Ch R = 1,1359,225,225,225
BEGIN DESCRIPTION:
Purtis Creek Trib B1358.67
END DESCRIPTION:
XS GIS Cut Line= 3
      2751288.03      6832843.12      2750971.38      6832932.47
      2750333.90      6833163.02
#Sta/Elev= 30
  4675.7  438.57  4689.8  438.87  4781.7  433.93  4802.5  434.00  4831.0  431.71
  4870.2  430.27  4907.4  429.88  4937.6  430.47  4943.4  429.62  5004.7  428.99
  5010.1  425.56  5012.8  425.38  5013.2  424.88  5018.1  425.38  5021.1  428.93
  5031.7  429.38  5116.8  429.53  5132.7  428.15  5148.7  429.38  5201.8  430.80
  5212.5  429.75  5349.0  432.98  5484.6  435.95  5515.2  437.61  5540.6  438.03
  5563.4  439.81  5616.6  440.66  5657.9  442.53  5669.7  443.77  5682.6  443.64
#Mann=5,-1,0
  4675.7    0.05       0  4907.4    0.12       0  5012.8    0.07       0
  5018.1    0.12       0  5349.0    0.05       0
Bank Sta=5012.8,5018.1
Exp/Cntr=0.3,0.1

Type RM Length L Ch R = 1,1134,320,320,320
BEGIN DESCRIPTION:
Purtis Creek Trib B1134
END DESCRIPTION:
XS GIS Cut Line= 3
      2751273.78      6832700.78      2750929.39      6832723.64
      2750022.96      6832532.06
#Sta/Elev= 30
  4650.3  436.67  4698.2  436.84  4738.3  435.24  4778.4  434.67  4798.4  432.84
  4874.5  430.34  4908.6  430.51  4938.7  428.34  4999.7  428.40  5006.5  424.47
  5006.9  423.97  5011.8  424.47  5019.4  427.82  5028.4  428.52  5033.5  427.87
  5050.0  428.66  5213.6  428.79  5510.0  431.83  5565.3  431.68  5601.9  432.80
  5615.0  432.29  5622.4  433.90  5632.6  433.56  5642.8  432.29  5653.1  432.33
  5690.3  433.92  5714.5  435.80  5765.5  435.93  5853.4  438.94  5921.9  442.62
#Mann=5,-1,0
  4650.3    0.05       0  4874.5    0.12       0  5006.5    0.07       0
  5011.8    0.12       0  5690.3    0.05       0
Bank Sta=5006.5,5011.8
Exp/Cntr=0.3,0.1

Type RM Length L Ch R = 1,814,435,435,435
BEGIN DESCRIPTION:
Purtis Creek Trib B814.27
END DESCRIPTION:
XS GIS Cut Line= 3
      2751189.34      6832546.33      2750872.13      6832417.46
      2750219.11      6832273.91
#Sta/Elev= 30
  4661.8  435.47  4797.9  435.89  4832.1  433.58  4870.2  432.03  4892.1  432.33
  4913.7  429.68  4946.0  428.19  4953.2  426.07  4958.6  428.51  4980.0  422.98
  4980.4  422.48  4985.3  422.98  4989.2  425.41  4999.4  427.72  5020.7  427.06
  5062.2  428.42  5100.8  427.71  5184.5  428.77  5225.5  428.06  5317.6  428.51
  5389.3  430.89  5409.8  430.49  5481.7  431.86  5512.2  433.82  5532.6  433.63
  5569.2  436.01  5603.2  436.55  5618.1  436.73  5635.0  439.14  5672.8  439.89
#Mann=5,-1,0
  4661.8    0.05       0  4832.1    0.12       0  4980.0    0.07       0
  4985.3    0.12       0  5603.2    0.05       0
Bank Sta=4980,4985.3
Exp/Cntr=0.3,0.1

Type RM Length L Ch R = 1,379,326,326,326
BEGIN DESCRIPTION:
Purtis Creek Trib B379.14
END DESCRIPTION:
XS GIS Cut Line= 3
      2751134.27      6832392.59      2750775.41      6832041.05
      2750234.56      6832041.86
#Sta/Elev= 30
  4498.6  434.11  4562.2  435.43  4665.2  432.74  4746.1  427.19  4795.5  427.87
  4802.6  424.82  4809.6  424.23  4816.8  420.12  4823.8  420.13  4830.9  423.04
  4837.9  420.72  4845.1  421.80  4852.1  420.09  4859.2  421.06  4866.2  424.63
  4901.6  426.64  4908.6  429.59  4958.1  426.17  5010.4  426.23  5020.4  420.16
  5027.5  419.34  5028.0  418.84  5033.3  419.34  5040.4  426.89  5167.9  428.00
  5322.5  433.91  5360.4  433.03  5426.9  434.58  5480.4  434.94  5541.8  438.58
#Mann=7,-1,0
  4498.6    0.05       0  4665.2    0.12       0  5027.5    0.07       0
  5033.3    0.12       0  5167.9    0.05       0  5322.5    0.12       0
  5426.9    0.05       0
Bank Sta=5027.5,5033.3
Exp/Cntr=0.3,0.1

Type RM Length L Ch R = 1,53,0,0,0
BEGIN DESCRIPTION:
Purtis Creek Trib B53.361
END DESCRIPTION:
XS GIS Cut Line= 3
      2751366.12      6832537.22      2750720.21      6831763.36
      2750116.46      6831952.89
#Sta/Elev= 30
  3992.0  433.90  4153.0  433.57  4181.6  434.86  4259.7  432.25  4301.4  433.69
  4429.9  433.27  4450.4  430.79  4479.7  430.33  4508.1  427.99  4572.1  426.72
  4862.3  427.33  4948.2  426.41  4976.8  424.82  4983.3  420.51  4997.1  416.98
  4997.5  416.48  5002.9  416.98  5014.9  417.66  5025.4  425.27  5035.9  425.87
  5171.3  426.36  5193.1  427.16  5209.0  429.27  5214.2  428.37  5276.1  430.56
  5376.3  434.05  5446.4  434.29  5486.5  438.14  5538.4  437.56  5632.8  439.47
#Mann=5,-1,0
  3992.0    0.05       0  4450.4    0.12       0  4997.1    0.07       0
  5002.9    0.12       0  5276.1    0.05       0
Bank Sta=4997.1,5002.9
Exp/Cntr=0.3,0.1

Chan Stop Cuts=-1