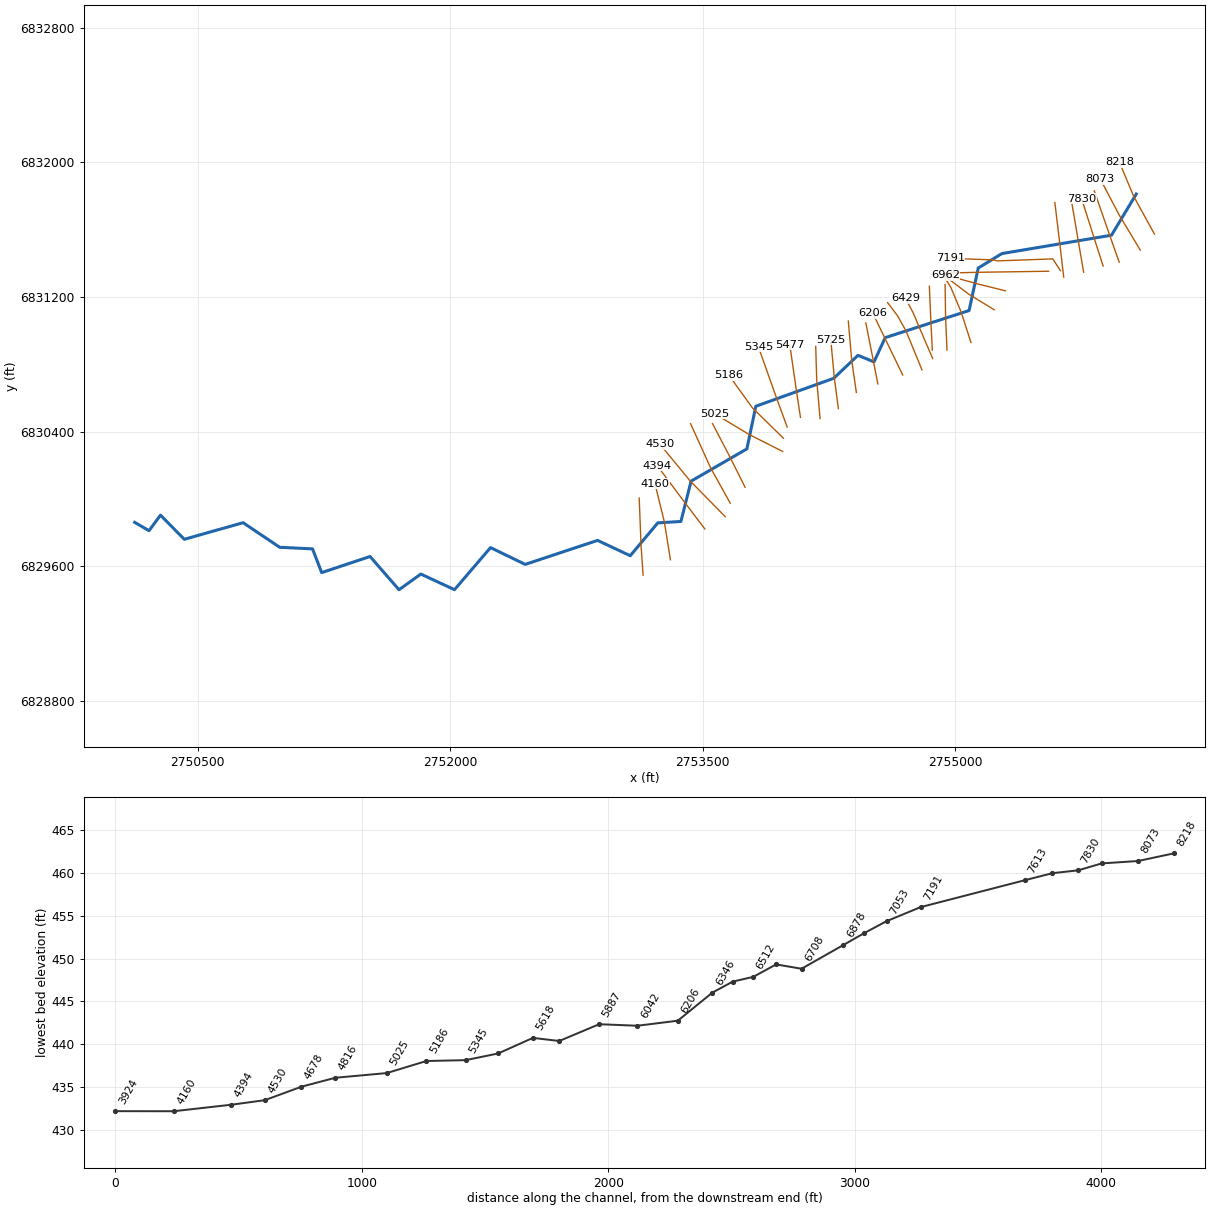
--- Purtis Creek Trib C.prj (project) ---

Proj Title=Purtis Creek Trib C Base Level Engineering
Current Plan=p01
Default Exp/Contr=0.3,0.1
English Units
Geom File=g01
Flow File=f01
Plan File=p01
BEGIN DESCRIPTION:
Purtis Creek Trib C
END DESCRIPTION:

--- Purtis Creek Trib C.p01 (plan) ---

Plan Title=Multiple Run
Short Identifier=Multiple
Geom File=g01
Flow File=f01
Subcritical Flow
K Sum by GR= 0
Std Step Tol= 0.01
Critical Tol= 0.01
Num of Std Step Trials= 20
Max Error Tol= 0.3
Flow Tol Ratio= 0.001
Split Flow NTrial= 30
Split Flow Tol= 0.02
Split Flow Ratio= 0.02
Log Output Level= 0
Friction Slope Method= 1
Unsteady Friction Slope Method= 2
Unsteady Bridges Friction Slope Method= 1
Parabolic Critical Depth
Global Vel Dist=  1 , 1 , 1
Global Log Level= 0
CheckData=True
Encroach Param= -1, 0, 0, 0
BEGIN DESCRIPTION:
Multiple Run
END DESCRIPTION:

--- Purtis Creek Trib C.f01 (steady flow) ---

Flow Title=Multiple
Number of Profiles=7
Profile Names=10-year,25-year,50-year,1pct_min,100-year,1pct_plu,500-year
River Rch & RM= Purtis Creek Tri,Reach-1,8218
     528     712     863     521    1040    2074    1510
River Rch & RM= Purtis Creek Tri,Reach-1,2534
     650     886    1081     656    1309    2611    1923
Boundary for River Rch & Prof#=Purtis Creek Tri,Reach-1,1
Up Type=0
Dn Type=3
Dn Slope=0.005
Boundary for River Rch & Prof#=Purtis Creek Tri,Reach-1,2
Up Type=0
Dn Type=3
Dn Slope=0.005
Boundary for River Rch & Prof#=Purtis Creek Tri,Reach-1,3
Up Type=0
Dn Type=3
Dn Slope=0.005
Boundary for River Rch & Prof#=Purtis Creek Tri,Reach-1,4
Up Type=0
Dn Type=3
Dn Slope=0.005
Boundary for River Rch & Prof#=Purtis Creek Tri,Reach-1,5
Up Type=0
Dn Type=3
Dn Slope=0.005
Boundary for River Rch & Prof#=Purtis Creek Tri,Reach-1,6
Up Type=0
Dn Type=3
Dn Slope=0.005
Boundary for River Rch & Prof#=Purtis Creek Tri,Reach-1,7
Up Type=0
Dn Type=3
Dn Slope=0.005

--- Purtis Creek Trib C.g01 (geometry) ---

Geom Title=Existing Conditions

River Reach=Purtis Creek Tri,Reach-1
Reach XY= 30
      2756076.00      6831811.00      2755928.71      6831566.40
      2755277.55      6831457.25      2755137.11      6831371.32
      2755082.80      6831118.86      2754584.32      6830957.84
      2754517.82      6830813.83      2754422.68      6830852.94
      2754278.66      6830716.46      2753815.94      6830550.39
      2753762.80      6830297.27      2753431.28      6830105.46
      2753370.98      6829866.02      2753233.72      6829857.83
      2753069.96      6829662.62      2752875.92      6829753.70
      2752446.03      6829611.06      2752240.04      6829710.91
      2752026.00      6829461.00      2751825.91      6829553.70
      2751696.37      6829460.62      2751524.37      6829657.87
      2751237.03      6829562.27      2751182.52      6829703.32
      2750987.83      6829712.65      2750770.02      6829858.84
      2750420.93      6829760.16      2750279.41      6829903.56
      2750211.30      6829811.31      2750126.00      6829861.00

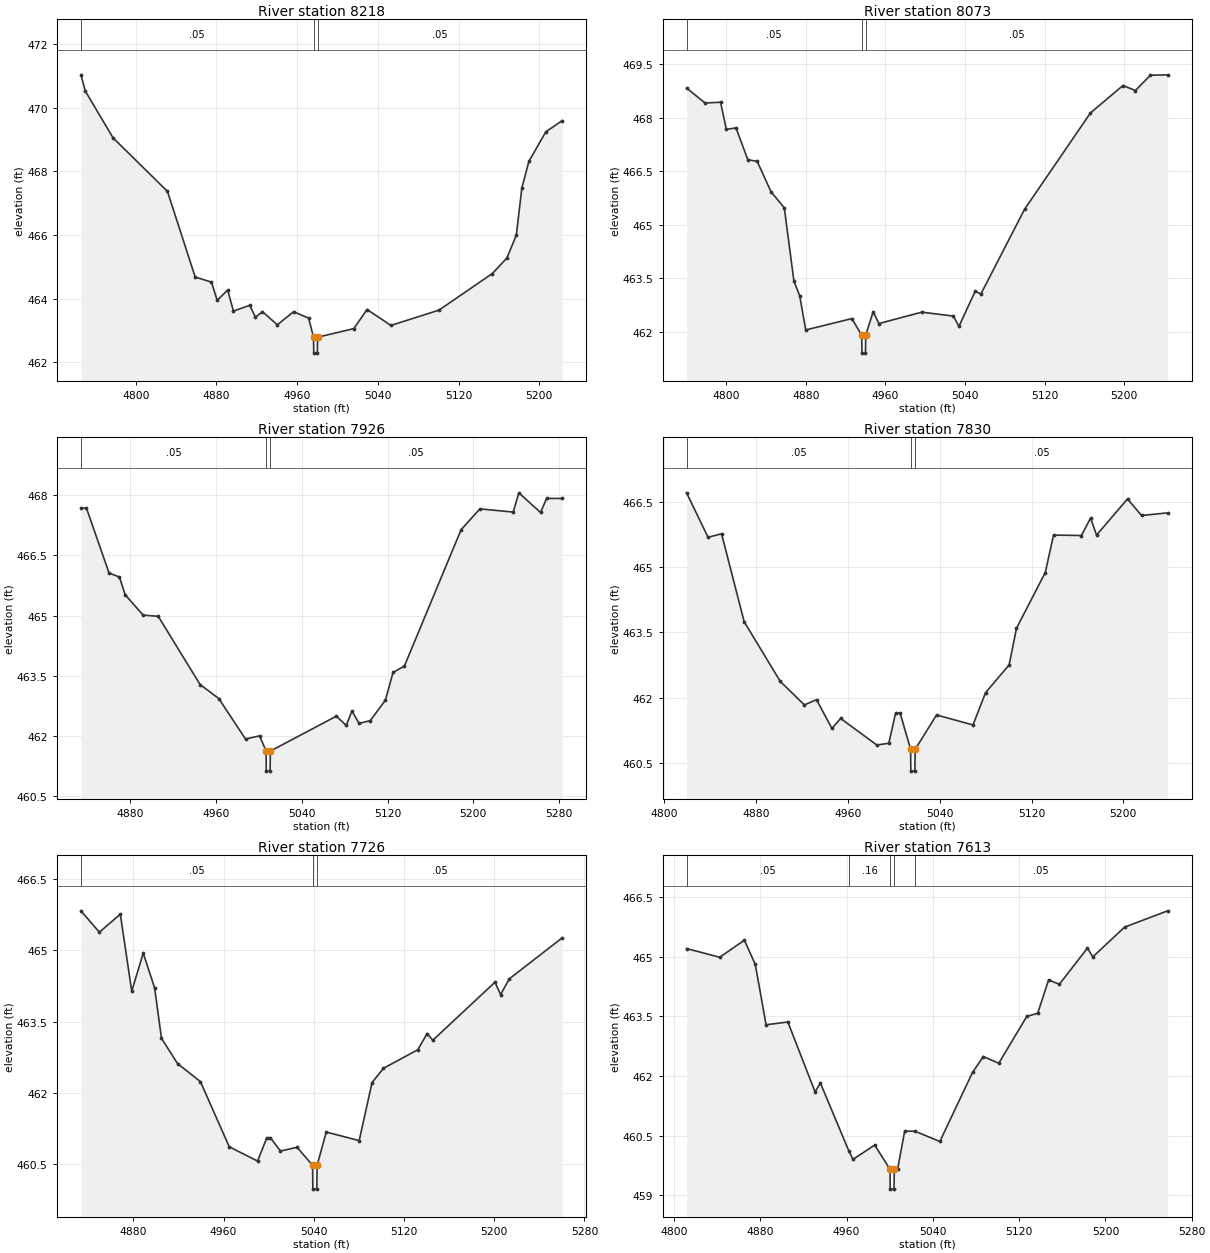
Type RM Length L Ch R = 1,8218,145,145,145
BEGIN DESCRIPTION:
Purtis Creek Trib C8217.94
END DESCRIPTION:
XS GIS Cut Line= 3
      2756183.74      6831573.41      2756061.07      6831796.17
      2755974.94      6832001.32
#Sta/Elev= 30
  4745.7  471.03  4750.0  470.52  4777.5  469.05  4831.4  467.37  4858.9  464.68
  4875.0  464.52  4880.7  463.95  4891.1  464.27  4896.8  463.61  4912.9  463.79
  4918.6  463.42  4925.6  463.59  4940.3  463.18  4956.4  463.59  4971.3  463.39
  4976.2  462.79  4976.4  462.29  4979.9  462.29  4980.2  462.79  5016.1  463.06
  5029.2  463.66  5052.9  463.16  5100.5  463.64  5153.4  464.79  5167.9  465.28
  5177.2  466.00  5182.6  467.47  5189.6  468.31  5206.4  469.24  5222.5  469.59
#Mann=3,-1,0
  4745.7    0.05       0  4976.2    0.05       0  4980.2    0.05       0
Bank Sta=4976.2,4980.2
Exp/Cntr=0.3,0.1

Type RM Length L Ch R = 1,8073,147,147,147
BEGIN DESCRIPTION:
Purtis Creek Trib C8072.71
END DESCRIPTION:
XS GIS Cut Line= 3
      2756099.44      6831478.16      2755974.23      6831686.84
      2755862.13      6831899.77
#Sta/Elev= 30
  4759.9  468.84  4778.5  468.42  4794.1  468.44  4799.9  467.68  4809.6  467.72
  4821.5  466.83  4831.0  466.78  4844.8  465.93  4858.2  465.48  4867.9  463.42
  4873.7  463.01  4879.8  462.05  4926.2  462.37  4936.1  461.90  4936.4  461.40
  4939.9  461.40  4940.1  461.90  4947.6  462.56  4953.4  462.23  4996.5  462.55
  5028.3  462.44  5033.9  462.15  5050.3  463.14  5056.0  463.06  5100.0  465.44
  5166.2  468.14  5198.9  468.91  5211.4  468.77  5226.6  469.20  5243.9  469.21
#Mann=3,-1,0
  4759.9    0.05       0  4936.1    0.05       0  4940.1    0.05       0
Bank Sta=4936.1,4940.1
Exp/Cntr=0.3,0.1

Type RM Length L Ch R = 1,7926,96,96,96
BEGIN DESCRIPTION:
Purtis Creek Trib C7926.09
END DESCRIPTION:
XS GIS Cut Line= 3
      2755974.43      6831406.31      2755918.82      6831563.40
      2755826.39      6831829.99
#Sta/Elev= 30
  4834.0  467.68  4839.1  467.68  4860.2  466.06  4869.9  465.96  4875.2  465.52
  4892.0  465.01  4906.1  464.98  4945.1  463.28  4962.6  462.93  4987.5  461.92
  5000.6  462.00  5006.7  461.62  5006.9  461.12  5010.4  461.12  5010.7  461.62
  5072.2  462.49  5081.5  462.26  5086.8  462.62  5093.4  462.31  5103.9  462.38
  5118.0  462.89  5125.1  463.58  5135.7  463.74  5188.6  467.14  5206.1  467.66
  5237.2  467.58  5242.5  468.06  5262.7  467.57  5268.4  467.92  5282.8  467.92
#Mann=3,-1,0
  4834.0    0.05       0  5006.7    0.05       0  5010.7    0.05       0
Bank Sta=5006.7,5010.7
Exp/Cntr=0.3,0.1

Type RM Length L Ch R = 1,7830,104,104,104
BEGIN DESCRIPTION:
Purtis Creek Trib C7829.75
END DESCRIPTION:
XS GIS Cut Line= 3
      2755879.11      6831383.20      2755823.08      6831557.18
      2755751.49      6831782.71
#Sta/Elev= 30
  4819.3  466.70  4838.0  465.68  4849.8  465.76  4869.5  463.74  4901.0  462.37
  4922.0  461.83  4932.6  461.95  4946.0  461.29  4953.6  461.52  4985.1  460.91
  4995.6  460.95  5001.5  461.64  5005.5  461.64  5014.6  460.81  5014.8  460.31
  5018.3  460.31  5018.6  460.81  5037.2  461.60  5069.0  461.37  5079.9  462.11
  5100.5  462.75  5106.9  463.59  5132.0  464.87  5139.2  465.73  5163.5  465.72
  5171.5  466.12  5176.7  465.73  5203.7  466.56  5215.9  466.18  5238.7  466.24
#Mann=3,-1,0
  4819.3    0.05       0  5014.6    0.05       0  5018.6    0.05       0
Bank Sta=5014.6,5018.6
Exp/Cntr=0.3,0.1

Type RM Length L Ch R = 1,7726,113,113,113
BEGIN DESCRIPTION:
Purtis Creek Trib C7726.03
END DESCRIPTION:
XS GIS Cut Line= 3
      2755763.17      6831346.61      2755734.90      6831512.18
      2755691.41      6831767.13
#Sta/Elev= 30
  4833.6  465.83  4849.9  465.38  4868.5  465.76  4878.6  464.14  4888.8  464.94
  4898.9  464.21  4905.0  463.15  4919.2  462.62  4939.5  462.24  4965.1  460.87
  4990.2  460.57  4998.4  461.06  5001.6  461.06  5010.5  460.78  5025.2  460.86
  5039.0  460.48  5039.2  459.98  5042.7  459.98  5043.0  460.48  5051.1  461.18
  5080.3  461.00  5091.7  462.22  5101.8  462.52  5132.3  462.91  5140.5  463.25
  5145.6  463.11  5200.7  464.33  5205.7  464.07  5213.4  464.40  5260.2  465.26
#Mann=3,-1,0
  4833.6    0.05       0  5039.0    0.05       0  5043.0    0.05       0
Bank Sta=5039,5043
Exp/Cntr=0.3,0.1

Type RM Length L Ch R = 1,7613,422,422,422
BEGIN DESCRIPTION:
Purtis Creek Trib C7612.78
END DESCRIPTION:
XS GIS Cut Line= 3
      2755644.83      6831317.77      2755622.58      6831508.15
      2755592.20      6831760.65
#Sta/Elev= 30
  4811.7  465.21  4842.4  464.99  4865.3  465.42  4875.4  464.81  4885.4  463.29
  4905.6  463.36  4930.8  461.60  4935.8  461.82  4962.3  460.10  4966.0  459.90
  4986.1  460.26  5000.3  459.65  5000.5  459.15  5004.0  459.15  5004.3  459.65
  5007.3  459.65  5013.9  460.61  5023.3  460.61  5046.5  460.35  5076.8  462.09
  5086.8  462.49  5101.1  462.32  5127.1  463.50  5137.2  463.58  5147.3  464.42
  5157.3  464.31  5183.3  465.22  5188.3  465.00  5217.8  465.75  5257.7  466.16
#Mann=5,-1,0
  4811.7    0.05       0  4962.3    0.16       0  5000.3    0.07       0
  5004.3    0.16       0  5023.3    0.05       0
Bank Sta=5000.3,5004.3
Exp/Cntr=0.3,0.1

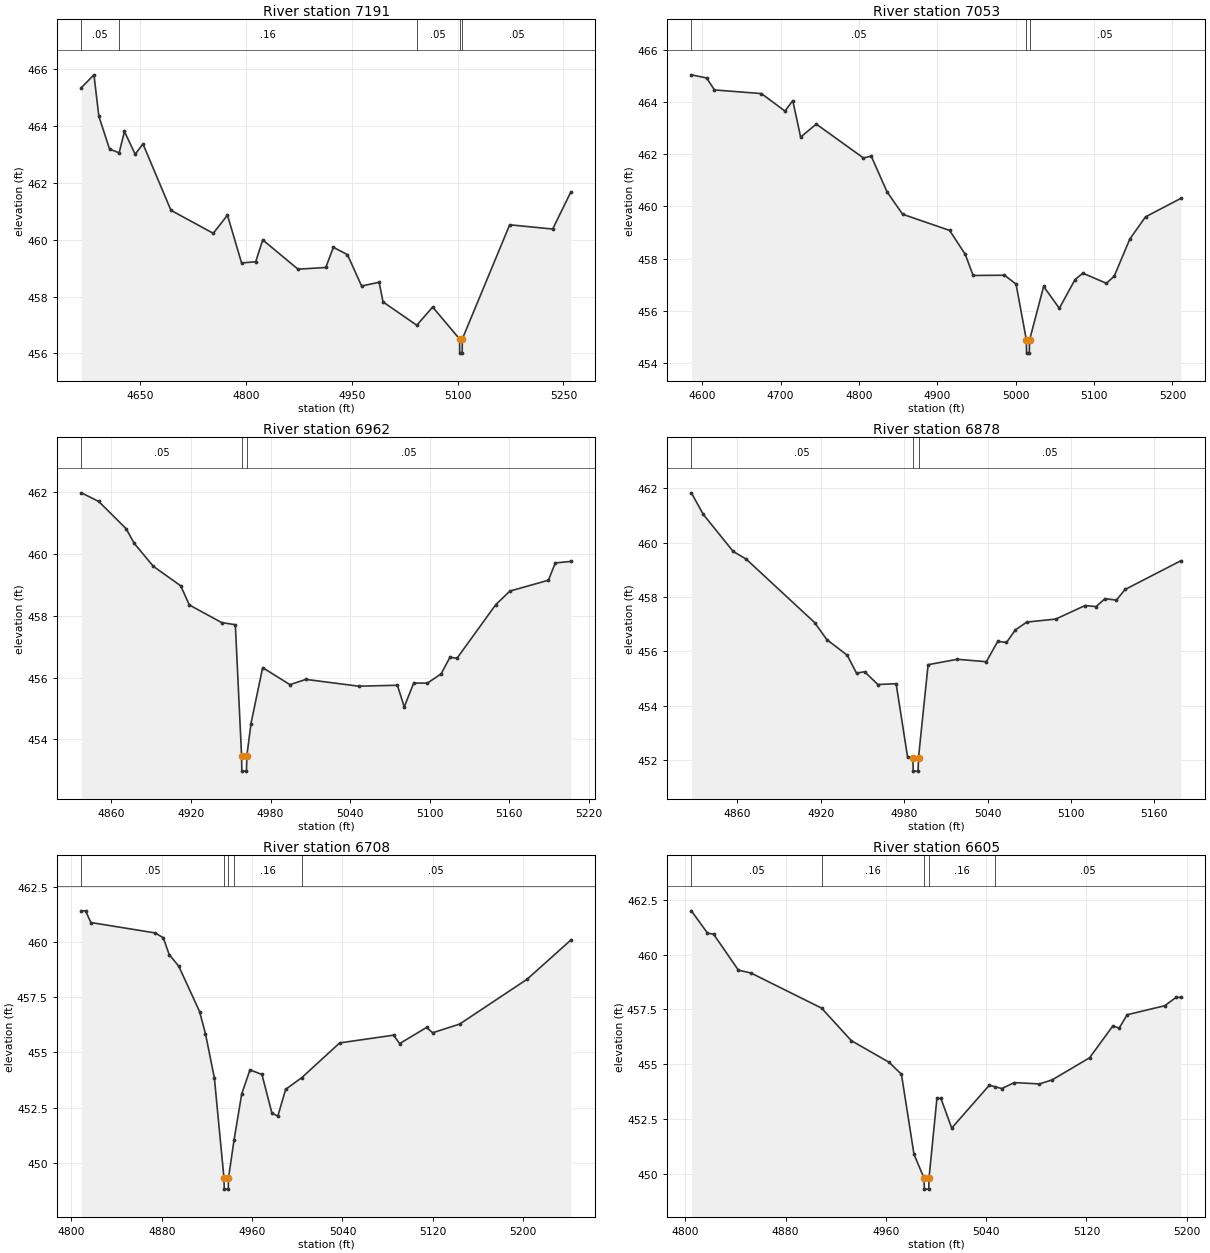
Type RM Length L Ch R = 1,7191,138,138,138
BEGIN DESCRIPTION:
Purtis Creek Trib C7190.81
END DESCRIPTION:
XS GIS Cut Line= 5
      2755624.93      6831356.07      2755580.07      6831425.67
      2755250.81      6831413.78      2755226.42      6831419.68
      2754970.16      6831429.01
#Sta/Elev= 30
  4566.9  465.34  4584.7  465.79  4591.6  464.34  4606.8  463.18  4620.4  463.05
  4627.9  463.80  4643.1  463.00  4654.2  463.36  4693.8  461.03  4753.8  460.22
  4773.9  460.86  4793.9  459.18  4813.9  459.22  4823.9  459.99  4873.9  458.96
  4913.3  459.02  4924.0  459.73  4944.0  459.47  4964.0  458.37  4988.9  458.50
  4994.4  457.81  5042.2  456.99  5064.7  457.63  5102.8  456.51  5103.0  456.01
  5106.5  456.01  5106.8  456.51  5173.9  460.52  5234.8  460.37  5260.7  461.68
#Mann=5,-1,0
  4566.9    0.05       0  4620.4    0.16       0  5042.2    0.05       0
  5102.8    0.07       0  5106.8    0.05       0
Bank Sta=5102.8,5106.8
Exp/Cntr=0.3,0.1

Type RM Length L Ch R = 1,7053,91,91,91
BEGIN DESCRIPTION:
Purtis Creek Trib C7053.2
END DESCRIPTION:
XS GIS Cut Line= 3
      2755555.43      6831352.33      2755141.13      6831346.18
      2754930.83      6831341.07
#Sta/Elev= 30
  4586.1  465.05  4605.5  464.93  4615.5  464.47  4675.5  464.33  4705.5  463.66
  4715.5  464.06  4725.5  462.66  4745.5  463.16  4805.6  461.86  4815.6  461.93
  4835.6  460.57  4855.6  459.70  4915.6  459.08  4935.6  458.16  4945.6  457.35
  4985.6  457.36  5000.4  457.02  5013.6  454.87  5013.8  454.37  5017.3  454.37
  5017.6  454.87  5035.6  456.93  5055.6  456.09  5075.6  457.19  5085.6  457.44
  5115.6  457.05  5125.6  457.32  5145.6  458.75  5165.6  459.60  5210.8  460.31
#Mann=3,-1,0
  4586.1    0.05       0  5013.6    0.05       0  5017.6    0.05       0
Bank Sta=5013.6,5017.6
Exp/Cntr=0.3,0.1

Type RM Length L Ch R = 1,6962,84,84,84
BEGIN DESCRIPTION:
Purtis Creek Trib C6962.16
END DESCRIPTION:
XS GIS Cut Line= 3
      2755298.73      6831236.14      2755139.52      6831275.55
      2754941.59      6831329.65
#Sta/Elev= 30
  4837.3  461.98  4850.4  461.70  4871.0  460.82  4877.2  460.34  4891.6  459.60
  4912.2  458.97  4918.7  458.35  4943.1  457.78  4953.4  457.71  4958.1  453.47
  4958.3  452.97  4961.8  452.97  4962.1  453.47  4965.2  454.51  4974.0  456.32
  4994.6  455.77  5006.6  455.94  5046.4  455.72  5075.6  455.75  5080.8  455.05
  5087.9  455.82  5098.3  455.82  5108.6  456.12  5115.3  456.66  5120.5  456.62
  5149.8  458.36  5160.5  458.80  5189.5  459.15  5194.7  459.71  5206.5  459.76
#Mann=3,-1,0
  4837.3    0.05       0  4958.1    0.05       0  4962.1    0.05       0
Bank Sta=4958.1,4962.1
Exp/Cntr=0.3,0.1

Type RM Length L Ch R = 1,6878,170,170,170
BEGIN DESCRIPTION:
Mapping XS b0eedcee
END DESCRIPTION:
XS GIS Cut Line= 3
      2755231.69      6831123.67      2755081.75      6831215.29
      2754941.05      6831321.83
#Sta/Elev= 30
  4826.9  461.84  4835.4  461.05  4857.0  459.68  4866.3  459.40  4915.6  457.06
  4924.4  456.43  4939.0  455.86  4945.7  455.20  4951.5  455.25  4961.1  454.78
  4974.2  454.81  4982.4  452.12  4986.3  452.09  4986.5  451.59  4990.0  451.59
  4990.3  452.09  4997.2  455.51  5018.2  455.71  5039.1  455.62  5047.3  456.37
  5053.6  456.33  5060.0  456.79  5068.2  457.08  5089.0  457.19  5110.2  457.69
  5118.1  457.65  5124.4  457.94  5132.7  457.89  5138.9  458.28  5179.1  459.34
#Mann=3,-1,0
  4826.9    0.05       0  4986.3    0.05       0  4990.3    0.05       0
Bank Sta=4986.3,4990.3
Exp/Cntr=0.3,0.1

Type RM Length L Ch R = 1,6708,103,103,103
BEGIN DESCRIPTION:
Purtis Creek Trib C6744.73
END DESCRIPTION:
XS GIS Cut Line= 4
      2755093.85      6830928.94      2755035.25      6831110.83
      2754974.98      6831255.13      2754930.14      6831328.31
#Sta/Elev= 30
  4808.9  461.41  4812.6  461.41  4817.3  460.88  4874.1  460.41  4881.4  460.19
  4886.6  459.43  4895.1  458.90  4913.5  456.85  4918.7  455.85  4926.6  453.84
  4935.1  449.31  4935.4  448.81  4938.9  448.81  4939.1  449.31  4944.0  451.03
  4950.8  453.12  4958.1  454.21  4968.7  454.00  4977.6  452.24  4982.8  452.12
  4989.7  453.33  5003.8  453.85  5037.5  455.43  5085.2  455.78  5090.6  455.40
  5114.4  456.13  5119.8  455.89  5143.6  456.28  5203.3  458.31  5242.2  460.09
#Mann=5,-1,0
  4808.9    0.05       0  4935.1    0.07       0  4939.1    0.05       0
  4944.0    0.16       0  5003.8    0.05       0
Bank Sta=4935.1,4939.1
Exp/Cntr=0.3,0.1

Type RM Length L Ch R = 1,6605,93,93,93
BEGIN DESCRIPTION:
Purtis Creek Trib C6604.63
END DESCRIPTION:
XS GIS Cut Line= 3
      2754951.56      6830883.53      2754943.06      6831082.45
      2754940.26      6831273.92
#Sta/Elev= 30
  4804.8  461.99  4817.6  460.98  4822.6  460.92  4842.3  459.29  4852.3  459.16
  4908.7  457.56  4932.4  456.08  4962.4  455.10  4972.4  454.55  4982.4  450.91
  4990.4  449.82  4990.7  449.32  4994.2  449.32  4994.4  449.82  5000.7  453.45
  5003.9  453.45  5012.5  452.10  5042.5  454.05  5047.1  453.98  5052.5  453.90
  5062.5  454.17  5082.5  454.11  5092.5  454.29  5122.5  455.30  5141.1  456.75
  5146.1  456.65  5152.5  457.26  5182.5  457.67  5191.5  458.05  5195.4  458.05
#Mann=5,-1,0
  4804.8    0.05       0  4908.7    0.16       0  4990.4    0.07       0
  4994.4    0.16       0  5047.1    0.05       0
Bank Sta=4990.4,4994.4
Exp/Cntr=0.3,0.1

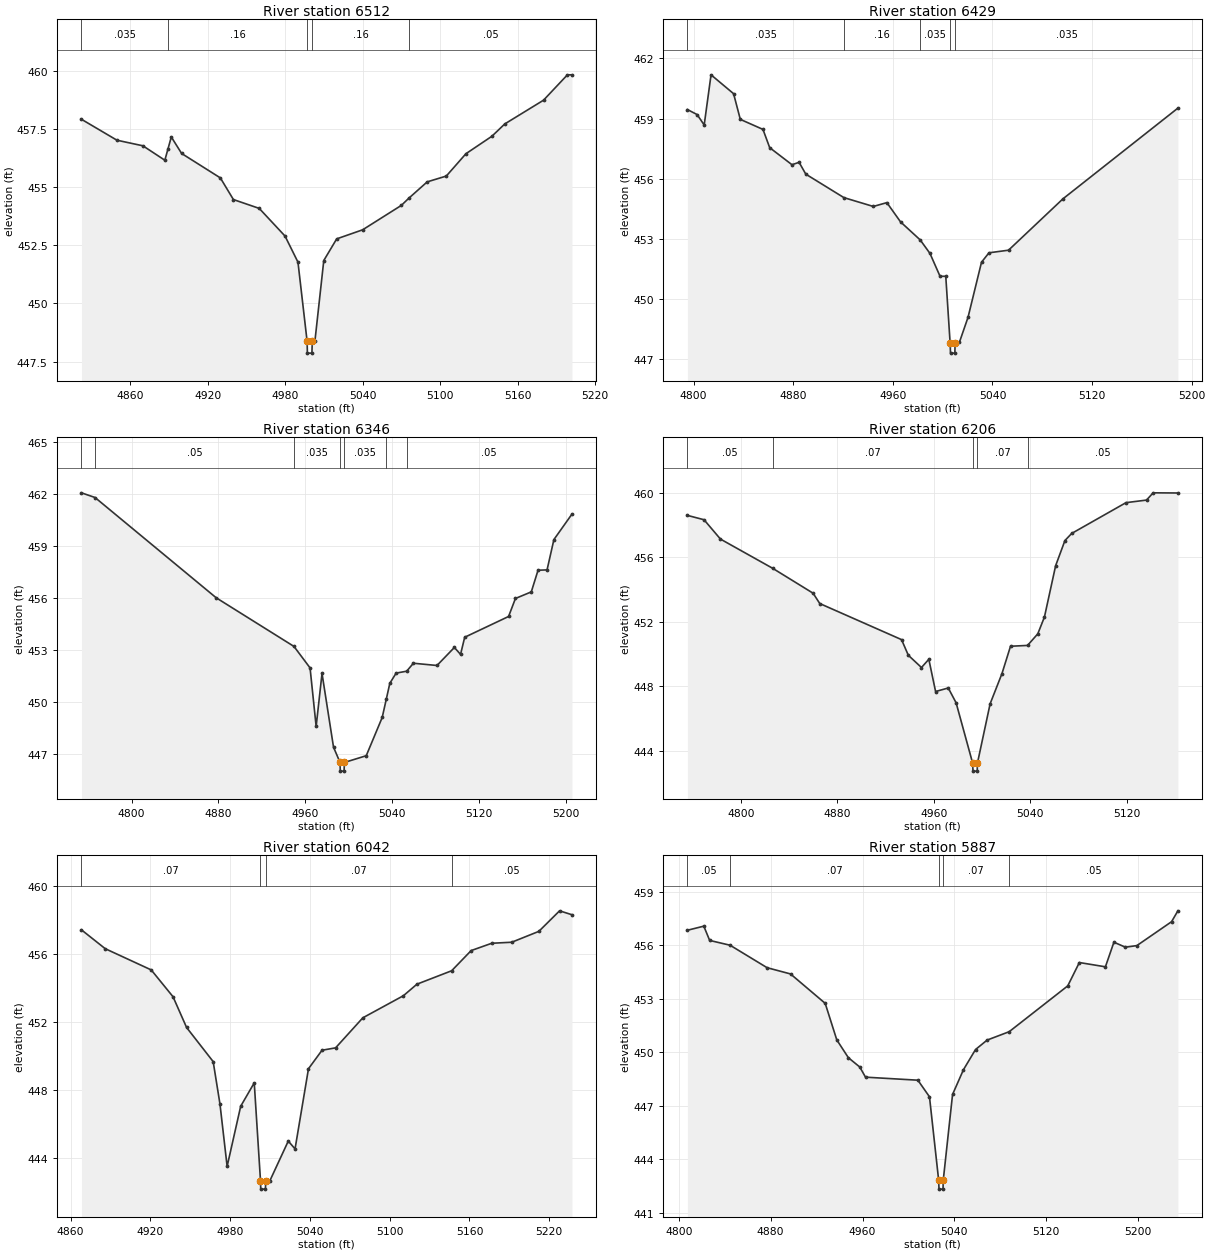
Type RM Length L Ch R = 1,6512,83,83,83
BEGIN DESCRIPTION:
Purtis Creek Trib C6511.88
END DESCRIPTION:
XS GIS Cut Line= 3
      2754864.31      6830883.49      2754855.34      6831064.08
      2754846.84      6831262.99
#Sta/Elev= 30
  4822.2  457.91  4849.7  457.01  4869.8  456.77  4886.8  456.15  4889.2  456.63
  4891.8  457.15  4899.8  456.44  4929.8  455.39  4939.9  454.46  4959.9  454.08
  4979.9  452.89  4989.9  451.77  4997.0  448.36  4997.2  447.86  5000.7  447.86
  5001.0  448.36  5003.0  448.36  5009.9  451.84  5019.9  452.77  5040.0  453.16
  5070.0  454.21  5075.8  454.52  5090.0  455.22  5104.8  455.47  5120.0  456.43
  5140.1  457.18  5150.1  457.71  5180.1  458.73  5198.6  459.82  5202.1  459.82
#Mann=5,-1,0
  4822.2   0.035       0  4889.2    0.16       0  4997.0    0.07       0
  5001.0    0.16       0  5075.8    0.05       0
Bank Sta=4997,5001
Exp/Cntr=0.3,0.1

Type RM Length L Ch R = 1,6429,83,83,83
BEGIN DESCRIPTION:
Purtis Creek Trib C6428.73
END DESCRIPTION:
XS GIS Cut Line= 4
      2754866.43      6830833.81      2754784.66      6831024.49
      2754751.50      6831103.78      2754704.33      6831192.51
#Sta/Elev= 30
  4795.0  459.45  4802.8  459.20  4808.5  458.68  4814.0  461.18  4832.1  460.24
  4837.5  458.96  4855.7  458.46  4861.1  457.55  4879.0  456.70  4884.7  456.82
  4890.1  456.23  4920.7  455.06  4944.3  454.62  4955.2  454.81  4966.2  453.85
  4982.0  452.95  4989.8  452.28  4997.9  451.14  5002.5  451.14  5006.0  447.81
  5006.3  447.31  5009.8  447.31  5010.0  447.81  5013.4  447.84  5020.4  449.10
  5031.2  451.84  5037.2  452.31  5052.9  452.44  5096.6  455.00  5188.9  459.52
#Mann=5,-1,0
  4795.0   0.035       0  4920.7    0.16       0  4982.0   0.035       0
  5006.0   0.035       0  5010.0   0.035       0
Bank Sta=5006,5010
Exp/Cntr=0.3,0.1

Type RM Length L Ch R = 1,6346,140,140,140
BEGIN DESCRIPTION:
Purtis Creek Trib C6345.64
END DESCRIPTION:
XS GIS Cut Line= 4
      2754802.84      6830766.27      2754708.15      6830997.74
      2754657.27      6831088.50      2754598.51      6831166.01
#Sta/Elev= 30
  4753.9  462.09  4766.4  461.82  4877.9  456.03  4949.5  453.22  4964.3  451.98
  4969.9  448.60  4975.3  451.66  4985.9  447.40  4991.9  446.52  4992.1  446.02
  4995.6  446.02  4995.9  446.52  5016.0  446.91  5030.7  449.12  5034.4  450.16
  5037.7  451.09  5043.5  451.68  5053.2  451.79  5059.4  452.25  5081.1  452.12
  5097.1  453.16  5102.8  452.76  5106.6  453.75  5147.0  454.95  5153.3  455.99
  5167.9  456.37  5174.1  457.62  5182.4  457.64  5188.7  459.39  5205.3  460.86
#Mann=7,-1,0
  4753.9   0.035       0  4766.4    0.05       0  4949.5   0.035       0
  4991.9   0.035       0  4995.9   0.035       0  5034.4    0.07       0
  5053.2    0.05       0
Bank Sta=4991.9,4995.9
Exp/Cntr=0.3,0.1

Type RM Length L Ch R = 1,6206,164,164,164
BEGIN DESCRIPTION:
Purtis Creek Trib C6205.92
END DESCRIPTION:
XS GIS Cut Line= 3
      2754688.34      6830736.34      2754581.59      6830957.14
      2754510.91      6831102.07
#Sta/Elev= 30
  4755.8  458.61  4769.6  458.34  4783.2  457.14  4826.4  455.33  4860.0  453.78
  4865.5  453.14  4933.3  450.90  4938.9  449.93  4949.8  449.17  4955.9  449.68
  4961.5  447.68  4972.0  447.90  4978.5  446.98  4992.2  443.24  4992.5  442.74
  4996.0  442.74  4996.2  443.24  5006.7  446.92  5016.5  448.79  5023.6  450.49
  5037.7  450.54  5046.2  451.26  5051.7  452.30  5061.0  455.49  5068.7  457.05
  5074.3  457.49  5119.3  459.40  5136.3  459.56  5141.8  460.01  5162.3  460.00
#Mann=5,-1,0
  4755.8    0.05       0  4826.4    0.07       0  4992.2    0.07       0
  4996.2    0.07       0  5037.7    0.05       0
Bank Sta=4992.2,4996.2
Exp/Cntr=0.3,0.1

Type RM Length L Ch R = 1,6042,155,155,155
BEGIN DESCRIPTION:
Purtis Creek Trib C6042.12
END DESCRIPTION:
XS GIS Cut Line= 3
      2754540.84      6830683.39      2754514.40      6830819.14
      2754469.23      6831045.37
#Sta/Elev= 30
  4868.1  457.42  4886.0  456.31  4920.6  455.06  4937.0  453.48  4947.2  451.67
  4967.2  449.66  4972.3  447.17  4977.7  443.49  4987.9  447.03  4998.1  448.41
  5002.8  442.65  5003.0  442.15  5006.5  442.15  5006.8  442.65  5009.9  442.65
  5023.7  444.98  5028.8  444.52  5038.9  449.24  5049.1  450.33  5059.3  450.47
  5079.8  452.24  5110.3  453.54  5120.5  454.22  5146.6  455.01  5161.3  456.20
  5176.8  456.63  5191.8  456.69  5212.2  457.33  5227.8  458.54  5237.1  458.31
#Mann=4,-1,0
  4868.1    0.07       0  5002.8    0.07       0  5006.8    0.07       0
  5146.6    0.05       0
Bank Sta=5002.8,5006.8
Exp/Cntr=0.3,0.1

Type RM Length L Ch R = 1,5887,162,162,162
BEGIN DESCRIPTION:
Purtis Creek Trib C5886.59
END DESCRIPTION:
XS GIS Cut Line= 3
      2754413.12      6830632.27      2754385.30      6830825.10
      2754365.40      6831056.52
#Sta/Elev= 30
  4807.5  456.85  4821.8  457.08  4826.9  456.28  4844.7  456.01  4876.9  454.75
  4897.3  454.40  4927.5  452.75  4937.6  450.70  4947.7  449.70  4957.6  449.18
  4962.6  448.61  5008.2  448.44  5018.3  447.51  5026.3  442.83  5026.6  442.33
  5030.1  442.33  5030.3  442.83  5038.4  447.64  5047.9  449.03  5058.4  450.16
  5068.5  450.69  5087.7  451.16  5138.7  453.73  5148.8  455.04  5171.5  454.80
  5178.9  456.18  5188.9  455.90  5198.9  455.99  5229.1  457.33  5234.6  457.94
#Mann=5,-1,0
  4807.5    0.05       0  4844.7    0.07       0  5026.3    0.07       0
  5030.3    0.07       0  5087.7    0.05       0
Bank Sta=5026.3,5030.3
Exp/Cntr=0.3,0.1

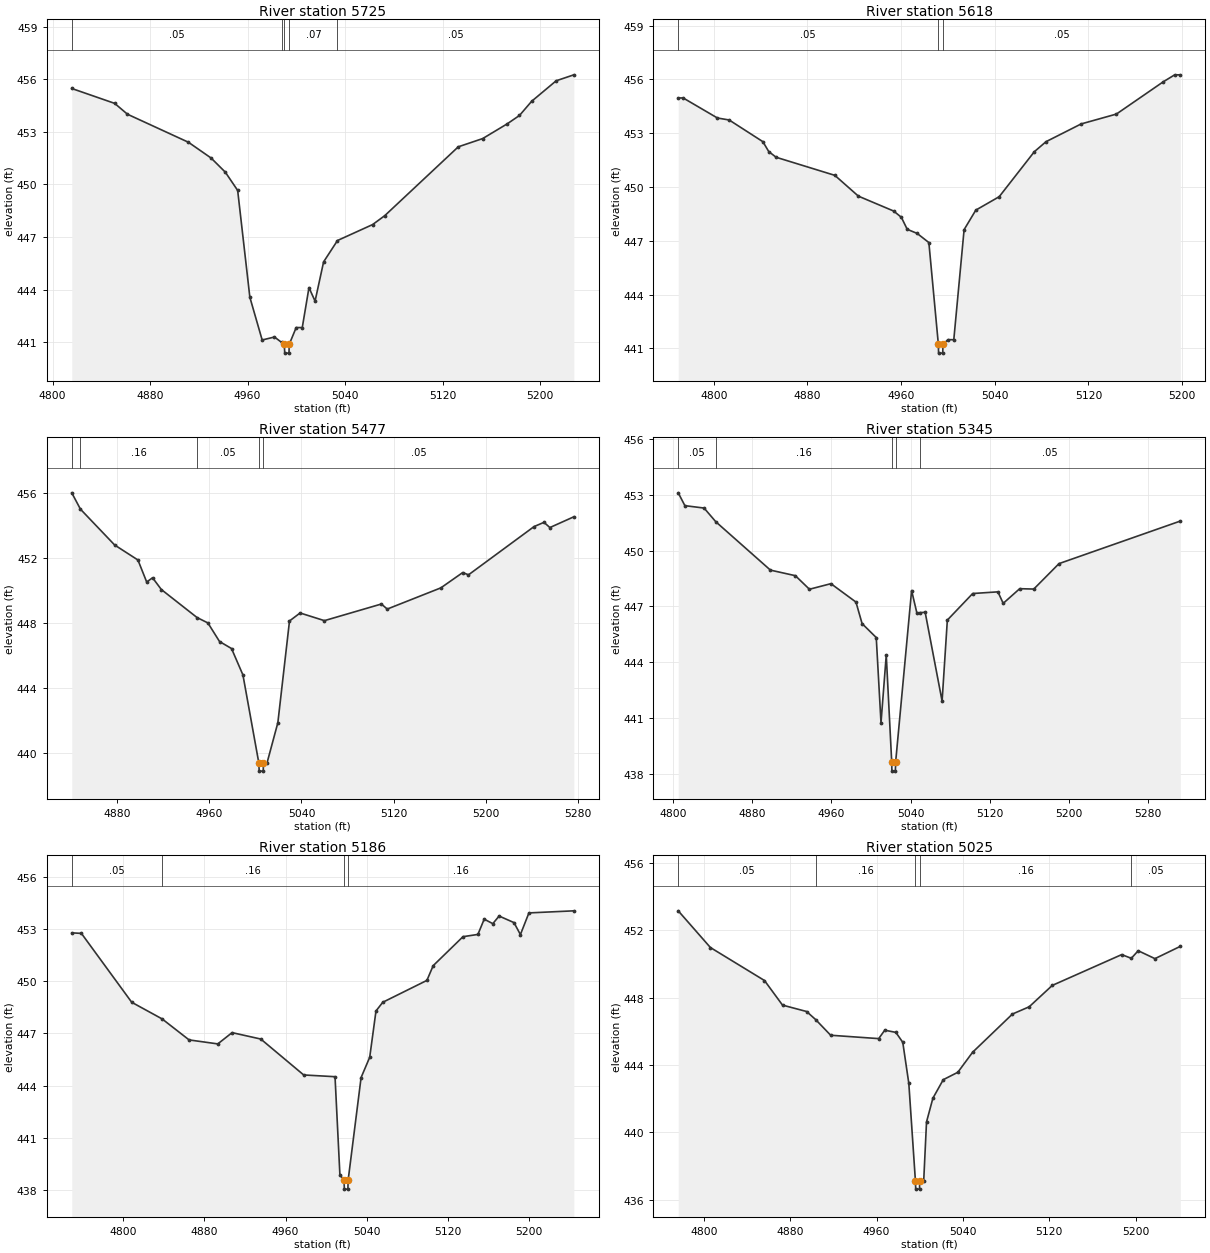
Type RM Length L Ch R = 1,5725,107,107,107
BEGIN DESCRIPTION:
Purtis Creek Trib C5724.85
END DESCRIPTION:
XS GIS Cut Line= 3
      2754306.34      6830536.10      2754282.01      6830721.28
      2754261.15      6830945.44
#Sta/Elev= 30
  4815.8  455.48  4851.0  454.63  4861.5  454.01  4911.5  452.41  4930.1  451.51
  4941.8  450.70  4951.9  449.66  4961.9  443.56  4972.0  441.12  4982.1  441.29
  4988.0  440.98  4990.2  440.87  4990.5  440.37  4994.0  440.37  4994.2  440.87
  4999.9  441.83  5004.9  441.83  5010.4  444.11  5015.4  443.34  5022.4  445.58
  5033.8  446.80  5062.6  447.71  5072.6  448.22  5132.9  452.15  5152.9  452.62
  5173.0  453.46  5183.1  453.94  5193.1  454.75  5213.2  455.92  5227.7  456.26
#Mann=5,-1,0
  4815.8    0.05       0  4988.0    0.07       0  4990.2    0.07       0
  4994.2    0.07       0  5033.8    0.05       0
Bank Sta=4990.2,4994.2
Exp/Cntr=0.3,0.1

Type RM Length L Ch R = 1,5618,141,141,141
BEGIN DESCRIPTION:
Purtis Creek Trib C5618.32
END DESCRIPTION:
XS GIS Cut Line= 3
      2754197.53      6830477.67      2754177.61      6830708.36
      2754171.73      6830905.62
#Sta/Elev= 30
  4769.6  454.97  4773.8  454.97  4803.1  453.85  4813.1  453.74  4841.9  452.53
  4846.9  451.98  4853.2  451.66  4903.4  450.65  4923.5  449.49  4953.6  448.66
  4960.2  448.31  4965.2  447.64  4973.7  447.41  4983.7  446.90  4991.8  441.23
  4992.0  440.73  4995.5  440.73  4995.8  441.23  5000.0  441.48  5005.0  441.48
  5013.8  447.62  5023.8  448.71  5043.8  449.46  5073.8  451.97  5083.8  452.53
  5113.8  453.52  5143.9  454.07  5183.9  455.87  5193.7  456.26  5198.5  456.26
#Mann=3,-1,0
  4769.6    0.05       0  4991.8    0.05       0  4995.8    0.05       0
Bank Sta=4991.8,4995.8
Exp/Cntr=0.3,0.1

Type RM Length L Ch R = 1,5477,132,132,132
BEGIN DESCRIPTION:
Purtis Creek Trib C5476.84
END DESCRIPTION:
XS GIS Cut Line= 3
      2754081.19      6830484.23      2754056.29      6830647.30
      2754017.84      6830915.19
#Sta/Elev= 30
  4840.7  455.98  4848.2  454.98  4877.9  452.78  4898.1  451.86  4905.7  450.51
  4910.8  450.77  4918.4  450.05  4949.4  448.33  4958.8  448.00  4968.9  446.86
  4979.3  446.43  4989.2  444.81  5003.0  439.41  5003.3  438.91  5006.8  438.91
  5007.0  439.41  5010.1  439.41  5019.5  441.88  5029.6  448.12  5038.8  448.61
  5059.9  448.14  5109.3  449.16  5114.4  448.85  5160.9  450.15  5179.9  451.09
  5184.9  450.95  5241.8  453.91  5250.4  454.17  5255.5  453.85  5276.3  454.51
#Mann=5,-1,0
  4840.7    0.05       0  4848.2    0.16       0  4949.4    0.05       0
  5003.0    0.05       0  5007.0    0.05       0
Bank Sta=5003,5007
Exp/Cntr=0.3,0.1

Type RM Length L Ch R = 1,5345,159,159,159
BEGIN DESCRIPTION:
Purtis Creek Trib C5344.8
END DESCRIPTION:
XS GIS Cut Line= 3
      2754002.11      6830426.51      2753933.64      6830614.45
      2753830.87      6830903.82
#Sta/Elev= 30
  4805.3  453.11  4812.0  452.42  4831.4  452.29  4843.3  451.55  4898.4  448.95
  4923.6  448.65  4937.8  447.92  4959.5  448.22  4984.8  447.23  4991.0  446.07
  5005.3  445.32  5010.1  440.73  5015.4  444.38  5020.9  438.63  5021.1  438.13
  5024.6  438.13  5024.9  438.63  5041.0  447.85  5046.3  446.65  5049.6  446.66
  5054.7  446.68  5071.8  441.90  5077.1  446.26  5102.7  447.69  5128.2  447.78
  5133.5  447.16  5150.2  447.95  5164.4  447.93  5189.9  449.30  5312.4  451.59
#Mann=5,-1,0
  4805.3    0.05       0  4843.3    0.16       0  5020.9    0.07       0
  5024.9    0.16       0  5049.6    0.05       0
Bank Sta=5020.9,5024.9
Exp/Cntr=0.3,0.1

Type RM Length L Ch R = 1,5186,161,161,161
BEGIN DESCRIPTION:
Purtis Creek Trib C5186.08
END DESCRIPTION:
XS GIS Cut Line= 3
      2753979.48      6830360.97      2753796.58      6830539.70
      2753656.34      6830733.69
#Sta/Elev= 30
  4749.2  452.80  4758.7  452.77  4808.3  448.80  4838.3  447.84  4864.9  446.63
  4893.2  446.40  4907.3  447.05  4935.6  446.68  4977.9  444.61  5008.8  444.51
  5013.6  438.86  5017.7  438.53  5018.0  438.03  5021.5  438.03  5021.7  438.53
  5034.5  444.46  5043.0  445.63  5049.2  448.30  5055.9  448.80  5099.4  450.06
  5105.6  450.91  5135.0  452.58  5149.7  452.71  5155.9  453.59  5164.4  453.33
  5170.6  453.77  5185.3  453.39  5191.6  452.70  5200.0  453.95  5244.3  454.07
#Mann=4,-1,0
  4749.2    0.05       0  4838.3    0.16       0  5017.7    0.07       0
  5021.7    0.16       0
Bank Sta=5017.7,5021.7
Exp/Cntr=0.3,0.1

Type RM Length L Ch R = 1,5025,209,209,209
BEGIN DESCRIPTION:
Purtis Creek Trib C5024.8
END DESCRIPTION:
XS GIS Cut Line= 3
      2753975.84      6830281.69      2753775.02      6830383.31
      2753569.51      6830507.33
#Sta/Elev= 30
  4776.3  453.15  4806.1  450.97  4856.2  449.01  4872.9  447.55  4895.2  447.17
  4903.6  446.69  4917.5  445.76  4962.0  445.56  4967.6  446.06  4977.9  445.93
  4984.3  445.34  4989.9  442.90  4996.0  437.12  4996.3  436.62  4999.8  436.62
  5000.0  437.12  5003.7  437.12  5006.3  440.61  5012.2  442.02  5021.8  443.12
  5035.3  443.56  5049.0  444.75  5085.9  447.02  5101.4  447.45  5122.8  448.72
  5187.1  450.55  5196.0  450.33  5202.4  450.78  5217.9  450.31  5241.4  451.04
#Mann=5,-1,0
  4776.3    0.05       0  4903.6    0.16       0  4996.0    0.07       0
  5000.0    0.16       0  5196.0    0.05       0
Bank Sta=4996,5000
Exp/Cntr=0.3,0.1

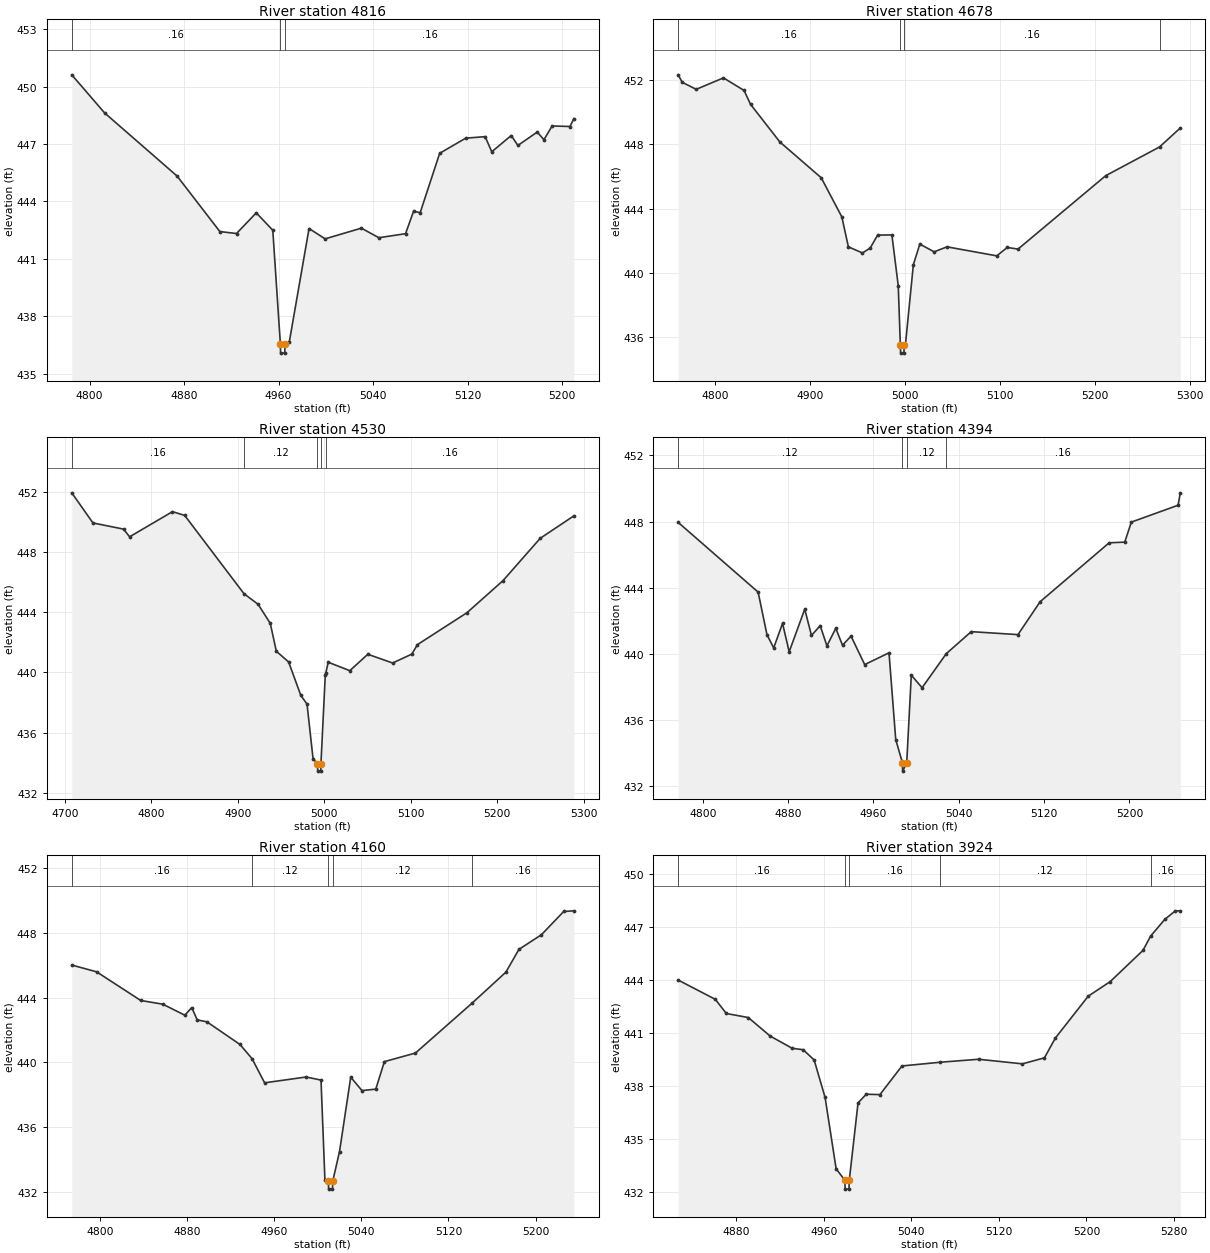
Type RM Length L Ch R = 1,4816,138,138,138
BEGIN DESCRIPTION:
Purtis Creek Trib C4816.18
END DESCRIPTION:
XS GIS Cut Line= 3
      2753752.30      6830068.86      2753653.88      6830265.17
      2753558.64      6830447.27
#Sta/Elev= 30
  4784.9  450.61  4812.7  448.62  4874.1  445.32  4910.3  442.42  4924.4  442.32
  4941.1  443.40  4955.1  442.49  4961.5  436.57  4961.7  436.07  4965.2  436.07
  4965.5  436.57  4969.1  436.66  4985.8  442.58  4999.4  442.04  5030.1  442.60
  5044.9  442.10  5067.5  442.31  5074.3  443.48  5079.9  443.41  5096.4  446.51
  5118.4  447.30  5134.9  447.38  5140.5  446.59  5157.0  447.44  5162.6  446.92
  5179.0  447.62  5184.7  447.22  5191.6  447.94  5206.7  447.91  5210.0  448.32
#Mann=3,-1,0
  4784.9    0.16       0  4961.5    0.07       0  4965.5    0.16       0
Bank Sta=4961.5,4965.5
Exp/Cntr=0.3,0.1

Type RM Length L Ch R = 1,4678,148,148,148
BEGIN DESCRIPTION:
Purtis Creek Trib C4678.18
END DESCRIPTION:
XS GIS Cut Line= 3
      2753664.21      6829974.51      2753547.85      6830183.37
      2753428.39      6830446.98
#Sta/Elev= 30
  4761.3  452.30  4765.4  451.84  4780.2  451.40  4808.9  452.11  4830.6  451.33
  4837.4  450.47  4868.3  448.13  4911.8  445.91  4933.5  443.48  4940.4  441.62
  4955.2  441.24  4963.3  441.54  4971.2  442.35  4986.2  442.36  4992.9  439.20
  4995.1  435.52  4995.4  435.02  4998.9  435.02  4999.1  435.52  5000.4  435.52
  5008.8  440.51  5015.6  441.79  5030.7  441.31  5044.2  441.62  5096.6  441.06
  5107.6  441.58  5119.0  441.48  5211.3  446.04  5267.9  447.82  5289.8  449.00
#Mann=4,-1,0
  4761.3    0.16       0  4995.1    0.07       0  4999.1    0.16       0
  5267.9    0.12       0
Bank Sta=4995.1,4999.1
Exp/Cntr=0.3,0.1

Type RM Length L Ch R = 1,4530,136,136,136
BEGIN DESCRIPTION:
Purtis Creek Trib C4530.1
END DESCRIPTION:
XS GIS Cut Line= 3
      2753634.21      6829894.51      2753426.27      6830106.39
      2753245.73      6830325.40
#Sta/Elev= 30
  4707.8  451.93  4732.3  449.93  4767.7  449.52  4774.7  449.01  4824.3  450.68
  4838.4  450.43  4907.0  445.23  4923.3  444.53  4937.4  443.26  4944.4  441.41
  4958.6  440.70  4972.7  438.48  4979.9  437.90  4986.9  434.26  4992.0  433.95
  4992.3  433.45  4995.8  433.45  4996.0  433.95  5001.0  439.81  5001.6  439.96
  5004.4  440.68  5029.4  440.12  5050.2  441.21  5078.9  440.63  5101.1  441.22
  5107.6  441.85  5164.9  443.97  5206.6  446.10  5249.6  448.91  5288.5  450.40
#Mann=5,-1,0
  4707.8    0.16       0  4907.0    0.12       0  4992.0    0.07       0
  4996.0    0.12       0  5001.6    0.16       0
Bank Sta=4992,4996
Exp/Cntr=0.3,0.1

Type RM Length L Ch R = 1,4394,234,234,234
BEGIN DESCRIPTION:
Purtis Creek Trib C4394.39
END DESCRIPTION:
XS GIS Cut Line= 3
      2753512.92      6829821.86      2753376.31      6830002.10
      2753230.01      6830198.04
#Sta/Elev= 30
  4777.0  447.95  4851.9  443.74  4860.2  441.16  4866.5  440.37  4874.8  441.85
  4881.0  440.13  4895.6  442.71  4901.9  441.12  4910.1  441.71  4916.4  440.49
  4924.7  441.55  4931.0  440.53  4939.0  441.08  4951.8  439.36  4974.6  440.07
  4980.9  434.83  4987.2  433.42  4987.4  432.92  4991.2  433.42  4995.5  438.72
  5005.6  437.96  5028.3  440.02  5051.7  441.35  5095.5  441.17  5116.3  443.16
  5181.0  446.72  5195.6  446.76  5201.8  447.97  5245.6  448.99  5247.7  449.74
#Mann=4,-1,0
  4777.0    0.12       0  4987.2    0.07       0  4991.2    0.12       0
  5028.3    0.16       0
Bank Sta=4987.2,4991.2
Exp/Cntr=0.3,0.1

Type RM Length L Ch R = 1,4160,236,236,236
BEGIN DESCRIPTION:
Purtis Creek Trib C4160.2
END DESCRIPTION:
XS GIS Cut Line= 3
      2753308.69      6829638.50      2753272.36      6829864.50
      2753216.94      6830089.99
#Sta/Elev= 30
  4774.1  446.01  4796.9  445.59  4837.4  443.82  4857.7  443.59  4877.9  442.91
  4884.3  443.38  4889.3  442.62  4898.2  442.50  4928.6  441.10  4939.7  440.22
  4951.2  438.73  4989.3  439.09  5003.0  438.90  5006.6  432.71  5009.8  432.66
  5010.0  432.16  5013.5  432.16  5013.8  432.66  5020.0  434.48  5030.3  439.08
  5040.6  438.25  5053.3  438.34  5061.2  440.04  5089.7  440.57  5142.0  443.67
  5172.8  445.57  5184.8  446.98  5205.4  447.88  5225.9  449.32  5235.2  449.36
#Mann=5,-1,0
  4774.1    0.16       0  4939.7    0.12       0  5009.8    0.07       0
  5013.8    0.12       0  5142.0    0.16       0
Bank Sta=5009.8,5013.8
Exp/Cntr=0.3,0.1

Type RM Length L Ch R = 1,3924,184,184,184
BEGIN DESCRIPTION:
Purtis Creek Trib C3923.94
END DESCRIPTION:
XS GIS Cut Line= 3
      2753146.30      6829547.17      2753134.38      6829720.88
      2753123.10      6830005.04
#Sta/Elev= 30
  4827.2  444.00  4861.1  442.91  4871.1  442.11  4891.2  441.88  4911.2  440.83
  4931.3  440.14  4941.3  440.06  4951.3  439.48  4961.3  437.36  4971.4  433.32
  4979.4  432.67  4979.6  432.17  4983.1  432.17  4983.4  432.67  4991.4  437.05
  4998.9  437.54  5011.4  437.52  5031.5  439.14  5066.2  439.35  5101.5  439.52
  5141.5  439.26  5161.6  439.60  5171.6  440.72  5201.6  443.09  5221.6  443.91
  5251.6  445.68  5258.6  446.49  5271.6  447.44  5281.2  447.92  5285.7  447.92
#Mann=5,-1,0
  4827.2    0.16       0  4979.4    0.07       0  4983.4    0.16       0
  5066.2    0.12       0  5258.6    0.16       0
Bank Sta=4979.4,4983.4
Exp/Cntr=0.3,0.1