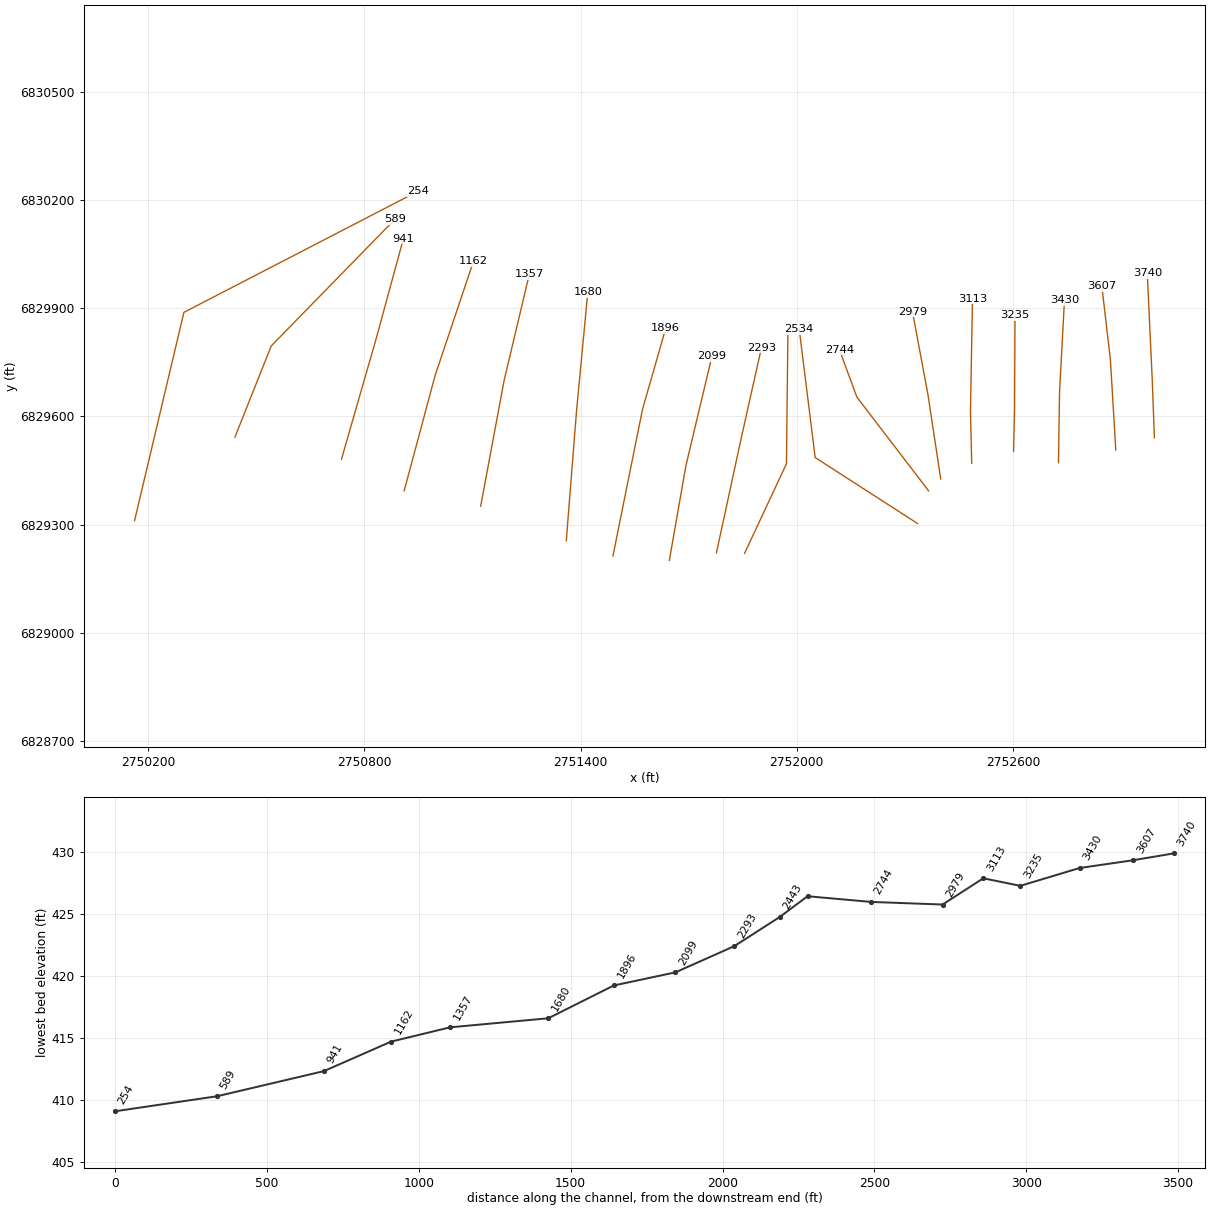
HEC-RAS study Purtis Creek Trib C.prj: Purtis Creek Trib C Base Level Engineering

--- Purtis Creek Trib C.g01 (geometry) --- (continued)

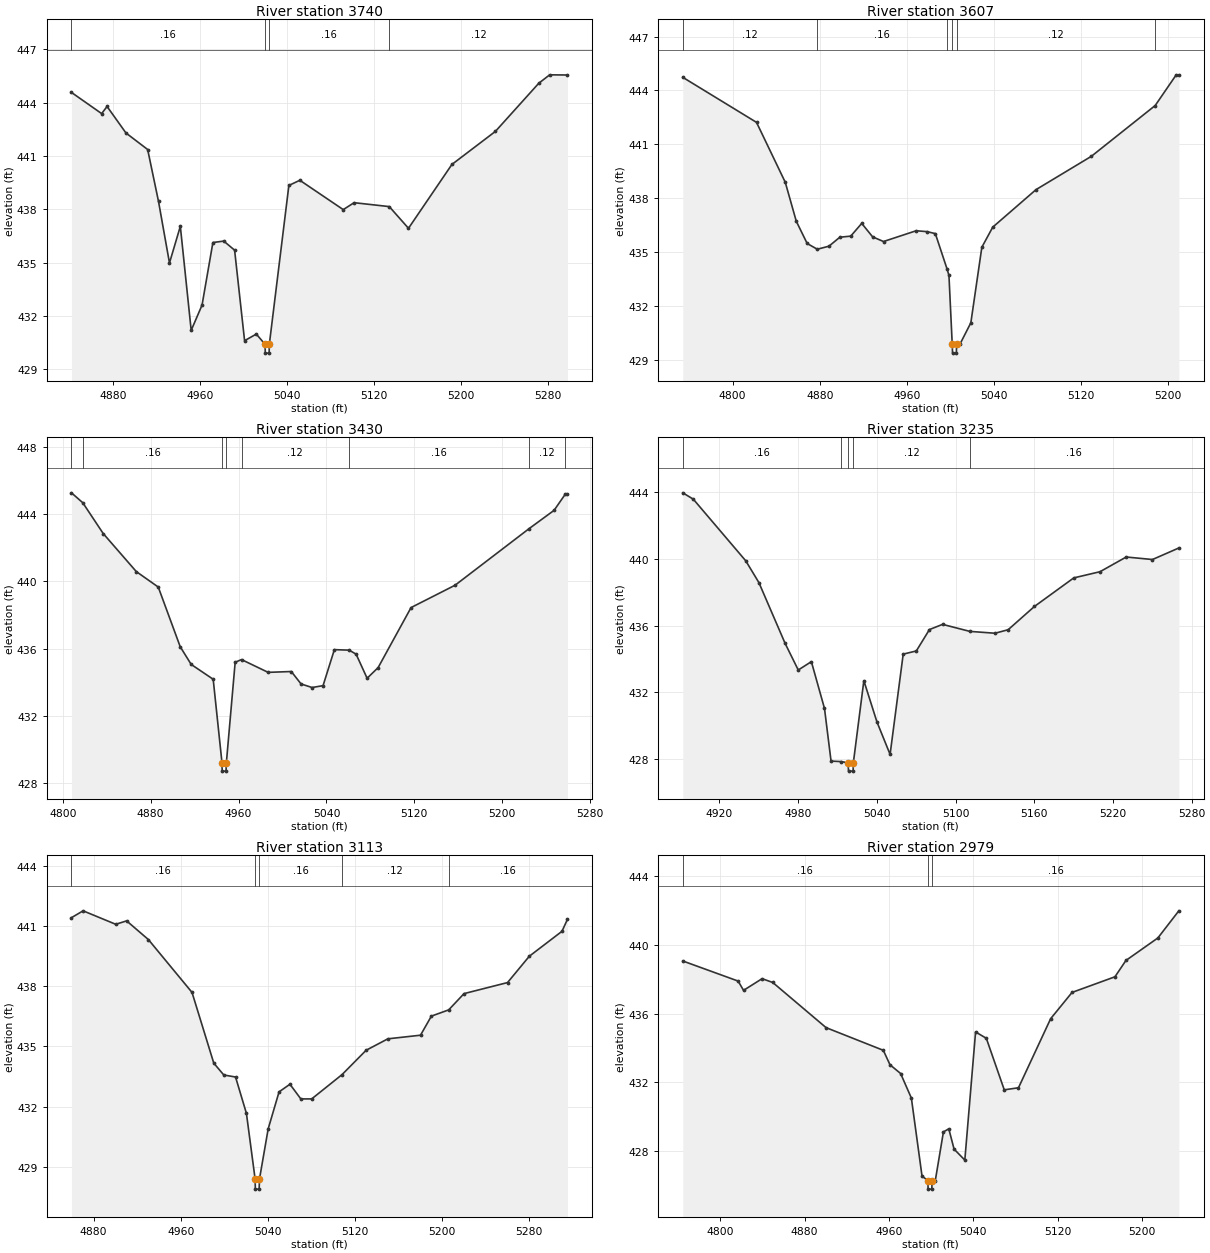
Type RM Length L Ch R = 1,3740,133,133,133
BEGIN DESCRIPTION:
Purtis Creek Trib C3739.8
END DESCRIPTION:
XS GIS Cut Line= 3
      2752992.15      6829540.81      2752985.99      6829704.30
      2752972.31      6829997.37
#Sta/Elev= 30
  4841.4  444.57  4869.2  443.38  4874.2  443.78  4891.6  442.29  4911.6  441.36
  4921.6  438.44  4931.7  434.98  4941.7  437.04  4951.7  431.19  4961.7  432.61
  4971.7  436.13  4981.7  436.21  4991.7  435.70  5000.9  430.61  5011.7  430.98
  5019.7  430.41  5020.0  429.91  5023.5  429.91  5023.7  430.41  5041.7  439.34
  5051.8  439.63  5091.8  437.98  5101.8  438.37  5134.2  438.15  5151.9  436.93
  5191.9  440.52  5232.0  442.38  5272.0  445.09  5282.0  445.56  5298.4  445.55
#Mann=4,-1,0
  4841.4    0.16       0  5019.7    0.07       0  5023.7    0.16       0
  5134.2    0.12       0
Bank Sta=5019.7,5023.7
Exp/Cntr=0.3,0.1

Type RM Length L Ch R = 1,3607,177,177,177
BEGIN DESCRIPTION:
Purtis Creek Trib C3607.17
END DESCRIPTION:
XS GIS Cut Line= 3
      2752884.95      6829507.03      2752870.10      6829756.05
      2752846.41      6829960.72
#Sta/Elev= 30
  4754.3  444.73  4822.0  442.22  4848.4  438.88  4858.5  436.71  4868.5  435.47
  4877.8  435.15  4888.5  435.32  4898.5  435.82  4908.5  435.88  4918.6  436.59
  4928.6  435.84  4938.6  435.58  4968.6  436.18  4978.7  436.13  4986.2  436.02
  4996.9  434.06  4998.7  433.69  5001.7  429.86  5002.0  429.36  5005.5  429.36
  5005.7  429.86  5008.8  429.86  5018.8  431.05  5028.9  435.26  5038.9  436.38
  5078.6  438.47  5129.5  440.33  5188.1  443.16  5207.4  444.87  5209.8  444.87
#Mann=6,-1,0
  4754.3    0.12       0  4877.8    0.16       0  4996.9    0.12       0
  5001.7    0.07       0  5005.7    0.12       0  5188.1    0.16       0
Bank Sta=5001.7,5005.7
Exp/Cntr=0.3,0.1

Type RM Length L Ch R = 1,3430,195,195,195
BEGIN DESCRIPTION:
Purtis Creek Trib C3430.01
END DESCRIPTION:
XS GIS Cut Line= 3
      2752725.97      6829472.05      2752728.94      6829668.21
      2752742.62      6829923.17
#Sta/Elev= 30
  4807.9  445.27  4818.2  444.68  4836.8  442.85  4866.9  440.59  4886.9  439.67
  4906.9  436.12  4916.9  435.07  4936.9  434.19  4944.9  429.23  4945.1  428.73
  4948.6  428.73  4948.9  429.23  4956.9  435.20  4962.7  435.36  4986.9  434.60
  5008.0  434.65  5016.9  433.91  5026.9  433.70  5036.9  433.81  5047.2  435.95
  5060.7  435.92  5067.0  435.68  5077.0  434.25  5087.0  434.88  5117.0  438.45
  5157.1  439.78  5224.2  443.13  5247.2  444.23  5257.5  445.20  5259.4  445.20
#Mann=8,-1,0
  4807.9    0.12       0  4818.2    0.16       0  4944.9    0.07       0
  4948.9    0.16       0  4962.7    0.12       0  5060.7    0.16       0
  5224.2    0.12       0  5257.5    0.16       0
Bank Sta=4944.9,4948.9
Exp/Cntr=0.3,0.1

Type RM Length L Ch R = 1,3235,122,122,122
BEGIN DESCRIPTION:
Purtis Creek Trib C3235.18
END DESCRIPTION:
XS GIS Cut Line= 3
      2752601.32      6829503.03      2752604.09      6829616.05
      2752605.40      6829881.10
#Sta/Elev= 30
  4892.1  443.94  4900.1  443.56  4940.1  439.87  4950.1  438.57  4970.1  434.93
  4980.1  433.34  4990.1  433.84  5000.1  431.04  5005.1  427.89  5012.9  427.86
  5018.1  427.79  5018.4  427.29  5021.9  427.29  5022.1  427.79  5030.1  432.70
  5040.1  430.23  5050.1  428.29  5060.1  434.29  5070.1  434.48  5080.1  435.76
  5090.1  436.07  5110.9  435.65  5130.1  435.54  5140.1  435.75  5160.1  437.14
  5190.1  438.85  5210.1  439.22  5230.1  440.10  5250.1  439.95  5270.2  440.64
#Mann=5,-1,0
  4892.1    0.16       0  5012.9    0.12       0  5018.1    0.07       0
  5022.1    0.12       0  5110.9    0.16       0
Bank Sta=5018.1,5022.1
Exp/Cntr=0.3,0.1

Type RM Length L Ch R = 1,3113,134,134,134
BEGIN DESCRIPTION:
Purtis Creek Trib C3113.07
END DESCRIPTION:
XS GIS Cut Line= 3
      2752485.27      6829470.28      2752481.79      6829614.39
      2752487.47      6829926.08
#Sta/Elev= 30
  4859.6  441.41  4870.3  441.75  4900.3  441.08  4910.3  441.25  4930.3  440.32
  4970.4  437.69  4990.4  434.17  4999.6  433.58  5010.4  433.48  5020.4  431.67
  5028.4  428.40  5028.6  427.90  5032.1  427.90  5032.4  428.40  5040.4  430.90
  5050.4  432.74  5060.4  433.12  5070.4  432.39  5080.4  432.39  5108.3  433.60
  5130.4  434.81  5150.4  435.38  5180.4  435.56  5190.4  436.51  5206.3  436.82
  5220.4  437.63  5260.4  438.18  5280.4  439.49  5310.4  440.73  5315.5  441.33
#Mann=5,-1,0
  4859.6    0.16       0  5028.4    0.07       0  5032.4    0.16       0
  5108.3    0.12       0  5206.3    0.16       0
Bank Sta=5028.4,5032.4
Exp/Cntr=0.3,0.1

Type RM Length L Ch R = 1,2979,235,235,235
BEGIN DESCRIPTION:
Purtis Creek Trib C2979.45
END DESCRIPTION:
XS GIS Cut Line= 3
      2752399.25      6829426.68      2752363.83      6829660.90
      2752320.89      6829890.53
#Sta/Elev= 30
  4764.5  439.06  4817.0  437.89  4822.1  437.35  4839.7  438.03  4849.8  437.81
  4900.4  435.18  4954.7  433.86  4961.0  433.02  4971.1  432.51  4981.3  431.08
  4991.4  426.54  4996.9  426.28  4997.2  425.78  5000.7  425.78  5000.9  426.28
  5004.0  426.28  5011.7  429.11  5016.8  429.29  5021.8  428.11  5032.0  427.47
  5042.2  434.93  5052.4  434.56  5069.4  431.56  5082.9  431.68  5113.4  435.70
  5133.7  437.23  5174.4  438.14  5184.8  439.09  5215.1  440.40  5235.0  441.98
#Mann=3,-1,0
  4764.5    0.16       0  4996.9    0.07       0  5000.9    0.16       0
Bank Sta=4996.9,5000.9
Exp/Cntr=0.3,0.1

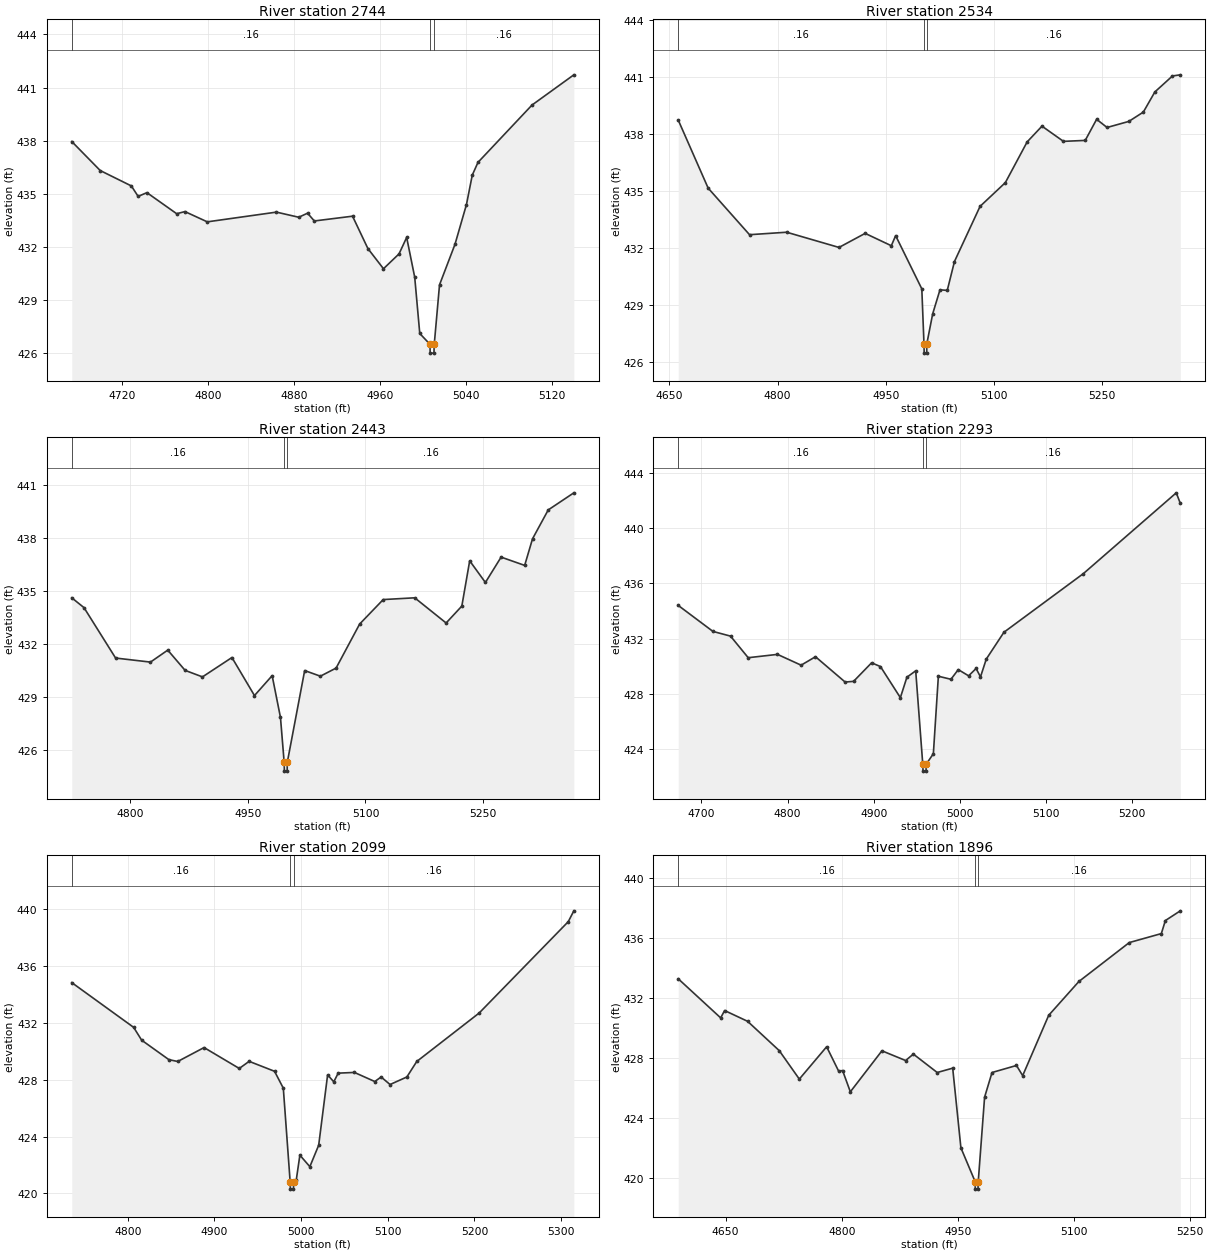
Type RM Length L Ch R = 1,2744,210,210,210
BEGIN DESCRIPTION:
Purtis Creek Trib C2744.41
END DESCRIPTION:
XS GIS Cut Line= 3
      2752365.88      6829393.39      2752166.71      6829653.54
      2752118.34      6829784.87
#Sta/Elev= 30
  4673.2  437.95  4699.7  436.31  4728.7  435.44  4735.0  434.85  4743.2  435.06
  4770.9  433.87  4778.6  433.99  4799.4  433.41  4863.8  433.96  4884.6  433.67
  4892.8  433.90  4899.1  433.46  4934.7  433.73  4949.0  431.90  4963.5  430.76
  4978.0  431.60  4985.1  432.53  4992.6  430.28  4997.3  427.10  5006.8  426.49
  5007.0  425.99  5010.5  425.99  5010.8  426.49  5015.7  429.85  5030.1  432.14
  5040.8  434.39  5046.2  436.05  5051.5  436.77  5101.8  440.01  5140.8  441.72
#Mann=3,-1,0
  4673.2    0.16       0  5006.8    0.07       0  5010.8    0.16       0
Bank Sta=5006.8,5010.8
Exp/Cntr=0.3,0.1

Type RM Length L Ch R = 1,2534,91,91,91
BEGIN DESCRIPTION:
Purtis Creek Trib C2534.366
END DESCRIPTION:
XS GIS Cut Line= 3
      2752335.04      6829302.99      2752051.00      6829486.00
      2752006.75      6829841.86
#Sta/Elev= 30
  4662.2  438.71  4703.7  435.13  4761.1  432.68  4812.6  432.81  4885.2  432.01
  4921.5  432.75  4957.8  432.10  4963.8  432.63  5000.1  429.83  5003.1  426.95
  5003.4  426.45  5006.9  426.45  5007.1  426.95  5015.2  428.52  5025.3  429.78
  5035.4  429.75  5045.4  431.27  5080.9  434.17  5116.0  435.42  5146.2  437.56
  5166.8  438.39  5196.6  437.59  5226.8  437.64  5242.6  438.75  5257.1  438.32
  5287.3  438.64  5307.4  439.13  5323.4  440.19  5347.8  441.03  5358.7  441.09
#Mann=3,-1,0
  4662.2    0.16       0  5003.1    0.07       0  5007.1    0.16       0
Bank Sta=5003.1,5007.1
Exp/Cntr=0.3,0.1

Type RM Length L Ch R = 1,2443,150,150,150
BEGIN DESCRIPTION:
Purtis Creek Trib C2442.6
END DESCRIPTION:
XS GIS Cut Line= 3
      2751855.13      6829220.27      2751971.30      6829468.79
      2751975.34      6829833.64
#Sta/Elev= 30
  4726.1  434.62  4741.7  434.06  4781.9  431.20  4826.3  430.97  4848.3  431.65
  4870.4  430.50  4892.5  430.13  4930.0  431.23  4958.7  429.07  4981.2  430.20
  4991.8  427.83  4996.5  425.28  4996.8  424.78  5000.3  424.78  5000.5  425.28
  5022.6  430.49  5042.6  430.17  5062.6  430.63  5092.6  433.13  5122.6  434.52
  5162.7  434.62  5202.7  433.19  5222.7  434.15  5232.7  436.72  5252.7  435.49
  5272.7  436.93  5302.7  436.46  5312.7  437.97  5332.7  439.61  5365.3  440.58
#Mann=3,-1,0
  4726.1    0.16       0  4996.5    0.07       0  5000.5    0.16       0
Bank Sta=4996.5,5000.5
Exp/Cntr=0.3,0.1

Type RM Length L Ch R = 1,2293,194,194,194
BEGIN DESCRIPTION:
Purtis Creek Trib C2293.2
END DESCRIPTION:
XS GIS Cut Line= 3
      2751777.03      6829221.63      2751846.43      6829542.62
      2751901.98      6829790.77
#Sta/Elev= 30
  4673.1  434.40  4713.4  432.52  4733.8  432.18  4754.3  430.62  4788.3  430.86
  4815.7  430.08  4832.4  430.69  4866.8  428.86  4876.6  428.91  4897.5  430.25
  4907.8  429.98  4930.9  427.73  4938.5  429.21  4948.7  429.67  4956.9  422.92
  4957.2  422.42  4960.7  422.42  4960.9  422.92  4969.2  423.68  4975.0  429.28
  4989.6  429.06  4998.1  429.76  5010.1  429.31  5018.8  429.84  5023.9  429.23
  5030.6  430.52  5051.1  432.46  5143.3  436.70  5251.1  442.54  5255.8  441.78
#Mann=3,-1,0
  4673.1    0.16       0  4956.9    0.07       0  4960.9    0.16       0
Bank Sta=4956.9,4960.9
Exp/Cntr=0.3,0.1

Type RM Length L Ch R = 1,2099,203,203,203
BEGIN DESCRIPTION:
Purtis Creek Trib C2099.42
END DESCRIPTION:
XS GIS Cut Line= 3
      2751646.42      6829200.64      2751692.42      6829463.68
      2751764.68      6829767.27
#Sta/Elev= 30
  4735.5  434.83  4806.9  431.68  4816.1  430.78  4847.5  429.41  4857.7  429.28
  4888.1  430.26  4928.7  428.79  4940.1  429.29  4969.4  428.59  4979.5  427.40
  4987.4  420.80  4987.7  420.30  4991.2  420.30  4991.4  420.80  4994.5  420.97
  4998.6  422.69  5010.1  421.88  5020.3  423.39  5030.6  428.34  5037.7  427.85
  5042.8  428.46  5061.5  428.51  5085.0  427.87  5092.3  428.19  5102.6  427.66
  5122.0  428.19  5133.4  429.28  5205.4  432.69  5308.2  439.12  5314.6  439.88
#Mann=3,-1,0
  4735.5    0.16       0  4987.4    0.07       0  4991.4    0.16       0
Bank Sta=4987.4,4991.4
Exp/Cntr=0.3,0.1

Type RM Length L Ch R = 1,1896,216,216,216
BEGIN DESCRIPTION:
Purtis Creek Trib C1895.71
END DESCRIPTION:
XS GIS Cut Line= 3
      2751489.98      6829213.12      2751572.00      6829619.88
      2751636.38      6829844.39
#Sta/Elev= 30
  4588.8  433.29  4643.6  430.68  4648.7  431.17  4678.4  430.45  4719.3  428.49
  4745.2  426.59  4780.5  428.75  4796.0  427.12  4801.1  427.16  4811.1  425.74
  4851.9  428.48  4882.5  427.83  4892.5  428.26  4923.3  427.03  4943.3  427.32
  4953.9  422.00  4972.3  419.74  4972.5  419.24  4976.0  419.24  4976.3  419.74
  4984.5  425.38  4994.1  427.03  5025.7  427.50  5033.7  426.82  5067.3  430.85
  5106.3  433.11  5171.4  435.71  5212.8  436.31  5218.0  437.18  5237.3  437.83
#Mann=3,-1,0
  4588.8    0.16       0  4972.3    0.07       0  4976.3    0.16       0
Bank Sta=4972.3,4976.3
Exp/Cntr=0.3,0.1

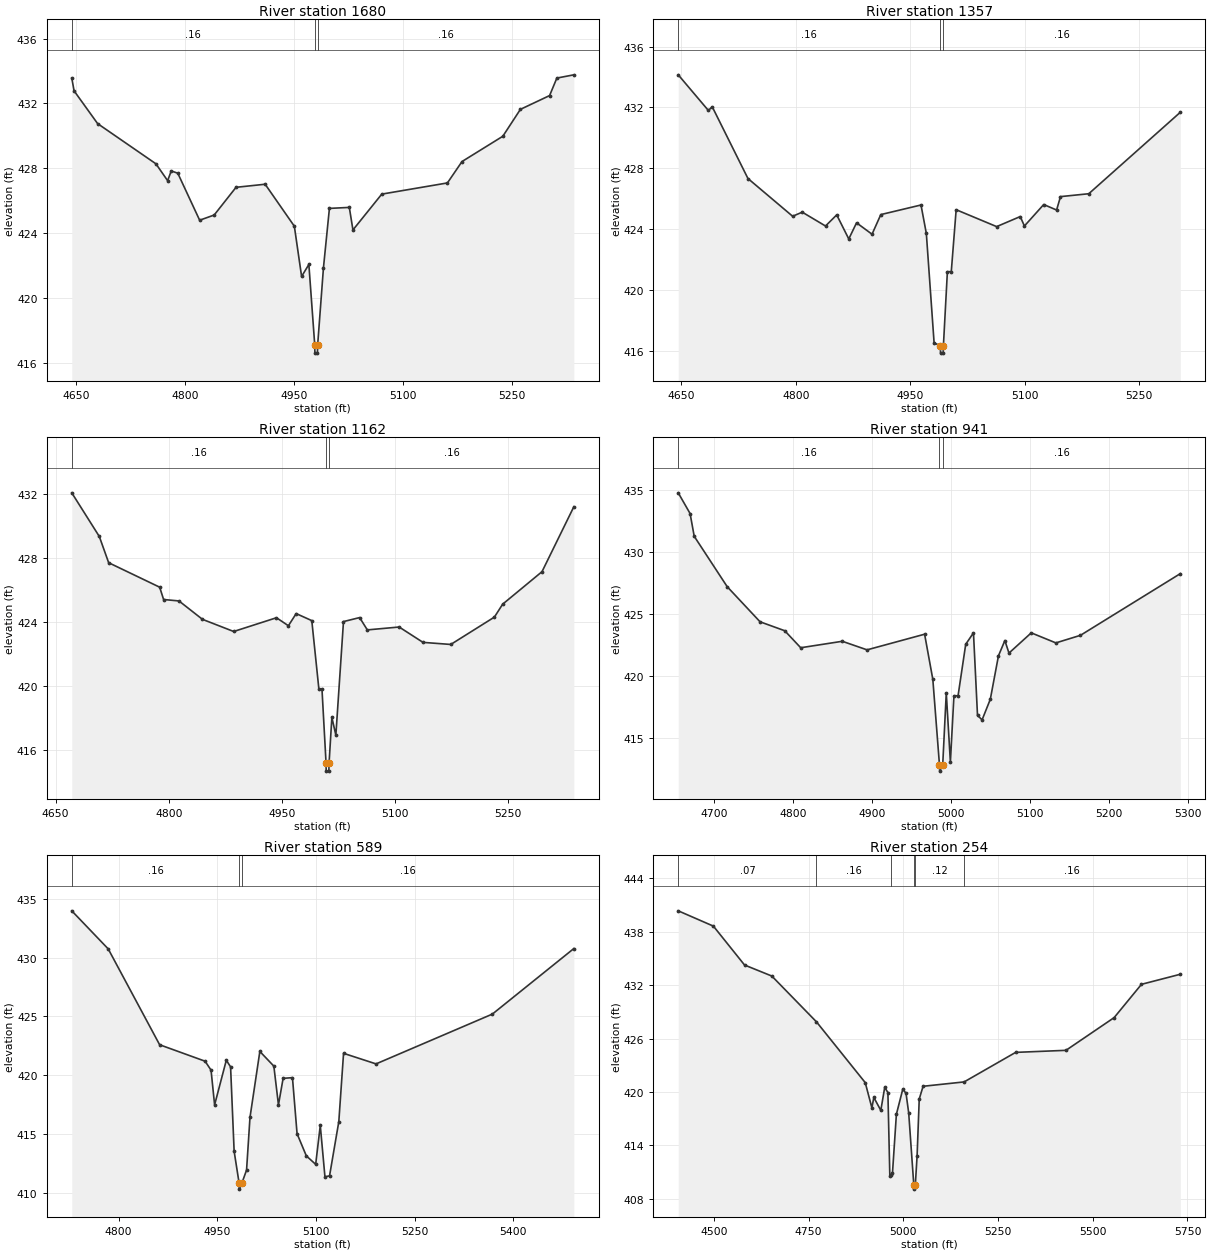
Type RM Length L Ch R = 1,1680,323,323,323
BEGIN DESCRIPTION:
Purtis Creek Trib C1680.16
END DESCRIPTION:
XS GIS Cut Line= 3
      2751360.54      6829255.48      2751388.67      6829612.28
      2751420.15      6829944.29
#Sta/Elev= 30
  4643.5  433.56  4646.7  432.77  4679.1  430.75  4759.4  428.27  4775.5  427.23
  4780.5  427.83  4789.5  427.69  4819.6  424.79  4839.6  425.11  4869.7  426.82
  4909.8  427.01  4950.0  424.42  4960.0  421.32  4970.0  422.06  4978.1  417.09
  4978.3  416.59  4981.8  416.59  4982.1  417.09  4990.1  421.86  4998.3  425.52
  5025.7  425.58  5030.7  424.19  5070.4  426.40  5160.8  427.09  5180.9  428.41
  5237.1  429.97  5261.3  431.63  5301.5  432.48  5311.5  433.56  5334.9  433.76
#Mann=3,-1,0
  4643.5    0.16       0  4978.1    0.07       0  4982.1    0.16       0
Bank Sta=4978.1,4982.1
Exp/Cntr=0.3,0.1

Type RM Length L Ch R = 1,1357,195,195,195
BEGIN DESCRIPTION:
Purtis Creek Trib C1356.95
END DESCRIPTION:
XS GIS Cut Line= 3
      2751123.02      6829351.17      2751188.08      6829700.23
      2751258.12      6829995.26
#Sta/Elev= 30
  4645.9  434.14  4685.4  431.80  4690.5  432.04  4737.3  427.33  4795.9  424.85
  4808.5  425.12  4839.0  424.21  4853.7  424.94  4869.5  423.36  4879.7  424.42
  4900.0  423.67  4911.5  424.96  4964.2  425.59  4971.2  423.72  4981.4  416.52
  4989.6  416.36  4989.8  415.86  4993.3  415.86  4993.6  416.36  4998.8  421.21
  5003.9  421.21  5010.3  425.28  5063.4  424.17  5094.3  424.83  5099.8  424.21
  5125.1  425.62  5142.0  425.26  5147.1  426.14  5184.2  426.33  5304.2  431.68
#Mann=3,-1,0
  4645.9    0.16       0  4989.6    0.07       0  4993.6    0.16       0
Bank Sta=4989.6,4993.6
Exp/Cntr=0.3,0.1

Type RM Length L Ch R = 1,1162,221,221,221
BEGIN DESCRIPTION:
Purtis Creek Trib C1162.08
END DESCRIPTION:
XS GIS Cut Line= 3
      2750910.75      6829393.73      2750996.70      6829714.01
      2751102.95      6830030.43
#Sta/Elev= 30
  4671.4  432.10  4707.9  429.37  4720.3  427.73  4787.9  426.20  4793.1  425.43
  4813.5  425.34  4844.6  424.19  4886.0  423.43  4942.7  424.29  4958.5  423.79
  4968.8  424.55  4989.5  424.11  4998.9  419.83  5003.0  419.83  5008.4  415.20
  5008.6  414.70  5012.1  414.70  5012.4  415.20  5016.1  418.06  5021.4  416.95
  5031.5  424.05  5052.9  424.30  5063.1  423.53  5105.3  423.71  5136.9  422.75
  5173.7  422.62  5231.5  424.33  5242.5  425.14  5294.6  427.17  5336.8  431.23
#Mann=3,-1,0
  4671.4    0.16       0  5008.4    0.07       0  5012.4    0.16       0
Bank Sta=5008.4,5012.4
Exp/Cntr=0.3,0.1

Type RM Length L Ch R = 1,941,352,352,352
BEGIN DESCRIPTION:
Purtis Creek Trib C940.52
END DESCRIPTION:
XS GIS Cut Line= 3
      2750736.87      6829481.55      2750833.47      6829817.23
      2750908.57      6830092.88
#Sta/Elev= 30
  4654.8  434.74  4669.8  433.07  4675.0  431.24  4716.7  427.18  4758.3  424.35
  4789.5  423.63  4809.7  422.26  4862.3  422.78  4893.6  422.09  4966.4  423.35
  4976.8  419.71  4985.2  412.82  4985.5  412.32  4989.3  412.82  4993.8  418.62
  4999.0  413.06  5003.5  418.39  5008.7  418.39  5018.4  422.54  5028.2  423.46
  5033.3  416.81  5039.1  416.45  5049.5  418.11  5059.8  421.61  5067.9  422.84
  5073.1  421.83  5101.3  423.46  5132.4  422.65  5163.5  423.26  5289.8  428.23
#Mann=3,-1,0
  4654.8    0.16       0  4985.2    0.07       0  4989.3    0.16       0
Bank Sta=4985.2,4989.3
Exp/Cntr=0.3,0.1

Type RM Length L Ch R = 1,589,335,335,335
BEGIN DESCRIPTION:
Purtis Creek Trib C589.17
END DESCRIPTION:
XS GIS Cut Line= 3
      2750441.24      6829542.66      2750542.03      6829795.73
      2750885.13      6830147.10
#Sta/Elev= 30
  4728.7  433.98  4784.1  430.74  4862.3  422.58  4931.4  421.18  4940.5  420.42
  4945.9  417.46  4963.7  421.26  4970.2  420.70  4975.6  413.52  4983.2  410.79
  4983.4  410.29  4987.3  410.79  4994.5  411.91  4999.7  416.39  5014.7  422.01
  5036.0  420.76  5043.0  417.46  5050.1  419.72  5064.3  419.78  5071.3  415.01
  5085.4  413.12  5099.6  412.40  5106.6  415.71  5113.7  411.34  5120.7  411.42
  5134.8  416.04  5142.0  421.85  5191.4  420.95  5368.3  425.19  5492.2  430.77
#Mann=3,-1,0
  4728.7    0.16       0  4983.2    0.07       0  4987.3    0.16       0
Bank Sta=4983.2,4987.3
Exp/Cntr=0.3,0.1

Type RM Length L Ch R = 1,254,0,0,0
BEGIN DESCRIPTION:
Purtis Creek Trib C254.486
END DESCRIPTION:
XS GIS Cut Line= 3
      2750162.72      6829310.68      2750299.64      6829888.78
      2750949.02      6830224.66
#Sta/Elev= 30
  4405.9  440.36  4498.7  438.64  4580.9  434.27  4652.9  433.03  4770.8  427.88
  4899.5  421.05  4917.0  418.22  4922.2  419.38  4940.6  417.93  4950.9  420.52
  4959.3  419.94  4964.4  410.56  4966.4  410.65  4971.4  410.89  4981.7  417.49
  4998.6  420.32  5007.2  419.84  5014.2  417.64  5027.6  409.58  5027.9  409.08
  5031.7  409.58  5036.4  412.85  5042.0  419.21  5052.2  420.64  5160.5  421.13
  5296.5  424.45  5429.3  424.68  5556.5  428.36  5628.6  432.10  5731.1  433.23
#Mann=6,-1,0
  4405.9    0.07       0  4770.8    0.16       0  4966.4    0.12       0
  5027.6    0.07       0  5031.7    0.12       0  5160.5    0.16       0
Bank Sta=5027.6,5031.7
Exp/Cntr=0.3,0.1

Chan Stop Cuts=-1