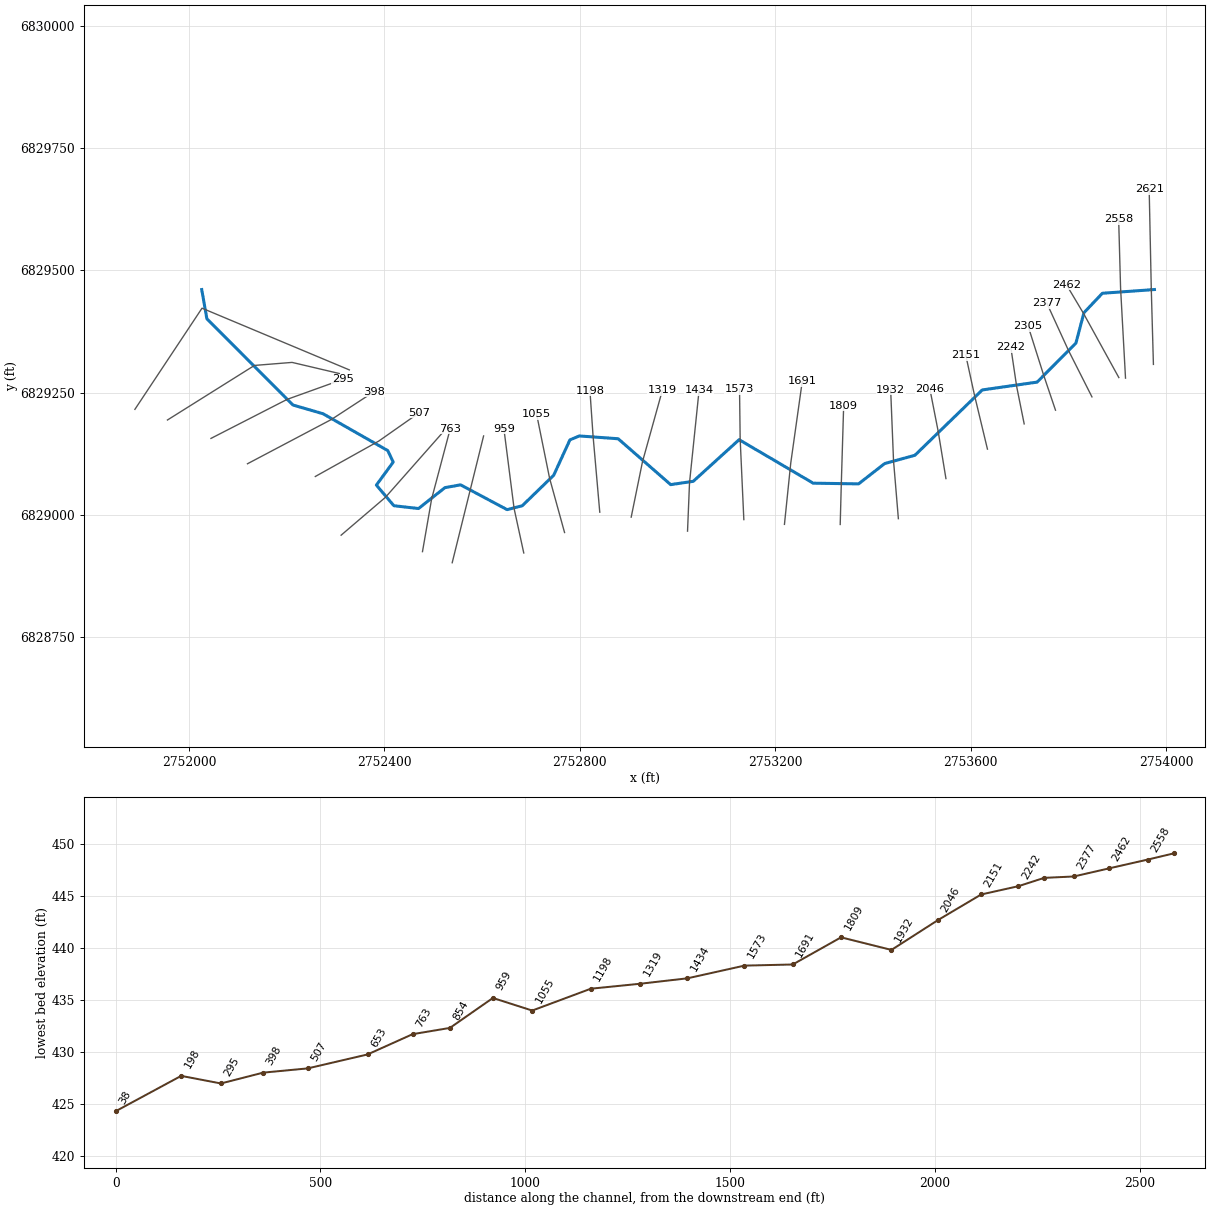
--- Purtis Creek Trib C1.prj (project) ---

Proj Title=Purtis Creek Trib C1 Base Level Engineering
Current Plan=p01
Default Exp/Contr=0.3,0.1
English Units
Geom File=g01
Flow File=f01
Plan File=p01
BEGIN DESCRIPTION:
Purtis Creek Trib C1
END DESCRIPTION:

--- Purtis Creek Trib C1.p01 (plan) ---

Plan Title=Multiple Run
Short Identifier=Multiple
Geom File=g01
Flow File=f01
Subcritical Flow
K Sum by GR= 0
Std Step Tol= 0.01
Critical Tol= 0.01
Num of Std Step Trials= 20
Max Error Tol= 0.3
Flow Tol Ratio= 0.001
Split Flow NTrial= 30
Split Flow Tol= 0.02
Split Flow Ratio= 0.02
Log Output Level= 0
Friction Slope Method= 1
Unsteady Friction Slope Method= 2
Unsteady Bridges Friction Slope Method= 1
Parabolic Critical Depth
Global Vel Dist=  1 , 1 , 1
Global Log Level= 0
CheckData=True
Encroach Param= -1, 0, 0, 0
BEGIN DESCRIPTION:
Multiple Run
END DESCRIPTION:

--- Purtis Creek Trib C1.f01 (steady flow) ---

Flow Title=Multiple
Number of Profiles=7
Profile Names=10-year,25-year,50-year,1pct_min,100-year,1pct_plu,500-year
River Rch & RM= Purtis Creek Tri,Reach-1,2621
     168     209     239     137     274     547     358
Boundary for River Rch & Prof#=Purtis Creek Tri,Reach-1,1
Up Type=0
Dn Type=3
Dn Slope=0.005
Boundary for River Rch & Prof#=Purtis Creek Tri,Reach-1,2
Up Type=0
Dn Type=3
Dn Slope=0.005
Boundary for River Rch & Prof#=Purtis Creek Tri,Reach-1,3
Up Type=0
Dn Type=3
Dn Slope=0.005
Boundary for River Rch & Prof#=Purtis Creek Tri,Reach-1,4
Up Type=0
Dn Type=3
Dn Slope=0.005
Boundary for River Rch & Prof#=Purtis Creek Tri,Reach-1,5
Up Type=0
Dn Type=3
Dn Slope=0.005
Boundary for River Rch & Prof#=Purtis Creek Tri,Reach-1,6
Up Type=0
Dn Type=3
Dn Slope=0.005
Boundary for River Rch & Prof#=Purtis Creek Tri,Reach-1,7
Up Type=0
Dn Type=3
Dn Slope=0.005

--- Purtis Creek Trib C1.g01 (geometry) ---

Geom Title=Existing Conditions

River Reach=Purtis Creek Tri,Reach-1
Reach XY= 30
      2753976.00      6829461.00      2753869.45      6829453.40
      2753831.73      6829413.57      2753815.23      6829351.31
      2753735.81      6829271.51      2753623.57      6829255.48
      2753485.68      6829121.76      2753423.83      6829104.85
      2753370.44      6829063.26      2753277.58      6829064.67
      2753125.92      6829153.70      2753032.05      6829068.50
      2752985.80      6829061.72      2752878.36      6829155.61
      2752798.76      6829161.38      2752779.57      6829153.25
      2752746.37      6829080.86      2752682.07      6829018.48
      2752651.04      6829010.51      2752555.82      6829061.26
      2752523.80      6829055.58      2752469.80      6829012.81
      2752419.32      6829018.48      2752383.48      6829060.74
      2752417.91      6829107.83      2752406.79      6829131.39
      2752274.27      6829206.81      2752212.79      6829224.62
      2752036.51      6829401.21      2752026.00      6829461.00

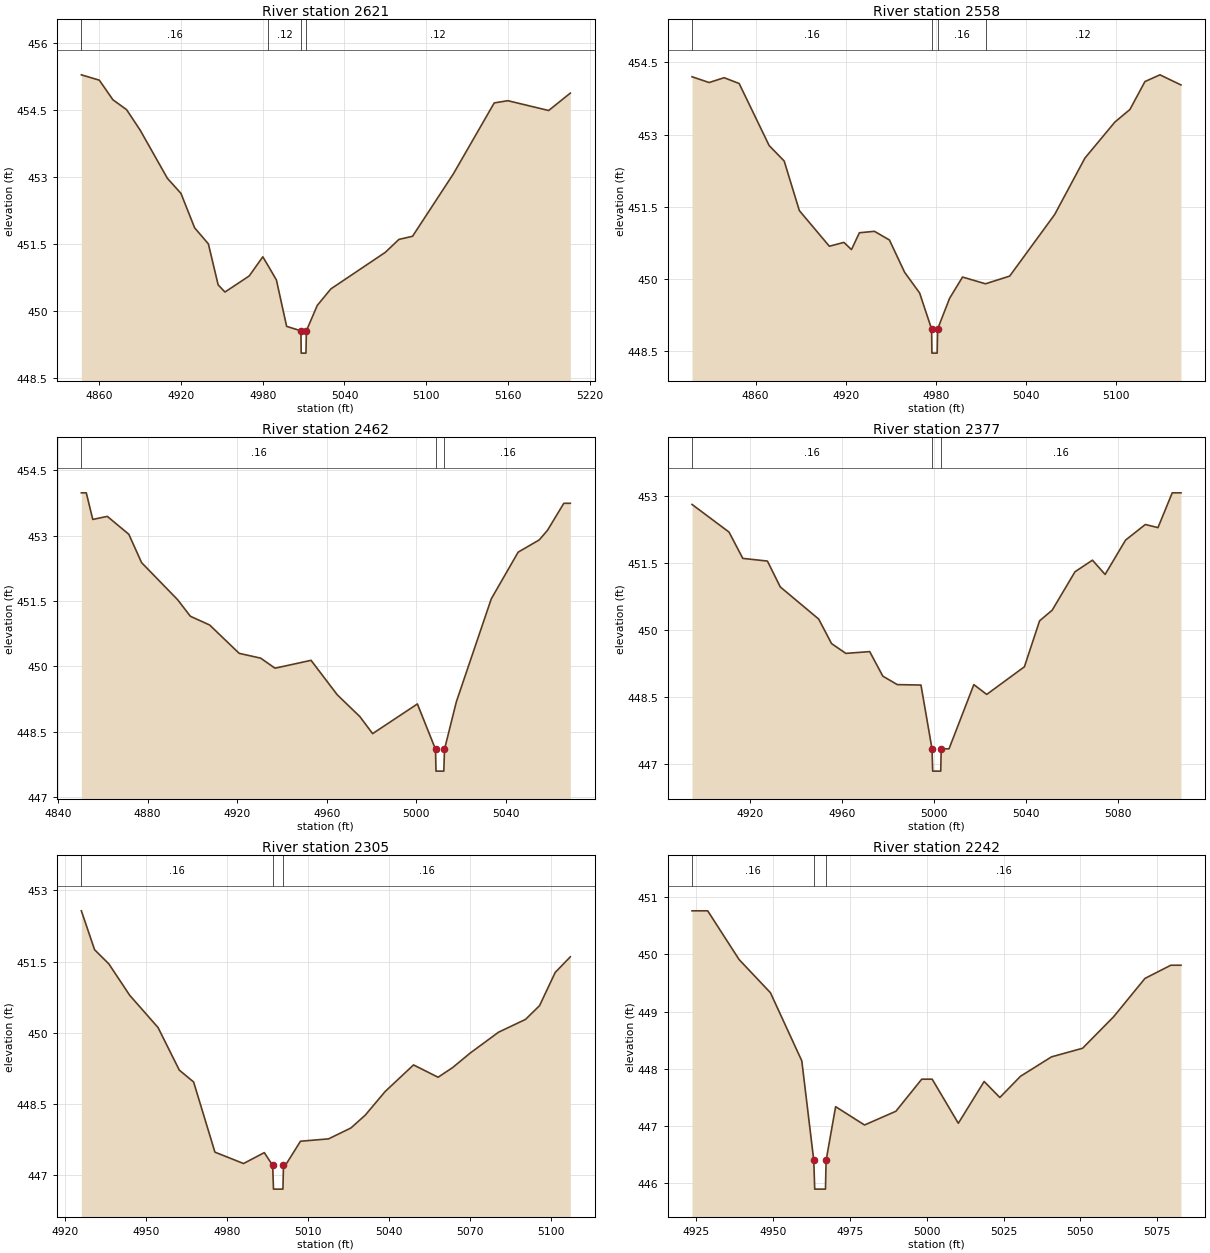
Type RM Length L Ch R = 1,2621,63,63,63
BEGIN DESCRIPTION:
Purtis Creek Trib C12621.133
END DESCRIPTION:
XS GIS Cut Line= 3
      2753973.91      6829307.79      2753969.57      6829461.02
      2753965.21      6829666.88
#Sta/Elev= 30
  4846.7  455.29  4859.9  455.17  4869.9  454.73  4879.9  454.51  4889.9  454.05
  4909.9  452.97  4919.9  452.63  4929.9  451.86  4940.0  451.50  4947.2  450.58
  4952.2  450.42  4970.0  450.78  4980.0  451.21  4983.9  451.01  4990.0  450.69
  4997.5  449.65  5008.0  449.55  5008.2  449.05  5011.7  449.05  5012.0  449.55
  5020.0  450.12  5030.0  450.49  5070.0  451.31  5080.0  451.60  5090.0  451.67
  5120.0  453.07  5150.0  454.66  5160.0  454.71  5190.0  454.49  5205.9  454.88
#Mann=4,-1,0
  4846.7    0.16       0  4983.9    0.12       0  5008.0    0.07       0
  5012.0    0.12       0
Bank Sta=5008,5012
Exp/Cntr=0.3,0.1

Type RM Length L Ch R = 1,2558,96,96,96
BEGIN DESCRIPTION:
Purtis Creek Trib C12558.36
END DESCRIPTION:
XS GIS Cut Line= 3
      2753916.80      6829279.66      2753906.73      6829463.10
      2753902.75      6829605.02
#Sta/Elev= 30
  4817.6  454.20  4829.0  454.08  4839.0  454.18  4849.0  454.06  4869.0  452.77
  4879.0  452.45  4889.1  451.42  4909.1  450.68  4918.8  450.76  4923.8  450.61
  4929.1  450.96  4939.1  450.99  4949.1  450.81  4959.2  450.14  4969.2  449.71
  4977.2  448.96  4977.4  448.46  4980.9  448.46  4981.2  448.96  4989.2  449.60
  4997.8  450.04  5013.1  449.90  5029.2  450.06  5059.2  451.34  5079.3  452.51
  5099.3  453.26  5109.3  453.52  5119.3  454.10  5129.3  454.24  5143.3  454.03
#Mann=4,-1,0
  4817.6    0.16       0  4977.2    0.07       0  4981.2    0.16       0
  5013.1    0.12       0
Bank Sta=4977.2,4981.2
Exp/Cntr=0.3,0.1

Type RM Length L Ch R = 1,2462,85,85,85
BEGIN DESCRIPTION:
Purtis Creek Trib C12462.43
END DESCRIPTION:
XS GIS Cut Line= 3
      2753903.11      6829280.85      2753830.40      6829412.89
      2753795.76      6829471.02
#Sta/Elev= 28
  4850.4  453.98  4852.6  453.98  4855.5  453.37  4862.0  453.44  4871.6  453.03
  4877.3  452.38  4893.4  451.53  4899.1  451.15  4907.7  450.95  4920.9  450.30
  4930.5  450.19  4936.9  449.96  4953.0  450.14  4964.7  449.35  4974.8  448.85
  4980.5  448.46  5000.5  449.14  5008.6  448.10  5008.8  447.60  5012.3  447.60
  5012.6  448.10  5017.9  449.19  5033.5  451.55  5045.5  452.62  5054.9  452.90
  5058.6  453.12  5065.9  453.74  5068.8  453.74
#Mann=3,-1,0
  4850.4    0.16       0  5008.6    0.07       0  5012.6    0.16       0
Bank Sta=5008.6,5012.6
Exp/Cntr=0.3,0.1

Type RM Length L Ch R = 1,2377,72,72,72
BEGIN DESCRIPTION:
Purtis Creek Trib C12377.05
END DESCRIPTION:
XS GIS Cut Line= 3
      2753848.09      6829241.31      2753800.07      6829336.30
      2753755.84      6829432.92
#Sta/Elev= 30
  4894.9  452.81  4911.0  452.19  4917.0  451.60  4927.7  451.54  4933.3  450.96
  4950.0  450.24  4955.6  449.69  4961.8  449.47  4972.2  449.51  4977.9  448.96
  4984.2  448.77  4994.5  448.76  4999.3  447.33  4999.6  446.83  5003.1  446.83
  5003.3  447.33  5006.7  447.33  5017.5  448.77  5023.1  448.55  5039.5  449.17
  5046.1  450.20  5051.6  450.44  5061.5  451.30  5069.1  451.56  5074.6  451.24
  5083.5  452.01  5092.1  452.36  5097.6  452.29  5103.8  453.07  5107.6  453.07
#Mann=3,-1,0
  4894.9    0.16       0  4999.3    0.07       0  5003.3    0.16       0
Bank Sta=4999.3,5003.3
Exp/Cntr=0.3,0.1

Type RM Length L Ch R = 1,2305,63,63,63
BEGIN DESCRIPTION:
Purtis Creek Trib C12305.03
END DESCRIPTION:
XS GIS Cut Line= 3
      2753773.49      6829214.09      2753749.27      6829285.72
      2753717.40      6829386.38
#Sta/Elev= 29
  4926.1  452.57  4931.0  451.75  4936.3  451.45  4944.0  450.79  4954.5  450.11
  4962.4  449.21  4967.7  448.96  4975.6  447.48  4986.2  447.24  4993.9  447.47
  4997.0  447.20  4997.3  446.70  5000.8  446.70  5001.0  447.20  5001.7  447.20
  5007.3  447.71  5017.7  447.76  5026.0  447.99  5031.3  448.26  5038.7  448.76
  5049.2  449.32  5058.3  449.06  5063.6  449.26  5070.2  449.57  5080.7  450.01
  5090.7  450.28  5095.9  450.57  5101.7  451.27  5107.3  451.60
#Mann=3,-1,0
  4926.1    0.16       0  4997.0    0.07       0  5001.0    0.16       0
Bank Sta=4997,5001
Exp/Cntr=0.3,0.1

Type RM Length L Ch R = 1,2242,91,91,91
BEGIN DESCRIPTION:
Purtis Creek Trib C12242.34
END DESCRIPTION:
XS GIS Cut Line= 3
      2753709.38      6829186.03      2753693.99      6829262.59
      2753682.07      6829342.62
#Sta/Elev= 24
  4923.7  450.76  4928.8  450.76  4939.0  449.91  4949.2  449.33  4959.4  448.14
  4963.3  446.40  4963.6  445.90  4967.1  445.90  4967.3  446.40  4970.4  447.34
  4979.8  447.02  4990.0  447.26  4998.4  447.82  5001.8  447.82  5010.3  447.05
  5018.7  447.78  5023.8  447.50  5030.5  447.87  5040.6  448.21  5050.7  448.36
  5060.8  448.91  5071.0  449.58  5079.4  449.81  5082.7  449.81
#Mann=3,-1,0
  4923.7    0.16       0  4963.3    0.07       0  4967.3    0.16       0
Bank Sta=4963.3,4967.3
Exp/Cntr=0.3,0.1

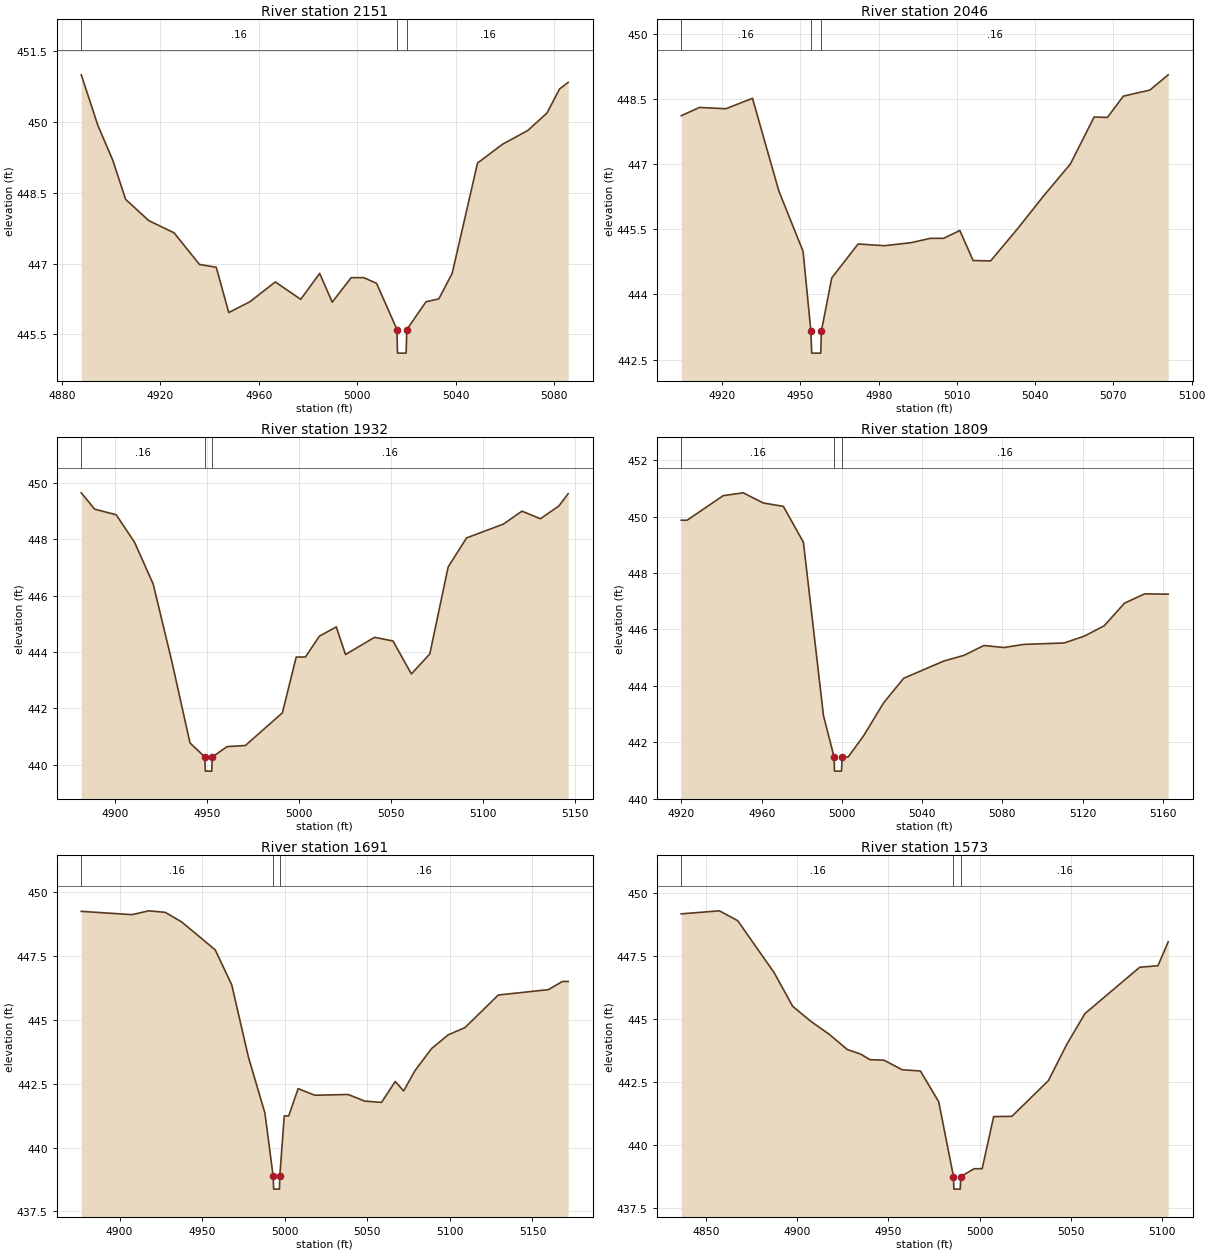
Type RM Length L Ch R = 1,2151,105,105,105
BEGIN DESCRIPTION:
Purtis Creek Trib C12150.96
END DESCRIPTION:
XS GIS Cut Line= 3
      2753634.20      6829134.37      2753607.40      6829245.95
      2753589.74      6829327.00
#Sta/Elev= 30
  4887.9  451.00  4894.7  449.92  4900.7  449.19  4905.9  448.36  4915.3  447.91
  4925.6  447.65  4935.9  446.98  4942.7  446.92  4947.8  445.96  4956.4  446.19
  4966.7  446.61  4977.0  446.24  4984.7  446.79  4989.8  446.18  4997.5  446.70
  5002.6  446.70  5007.8  446.58  5016.1  445.60  5016.3  445.10  5019.8  445.10
  5020.1  445.60  5027.9  446.19  5033.1  446.25  5038.5  446.79  5048.8  449.13
  5059.0  449.53  5069.2  449.82  5077.0  450.19  5082.1  450.70  5085.6  450.84
#Mann=3,-1,0
  4887.9    0.16       0  5016.1    0.07       0  5020.1    0.16       0
Bank Sta=5016.1,5020.1
Exp/Cntr=0.3,0.1

Type RM Length L Ch R = 1,2046,114,114,114
BEGIN DESCRIPTION:
Purtis Creek Trib C12045.51
END DESCRIPTION:
XS GIS Cut Line= 3
      2753549.24      6829074.09      2753533.38      6829170.68
      2753516.30      6829257.84
#Sta/Elev= 28
  4904.3  448.11  4911.3  448.30  4921.4  448.27  4931.6  448.51  4941.7  446.38
  4951.0  444.99  4954.0  443.15  4954.3  442.65  4957.8  442.65  4958.0  443.15
  4962.0  444.38  4972.1  445.16  4982.2  445.12  4992.4  445.19  4999.8  445.29
  5002.2  445.29  5004.9  445.29  5011.1  445.47  5016.2  444.78  5022.9  444.77
  5033.1  445.50  5043.3  446.27  5053.5  447.00  5062.6  448.08  5067.7  448.07
  5073.8  448.56  5084.0  448.70  5091.0  449.05
#Mann=3,-1,0
  4904.3    0.16       0  4954.0    0.07       0  4958.0    0.16       0
Bank Sta=4954,4958
Exp/Cntr=0.3,0.1

Type RM Length L Ch R = 1,1932,123,123,123
BEGIN DESCRIPTION:
Purtis Creek Trib C11932.36
END DESCRIPTION:
XS GIS Cut Line= 3
      2753451.88      6828992.06      2753441.95      6829110.97
      2753436.09      6829256.13
#Sta/Elev= 30
  4881.6  449.65  4888.9  449.07  4900.6  448.87  4910.6  447.89  4920.7  446.41
  4930.7  443.70  4940.7  440.77  4948.8  440.27  4949.0  439.77  4952.5  439.77
  4952.8  440.27  4960.8  440.64  4970.8  440.68  4990.9  441.84  4998.4  443.82
  5003.4  443.82  5011.0  444.56  5020.2  444.89  5025.2  443.91  5041.0  444.52
  5051.0  444.39  5061.0  443.22  5071.0  443.93  5081.0  447.02  5091.0  448.05
  5111.0  448.54  5121.1  449.00  5131.1  448.73  5141.1  449.18  5146.2  449.62
#Mann=3,-1,0
  4881.6    0.16       0  4948.8    0.07       0  4952.8    0.16       0
Bank Sta=4948.8,4952.8
Exp/Cntr=0.3,0.1

Type RM Length L Ch R = 1,1809,118,118,118
BEGIN DESCRIPTION:
Purtis Creek Trib C11809.47
END DESCRIPTION:
XS GIS Cut Line= 3
      2753332.83      6828980.14      2753335.00      6829060.59
      2753339.90      6829222.84
#Sta/Elev= 27
  4919.9  449.87  4922.8  449.87  4940.8  450.74  4950.8  450.84  4960.8  450.48
  4970.8  450.36  4980.8  449.09  4990.8  442.95  4996.1  441.48  4996.3  440.98
  4999.8  440.98  5000.1  441.48  5003.1  441.48  5010.8  442.23  5020.8  443.40
  5030.8  444.27  5050.8  444.88  5060.8  445.08  5070.8  445.43  5080.8  445.36
  5090.8  445.47  5110.8  445.52  5120.8  445.76  5130.8  446.13  5140.9  446.93
  5150.9  447.26  5162.7  447.25
#Mann=3,-1,0
  4919.9    0.16       0  4996.1    0.07       0  5000.1    0.16       0
Bank Sta=4996.1,5000.1
Exp/Cntr=0.3,0.1

Type RM Length L Ch R = 1,1691,118,118,118
BEGIN DESCRIPTION:
Purtis Creek Trib C11691.33
END DESCRIPTION:
XS GIS Cut Line= 3
      2753218.71      6828980.37      2753231.55      6829105.33
      2753255.13      6829272.86
#Sta/Elev= 30
  4876.8  449.26  4907.6  449.13  4917.6  449.28  4927.7  449.22  4937.7  448.84
  4957.9  447.75  4967.9  446.38  4978.0  443.55  4988.0  441.35  4993.0  438.87
  4993.3  438.37  4996.8  438.37  4997.0  438.87  4999.7  441.24  5002.4  441.24
  5008.1  442.31  5018.2  442.05  5038.4  442.08  5048.5  441.82  5058.6  441.77
  5066.9  442.59  5072.0  442.22  5078.8  443.01  5088.9  443.88  5099.0  444.42
  5109.1  444.70  5129.3  445.98  5159.6  446.19  5168.1  446.51  5171.6  446.51
#Mann=3,-1,0
  4876.8    0.16       0  4993.0    0.07       0  4997.0    0.16       0
Bank Sta=4993,4997
Exp/Cntr=0.3,0.1

Type RM Length L Ch R = 1,1573,139,139,139
BEGIN DESCRIPTION:
Purtis Creek Trib C11572.82
END DESCRIPTION:
XS GIS Cut Line= 3
      2753135.58      6828990.10      2753128.07      6829154.78
      2753126.77      6829256.63
#Sta/Elev= 28
  4836.6  449.19  4857.5  449.31  4867.5  448.92  4887.5  446.85  4897.6  445.52
  4907.6  444.92  4917.6  444.41  4927.6  443.80  4934.9  443.62  4939.9  443.40
  4947.6  443.38  4957.6  443.00  4967.6  442.95  4977.6  441.73  4985.7  438.76
  4985.9  438.26  4989.4  438.26  4989.7  438.76  4997.0  439.07  5001.4  439.07
  5007.7  441.14  5017.7  441.15  5037.7  442.57  5047.7  444.00  5057.7  445.23
  5087.7  447.07  5097.7  447.13  5103.3  448.08
#Mann=3,-1,0
  4836.6    0.16       0  4985.7    0.07       0  4989.7    0.16       0
Bank Sta=4985.7,4989.7
Exp/Cntr=0.3,0.1

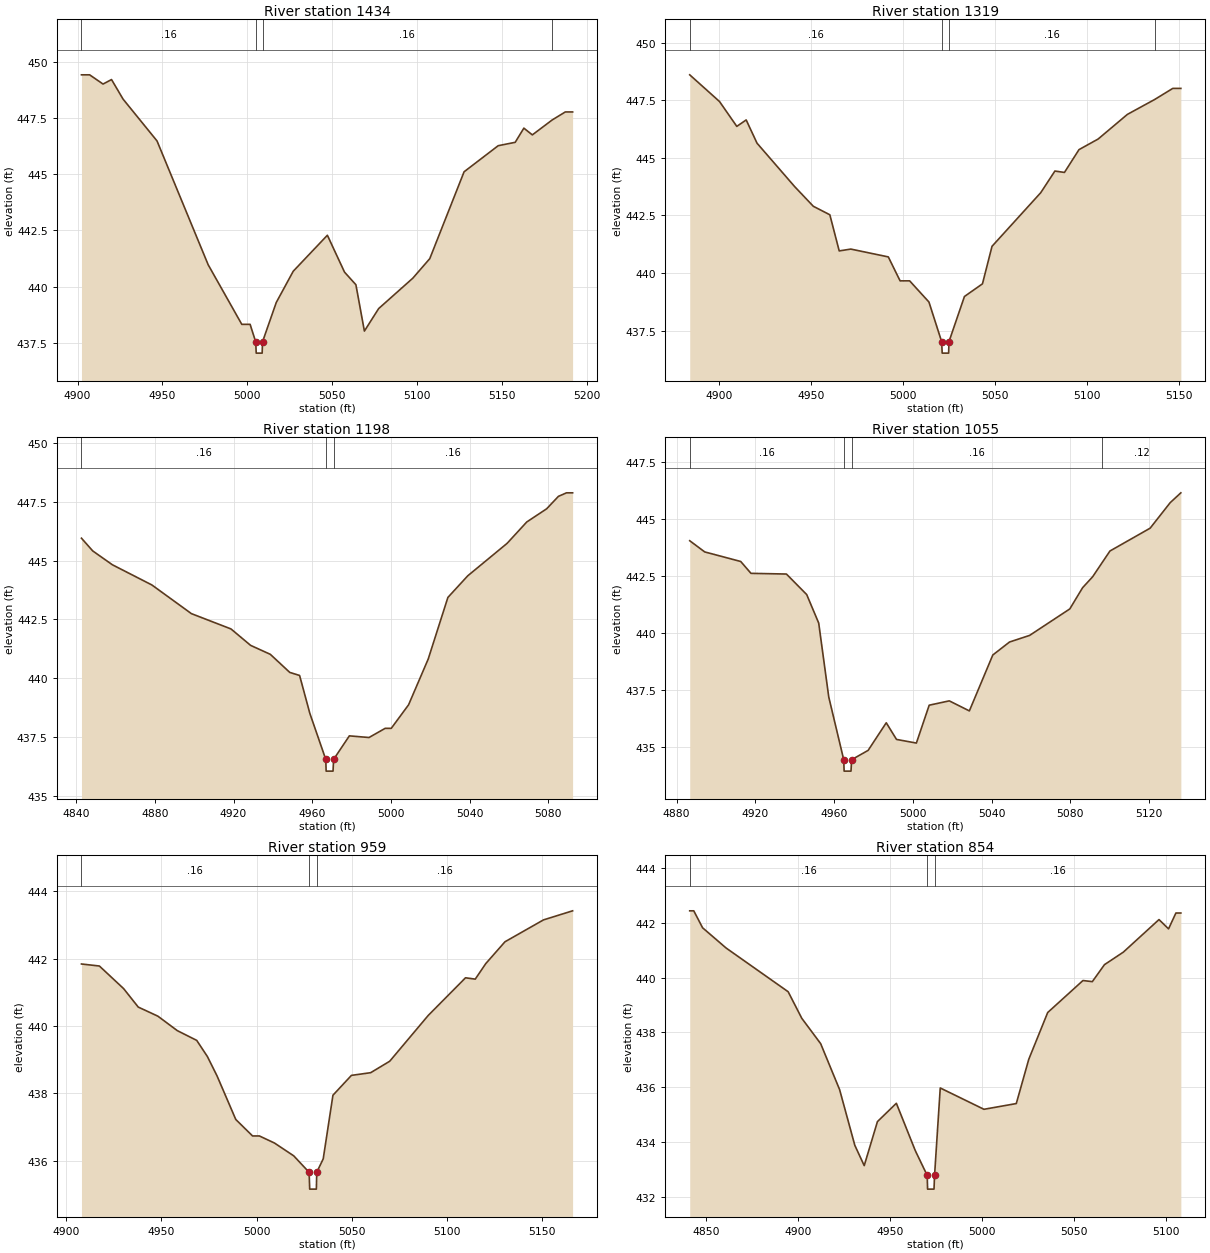
Type RM Length L Ch R = 1,1434,115,115,115
BEGIN DESCRIPTION:
Purtis Creek Trib C11433.86
END DESCRIPTION:
XS GIS Cut Line= 3
      2753020.34      6828966.50      2753024.41      6829065.68
      2753043.95      6829254.61
#Sta/Elev= 30
  4902.3  449.41  4907.1  449.41  4915.0  449.00  4920.0  449.20  4926.8  448.33
  4946.8  446.47  4976.9  440.97  4996.7  438.32  5001.6  438.32  5004.9  437.54
  5005.2  437.04  5008.7  437.04  5008.9  437.54  5017.0  439.29  5027.0  440.68
  5047.1  442.28  5057.2  440.64  5063.9  440.08  5068.9  438.02  5077.3  439.02
  5097.4  440.37  5107.4  441.24  5127.6  445.10  5147.7  446.26  5157.7  446.41
  5162.8  447.04  5167.8  446.74  5179.4  447.40  5187.2  447.76  5191.5  447.76
#Mann=4,-1,0
  4902.3    0.16       0  5004.9    0.07       0  5008.9    0.16       0
  5179.4    0.12       0
Bank Sta=5004.9,5008.9
Exp/Cntr=0.3,0.1

Type RM Length L Ch R = 1,1319,121,121,121
BEGIN DESCRIPTION:
Purtis Creek Trib C11319.36
END DESCRIPTION:
XS GIS Cut Line= 3
      2752905.03      6828995.15      2752928.14      6829108.59
      2752968.71      6829254.38
#Sta/Elev= 30
  4884.1  448.61  4900.3  447.45  4909.7  446.37  4914.8  446.65  4920.7  445.64
  4941.1  443.76  4951.3  442.90  4960.3  442.53  4965.4  440.96  4971.7  441.04
  4992.1  440.70  4998.5  439.66  5003.7  439.66  5014.2  438.74  5021.1  437.02
  5021.4  436.52  5024.9  436.52  5025.1  437.02  5033.5  438.98  5043.3  439.53
  5048.5  441.16  5075.0  443.49  5082.7  444.43  5087.9  444.37  5095.8  445.36
  5106.2  445.82  5122.1  446.89  5137.0  447.54  5146.8  448.02  5151.2  448.02
#Mann=4,-1,0
  4884.1    0.16       0  5021.1    0.07       0  5025.1    0.16       0
  5137.0    0.12       0
Bank Sta=5021.1,5025.1
Exp/Cntr=0.3,0.1

Type RM Length L Ch R = 1,1198,143,143,143
BEGIN DESCRIPTION:
Purtis Creek Trib C11198.44
END DESCRIPTION:
XS GIS Cut Line= 3
      2752840.70      6829005.32      2752826.91      6829162.25
      2752820.57      6829254.20
#Sta/Elev= 29
  4842.7  445.95  4848.4  445.41  4858.4  444.82  4878.5  443.96  4898.6  442.74
  4918.7  442.09  4928.7  441.39  4938.7  441.01  4948.6  440.24  4953.6  440.11
  4958.8  438.50  4966.9  436.54  4967.1  436.04  4970.6  436.04  4970.9  436.54
  4978.9  437.54  4988.9  437.47  4997.1  437.86  5000.2  437.86  5009.0  438.86
  5019.0  440.81  5029.0  443.43  5039.1  444.35  5059.1  445.73  5069.1  446.64
  5079.2  447.20  5085.2  447.73  5089.3  447.88  5092.4  447.88
#Mann=3,-1,0
  4842.7    0.16       0  4966.9    0.07       0  4970.9    0.16       0
Bank Sta=4966.9,4970.9
Exp/Cntr=0.3,0.1

Type RM Length L Ch R = 1,1055,96,96,96
BEGIN DESCRIPTION:
Purtis Creek Trib C11054.94
END DESCRIPTION:
XS GIS Cut Line= 3
      2752768.62      6828963.70      2752738.02      6829074.64
      2752711.36      6829206.28
#Sta/Elev= 30
  4886.7  444.04  4894.3  443.55  4912.6  443.13  4917.8  442.61  4935.8  442.58
  4946.1  441.68  4952.2  440.43  4957.3  437.19  4964.9  434.44  4965.1  433.94
  4968.6  433.94  4968.9  434.44  4977.3  434.85  4986.5  436.06  4991.7  435.33
  5001.8  435.17  5008.3  436.83  5018.5  437.02  5028.7  436.58  5040.6  439.03
  5049.1  439.60  5059.3  439.89  5079.7  441.05  5086.2  441.98  5091.3  442.46
  5096.2  443.09  5100.1  443.59  5120.5  444.59  5130.7  445.71  5136.1  446.14
#Mann=4,-1,0
  4886.7    0.16       0  4964.9    0.07       0  4968.9    0.16       0
  5096.2    0.12       0
Bank Sta=4964.9,4968.9
Exp/Cntr=0.3,0.1

Type RM Length L Ch R = 1,959,105,105,105
BEGIN DESCRIPTION:
Purtis Creek Trib C1958.5
END DESCRIPTION:
XS GIS Cut Line= 3
      2752685.13      6828921.85      2752665.29      6829013.13
      2752644.46      6829176.19
#Sta/Elev= 30
  4908.1  441.84  4917.5  441.78  4930.2  441.11  4937.9  440.56  4948.2  440.29
  4958.4  439.86  4968.6  439.57  4974.2  439.09  4979.3  438.51  4989.1  437.22
  4997.9  436.73  5001.5  436.73  5009.4  436.52  5019.5  436.14  5027.6  435.65
  5027.9  435.15  5031.4  435.15  5031.6  435.65  5035.0  436.05  5040.1  437.94
  5049.8  438.53  5059.9  438.61  5069.9  438.95  5090.1  440.31  5109.7  441.43
  5114.8  441.39  5120.3  441.85  5130.4  442.50  5150.6  443.15  5165.9  443.42
#Mann=3,-1,0
  4908.1    0.16       0  5027.6    0.07       0  5031.6    0.16       0
Bank Sta=5027.6,5031.6
Exp/Cntr=0.3,0.1

Type RM Length L Ch R = 1,854,91,91,91
BEGIN DESCRIPTION:
Purtis Creek Trib C1853.94
END DESCRIPTION:
XS GIS Cut Line= 3
      2752538.65      6828901.82      2752577.48      6829058.63
      2752602.91      6829161.38
#Sta/Elev= 30
  4840.9  442.45  4843.1  442.45  4847.9  441.83  4860.7  441.09  4894.5  439.49
  4901.9  438.52  4912.2  437.59  4922.5  435.91  4930.8  433.87  4935.9  433.13
  4943.1  434.74  4953.4  435.41  4963.7  433.68  4970.2  432.77  4970.4  432.27
  4973.9  432.27  4974.2  432.77  4977.3  435.97  5001.1  435.19  5018.7  435.40
  5025.5  437.02  5035.8  438.73  5055.0  439.90  5060.1  439.86  5066.7  440.48
  5077.0  440.94  5096.4  442.13  5101.6  441.79  5105.6  442.37  5108.3  442.37
#Mann=3,-1,0
  4840.9    0.16       0  4970.2    0.07       0  4974.2    0.16       0
Bank Sta=4970.2,4974.2
Exp/Cntr=0.3,0.1

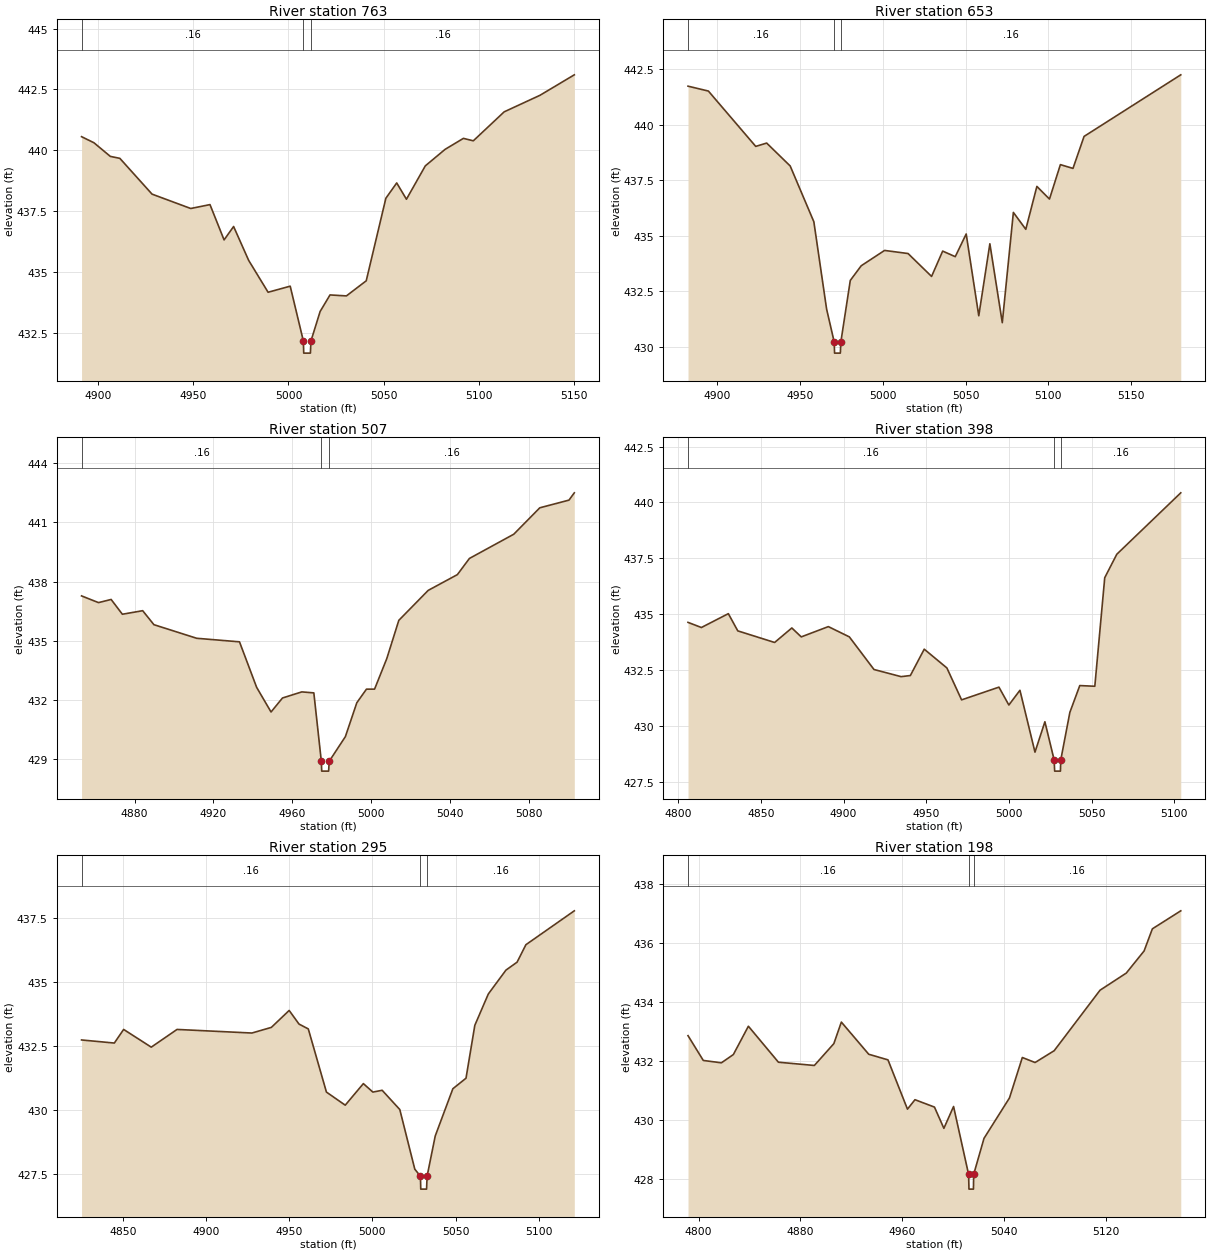
Type RM Length L Ch R = 1,763,110,110,110
BEGIN DESCRIPTION:
Purtis Creek Trib C1762.61
END DESCRIPTION:
XS GIS Cut Line= 3
      2752477.84      6828924.56      2752496.55      6829032.43
      2752534.79      6829176.56
#Sta/Elev= 30
  4891.4  440.56  4897.9  440.31  4906.5  439.75  4911.5  439.67  4928.4  438.20
  4948.7  437.61  4958.8  437.77  4966.2  436.32  4971.2  436.87  4979.1  435.48
  4989.3  434.17  5000.9  434.42  5007.8  432.17  5008.0  431.67  5011.5  431.67
  5011.8  432.17  5016.6  433.38  5021.8  434.06  5030.4  434.02  5040.8  434.64
  5051.1  438.03  5056.8  438.66  5061.9  437.99  5071.8  439.36  5082.2  440.04
  5091.8  440.49  5097.0  440.39  5113.2  441.58  5132.0  442.26  5150.0  443.10
#Mann=3,-1,0
  4891.4    0.16       0  5007.8    0.07       0  5011.8    0.16       0
Bank Sta=5007.8,5011.8
Exp/Cntr=0.3,0.1

Type RM Length L Ch R = 1,653,146,146,146
BEGIN DESCRIPTION:
Purtis Creek Trib C1652.83
END DESCRIPTION:
XS GIS Cut Line= 3
      2752311.32      6828958.24      2752402.04      6829035.77
      2752520.06      6829169.38
#Sta/Elev= 30
  4882.4  441.73  4894.7  441.51  4923.3  439.02  4929.9  439.17  4944.1  438.14
  4958.4  435.63  4966.1  431.70  4970.7  430.22  4970.9  429.72  4974.4  429.72
  4974.7  430.22  4980.4  432.99  4987.0  433.65  5001.1  434.34  5015.3  434.20
  5029.5  433.17  5036.2  434.31  5043.8  434.06  5050.4  435.08  5058.0  431.40
  5064.7  434.64  5072.2  431.09  5078.9  436.05  5086.4  435.29  5093.1  437.22
  5100.7  436.65  5107.3  438.20  5114.9  438.03  5121.6  439.47  5180.0  442.24
#Mann=3,-1,0
  4882.4    0.16       0  4970.7    0.07       0  4974.7    0.16       0
Bank Sta=4970.7,4974.7
Exp/Cntr=0.3,0.1

Type RM Length L Ch R = 1,507,109,109,109
BEGIN DESCRIPTION:
Purtis Creek Trib C1507.23
END DESCRIPTION:
XS GIS Cut Line= 3
      2752258.47      6829078.37      2752388.24      6829150.78
      2752471.17      6829208.95
#Sta/Elev= 30
  4853.1  437.27  4861.7  436.93  4868.1  437.09  4873.8  436.34  4884.1  436.52
  4889.8  435.81  4911.5  435.12  4933.2  434.94  4941.9  432.63  4949.2  431.38
  4955.0  432.09  4964.8  432.40  4970.9  432.35  4974.7  428.88  4974.9  428.38
  4978.4  428.38  4978.7  428.88  4986.9  430.13  4992.7  431.85  4997.6  432.54
  5001.7  432.54  5007.9  434.09  5014.0  436.03  5028.9  437.55  5043.7  438.35
  5049.8  439.17  5072.3  440.40  5085.5  441.74  5100.3  442.13  5103.0  442.50
#Mann=3,-1,0
  4853.1    0.16       0  4974.7    0.07       0  4978.7    0.16       0
Bank Sta=4974.7,4978.7
Exp/Cntr=0.3,0.1

Type RM Length L Ch R = 1,398,103,103,103
BEGIN DESCRIPTION:
Purtis Creek Trib C1398.06
END DESCRIPTION:
XS GIS Cut Line= 3
      2752119.66      6829104.44      2752291.64      6829195.20
      2752378.43      6829251.84
#Sta/Elev= 30
  4805.9  434.63  4814.0  434.40  4830.3  435.02  4836.0  434.25  4858.3  433.73
  4868.7  434.38  4874.4  433.98  4890.8  434.44  4903.5  433.98  4918.4  432.52
  4934.8  432.20  4940.4  432.25  4948.8  433.43  4962.5  432.59  4971.4  431.16
  4994.0  431.73  5000.0  430.93  5006.7  431.59  5015.8  428.82  5021.8  430.18
  5027.4  428.47  5027.7  427.97  5031.2  427.97  5031.4  428.47  5036.9  430.60
  5042.9  431.80  5052.0  431.77  5058.0  436.63  5065.3  437.68  5104.0  440.43
#Mann=3,-1,0
  4805.9    0.16       0  5027.4    0.07       0  5031.4    0.16       0
Bank Sta=5027.4,5031.4
Exp/Cntr=0.3,0.1

Type RM Length L Ch R = 1,295,97,97,97
BEGIN DESCRIPTION:
Purtis Creek Trib C1295.14
END DESCRIPTION:
XS GIS Cut Line= 3
      2752044.91      6829156.32      2752201.00      6829236.31
      2752314.69      6829277.17
#Sta/Elev= 30
  4825.2  432.74  4844.9  432.62  4850.5  433.15  4867.1  432.46  4882.6  433.15
  4927.6  433.01  4939.3  433.23  4950.0  433.89  4955.9  433.36  4961.5  433.17
  4972.4  430.71  4983.7  430.20  4994.6  431.04  5000.3  430.71  5005.9  430.78
  5016.5  430.03  5025.5  427.71  5028.9  427.43  5029.1  426.93  5032.6  426.93
  5032.9  427.43  5037.8  429.00  5048.4  430.84  5056.3  431.25  5061.6  433.31
  5069.7  434.53  5080.3  435.46  5087.0  435.77  5092.3  436.45  5121.4  437.77
#Mann=3,-1,0
  4825.2    0.16       0  5028.9    0.07       0  5032.9    0.16       0
Bank Sta=5028.9,5032.9
Exp/Cntr=0.3,0.1

Type RM Length L Ch R = 1,198,160,160,160
BEGIN DESCRIPTION:
Purtis Creek Trib C1198.4
END DESCRIPTION:
XS GIS Cut Line= 4
      2751955.83      6829193.99      2752133.92      6829305.69
      2752210.93      6829311.88      2752307.71      6829289.12
#Sta/Elev= 30
  4791.7  432.86  4803.7  432.02  4817.9  431.94  4827.3  432.22  4839.1  433.18
  4862.7  431.96  4890.9  431.85  4906.2  432.59  4912.1  433.32  4933.6  432.23
  4948.7  432.04  4964.0  430.37  4969.9  430.69  4985.2  430.44  4992.6  429.72
  5000.2  430.46  5012.0  428.16  5012.3  427.66  5015.8  427.66  5016.0  428.16
  5024.1  429.38  5044.1  430.75  5054.2  432.12  5064.2  431.95  5079.2  432.35
  5115.2  434.40  5135.8  434.98  5149.8  435.73  5156.3  436.48  5178.6  437.09
#Mann=3,-1,0
  4791.7    0.16       0  5012.0    0.07       0  5016.0    0.16       0
Bank Sta=5012,5016
Exp/Cntr=0.3,0.1

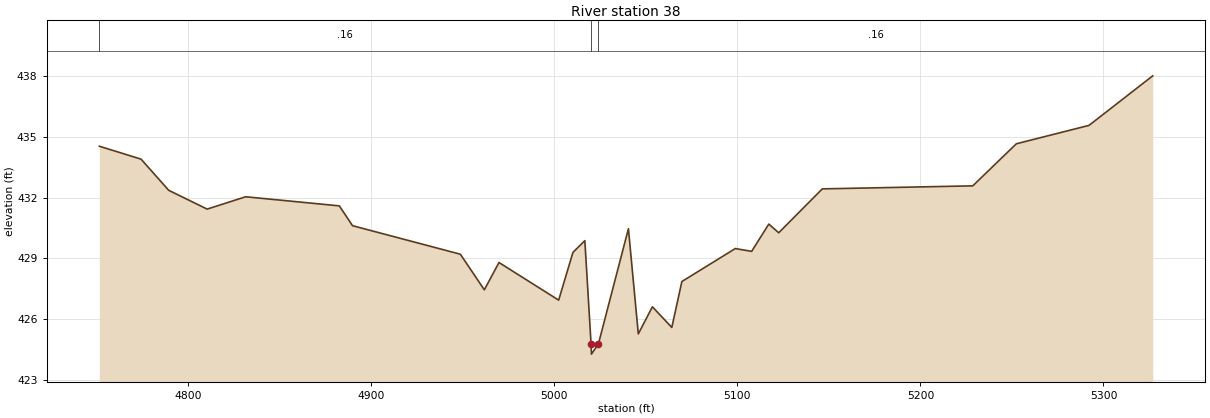
Type RM Length L Ch R = 1,38,0,0,0
BEGIN DESCRIPTION:
Purtis Creek Trib C138.21
END DESCRIPTION:
XS GIS Cut Line= 3
      2751889.20      6829215.78      2752026.59      6829422.84
      2752328.10      6829296.54
#Sta/Elev= 30
  4751.5  434.54  4774.3  433.90  4789.4  432.36  4810.4  431.43  4831.4  432.04
  4882.6  431.59  4889.8  430.61  4948.7  429.20  4961.8  427.44  4969.8  428.79
  5002.4  426.93  5010.2  429.29  5016.7  429.87  5020.1  424.76  5020.3  424.26
  5024.1  424.76  5040.5  430.46  5045.9  425.26  5053.6  426.60  5064.2  425.58
  5069.7  427.85  5098.9  429.48  5107.8  429.34  5117.2  430.69  5122.6  430.26
  5146.4  432.43  5228.6  432.58  5252.4  434.66  5292.1  435.57  5326.9  438.02
#Mann=3,-1,0
  4751.5    0.16       0  5020.1    0.07       0  5024.1    0.16       0
Bank Sta=5020.1,5024.1
Exp/Cntr=0.3,0.1

Chan Stop Cuts=-1