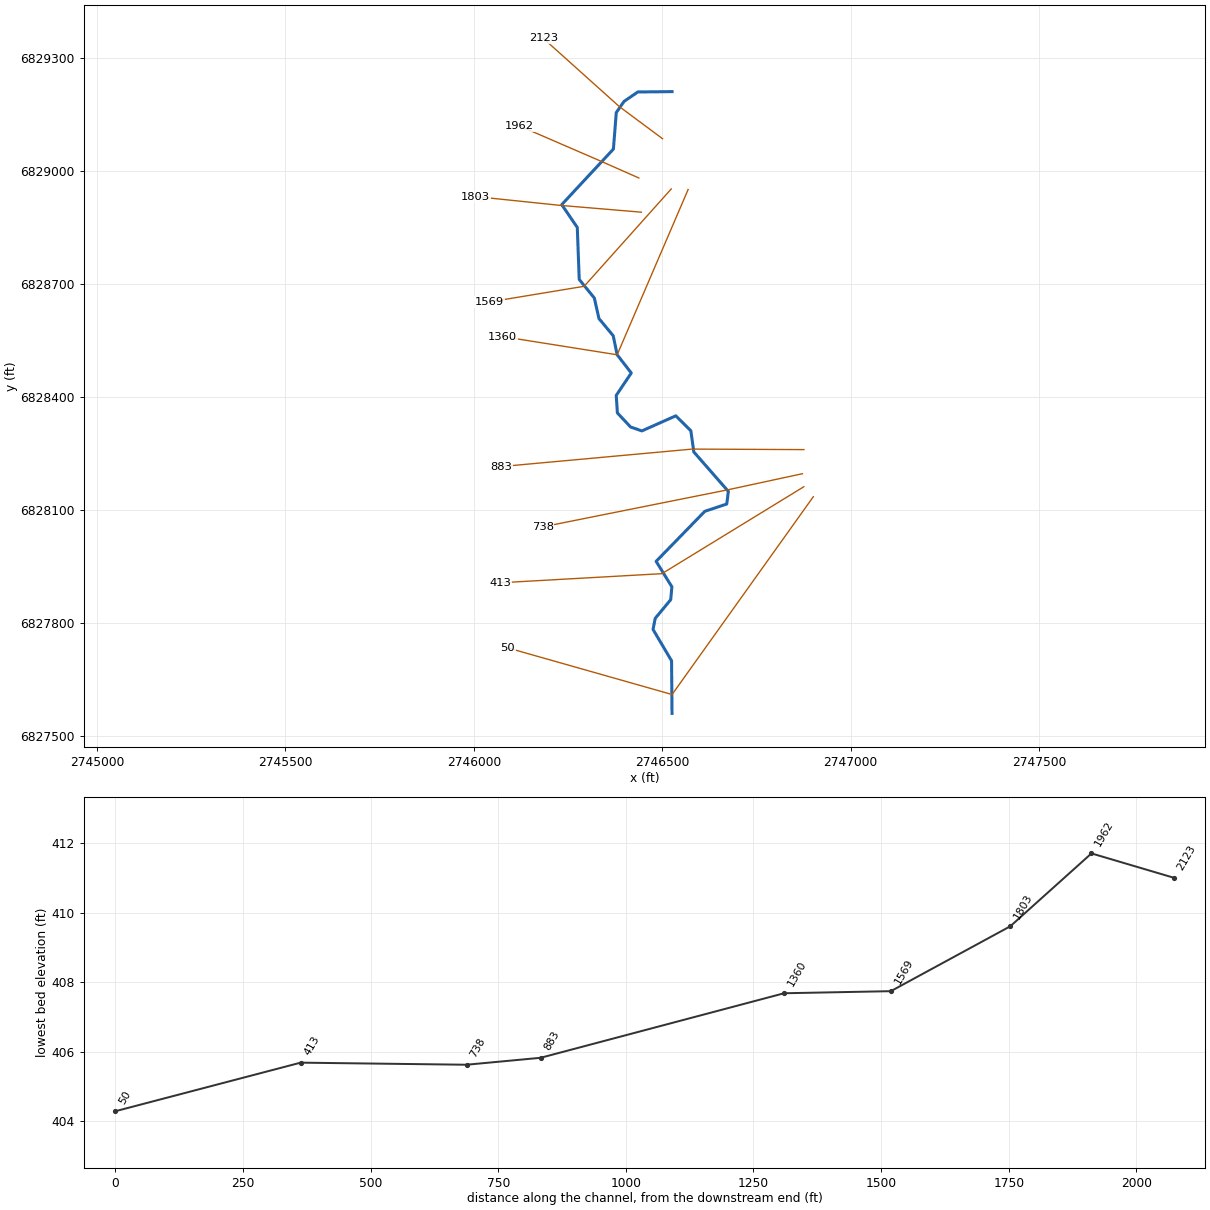
--- Purtis Creek Trib D.prj (project) ---

Proj Title=Purtis Creek Trib D Base Level Engineering
Current Plan=p01
Default Exp/Contr=0.3,0.1
English Units
Geom File=g01
Flow File=f01
Plan File=p01
BEGIN DESCRIPTION:
Purtis Creek Trib D
END DESCRIPTION:

--- Purtis Creek Trib D.p01 (plan) ---

Plan Title=Multiple Run
Short Identifier=Multiple
Geom File=g01
Flow File=f01
Subcritical Flow
K Sum by GR= 0
Std Step Tol= 0.01
Critical Tol= 0.01
Num of Std Step Trials= 20
Max Error Tol= 0.3
Flow Tol Ratio= 0.001
Split Flow NTrial= 30
Split Flow Tol= 0.02
Split Flow Ratio= 0.02
Log Output Level= 0
Friction Slope Method= 1
Unsteady Friction Slope Method= 2
Unsteady Bridges Friction Slope Method= 1
Parabolic Critical Depth
Global Vel Dist=  1 , 1 , 1
Global Log Level= 0
CheckData=True
Encroach Param= -1, 0, 0, 0
BEGIN DESCRIPTION:
Multiple Run
END DESCRIPTION:

--- Purtis Creek Trib D.f01 (steady flow) ---

Flow Title=Multiple
Number of Profiles=7
Profile Names=10-year,25-year,50-year,1pct_min,100-year,1pct_plu,500-year
River Rch & RM= Purtis Creek Tri,Reach-1,2123
     160     198     226     129     257     513     333
River Rch & RM= Purtis Creek Tri,Reach-1,883
     267     341     399     232     464     925     627
Boundary for River Rch & Prof#=Purtis Creek Tri,Reach-1,1
Up Type=0
Dn Type=3
Dn Slope=0.005
Boundary for River Rch & Prof#=Purtis Creek Tri,Reach-1,2
Up Type=0
Dn Type=3
Dn Slope=0.005
Boundary for River Rch & Prof#=Purtis Creek Tri,Reach-1,3
Up Type=0
Dn Type=3
Dn Slope=0.005
Boundary for River Rch & Prof#=Purtis Creek Tri,Reach-1,4
Up Type=0
Dn Type=3
Dn Slope=0.005
Boundary for River Rch & Prof#=Purtis Creek Tri,Reach-1,5
Up Type=0
Dn Type=3
Dn Slope=0.005
Boundary for River Rch & Prof#=Purtis Creek Tri,Reach-1,6
Up Type=0
Dn Type=3
Dn Slope=0.005
Boundary for River Rch & Prof#=Purtis Creek Tri,Reach-1,7
Up Type=0
Dn Type=3
Dn Slope=0.005

--- Purtis Creek Trib D.g01 (geometry) ---

Geom Title=Existing Conditions

River Reach=Purtis Creek Tri,Reach-1
Reach XY= 30
      2746526.00      6829211.00      2746435.28      6829210.11
      2746398.63      6829185.02      2746378.06      6829155.31
      2746370.47      6829058.58      2746233.32      6828911.10
      2746274.60      6828850.56      2746279.76      6828712.56
      2746319.88      6828663.18      2746332.08      6828608.80
      2746369.95      6828563.19      2746380.42      6828512.64
      2746417.93      6828464.30      2746377.97      6828404.90
      2746381.01      6828358.39      2746415.89      6828321.07
      2746446.02      6828310.59      2746536.08      6828350.66
      2746576.00      6828311.00      2746583.79      6828254.80
      2746675.61      6828149.97      2746671.26      6828116.62
      2746613.08      6828097.27      2746483.82      6827964.41
      2746525.60      6827896.96      2746522.56      6827862.74
      2746481.41      6827813.20      2746475.63      6827783.81
      2746524.81      6827700.52      2746526.00      6827561.00

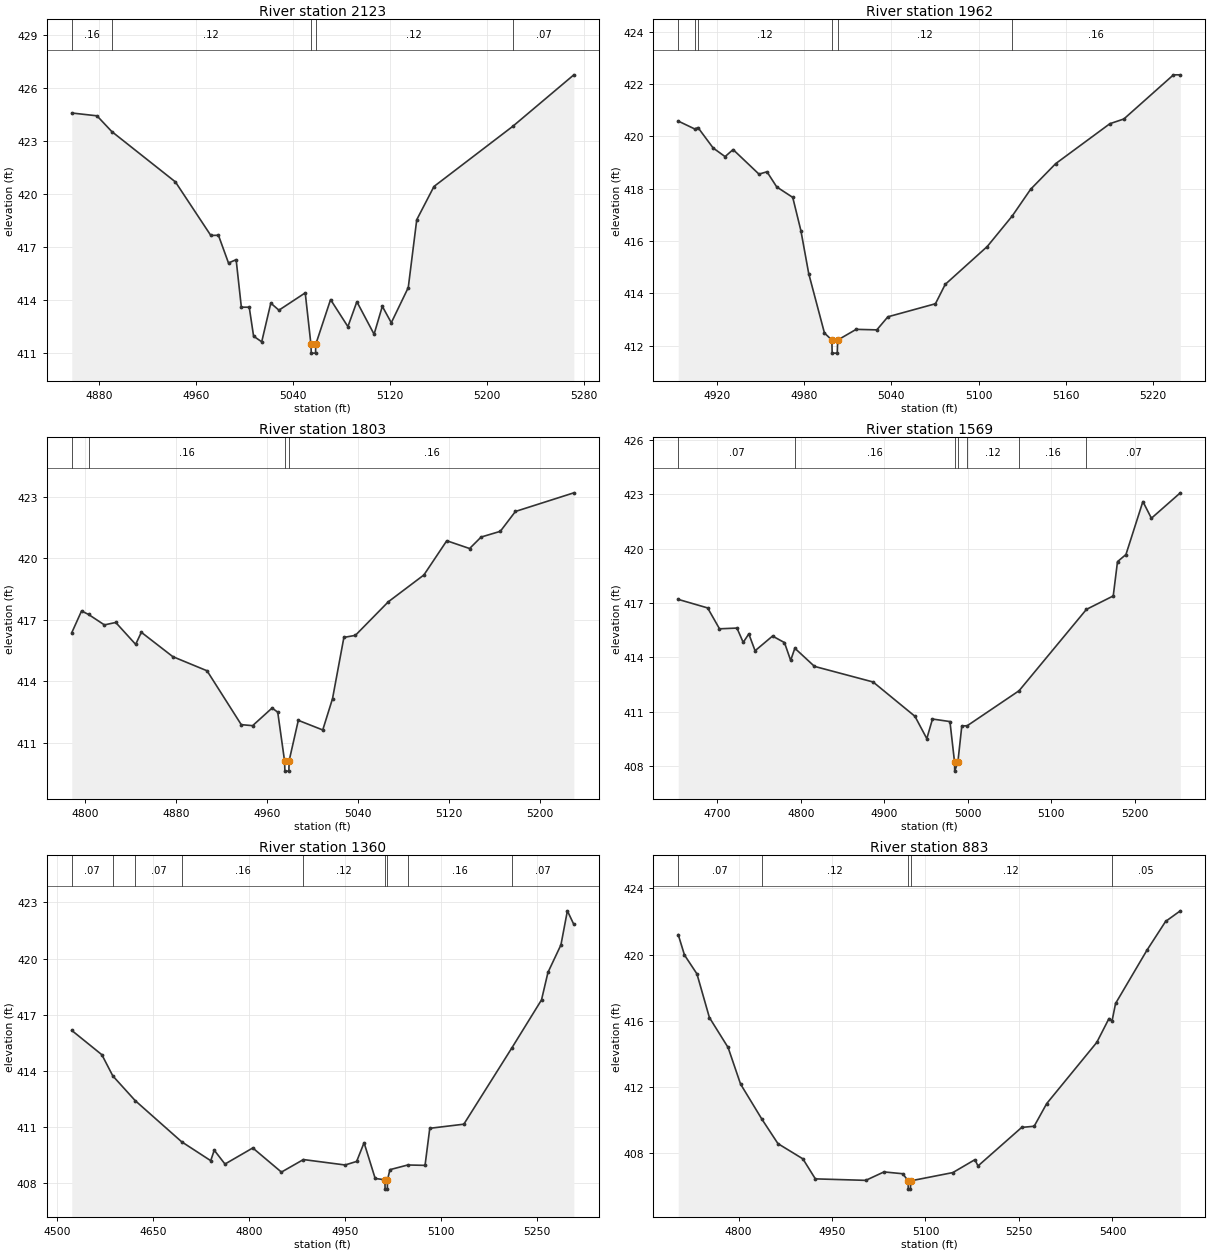
Type RM Length L Ch R = 1,2123,161,161,161
BEGIN DESCRIPTION:
Purtis Creek Trib D2123.386
END DESCRIPTION:
XS GIS Cut Line= 3
      2746500.98      6829086.02      2746386.34      6829171.16
      2746184.36      6829352.43
#Sta/Elev= 30
  4857.2  424.60  4878.0  424.44  4890.2  423.55  4942.7  420.70  4971.9  417.67
  4978.2  417.68  4986.5  416.11  4992.8  416.30  4997.1  413.61  5003.6  413.61
  5007.2  411.97  5013.9  411.65  5021.4  413.84  5028.1  413.44  5049.8  414.42
  5054.5  411.51  5054.8  411.01  5058.3  411.01  5058.5  411.51  5070.7  414.04
  5085.0  412.51  5092.4  413.92  5106.6  412.08  5113.4  413.66  5120.8  412.73
  5134.8  414.72  5141.8  418.56  5156.0  420.44  5221.1  423.85  5271.4  426.76
#Mann=5,-1,0
  4857.2    0.16       0  4890.2    0.12       0  5054.5    0.07       0
  5058.5    0.12       0  5221.1    0.07       0
Bank Sta=5054.5,5058.5
Exp/Cntr=0.3,0.1

Type RM Length L Ch R = 1,1962,159,159,159
BEGIN DESCRIPTION:
Purtis Creek Trib D1962.48
END DESCRIPTION:
XS GIS Cut Line= 3
      2746437.93      6828981.85      2746337.67      6829026.20
      2746121.58      6829119.74
#Sta/Elev= 30
  4893.5  420.59  4904.8  420.29  4907.1  420.34  4917.5  419.56  4925.7  419.23
  4931.2  419.50  4949.0  418.56  4954.5  418.65  4961.2  418.07  4972.2  417.67
  4977.8  416.40  4983.2  414.75  4994.0  412.48  4999.1  412.21  4999.3  411.71
  5002.8  411.71  5003.1  412.21  5015.8  412.62  5030.0  412.60  5037.6  413.10
  5070.3  413.60  5077.0  414.34  5105.9  415.79  5123.1  416.96  5135.7  417.98
  5152.9  418.96  5190.2  420.49  5199.8  420.67  5233.9  422.36  5238.6  422.36
#Mann=6,-1,0
  4893.5    0.07       0  4904.8    0.16       0  4907.1    0.12       0
  4999.1    0.07       0  5003.1    0.12       0  5123.1    0.16       0
Bank Sta=4999.1,5003.1
Exp/Cntr=0.3,0.1

Type RM Length L Ch R = 1,1803,234,234,234
BEGIN DESCRIPTION:
Purtis Creek Trib D1802.69
END DESCRIPTION:
XS GIS Cut Line= 3
      2746444.56      6828891.09      2746228.05      6828909.27
      2746004.83      6828932.50
#Sta/Elev= 30
  4788.4  416.37  4797.0  417.43  4803.2  417.26  4817.1  416.75  4827.1  416.87
  4844.6  415.80  4849.6  416.39  4877.3  415.20  4907.4  414.51  4937.5  411.88
  4947.5  411.83  4964.6  412.69  4969.6  412.49  4975.6  410.11  4975.9  409.61
  4979.4  409.61  4979.6  410.11  4987.7  412.09  5009.2  411.62  5017.8  413.15
  5027.8  416.14  5037.9  416.24  5066.9  417.88  5098.2  419.19  5118.3  420.86
  5138.4  420.48  5148.5  421.04  5165.4  421.32  5178.7  422.29  5230.1  423.20
#Mann=4,-1,0
  4788.4    0.07       0  4803.2    0.16       0  4975.6    0.07       0
  4979.6    0.16       0
Bank Sta=4975.6,4979.6
Exp/Cntr=0.3,0.1

Type RM Length L Ch R = 1,1569,209,209,209
BEGIN DESCRIPTION:
Purtis Creek Trib D1623.75
END DESCRIPTION:
XS GIS Cut Line= 3
      2746523.96      6828952.79      2746292.81      6828694.39
      2746041.82      6828652.90
#Sta/Elev= 30
  4653.3  417.20  4688.5  416.73  4702.7  415.58  4723.6  415.62  4731.1  414.83
  4737.8  415.30  4745.3  414.37  4766.2  415.18  4780.5  414.82  4787.9  413.84
  4792.9  414.51  4816.4  413.51  4886.6  412.65  4936.7  410.76  4950.9  409.53
  4957.7  410.61  4978.6  410.47  4984.1  408.24  4984.3  407.74  4988.1  408.24
  4992.8  410.23  4999.3  410.24  5061.4  412.17  5142.0  416.65  5174.1  417.39
  5179.2  419.28  5189.3  419.67  5209.6  422.59  5219.8  421.67  5254.4  423.07
#Mann=7,-1,0
  4653.3    0.07       0  4792.9    0.16       0  4984.1    0.07       0
  4988.1    0.16       0  4999.3    0.12       0  5061.4    0.16       0
  5142.0    0.07       0
Bank Sta=4984.1,4988.1
Exp/Cntr=0.3,0.1

Type RM Length L Ch R = 1,1360,477,477,477
BEGIN DESCRIPTION:
Purtis Creek Trib D1360.445
END DESCRIPTION:
XS GIS Cut Line= 3
      2746568.74      6828951.22      2746380.42      6828512.64
      2746076.04      6828560.99
#Sta/Elev= 30
  4522.7  416.16  4569.8  414.86  4586.9  413.73  4621.9  412.41  4694.6  410.21
  4740.1  409.20  4745.6  409.76  4762.4  409.02  4805.9  409.88  4850.7  408.59
  4885.1  409.26  4950.3  408.97  4968.4  409.16  4980.0  410.16  4997.4  408.25
  5012.6  408.18  5012.9  407.68  5016.4  407.68  5016.6  408.18  5020.5  408.72
  5048.4  408.97  5075.4  408.95  5082.8  410.93  5136.1  411.15  5211.3  415.23
  5257.6  417.79  5267.7  419.26  5288.0  420.73  5298.1  422.55  5308.2  421.82
#Mann=9,-1,0
  4522.7    0.07       0  4586.9    0.16       0  4621.9    0.07       0
  4694.6    0.16       0  4885.1    0.12       0  5012.6    0.07       0
  5016.6    0.12       0  5048.4    0.16       0  5211.3    0.07       0
Bank Sta=5012.6,5016.6
Exp/Cntr=0.3,0.1

Type RM Length L Ch R = 1,883,145,145,145
BEGIN DESCRIPTION:
Purtis Creek Trib D883.201
END DESCRIPTION:
XS GIS Cut Line= 3
      2746875.99      6828261.00      2746579.29      6828262.36
      2746072.51      6828215.97
#Sta/Elev= 30
  4703.3  421.20  4713.3  419.97  4733.3  418.83  4753.3  416.19  4783.3  414.38
  4803.3  412.17  4837.5  410.05  4863.3  408.57  4903.3  407.65  4923.3  406.44
  5004.2  406.35  5033.4  406.86  5063.6  406.75  5072.2  406.32  5072.4  405.82
  5075.9  405.82  5076.2  406.32  5143.9  406.82  5179.3  407.60  5184.3  407.22
  5254.4  409.55  5274.4  409.62  5294.5  410.99  5374.9  414.69  5394.4  416.13
  5399.4  415.99  5405.0  417.04  5455.2  420.25  5485.3  422.00  5508.9  422.64
#Mann=5,-1,0
  4703.3    0.07       0  4837.5    0.12       0  5072.2    0.07       0
  5076.2    0.12       0  5399.4    0.05       0
Bank Sta=5072.2,5076.2
Exp/Cntr=0.3,0.1

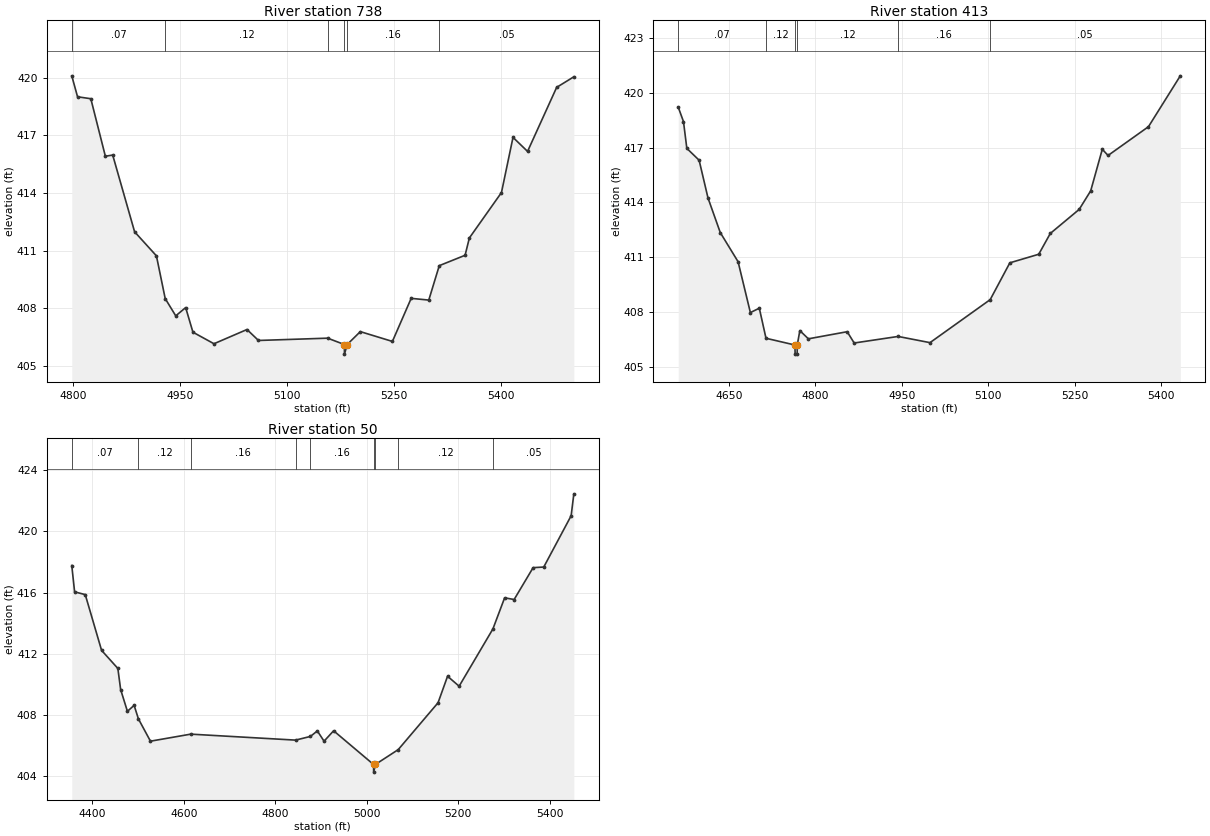
Type RM Length L Ch R = 1,738,325,325,325
BEGIN DESCRIPTION:
Purtis Creek Trib D738.24
END DESCRIPTION:
XS GIS Cut Line= 3
      2746872.07      6828197.02      2746673.24      6828154.15
      2746182.38      6828055.89
#Sta/Elev= 30
  4798.0  420.09  4806.1  419.00  4824.7  418.90  4845.1  415.91  4855.4  415.97
  4886.1  411.98  4916.7  410.73  4929.0  408.51  4943.8  407.61  4957.7  408.04
  4967.9  406.76  4997.4  406.16  5043.7  406.90  5059.8  406.33  5156.8  406.45
  5180.2  406.12  5180.4  405.62  5184.2  406.12  5202.6  406.79  5247.6  406.28
  5273.9  408.52  5298.6  408.43  5313.3  410.22  5349.5  410.76  5355.5  411.66
  5400.5  414.02  5416.7  416.89  5437.1  416.16  5477.9  419.49  5502.0  420.04
#Mann=6,-1,0
  4798.0    0.07       0  4929.0    0.12       0  5156.8    0.16       0
  5180.2    0.07       0  5184.2    0.16       0  5313.3    0.05       0
Bank Sta=5180.2,5184.2
Exp/Cntr=0.3,0.1

Type RM Length L Ch R = 1,413,363,363,363
BEGIN DESCRIPTION:
Purtis Creek Trib D413.28
END DESCRIPTION:
XS GIS Cut Line= 3
      2746875.86      6828162.48      2746499.27      6827931.77
      2746070.89      6827907.65
#Sta/Elev= 30
  4562.5  419.23  4571.6  418.44  4577.4  416.97  4598.7  416.32  4614.1  414.25
  4635.4  412.35  4666.3  410.75  4687.6  407.96  4703.1  408.20  4714.7  406.55
  4764.9  406.18  4765.2  405.68  4768.7  405.68  4768.9  406.18  4773.4  406.97
  4788.2  406.52  4855.5  406.91  4867.6  406.29  4943.8  406.65  4999.1  406.31
  5103.5  408.67  5137.6  410.69  5187.7  411.16  5207.7  412.30  5257.8  413.62
  5277.8  414.64  5297.9  416.92  5307.9  416.58  5378.0  418.16  5433.2  420.95
#Mann=6,-1,0
  4562.5    0.07       0  4714.7    0.12       0  4764.9    0.07       0
  4768.9    0.12       0  4943.8    0.16       0  5103.5    0.05       0
Bank Sta=4764.9,4768.9
Exp/Cntr=0.3,0.1

Type RM Length L Ch R = 1,50,0,0,0
BEGIN DESCRIPTION:
Purtis Creek Trib D50.048
END DESCRIPTION:
XS GIS Cut Line= 3
      2746901.02      6828136.02      2746526.11      6827611.05
      2746090.31      6827734.69
#Sta/Elev= 30
  4354.9  417.77  4361.1  416.05  4384.4  415.87  4420.1  412.23  4455.7  411.05
  4461.8  409.67  4476.6  408.25  4491.3  408.64  4500.6  407.76  4527.0  406.30
  4615.1  406.76  4844.3  406.37  4876.8  406.61  4892.0  406.97  4906.7  406.30
  4927.6  406.98  5014.9  404.78  5015.2  404.28  5018.9  404.78  5068.9  405.75
  5156.0  408.81  5176.8  410.54  5202.1  409.89  5276.0  413.63  5301.6  415.66
  5322.4  415.55  5363.9  417.63  5387.2  417.67  5447.1  421.02  5453.0  422.45
#Mann=9,-1,0
  4354.9    0.07       0  4500.6    0.12       0  4615.1    0.16       0
  4844.3    0.12       0  4876.8    0.16       0  5014.9    0.07       0
  5018.9    0.16       0  5068.9    0.12       0  5276.0    0.05       0
Bank Sta=5014.9,5018.9
Exp/Cntr=0.3,0.1

Chan Stop Cuts=-1