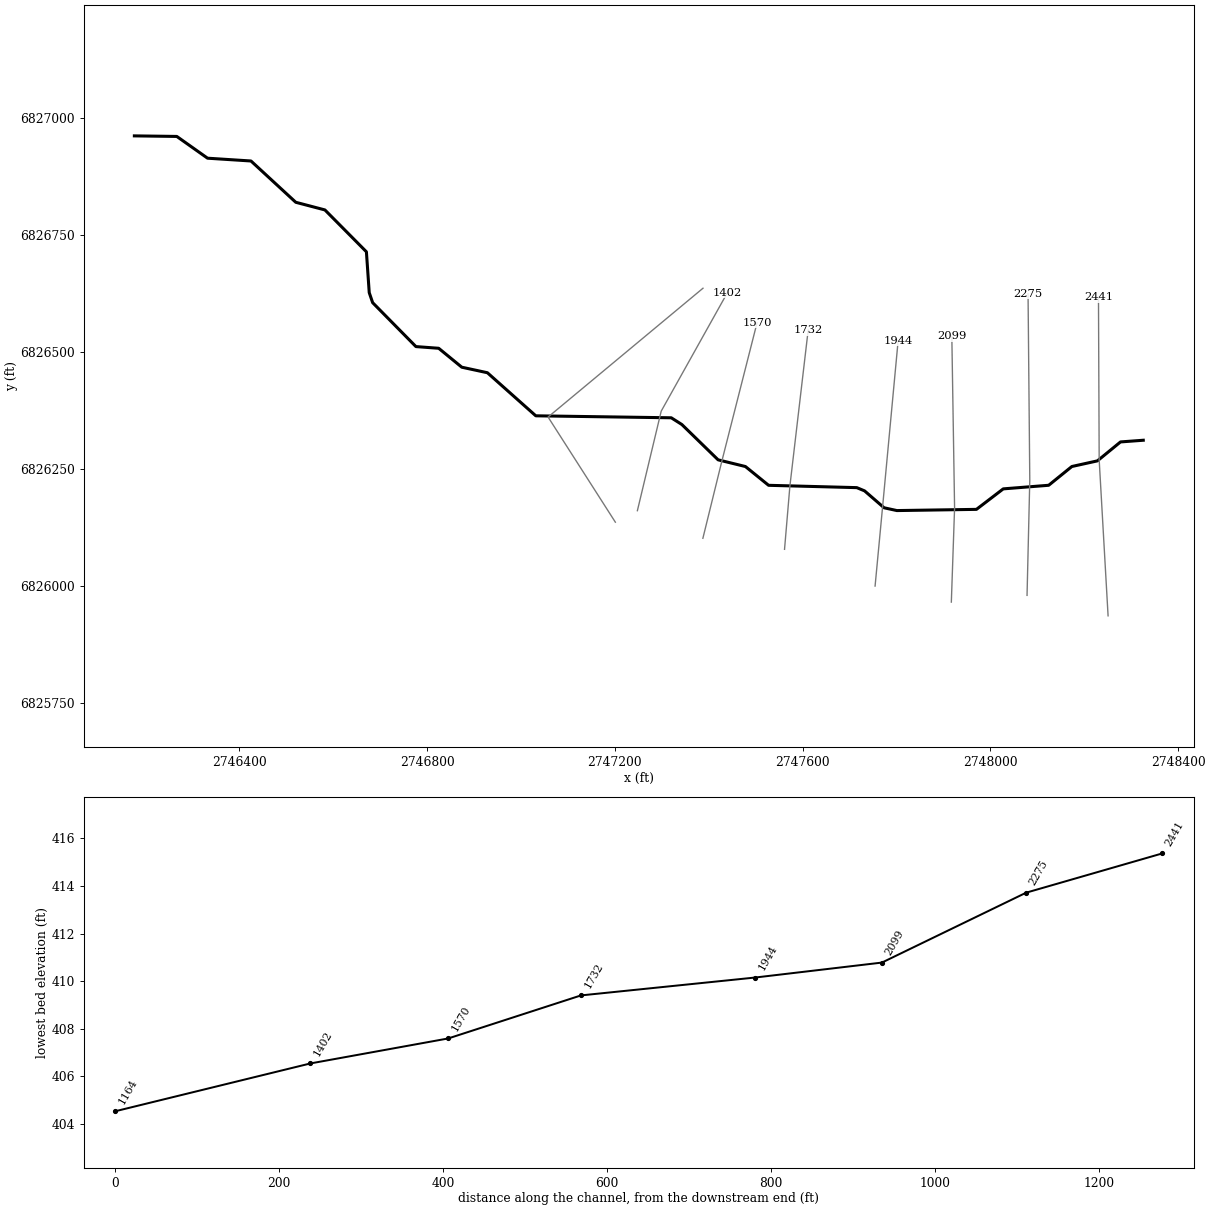
--- Purtis Creek Trib E.prj (project) ---

Proj Title=Purtis Creek Trib E Base Level Engineering
Current Plan=p01
Default Exp/Contr=0.3,0.1
English Units
Geom File=g01
Flow File=f01
Plan File=p01
BEGIN DESCRIPTION:
Purtis Creek Trib E
END DESCRIPTION:

--- Purtis Creek Trib E.p01 (plan) ---

Plan Title=Multiple Run
Short Identifier=Multiple
Geom File=g01
Flow File=f01
Subcritical Flow
K Sum by GR= 0
Std Step Tol= 0.01
Critical Tol= 0.01
Num of Std Step Trials= 20
Max Error Tol= 0.3
Flow Tol Ratio= 0.001
Split Flow NTrial= 30
Split Flow Tol= 0.02
Split Flow Ratio= 0.02
Log Output Level= 0
Friction Slope Method= 1
Unsteady Friction Slope Method= 2
Unsteady Bridges Friction Slope Method= 1
Parabolic Critical Depth
Global Vel Dist=  1 , 1 , 1
Global Log Level= 0
CheckData=True
Encroach Param= -1, 0, 0, 0
BEGIN DESCRIPTION:
Multiple Run
END DESCRIPTION:

--- Purtis Creek Trib E.f01 (steady flow) ---

Flow Title=Multiple
Number of Profiles=7
Profile Names=10-year,25-year,50-year,1pct_min,100-year,1pct_plu,500-year
River Rch & RM= Purtis Creek Tri,Reach-1,2441
     287     367     429     250     498     994     672
Boundary for River Rch & Prof#=Purtis Creek Tri,Reach-1,1
Up Type=0
Dn Type=3
Dn Slope=0.005
Boundary for River Rch & Prof#=Purtis Creek Tri,Reach-1,2
Up Type=0
Dn Type=3
Dn Slope=0.005
Boundary for River Rch & Prof#=Purtis Creek Tri,Reach-1,3
Up Type=0
Dn Type=3
Dn Slope=0.005
Boundary for River Rch & Prof#=Purtis Creek Tri,Reach-1,4
Up Type=0
Dn Type=3
Dn Slope=0.005
Boundary for River Rch & Prof#=Purtis Creek Tri,Reach-1,5
Up Type=0
Dn Type=3
Dn Slope=0.005
Boundary for River Rch & Prof#=Purtis Creek Tri,Reach-1,6
Up Type=0
Dn Type=3
Dn Slope=0.005
Boundary for River Rch & Prof#=Purtis Creek Tri,Reach-1,7
Up Type=0
Dn Type=3
Dn Slope=0.005

--- Purtis Creek Trib E.g01 (geometry) ---

Geom Title=Existing Conditions

River Reach=Purtis Creek Tri,Reach-1
Reach XY= 30
      2748326.00      6826311.00      2748277.49      6826307.40
      2748228.25      6826266.95      2748173.81      6826254.90
      2748124.42      6826214.82      2748027.60      6826207.14
      2747970.47      6826163.37      2747800.92      6826160.80
      2747773.67      6826166.75      2747732.06      6826202.86
      2747715.49      6826209.78      2747527.55      6826214.75
      2747478.17      6826254.86      2747419.95      6826269.16
      2747342.75      6826344.54      2747320.14      6826358.94
      2747031.45      6826363.18      2746928.30      6826455.17
      2746873.76      6826466.97      2746824.51      6826507.40
      2746776.00      6826511.00      2746683.79      6826604.80
      2746676.51      6826626.21      2746670.48      6826713.44
      2746582.07      6826802.85      2746519.96      6826819.18
      2746424.50      6826907.38      2746331.97      6826913.34
      2746266.42      6826959.81      2746176.00      6826961.00

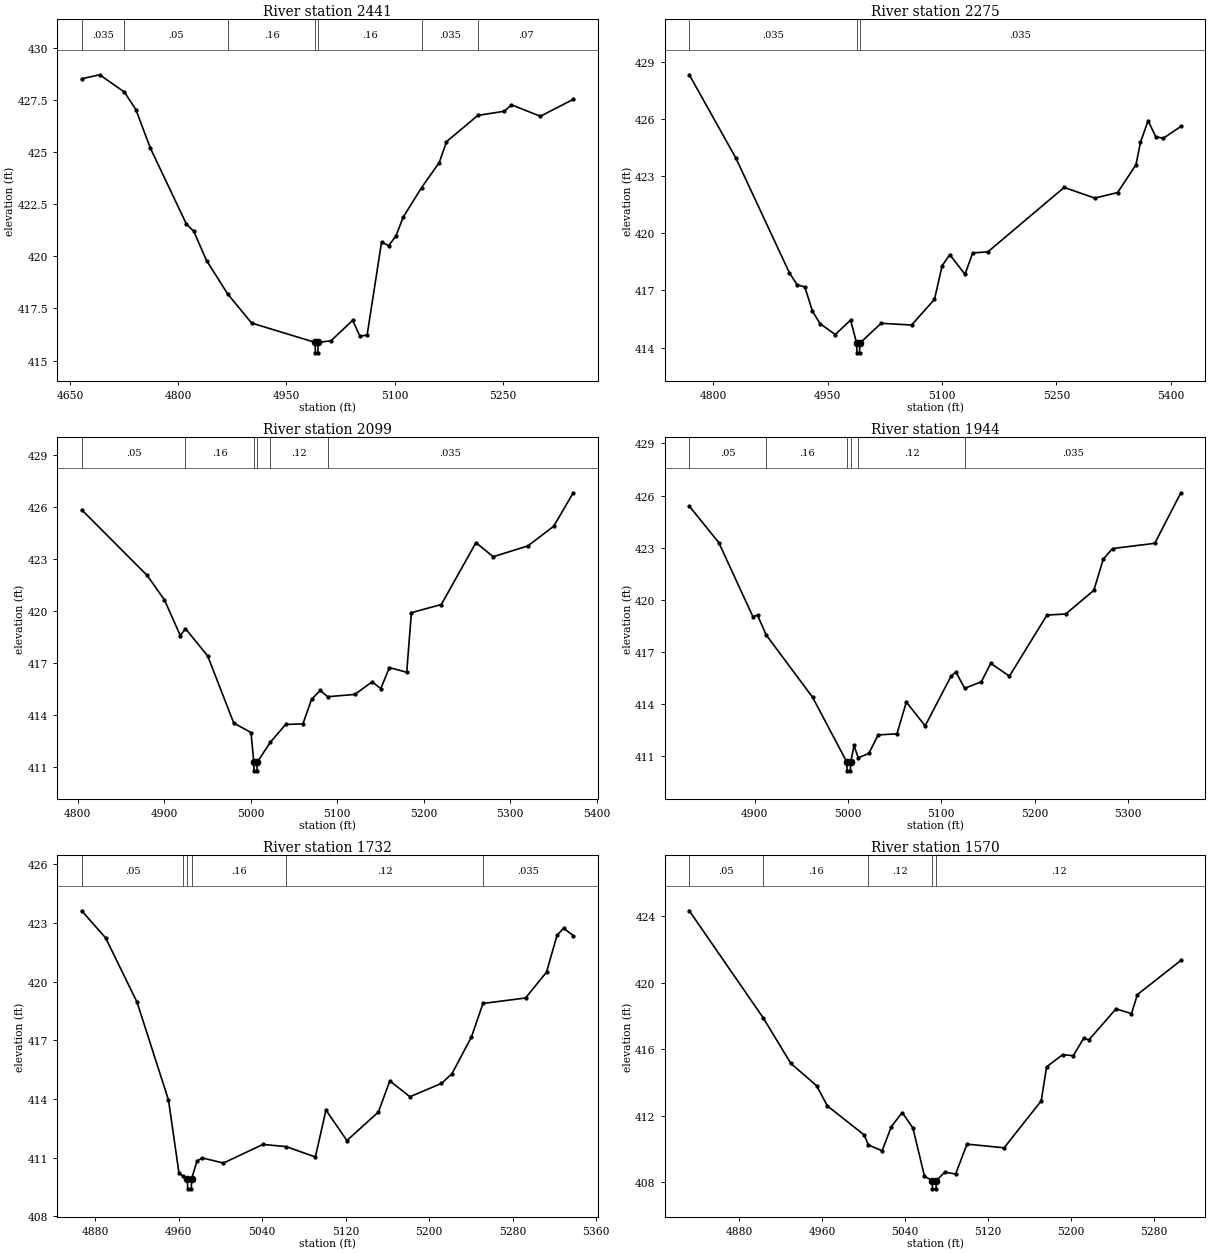
Type RM Length L Ch R = 1,2441,166,166,166
BEGIN DESCRIPTION:
Purtis Creek Trib E2440.561
END DESCRIPTION:
XS GIS Cut Line= 3
      2748251.00      6825936.00      2748232.01      6826269.26
      2748230.53      6826616.56
#Sta/Elev= 30
  4666.2  428.52  4691.2  428.71  4725.4  427.88  4741.3  427.04  4761.4  425.19
  4811.4  421.54  4821.4  421.21  4839.2  419.80  4868.6  418.19  4901.6  416.80
  4989.7  415.87  4990.0  415.37  4993.5  415.37  4993.7  415.87  5011.7  415.95
  5041.7  416.93  5051.7  416.17  5061.7  416.22  5081.7  420.68  5091.7  420.51
  5101.7  420.98  5111.7  421.88  5137.2  423.30  5161.7  424.50  5171.7  425.50
  5215.1  426.76  5251.7  426.96  5261.7  427.27  5301.7  426.72  5347.3  427.53
#Mann=7,-1,0
  4666.2   0.035       0  4725.4    0.05       0  4868.6    0.16       0
  4989.7    0.07       0  4993.7    0.16       0  5137.2   0.035       0
  5215.1    0.07       0
Bank Sta=4989.7,4993.7
Exp/Cntr=0.3,0.1

Type RM Length L Ch R = 1,2275,176,176,176
BEGIN DESCRIPTION:
Purtis Creek Trib E2275.01
END DESCRIPTION:
XS GIS Cut Line= 3
      2748078.30      6825979.69      2748084.14      6826225.71
      2748080.45      6826623.90
#Sta/Elev= 30
  4768.7  428.31  4830.0  423.92  4900.0  417.91  4910.0  417.29  4920.1  417.18
  4930.1  415.91  4940.1  415.25  4960.1  414.68  4980.1  415.44  4988.1  414.22
  4988.3  413.72  4991.8  413.72  4992.1  414.22  5020.1  415.27  5060.1  415.18
  5090.1  416.53  5100.1  418.29  5110.1  418.87  5130.1  417.84  5140.1  418.96
  5160.1  419.02  5260.1  422.40  5300.1  421.84  5330.1  422.13  5354.2  423.59
  5360.1  424.77  5370.1  425.90  5380.1  425.06  5390.1  424.98  5413.0  425.60
#Mann=3,-1,0
  4768.7   0.035       0  4988.1   0.035       0  4992.1   0.035       0
Bank Sta=4988.1,4992.1
Exp/Cntr=0.3,0.1

Type RM Length L Ch R = 1,2099,155,155,155
BEGIN DESCRIPTION:
Purtis Creek Trib E2098.85
END DESCRIPTION:
XS GIS Cut Line= 3
      2747916.97      6825965.35      2747923.89      6826166.44
      2747918.01      6826533.48
#Sta/Elev= 30
  4804.6  425.85  4880.3  422.06  4900.3  420.65  4918.6  418.59  4924.6  418.99
  4950.3  417.41  4980.4  413.54  5000.4  412.99  5003.6  411.28  5003.8  410.78
  5007.3  410.78  5007.6  411.28  5022.7  412.43  5040.4  413.46  5060.4  413.49
  5070.4  414.91  5080.4  415.42  5089.0  415.06  5120.4  415.19  5140.4  415.92
  5150.4  415.53  5160.4  416.74  5180.4  416.47  5185.8  419.91  5220.4  420.38
  5260.4  423.95  5280.4  423.14  5320.4  423.76  5350.4  424.90  5372.9  426.83
#Mann=6,-1,0
  4804.6    0.05       0  4924.6    0.16       0  5003.6    0.07       0
  5007.6    0.16       0  5022.7    0.12       0  5089.0   0.035       0
Bank Sta=5003.6,5007.6
Exp/Cntr=0.3,0.1

Type RM Length L Ch R = 1,1944,212,212,212
BEGIN DESCRIPTION:
Purtis Creek Trib E1944.09
END DESCRIPTION:
XS GIS Cut Line= 3
      2747754.47      6825999.56      2747770.88      6826173.15
      2747803.60      6826523.76
#Sta/Elev= 30
  4830.0  425.39  4861.6  423.29  4898.1  419.03  4903.1  419.11  4912.3  417.98
  4962.0  414.39  4998.8  410.65  4999.0  410.15  5002.5  410.15  5002.8  410.65
  5006.5  411.61  5010.9  410.90  5022.3  411.15  5032.3  412.22  5052.4  412.28
  5062.5  414.11  5082.6  412.74  5110.5  415.61  5115.5  415.84  5125.0  414.90
  5142.8  415.28  5152.9  416.34  5172.9  415.60  5213.1  419.12  5233.2  419.18
  5263.3  420.54  5273.4  422.34  5283.4  422.95  5328.6  423.25  5356.5  426.16
#Mann=6,-1,0
  4830.0    0.05       0  4912.3    0.16       0  4998.8    0.07       0
  5002.8    0.16       0  5010.9    0.12       0  5125.0   0.035       0
Bank Sta=4998.8,5002.8
Exp/Cntr=0.3,0.1

Type RM Length L Ch R = 1,1732,162,162,162
BEGIN DESCRIPTION:
Purtis Creek Trib E1731.73
END DESCRIPTION:
XS GIS Cut Line= 3
      2747561.51      6826078.05      2747572.96      6826213.42
      2747611.93      6826546.40
#Sta/Elev= 30
  4867.0  423.62  4890.0  422.23  4920.1  418.94  4950.2  413.94  4960.3  410.19
  4964.2  410.05  4968.3  409.90  4968.6  409.40  4972.1  409.40  4972.3  409.90
  4977.5  410.82  4982.5  410.98  5002.9  410.72  5040.7  411.67  5062.9  411.56
  5091.0  411.03  5101.1  413.43  5121.2  411.87  5151.4  413.33  5162.3  414.92
  5181.6  414.11  5211.8  414.79  5221.9  415.29  5240.6  417.17  5251.6  418.88
  5292.4  419.16  5312.5  420.48  5322.6  422.37  5328.9  422.73  5338.1  422.35
#Mann=6,-1,0
  4867.0    0.05       0  4964.2    0.16       0  4968.3    0.07       0
  4972.3    0.16       0  5062.9    0.12       0  5251.6   0.035       0
Bank Sta=4968.3,4972.3
Exp/Cntr=0.3,0.1

Type RM Length L Ch R = 1,1570,168,168,168
BEGIN DESCRIPTION:
Purtis Creek Trib E1570.32
END DESCRIPTION:
XS GIS Cut Line= 3
      2747387.52      6826101.62      2747427.68      6826265.35
      2747502.87      6826561.58
#Sta/Elev= 30
  4831.8  424.32  4903.2  417.87  4929.7  415.14  4954.7  413.79  4965.0  412.58
  5000.4  410.84  5004.6  410.23  5017.8  409.88  5026.8  411.34  5037.2  412.18
  5047.5  411.25  5058.7  408.35  5066.1  408.09  5066.4  407.59  5069.9  407.59
  5070.1  408.09  5078.4  408.60  5088.7  408.48  5099.7  410.28  5135.5  410.06
  5171.3  412.88  5176.5  414.93  5191.9  415.66  5202.2  415.60  5212.3  416.65
  5217.4  416.56  5243.5  418.42  5258.4  418.13  5264.1  419.28  5306.0  421.33
#Mann=5,-1,0
  4831.8    0.05       0  4903.2    0.16       0  5004.6    0.12       0
  5066.1    0.07       0  5070.1    0.12       0
Bank Sta=5066.1,5070.1
Exp/Cntr=0.3,0.1

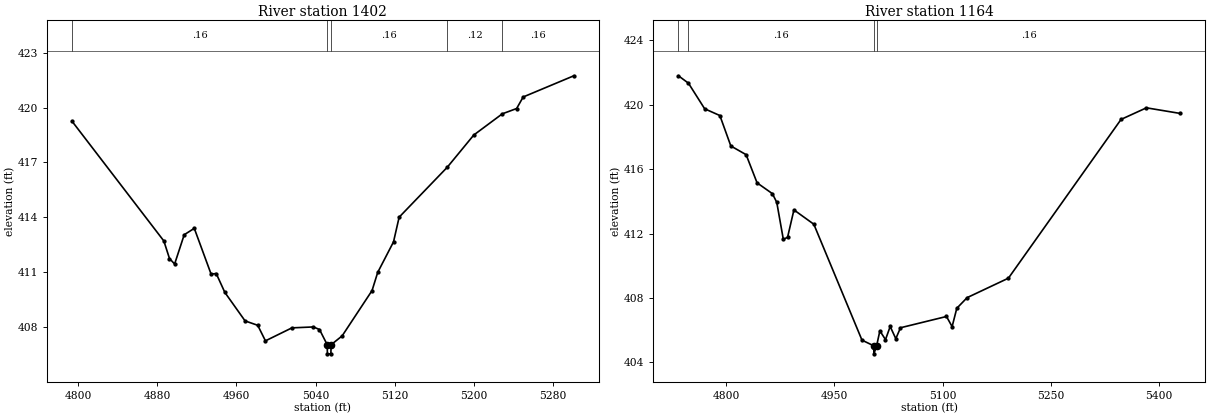
Type RM Length L Ch R = 1,1402,238,238,238
BEGIN DESCRIPTION:
Purtis Creek Trib E1402.12
END DESCRIPTION:
XS GIS Cut Line= 3
      2747247.93      6826160.54      2747298.69      6826373.09
      2747439.59      6826625.85
#Sta/Elev= 30
  4793.5  419.26  4886.5  412.71  4892.2  411.75  4897.4  411.45  4907.1  413.05
  4917.3  413.40  4934.3  410.90  4939.5  410.93  4948.2  409.90  4968.7  408.34
  4981.5  408.10  4989.3  407.25  5016.1  407.96  5037.8  408.01  5044.0  407.87
  5051.8  407.04  5052.0  406.54  5055.5  406.54  5055.8  407.04  5066.9  407.52
  5097.2  410.00  5102.9  410.99  5118.9  412.66  5124.6  414.01  5173.3  416.74
  5200.1  418.50  5229.0  419.66  5243.5  419.95  5250.1  420.58  5301.4  421.74
#Mann=5,-1,0
  4793.5    0.16       0  5051.8    0.07       0  5055.8    0.16       0
  5173.3    0.12       0  5229.0    0.16       0
Bank Sta=5051.8,5055.8
Exp/Cntr=0.3,0.1

Type RM Length L Ch R = 1,1164,0,0,0
BEGIN DESCRIPTION:
Purtis Creek Trib E1163.843
END DESCRIPTION:
XS GIS Cut Line= 3
      2747200.99      6826136.01      2747057.63      6826360.54
      2747387.74      6826635.63
#Sta/Elev= 30
  4733.6  421.80  4747.5  421.34  4770.0  419.75  4791.1  419.33  4806.3  417.44
  4827.5  416.90  4842.7  415.15  4863.9  414.48  4870.0  413.94  4879.1  411.64
  4885.0  411.77  4893.8  413.47  4921.4  412.58  4988.2  405.38  5004.5  405.03
  5004.7  404.53  5008.5  405.03  5013.0  405.96  5020.8  405.41  5027.3  406.23
  5035.1  405.47  5041.6  406.15  5105.4  406.85  5113.2  406.22  5119.7  407.36
  5134.0  408.02  5191.3  409.23  5347.5  419.09  5382.7  419.81  5429.7  419.46
#Mann=4,-1,0
  4733.6    0.05       0  4747.5    0.16       0  5004.5    0.07       0
  5008.5    0.16       0
Bank Sta=5004.5,5008.5
Exp/Cntr=0.3,0.1

Chan Stop Cuts=-1