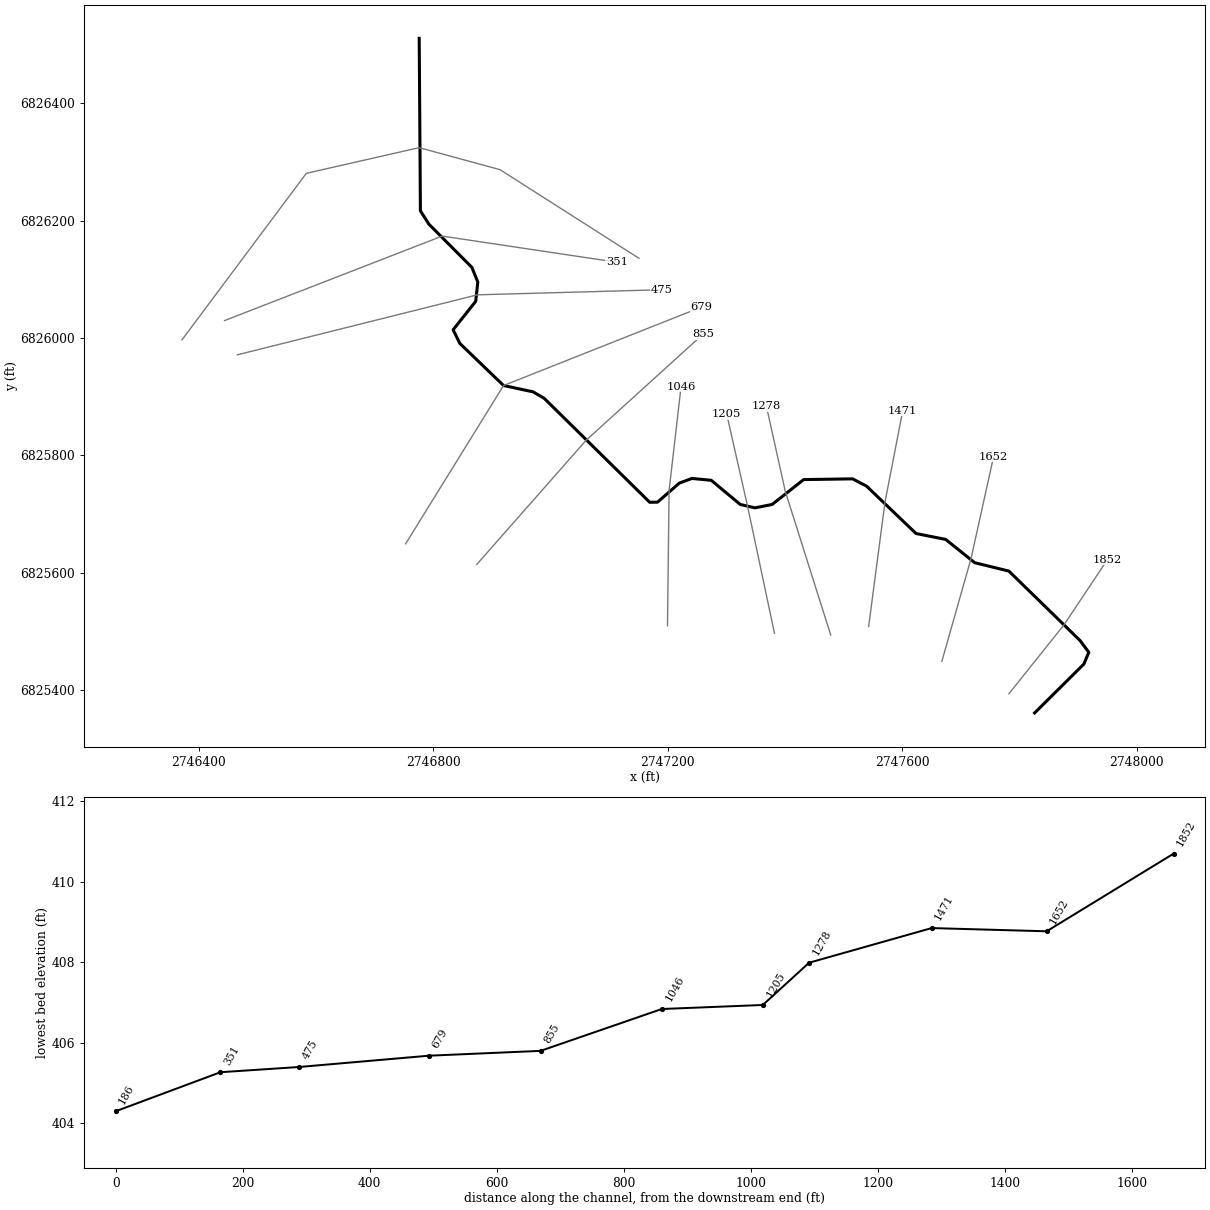
--- Purtis Creek Trib E1.prj (project) ---

Proj Title=Purtis Creek Trib E1 Base Level Engineering
Current Plan=p01
Default Exp/Contr=0.3,0.1
English Units
Geom File=g01
Flow File=f01
Plan File=p01
BEGIN DESCRIPTION:
Purtis Creek Trib E1
END DESCRIPTION:

--- Purtis Creek Trib E1.p01 (plan) ---

Plan Title=Multiple Run
Short Identifier=Multiple
Geom File=g01
Flow File=f01
Subcritical Flow
K Sum by GR= 0
Std Step Tol= 0.01
Critical Tol= 0.01
Num of Std Step Trials= 20
Max Error Tol= 0.3
Flow Tol Ratio= 0.001
Split Flow NTrial= 30
Split Flow Tol= 0.02
Split Flow Ratio= 0.02
Log Output Level= 0
Friction Slope Method= 1
Unsteady Friction Slope Method= 2
Unsteady Bridges Friction Slope Method= 1
Parabolic Critical Depth
Global Vel Dist=  1 , 1 , 1
Global Log Level= 0
CheckData=True
Encroach Param= -1, 0, 0, 0
BEGIN DESCRIPTION:
Multiple Run
END DESCRIPTION:

--- Purtis Creek Trib E1.f01 (steady flow) ---

Flow Title=Multiple
Number of Profiles=7
Profile Names=10-year,25-year,50-year,1pct_min,100-year,1pct_plu,500-year
River Rch & RM= Purtis Creek Tri,Reach-1,1852
     242     306     356     206     411     819     548
Boundary for River Rch & Prof#=Purtis Creek Tri,Reach-1,1
Up Type=0
Dn Type=3
Dn Slope=0.005
Boundary for River Rch & Prof#=Purtis Creek Tri,Reach-1,2
Up Type=0
Dn Type=3
Dn Slope=0.005
Boundary for River Rch & Prof#=Purtis Creek Tri,Reach-1,3
Up Type=0
Dn Type=3
Dn Slope=0.005
Boundary for River Rch & Prof#=Purtis Creek Tri,Reach-1,4
Up Type=0
Dn Type=3
Dn Slope=0.005
Boundary for River Rch & Prof#=Purtis Creek Tri,Reach-1,5
Up Type=0
Dn Type=3
Dn Slope=0.005
Boundary for River Rch & Prof#=Purtis Creek Tri,Reach-1,6
Up Type=0
Dn Type=3
Dn Slope=0.005
Boundary for River Rch & Prof#=Purtis Creek Tri,Reach-1,7
Up Type=0
Dn Type=3
Dn Slope=0.005

--- Purtis Creek Trib E1.g01 (geometry) ---

Geom Title=Existing Conditions

River Reach=Purtis Creek Tri,Reach-1
Reach XY= 30
      2747826.00      6825361.00      2747910.01      6825444.33
      2747918.49      6825464.33      2747903.62      6825484.34
      2747782.06      6825602.86      2747723.81      6825617.10
      2747674.27      6825656.81      2747623.71      6825666.85
      2747539.29      6825747.64      2747515.52      6825760.06
      2747431.97      6825758.81      2747378.18      6825716.38
      2747348.80      6825710.63      2747323.80      6825716.41
      2747274.26      6825757.56      2747241.34      6825760.76
      2747219.94      6825752.85      2747182.55      6825720.33
      2747169.27      6825720.15      2746989.21      6825897.37
      2746970.36      6825908.36      2746919.91      6825919.16
      2746845.28      6825990.93      2746833.91      6826014.22
      2746872.41      6826062.65      2746875.98      6826095.64
      2746865.77      6826120.67      2746792.47      6826194.25
      2746778.07      6826216.86      2746776.00      6826511.00

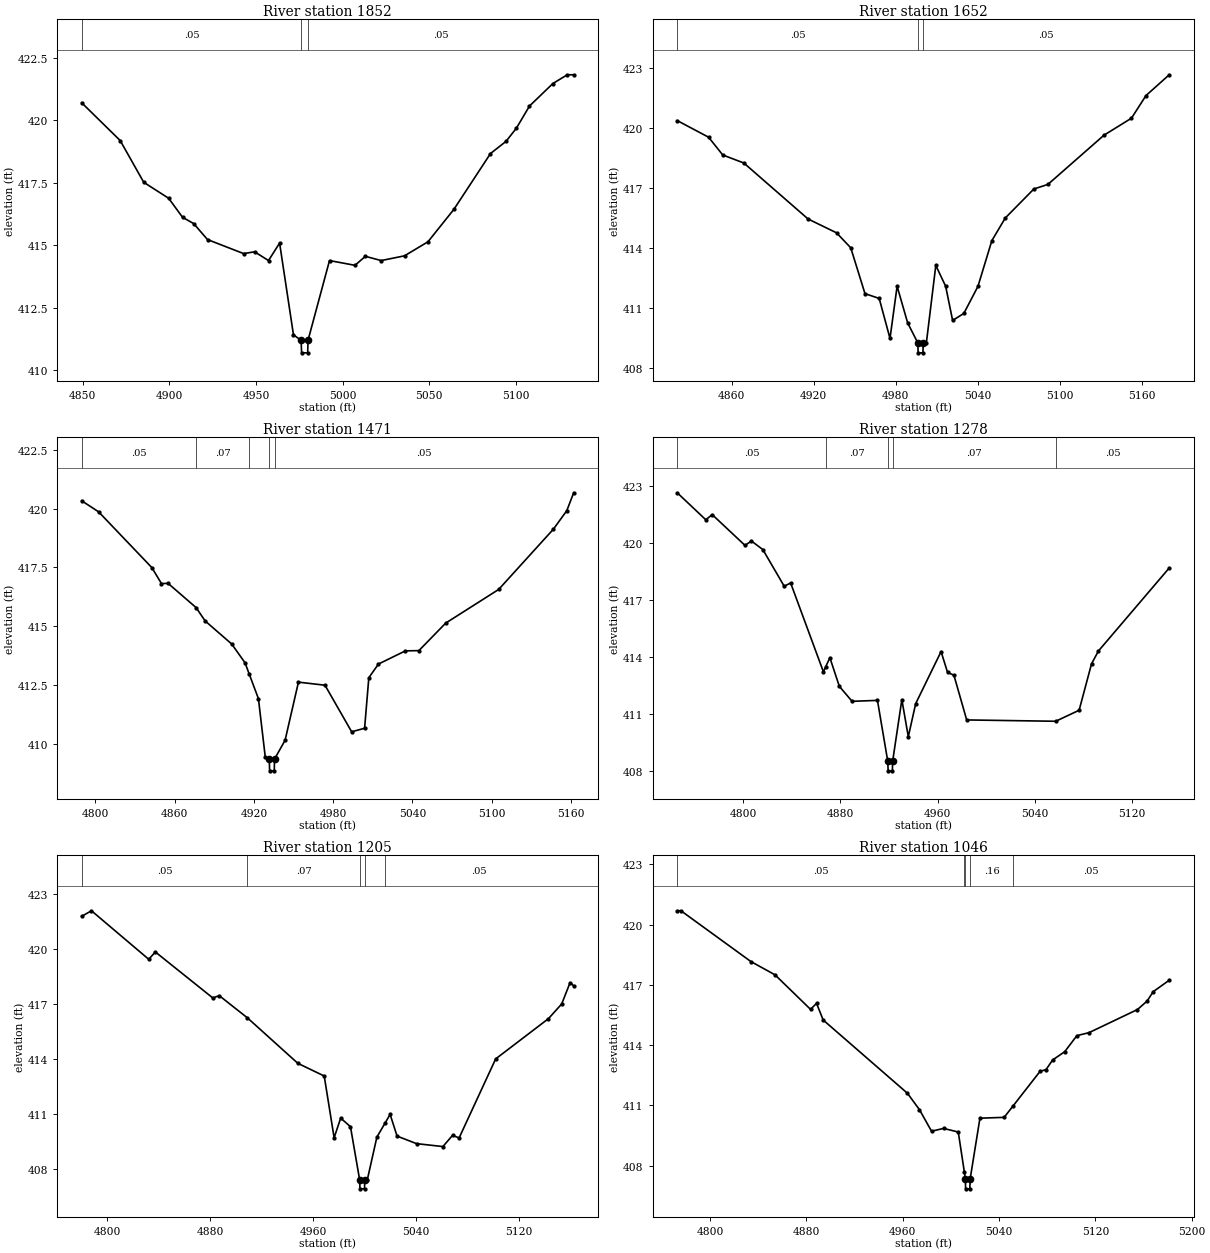
Type RM Length L Ch R = 1,1852,200,200,200
BEGIN DESCRIPTION:
Purtis Creek Trib E11852.014
END DESCRIPTION:
XS GIS Cut Line= 3
      2747782.15      6825393.69      2747876.00      6825511.00
      2747950.15      6825622.22
#Sta/Elev= 30
  4849.4  420.70  4871.6  419.19  4885.2  417.52  4899.6  416.88  4907.6  416.12
  4914.0  415.87  4922.0  415.23  4942.8  414.67  4949.2  414.74  4957.2  414.39
  4963.6  415.09  4971.6  411.42  4976.0  411.20  4976.3  410.70  4979.8  410.70
  4980.0  411.20  4992.4  414.39  5007.1  414.20  5013.1  414.56  5022.2  414.39
  5035.7  414.58  5049.2  415.14  5064.2  416.44  5085.3  418.67  5094.3  419.16
  5100.3  419.69  5107.8  420.57  5121.3  421.47  5129.6  421.82  5133.3  421.82
#Mann=3,-1,0
  4849.4    0.05       0  4976.0    0.05       0  4980.0    0.05       0
Bank Sta=4976,4980
Exp/Cntr=0.3,0.1

Type RM Length L Ch R = 1,1652,181,181,181
BEGIN DESCRIPTION:
Purtis Creek Trib E11651.54
END DESCRIPTION:
XS GIS Cut Line= 3
      2747667.72      6825448.96      2747717.53      6825624.24
      2747755.96      6825797.61
#Sta/Elev= 30
  4820.3  420.38  4843.2  419.55  4853.6  418.66  4869.0  418.26  4916.0  415.46
  4936.8  414.77  4947.2  414.02  4957.6  411.73  4968.0  411.49  4975.9  409.49
  4981.1  412.10  4988.8  410.27  4996.2  409.27  4996.5  408.77  5000.0  408.77
  5000.2  409.27  5002.5  409.27  5009.4  413.14  5016.6  412.10  5021.7  410.39
  5029.9  410.74  5040.2  412.09  5050.4  414.38  5060.2  415.51  5081.1  416.96
  5091.4  417.19  5132.4  419.65  5152.5  420.50  5163.1  421.63  5180.1  422.67
#Mann=3,-1,0
  4820.3    0.05       0  4996.2    0.05       0  5000.2    0.05       0
Bank Sta=4996.2,5000.2
Exp/Cntr=0.3,0.1

Type RM Length L Ch R = 1,1471,193,193,193
BEGIN DESCRIPTION:
Purtis Creek Trib E11470.94
END DESCRIPTION:
XS GIS Cut Line= 3
      2747542.84      6825508.33      2747570.80      6825720.72
      2747600.98      6825876.10
#Sta/Elev= 30
  4789.6  420.33  4802.4  419.86  4842.7  417.49  4850.0  416.81  4855.0  416.82
  4876.2  415.79  4883.1  415.22  4903.2  414.24  4913.3  413.44  4916.4  412.97
  4923.4  411.92  4928.6  409.43  4931.6  409.35  4931.9  408.85  4935.4  408.85
  4935.6  409.35  4943.6  410.15  4953.7  412.62  4973.8  412.49  4994.0  410.51
  5003.8  410.66  5007.0  412.81  5014.3  413.39  5034.7  413.95  5044.9  413.96
  5065.2  415.13  5105.3  416.56  5146.7  419.12  5156.9  419.91  5162.1  420.67
#Mann=5,-1,0
  4789.6    0.05       0  4876.2    0.07       0  4916.4    0.05       0
  4931.6    0.05       0  4935.6    0.05       0
Bank Sta=4931.6,4935.6
Exp/Cntr=0.3,0.1

Type RM Length L Ch R = 1,1278,73,73,73
BEGIN DESCRIPTION:
Purtis Creek Trib E11277.84
END DESCRIPTION:
XS GIS Cut Line= 3
      2747478.16      6825493.76      2747400.61      6825738.71
      2747368.47      6825883.45
#Sta/Elev= 30
  4745.6  422.63  4769.1  421.21  4774.4  421.48  4801.4  419.86  4806.7  420.09
  4816.1  419.64  4833.7  417.71  4839.0  417.88  4866.0  413.20  4867.9  413.47
  4871.3  413.95  4879.1  412.44  4889.6  411.65  4910.5  411.70  4919.0  408.49
  4919.3  407.99  4922.8  407.99  4923.0  408.49  4930.6  411.74  4935.9  409.79
  4942.0  411.53  4962.9  414.27  4968.2  413.18  4973.5  413.02  4984.0  410.67
  5057.3  410.60  5076.6  411.18  5086.8  413.62  5092.5  414.30  5150.8  418.67
#Mann=5,-1,0
  4745.6    0.05       0  4867.9    0.07       0  4919.0    0.07       0
  4923.0    0.07       0  5057.3    0.05       0
Bank Sta=4919,4923
Exp/Cntr=0.3,0.1

Type RM Length L Ch R = 1,1205,159,159,159
BEGIN DESCRIPTION:
Purtis Creek Trib E11204.6
END DESCRIPTION:
XS GIS Cut Line= 3
      2747382.17      6825496.70      2747336.17      6825713.79
      2747300.71      6825870.11
#Sta/Elev= 30
  4780.1  421.77  4787.7  422.07  4832.2  419.43  4837.3  419.83  4881.9  417.33
  4887.0  417.45  4908.9  416.24  4948.0  413.77  4968.5  413.08  4976.2  409.72
  4981.3  410.79  4988.9  410.32  4996.0  407.44  4996.3  406.94  4999.8  406.94
  5000.0  407.44  5002.0  407.44  5009.4  409.75  5015.7  410.51  5019.7  410.99
  5025.1  409.81  5040.2  409.40  5060.7  409.24  5068.2  409.85  5073.3  409.71
  5101.7  414.01  5142.7  416.20  5153.0  417.00  5159.5  418.16  5162.3  417.99
#Mann=5,-1,0
  4780.1    0.05       0  4908.9    0.07       0  4996.0    0.07       0
  5000.0    0.07       0  5015.7    0.05       0
Bank Sta=4996,5000
Exp/Cntr=0.3,0.1

Type RM Length L Ch R = 1,1046,191,191,191
BEGIN DESCRIPTION:
Purtis Creek Trib E11046.14
END DESCRIPTION:
XS GIS Cut Line= 3
      2747199.64      6825509.80      2747202.37      6825740.38
      2747222.76      6825917.21
#Sta/Elev= 30
  4772.7  420.69  4775.8  420.69  4833.9  418.16  4853.9  417.50  4883.4  415.78
  4888.4  416.08  4893.9  415.25  4963.9  411.60  4973.9  410.78  4983.9  409.71
  4993.9  409.85  5006.1  409.67  5011.1  407.70  5012.0  407.34  5012.2  406.84
  5015.7  406.84  5016.0  407.34  5024.1  410.36  5044.2  410.40  5051.5  410.96
  5074.0  412.69  5079.0  412.78  5084.5  413.26  5094.5  413.67  5104.6  414.47
  5114.7  414.62  5154.9  415.77  5162.9  416.19  5168.0  416.66  5181.3  417.23
#Mann=5,-1,0
  4772.7    0.05       0  5011.1    0.16       0  5012.0    0.05       0
  5016.0    0.16       0  5051.5    0.05       0
Bank Sta=5012,5016
Exp/Cntr=0.3,0.1

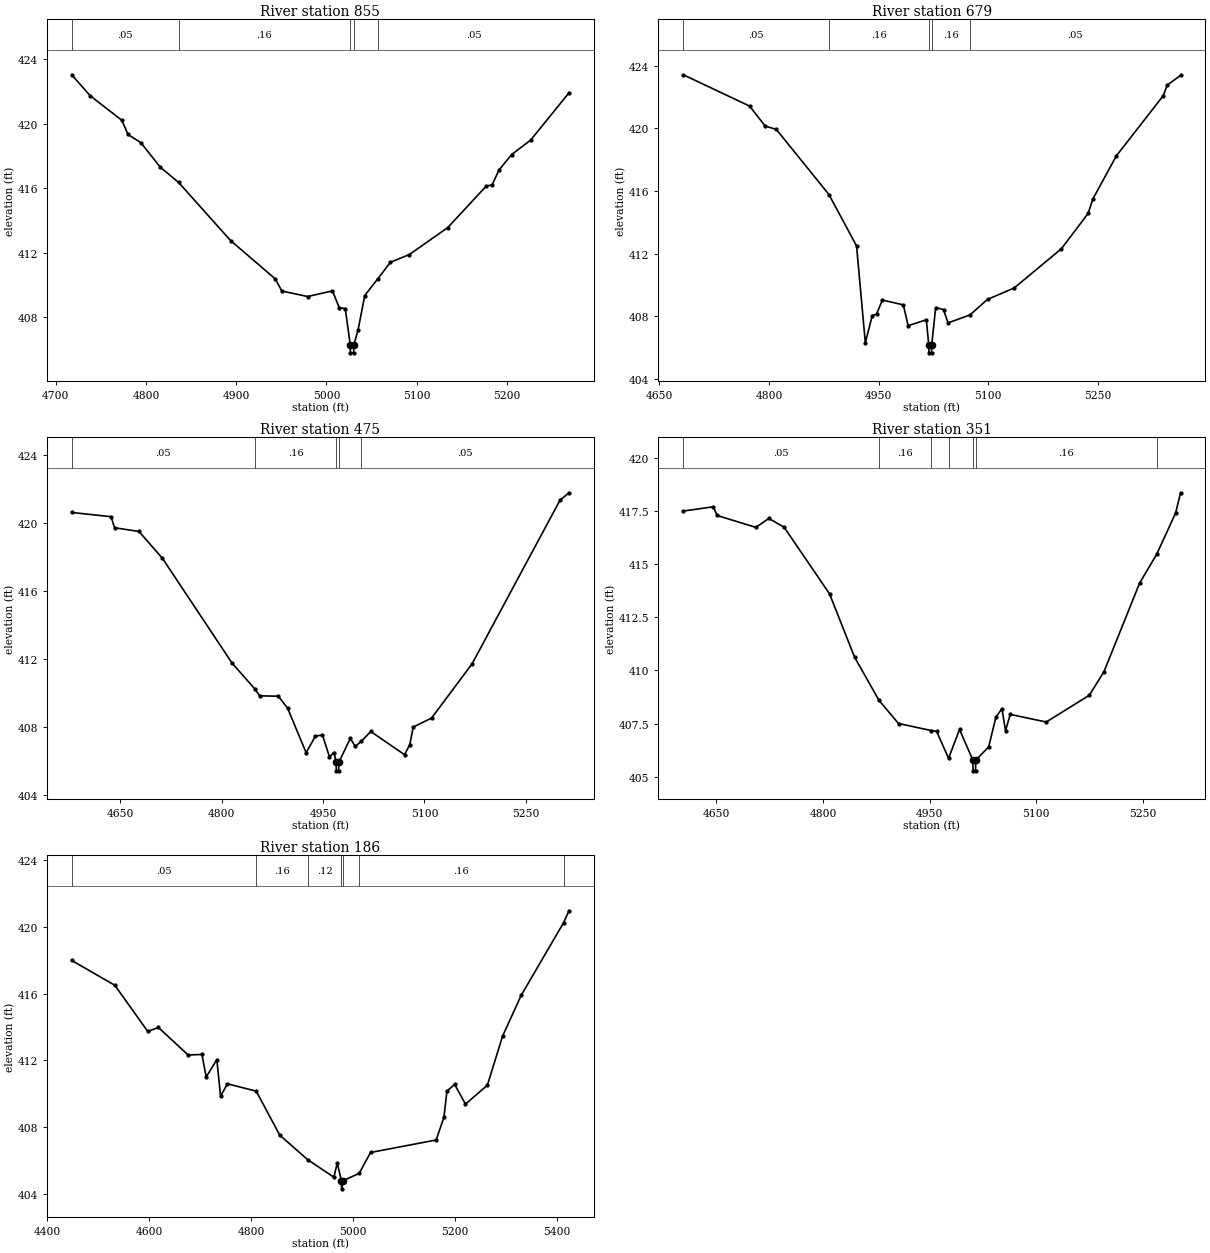
Type RM Length L Ch R = 1,855,176,176,176
BEGIN DESCRIPTION:
Purtis Creek Trib E1854.6
END DESCRIPTION:
XS GIS Cut Line= 3
      2746874.27      6825614.19      2747060.69      6825825.73
      2747260.22      6826006.65
#Sta/Elev= 30
  4717.6  423.03  4738.1  421.73  4773.2  420.21  4780.0  419.33  4794.1  418.83
  4815.9  417.30  4836.1  416.36  4893.7  412.76  4943.1  410.39  4950.6  409.63
  4979.1  409.29  5006.7  409.64  5014.2  408.60  5020.9  408.54  5026.4  406.30
  5026.6  405.80  5030.1  405.80  5030.4  406.30  5035.1  407.22  5042.5  409.35
  5057.0  410.39  5070.9  411.41  5091.9  411.89  5134.5  413.56  5177.0  416.12
  5183.8  416.22  5191.2  417.12  5205.4  418.09  5226.4  418.98  5268.9  421.91
#Mann=5,-1,0
  4717.6    0.05       0  4836.1    0.16       0  5026.4    0.07       0
  5030.4    0.16       0  5057.0    0.05       0
Bank Sta=5026.4,5030.4
Exp/Cntr=0.3,0.1

Type RM Length L Ch R = 1,679,204,204,204
BEGIN DESCRIPTION:
Purtis Creek Trib E1643.61
END DESCRIPTION:
XS GIS Cut Line= 3
      2746752.89      6825649.38      2746919.91      6825919.16
      2747257.61      6826052.87
#Sta/Elev= 30
  4682.7  423.42  4773.5  421.42  4794.7  420.15  4810.1  419.93  4882.0  415.78
  4919.8  412.50  4931.8  406.32  4941.3  408.06  4947.2  408.15  4955.1  409.05
  4983.8  408.74  4990.4  407.41  5015.3  407.79  5018.6  406.18  5018.9  405.68
  5022.4  405.68  5022.6  406.18  5028.1  408.57  5038.8  408.44  5045.0  407.59
  5075.0  408.10  5099.0  409.09  5135.6  409.82  5200.1  412.32  5236.8  414.58
  5243.2  415.50  5275.4  418.25  5339.6  422.09  5344.9  422.76  5363.2  423.38
#Mann=5,-1,0
  4682.7    0.05       0  4882.0    0.16       0  5018.6    0.07       0
  5022.6    0.16       0  5075.0    0.05       0
Bank Sta=5018.6,5022.6
Exp/Cntr=0.3,0.1

Type RM Length L Ch R = 1,475,124,124,124
BEGIN DESCRIPTION:
Purtis Creek Trib E1474.73
END DESCRIPTION:
XS GIS Cut Line= 3
      2746465.90      6825971.52      2746875.30      6826073.76
      2747189.31      6826082.40
#Sta/Elev= 30
  4577.9  420.63  4636.2  420.38  4641.3  419.73  4677.4  419.51  4712.0  417.94
  4815.1  411.76  4848.9  410.23  4856.3  409.82  4883.7  409.80  4897.5  409.09
  4924.9  406.47  4938.7  407.45  4949.1  407.51  4959.4  406.23  4966.2  406.48
  4969.3  405.90  4969.6  405.40  4973.1  405.40  4973.3  405.90  4990.3  407.31
  4997.7  406.84  5006.5  407.14  5020.6  407.72  5070.6  406.35  5078.4  406.95
  5083.4  407.98  5110.6  408.51  5170.6  411.71  5300.7  421.35  5314.0  421.79
#Mann=5,-1,0
  4577.9    0.05       0  4848.9    0.16       0  4969.3    0.07       0
  4973.3    0.16       0  5006.5    0.05       0
Bank Sta=4969.3,4973.3
Exp/Cntr=0.3,0.1

Type RM Length L Ch R = 1,351,165,165,165
BEGIN DESCRIPTION:
Mapping XS e800138e
END DESCRIPTION:
XS GIS Cut Line= 3
      2746443.90      6826029.87      2746815.26      6826173.87
      2747112.85      6826129.38
#Sta/Elev= 30
  4603.6  417.51  4645.8  417.71  4651.2  417.30  4705.6  416.74  4723.8  417.16
  4745.3  416.75  4809.2  413.61  4844.5  410.62  4878.8  408.59  4906.2  407.50
  4952.0  407.17  4959.8  407.13  4976.6  405.86  4992.0  407.22  5010.8  405.77
  5011.0  405.27  5014.5  405.27  5014.8  405.77  5033.0  406.40  5043.1  407.79
  5051.6  408.20  5056.7  407.16  5063.3  407.93  5113.9  407.57  5174.5  408.83
  5195.1  409.94  5245.3  414.12  5269.5  415.49  5295.9  417.42  5302.8  418.37
#Mann=7,-1,0
  4603.6    0.05       0  4878.8    0.16       0  4952.0    0.12       0
  4976.6    0.16       0  5010.8    0.07       0  5014.8    0.16       0
  5269.5    0.05       0
Bank Sta=5010.8,5014.8
Exp/Cntr=0.3,0.1

Type RM Length L Ch R = 1,186,0,0,0
BEGIN DESCRIPTION:
Purtis Creek Trib E1186.382
END DESCRIPTION:
XS GIS Cut Line= 5
      2746371.22      6825996.96      2746583.41      6826280.87
      2746775.96      6826324.62      2746913.95      6826287.07
      2747150.99      6826136.00
#Sta/Elev= 30
  4448.1  418.00  4532.8  416.51  4597.4  413.74  4618.2  413.98  4676.6  412.33
  4703.7  412.36  4712.0  411.01  4732.9  412.05  4740.3  409.86  4753.7  410.60
  4810.2  410.16  4856.5  407.52  4911.2  406.05  4962.6  405.00  4969.3  405.84
  4977.5  404.80  4977.8  404.30  4981.5  404.80  5012.4  405.23  5034.6  406.48
  5163.4  407.23  5178.7  408.59  5184.6  410.17  5199.8  410.56  5221.0  409.38
  5264.0  410.52  5293.8  413.46  5330.2  415.90  5413.6  420.27  5424.1  420.98
#Mann=7,-1,0
  4448.1    0.05       0  4810.2    0.16       0  4911.2    0.12       0
  4977.5    0.07       0  4981.5    0.12       0  5012.4    0.16       0
  5413.6    0.05       0
Bank Sta=4977.5,4981.5
Exp/Cntr=0.3,0.1

Chan Stop Cuts=-1