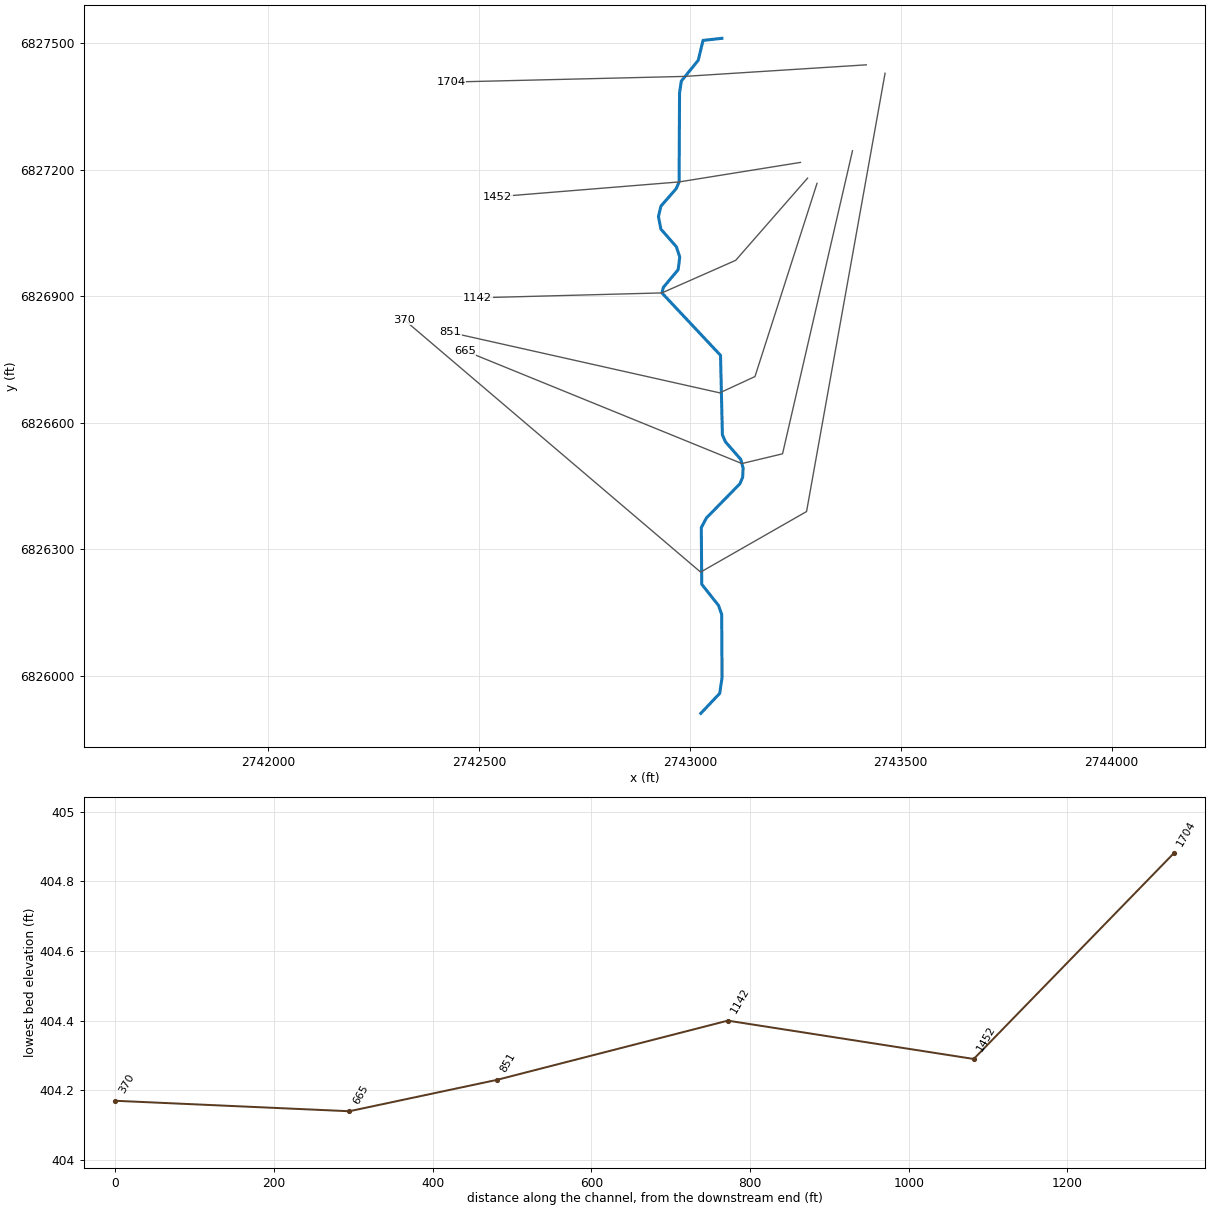
--- Purtis Creek Trib F.prj (project) ---

Proj Title=Purtis Creek Trib F Base Level Engineering
Current Plan=p01
Default Exp/Contr=0.3,0.1
English Units
Geom File=g01
Flow File=f01
Plan File=p01
BEGIN DESCRIPTION:
Purtis Creek Trib F
END DESCRIPTION:

--- Purtis Creek Trib F.p01 (plan) ---

Plan Title=Multiple Run
Short Identifier=Multiple
Geom File=g01
Flow File=f01
Subcritical Flow
K Sum by GR= 0
Std Step Tol= 0.01
Critical Tol= 0.01
Num of Std Step Trials= 20
Max Error Tol= 0.3
Flow Tol Ratio= 0.001
Split Flow NTrial= 30
Split Flow Tol= 0.02
Split Flow Ratio= 0.02
Log Output Level= 0
Friction Slope Method= 1
Unsteady Friction Slope Method= 2
Unsteady Bridges Friction Slope Method= 1
Parabolic Critical Depth
Global Vel Dist=  1 , 1 , 1
Global Log Level= 0
CheckData=True
Encroach Param= -1, 0, 0, 0
BEGIN DESCRIPTION:
Multiple Run
END DESCRIPTION:

--- Purtis Creek Trib F.f01 (steady flow) ---

Flow Title=Multiple
Number of Profiles=7
Profile Names=10-year,25-year,50-year,1pct_min,100-year,1pct_plu,500-year
River Rch & RM= Purtis Creek Tri,Reach-1,1704
     146     180     205     117     232     464     299
River Rch & RM= Purtis Creek Tri,Reach-1,851
     315     405     475     277     552    1102     748
Boundary for River Rch & Prof#=Purtis Creek Tri,Reach-1,1
Up Type=0
Dn Type=3
Dn Slope=0.005
Boundary for River Rch & Prof#=Purtis Creek Tri,Reach-1,2
Up Type=0
Dn Type=3
Dn Slope=0.005
Boundary for River Rch & Prof#=Purtis Creek Tri,Reach-1,3
Up Type=0
Dn Type=3
Dn Slope=0.005
Boundary for River Rch & Prof#=Purtis Creek Tri,Reach-1,4
Up Type=0
Dn Type=3
Dn Slope=0.005
Boundary for River Rch & Prof#=Purtis Creek Tri,Reach-1,5
Up Type=0
Dn Type=3
Dn Slope=0.005
Boundary for River Rch & Prof#=Purtis Creek Tri,Reach-1,6
Up Type=0
Dn Type=3
Dn Slope=0.005
Boundary for River Rch & Prof#=Purtis Creek Tri,Reach-1,7
Up Type=0
Dn Type=3
Dn Slope=0.005

--- Purtis Creek Trib F.g01 (geometry) ---

Geom Title=Existing Conditions

River Reach=Purtis Creek Tri,Reach-1
Reach XY= 30
      2743076.00      6827511.00      2743031.28      6827506.10
      2743019.96      6827459.00      2742979.72      6827409.48
      2742975.63      6827381.16      2742974.60      6827170.65
      2742967.81      6827154.92      2742931.38      6827113.18
      2742925.63      6827088.19      2742931.41      6827058.80
      2742968.12      6827016.93      2742976.09      6826992.54
      2742972.38      6826962.63      2742937.39      6826920.87
      2742933.82      6826907.59      2743072.73      6826759.64
      2743077.19      6826571.48      2743084.18      6826554.92
      2743120.65      6826513.17      2743126.25      6826492.54
      2743125.24      6826470.78      2743118.50      6826454.95
      2743039.40      6826374.31      2743027.20      6826351.40
      2743028.25      6826216.94      2743067.86      6826167.06
      2743075.48      6826145.78      2743076.41      6825995.83
      2743070.86      6825958.41      2743026.00      6825911.00

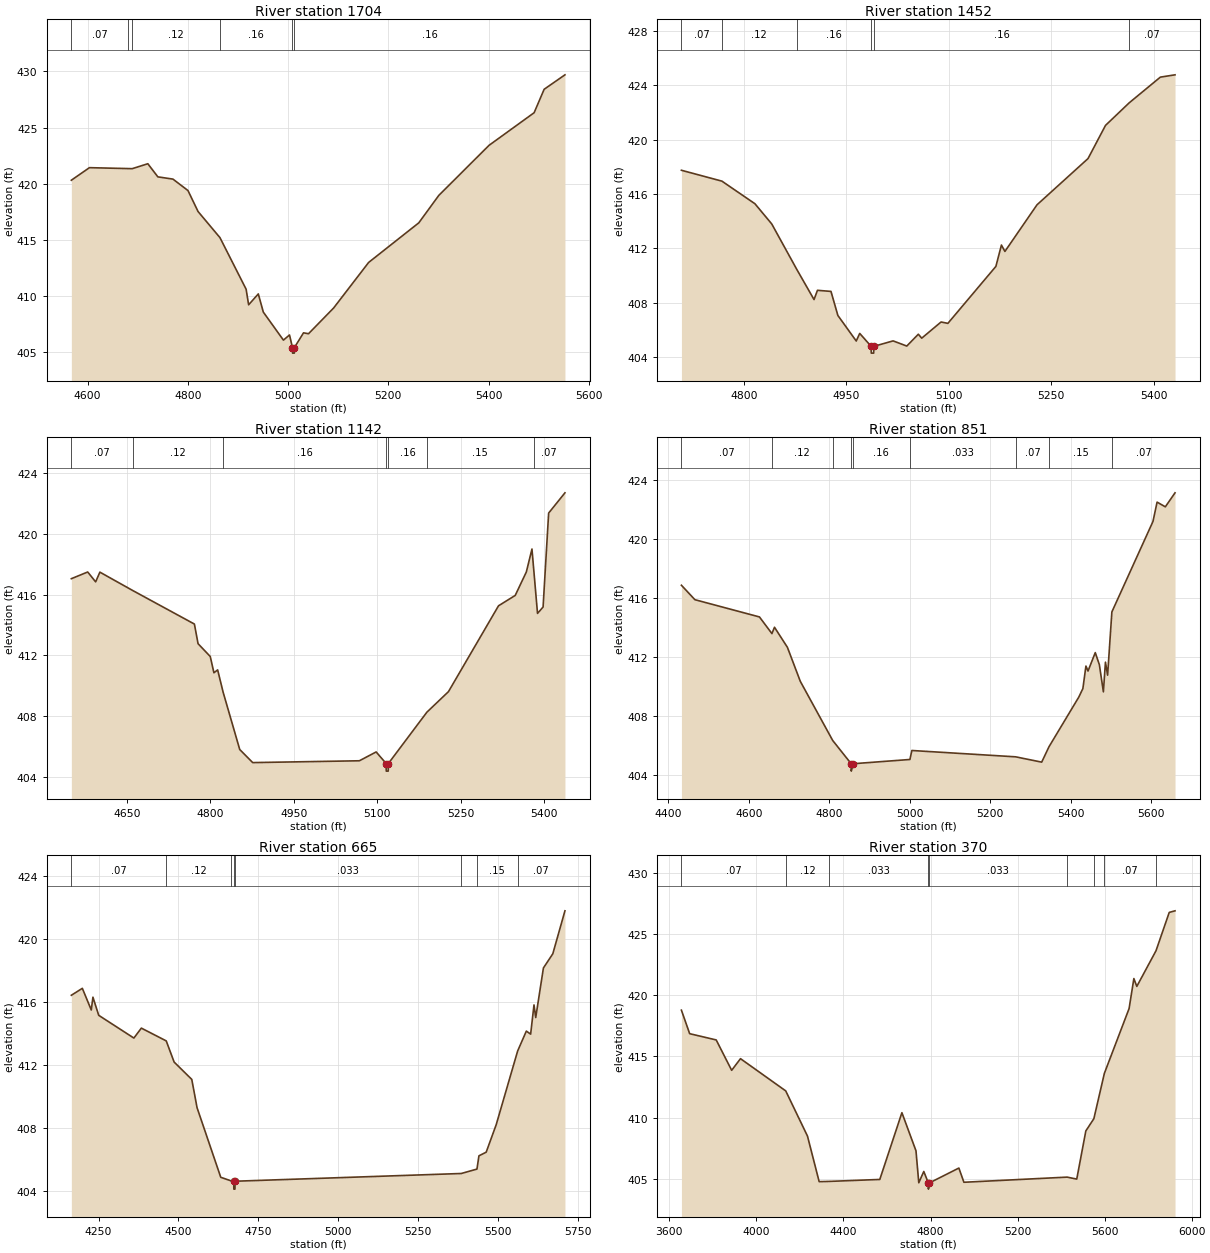
Type RM Length L Ch R = 1,1704,252,252,252
BEGIN DESCRIPTION:
Purtis Creek Trib F1704.426
END DESCRIPTION:
XS GIS Cut Line= 3
      2743418.27      6827448.21      2742986.74      6827420.73
      2742434.50      6827407.40
#Sta/Elev= 30
  4567.6  420.30  4603.7  421.42  4680.5  421.34  4689.0  421.33  4720.2  421.77
  4740.2  420.60  4770.3  420.40  4800.3  419.38  4820.4  417.51  4864.1  415.18
  4916.3  410.58  4921.3  409.19  4940.6  410.16  4950.6  408.54  4990.7  406.04
  5002.9  406.50  5008.7  405.38  5009.0  404.88  5012.5  404.88  5012.7  405.38
  5030.8  406.69  5040.8  406.61  5090.8  408.90  5160.8  412.97  5260.8  416.50
  5300.8  418.95  5400.9  423.41  5490.9  426.32  5510.9  428.41  5552.4  429.70
#Mann=6,-1,0
  4567.6    0.07       0  4680.5    0.16       0  4689.0    0.12       0
  4864.1    0.16       0  5008.7    0.07       0  5012.7    0.16       0
Bank Sta=5008.7,5012.7
Exp/Cntr=0.3,0.1

Type RM Length L Ch R = 1,1452,310,310,310
BEGIN DESCRIPTION:
Purtis Creek Trib F1350.29
END DESCRIPTION:
XS GIS Cut Line= 3
      2743262.20      6827216.92      2742974.60      6827170.65
      2742544.52      6827135.62
#Sta/Elev= 30
  4708.7  417.74  4768.0  416.94  4816.3  415.28  4841.0  413.79  4877.5  410.46
  4902.9  408.23  4907.9  408.91  4927.7  408.83  4937.8  407.06  4964.7  405.18
  4969.8  405.74  4986.5  404.79  4986.7  404.29  4990.2  404.29  4990.5  404.79
  5018.7  405.19  5038.7  404.81  5055.6  405.68  5060.6  405.39  5088.9  406.58
  5098.9  406.48  5169.2  410.67  5177.3  412.24  5182.4  411.77  5229.4  415.20
  5304.1  418.60  5329.7  421.04  5364.4  422.70  5410.0  424.59  5431.5  424.76
#Mann=6,-1,0
  4708.7    0.07       0  4768.0    0.12       0  4877.5    0.16       0
  4986.5    0.07       0  4990.5    0.16       0  5364.4    0.07       0
Bank Sta=4986.5,4990.5
Exp/Cntr=0.3,0.1

Type RM Length L Ch R = 1,1142,291,291,291
BEGIN DESCRIPTION:
Mapping XS f3c2a406
END DESCRIPTION:
XS GIS Cut Line= 4
      2743279.09      6827179.65      2743108.73      6826984.84
      2742933.82      6826907.59      2742496.67      6826896.01
#Sta/Elev= 30
  4550.0  417.04  4579.4  417.48  4593.7  416.83  4601.3  417.47  4660.5  416.26
  4771.2  414.06  4777.8  412.77  4799.7  411.93  4806.3  410.86  4813.0  411.05
  4822.8  409.59  4852.7  405.82  4876.0  404.96  5067.8  405.08  5097.9  405.66
  5115.9  404.90  5116.1  404.40  5119.6  404.40  5119.9  404.90  5189.1  408.27
  5227.9  409.62  5317.9  415.26  5347.9  415.94  5367.9  417.48  5378.0  418.99
  5381.0  417.72  5388.0  414.76  5398.0  415.18  5408.0  421.35  5437.3  422.68
#Mann=7,-1,0
  4550.0    0.07       0  4660.5    0.12       0  4822.8    0.16       0
  5115.9    0.07       0  5119.9    0.16       0  5189.1    0.15       0
  5381.0    0.07       0
Bank Sta=5115.9,5119.9
Exp/Cntr=0.3,0.1

Type RM Length L Ch R = 1,851,186,186,186
BEGIN DESCRIPTION:
Mapping XS c4984a3f
END DESCRIPTION:
XS GIS Cut Line= 4
      2743301.45      6827167.23      2743154.42      6826709.32
      2743070.80      6826670.74      2742432.50      6826813.94
#Sta/Elev= 30
  4432.6  416.84  4466.1  415.86  4626.6  414.69  4657.6  413.56  4664.0  413.99
  4696.1  412.63  4728.2  410.32  4808.7  406.31  4854.7  404.73  4854.9  404.23
  4858.7  404.73  5000.7  405.02  5005.5  405.63  5263.5  405.20  5328.3  404.84
  5346.6  405.89  5420.5  409.25  5430.7  409.83  5438.3  411.36  5443.5  411.02
  5461.5  412.27  5471.7  411.45  5481.7  409.61  5486.8  411.62  5492.2  410.74
  5502.8  415.03  5605.0  421.17  5615.2  422.48  5635.7  422.16  5659.8  423.11
#Mann=9,-1,0
  4432.6    0.07       0  4657.6    0.12       0  4808.7    0.16       0
  4854.7    0.07       0  4858.7    0.16       0  5000.7   0.033       0
  5263.5    0.07       0  5346.6    0.15       0  5502.8    0.07       0
Bank Sta=4854.7,4858.7
Exp/Cntr=0.3,0.1

Type RM Length L Ch R = 1,665,295,295,295
BEGIN DESCRIPTION:
Mapping XS e3863d92
END DESCRIPTION:
XS GIS Cut Line= 4
      2743385.57      6827244.54      2743219.76      6826526.23
      2743123.31      6826503.14      2742466.56      6826770.61
#Sta/Elev= 30
  4164.9  416.42  4199.3  416.86  4227.3  415.49  4232.5  416.30  4250.6  415.15
  4360.7  413.71  4384.1  414.34  4462.0  413.53  4486.7  412.19  4542.0  411.09
  4558.5  409.30  4632.7  404.89  4664.1  404.67  4673.4  404.64  4673.7  404.14
  4677.2  404.14  4677.4  404.64  5385.7  405.13  5434.9  405.41  5441.1  406.25
  5463.8  406.48  5495.1  408.22  5562.3  412.89  5589.5  414.15  5603.0  413.96
  5613.5  415.81  5618.9  415.01  5643.0  418.15  5672.4  419.05  5710.4  421.77
#Mann=8,-1,0
  4164.9    0.07       0  4462.0    0.12       0  4664.1   0.033       0
  4673.4   0.033       0  4677.4   0.033       0  5385.7    0.07       0
  5434.9    0.15       0  5562.3    0.07       0
Bank Sta=4673.4,4677.4
Exp/Cntr=0.3,0.1

Type RM Length L Ch R = 1,370,0,0,0
BEGIN DESCRIPTION:
Purtis Creek Trib F966.3
END DESCRIPTION:
XS GIS Cut Line= 4
      2743462.76      6827428.28      2743276.67      6826389.39
      2743025.53      6826245.84      2742322.26      6826844.55
#Sta/Elev= 30
  3655.3  418.78  3693.2  416.86  3815.1  416.35  3886.2  413.87  3926.8  414.82
  4134.6  412.19  4234.6  408.50  4288.3  404.78  4334.5  404.80  4566.9  404.96
  4668.5  410.41  4733.2  407.30  4746.1  404.69  4769.1  405.61  4790.1  404.67
  4790.4  404.17  4794.1  404.67  4930.3  405.89  4953.4  404.73  5427.6  405.15
  5472.0  404.99  5513.7  408.92  5550.6  409.92  5598.9  413.62  5712.5  418.91
  5734.5  421.36  5748.0  420.72  5836.2  423.63  5897.0  426.76  5923.6  426.89
#Mann=9,-1,0
  3655.3    0.07       0  4134.6    0.12       0  4334.5   0.033       0
  4790.1   0.033       0  4794.1   0.033       0  5427.6    0.07       0
  5550.6    0.15       0  5598.9    0.07       0  5836.2   0.035       0
Bank Sta=4790.1,4794.1
Exp/Cntr=0.3,0.1

Chan Stop Cuts=-1