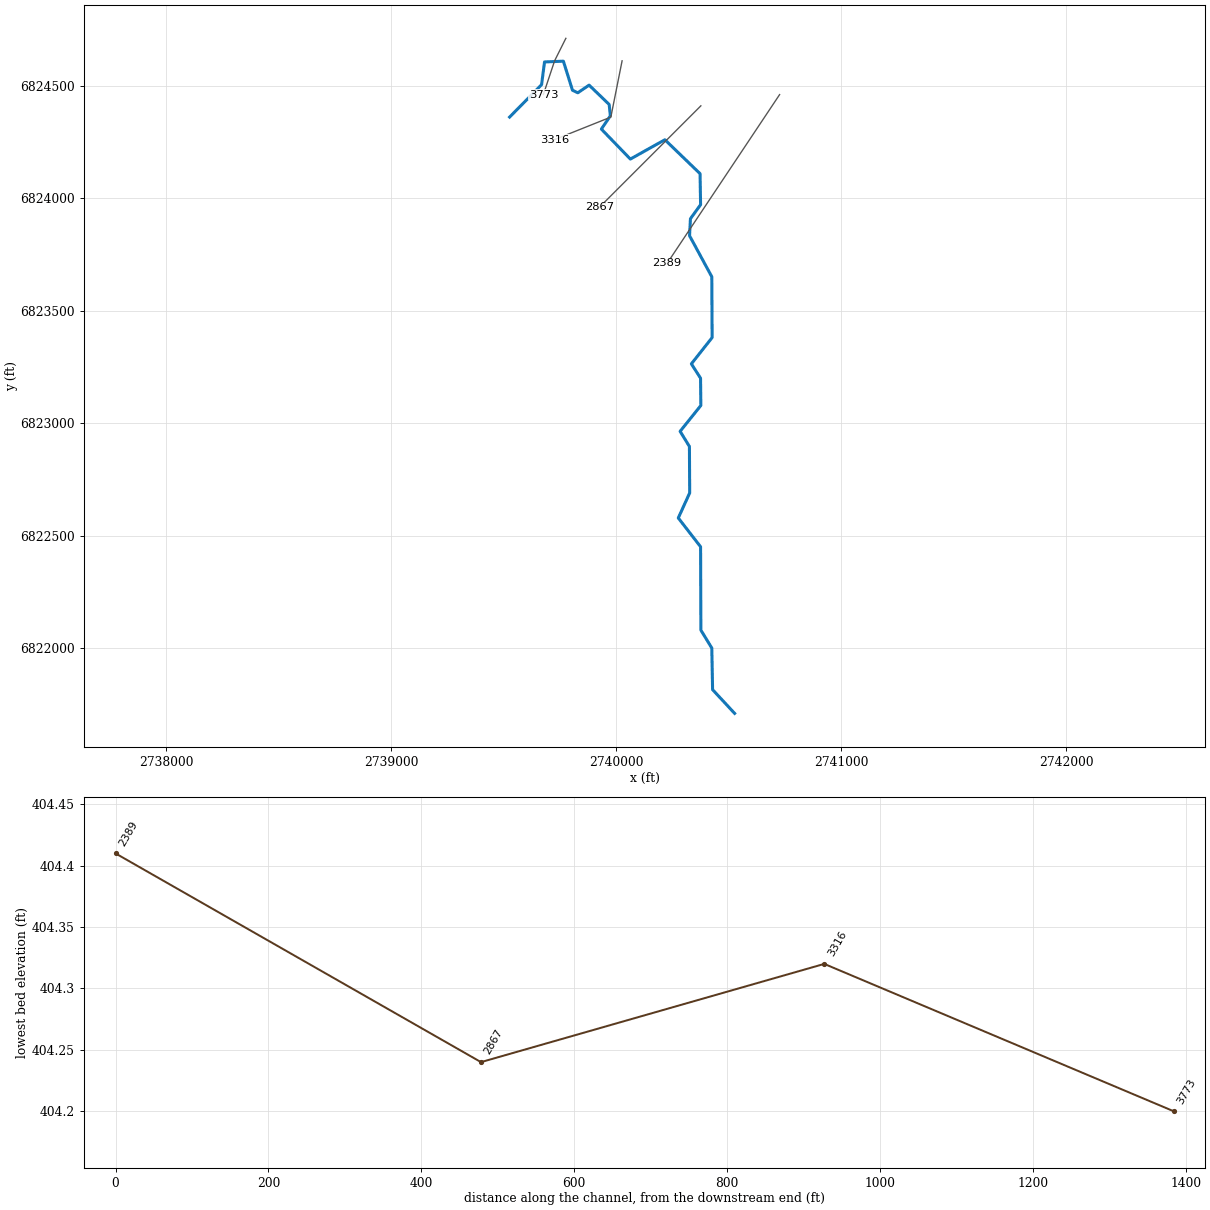
--- Purtis Creek Trib G.prj (project) ---

Proj Title=Purtis Creek Trib G Base Level Engineering
Current Plan=p01
Default Exp/Contr=0.3,0.1
English Units
Geom File=g01
Flow File=f01
Plan File=p01
BEGIN DESCRIPTION:
Purtis Creek Trib G
END DESCRIPTION:

--- Purtis Creek Trib G.p01 (plan) ---

Plan Title=Multiple Run
Short Identifier=Multiple
Geom File=g01
Flow File=f01
Subcritical Flow
K Sum by GR= 0
Std Step Tol= 0.01
Critical Tol= 0.01
Num of Std Step Trials= 20
Max Error Tol= 0.3
Flow Tol Ratio= 0.001
Split Flow NTrial= 30
Split Flow Tol= 0.02
Split Flow Ratio= 0.02
Log Output Level= 0
Friction Slope Method= 1
Unsteady Friction Slope Method= 2
Unsteady Bridges Friction Slope Method= 1
Parabolic Critical Depth
Global Vel Dist=  1 , 1 , 1
Global Log Level= 0
CheckData=True
Encroach Param= -1, 0, 0, 0
BEGIN DESCRIPTION:
Multiple Run
END DESCRIPTION:

--- Purtis Creek Trib G.f01 (steady flow) ---

Flow Title=Multiple
Number of Profiles=7
Profile Names=10-year,25-year,50-year,1pct_min,100-year,1pct_plu,500-year
River Rch & RM= Purtis Creek Tri,Reach-1,3773
     273     348     404     234     468     933     626
Boundary for River Rch & Prof#=Purtis Creek Tri,Reach-1,1
Up Type=0
Dn Type=3
Dn Slope=0.005
Boundary for River Rch & Prof#=Purtis Creek Tri,Reach-1,2
Up Type=0
Dn Type=3
Dn Slope=0.005
Boundary for River Rch & Prof#=Purtis Creek Tri,Reach-1,3
Up Type=0
Dn Type=3
Dn Slope=0.005
Boundary for River Rch & Prof#=Purtis Creek Tri,Reach-1,4
Up Type=0
Dn Type=3
Dn Slope=0.005
Boundary for River Rch & Prof#=Purtis Creek Tri,Reach-1,5
Up Type=0
Dn Type=3
Dn Slope=0.005
Boundary for River Rch & Prof#=Purtis Creek Tri,Reach-1,6
Up Type=0
Dn Type=3
Dn Slope=0.005
Boundary for River Rch & Prof#=Purtis Creek Tri,Reach-1,7
Up Type=0
Dn Type=3
Dn Slope=0.005

--- Purtis Creek Trib G.g01 (geometry) ---

Geom Title=Existing Conditions

River Reach=Purtis Creek Tri,Reach-1
Reach XY= 30
      2739526.00      6824361.00      2739668.12      6824504.88
      2739681.19      6824606.08      2739764.99      6824609.44
      2739805.52      6824480.18      2739829.13      6824469.08
      2739879.34      6824503.00      2739968.50      6824417.08
      2739973.89      6824366.64      2739933.82      6824307.59
      2740062.66      6824174.41      2740216.20      6824260.29
      2740372.47      6824109.53      2740374.79      6823971.51
      2740329.70      6823909.40      2740325.71      6823833.76
      2740424.64      6823651.35      2740426.03      6823380.98
      2740333.81      6823264.41      2740374.62      6823200.56
      2740375.92      6823079.23      2740283.81      6822964.41
      2740325.17      6822897.14      2740326.35      6822690.85
      2740275.70      6822579.38      2740374.79      6822451.41
      2740376.07      6822081.03      2740424.62      6822001.34
      2740428.13      6821816.43      2740526.00      6821711.00

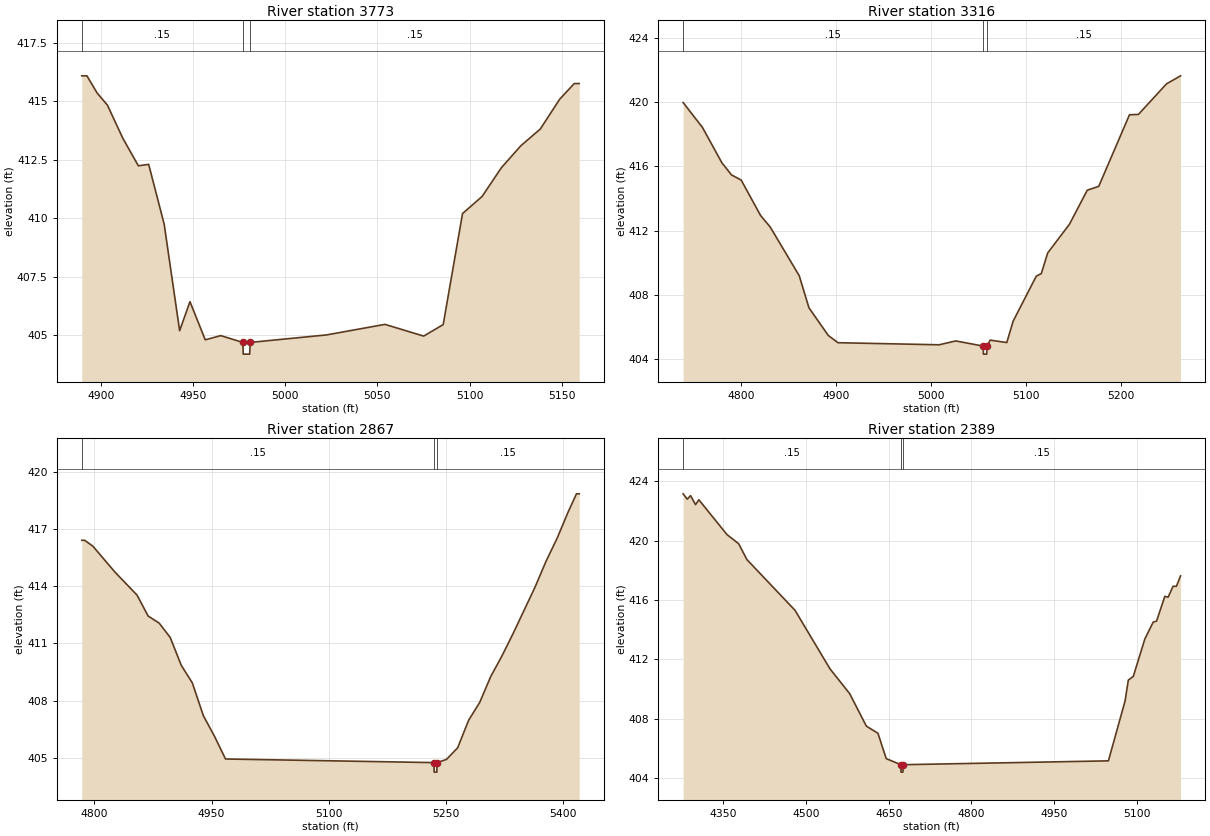
Type RM Length L Ch R = 1,3773,457,457,457
BEGIN DESCRIPTION:
Purtis Creek Trib G 4.0
END DESCRIPTION:
XS GIS Cut Line= 3
      2739775.98      6824710.96      2739726.00      6824611.00
      2739675.99      6824460.98
#Sta/Elev= 28
  4889.6  416.08  4892.4  416.08  4897.9  415.35  4903.5  414.83  4911.9  413.41
  4920.3  412.24  4925.9  412.30  4934.3  409.75  4942.7  405.20  4948.3  406.44
  4956.6  404.81  4965.0  404.99  4977.0  404.70  4977.2  404.20  4980.7  404.20
  4981.0  404.70  5022.4  405.02  5054.1  405.47  5075.1  404.97  5085.7  405.46
  5096.2  410.20  5106.8  410.93  5117.3  412.16  5127.9  413.10  5138.4  413.81
  5148.9  415.08  5156.8  415.75  5159.5  415.75
#Mann=3,-1,0
  4889.6    0.15       0  4977.0    0.05       0  4981.0    0.15       0
Bank Sta=4977,4981
Exp/Cntr=0.3,0.1

Type RM Length L Ch R = 1,3316,449,449,449
BEGIN DESCRIPTION:
Purtis Creek Trib G 3.0
END DESCRIPTION:
XS GIS Cut Line= 3
      2740026.00      6824611.00      2739976.00      6824361.00
      2739726.01      6824261.00
#Sta/Elev= 30
  4739.0  419.96  4759.4  418.41  4779.8  416.22  4790.0  415.46  4800.2  415.14
  4820.6  412.94  4830.8  412.22  4861.4  409.19  4871.6  407.20  4892.0  405.48
  4902.2  405.03  5008.8  404.90  5026.3  405.14  5055.2  404.82  5055.5  404.32
  5059.0  404.32  5059.2  404.82  5062.6  405.19  5080.1  405.04  5086.8  406.37
  5111.1  409.16  5116.5  409.33  5123.2  410.61  5146.1  412.39  5164.9  414.51
  5177.0  414.75  5209.4  419.20  5218.8  419.22  5248.4  421.12  5263.2  421.62
#Mann=3,-1,0
  4739.0    0.15       0  5055.2    0.05       0  5059.2    0.15       0
Bank Sta=5055.2,5059.2
Exp/Cntr=0.3,0.1

Type RM Length L Ch R = 1,2867,478,478,478
BEGIN DESCRIPTION:
Purtis Creek Trib G 2.0
END DESCRIPTION:
XS GIS Cut Line= 3
      2740376.01      6824411.01      2740226.00      6824261.00
      2739926.01      6823961.01
#Sta/Elev= 30
  4784.0  416.42  4787.6  416.42  4798.2  416.11  4826.4  414.75  4854.7  413.54
  4868.9  412.44  4883.0  412.07  4897.2  411.31  4911.3  409.85  4925.4  408.93
  4939.6  407.20  4953.7  406.13  4967.9  404.93  5234.6  404.74  5234.8  404.24
  5238.3  404.24  5238.6  404.74  5250.7  404.91  5264.9  405.52  5279.0  406.97
  5293.1  407.90  5307.3  409.27  5321.4  410.33  5335.6  411.50  5363.8  413.95
  5378.0  415.32  5392.1  416.52  5406.3  417.91  5416.9  418.86  5420.4  418.86
#Mann=3,-1,0
  4784.0    0.15       0  5234.6    0.05       0  5238.6    0.15       0
Bank Sta=5234.6,5238.6
Exp/Cntr=0.3,0.1

Type RM Length L Ch R = 1,2389,0,0,0
BEGIN DESCRIPTION:
Purtis Creek Trib G 1.0
END DESCRIPTION:
XS GIS Cut Line= 3
      2740725.97      6824460.96      2740326.00      6823861.00
      2740226.02      6823711.03
#Sta/Elev= 30
  4277.5  423.16  4285.0  422.80  4291.0  423.04  4300.0  422.43  4306.0  422.76
  4357.1  420.41  4378.1  419.80  4393.1  418.73  4480.3  415.31  4543.4  411.38
  4579.4  409.69  4609.5  407.51  4630.5  407.03  4645.5  405.32  4672.1  404.91
  4672.3  404.41  4675.8  404.41  4676.1  404.91  5048.1  405.17  5078.2  409.19
  5084.2  410.61  5093.2  410.86  5114.2  413.39  5129.3  414.52  5135.3  414.58
  5150.3  416.25  5156.3  416.20  5165.3  416.93  5171.3  416.93  5178.8  417.63
#Mann=3,-1,0
  4277.5    0.15       0  4672.1    0.05       0  4676.1    0.15       0
Bank Sta=4672.1,4676.1
Exp/Cntr=0.3,0.1

Chan Stop Cuts=-1