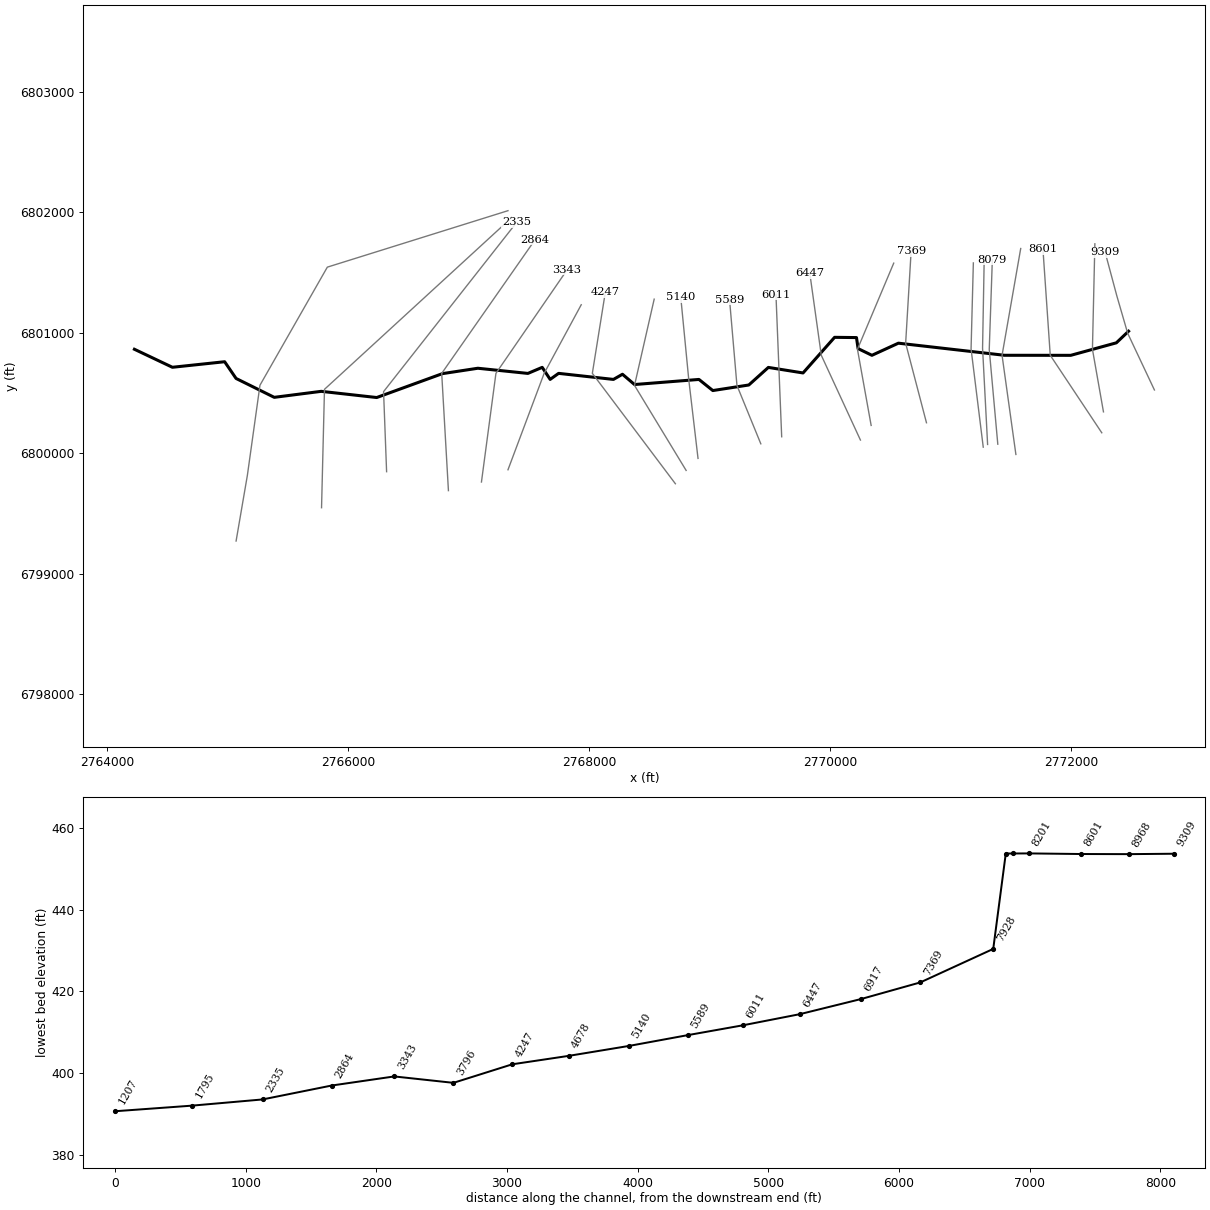
--- Red Oak Branch.prj (project) ---

Proj Title=Red Oak Branch Base Level Engineering
Current Plan=p01
Default Exp/Contr=0.3,0.1
English Units
Geom File=g01
Flow File=f01
Plan File=p01
BEGIN DESCRIPTION:
Red Oak Branch
END DESCRIPTION:

--- Red Oak Branch.p01 (plan) ---

Plan Title=Multiple Run
Short Identifier=Multiple
Geom File=g01
Flow File=f01
Subcritical Flow
K Sum by GR= 0
Std Step Tol= 0.01
Critical Tol= 0.01
Num of Std Step Trials= 20
Max Error Tol= 0.3
Flow Tol Ratio= 0.001
Split Flow NTrial= 30
Split Flow Tol= 0.02
Split Flow Ratio= 0.02
Log Output Level= 0
Friction Slope Method= 1
Unsteady Friction Slope Method= 2
Unsteady Bridges Friction Slope Method= 1
Parabolic Critical Depth
Global Vel Dist=  1 , 1 , 1
Global Log Level= 0
CheckData=True
Encroach Param= -1, 0, 0, 0
BEGIN DESCRIPTION:
Multiple Run
END DESCRIPTION:

--- Red Oak Branch.f01 (steady flow) ---

Flow Title=Multiple
Number of Profiles=7
Profile Names=10-year,25-year,50-year,1pct_min,100-year,1pct_plu,500-year
River Rch & RM= Red Oak Branch,Reach-1,9309
     756    1048    1295     797    1589    3171    2397
River Rch & RM= Red Oak Branch,Reach-1,7369
     918    1283    1594     984    1962    3916    2983
River Rch & RM= Red Oak Branch,Reach-1,3796
    1304    1852    2323    1446    2886    5757    4465
Boundary for River Rch & Prof#=Red Oak Branch,Reach-1,1
Up Type=0
Dn Type=3
Dn Slope=0.005
Boundary for River Rch & Prof#=Red Oak Branch,Reach-1,2
Up Type=0
Dn Type=3
Dn Slope=0.005
Boundary for River Rch & Prof#=Red Oak Branch,Reach-1,3
Up Type=0
Dn Type=3
Dn Slope=0.005
Boundary for River Rch & Prof#=Red Oak Branch,Reach-1,4
Up Type=0
Dn Type=3
Dn Slope=0.005
Boundary for River Rch & Prof#=Red Oak Branch,Reach-1,5
Up Type=0
Dn Type=3
Dn Slope=0.005
Boundary for River Rch & Prof#=Red Oak Branch,Reach-1,6
Up Type=0
Dn Type=3
Dn Slope=0.005
Boundary for River Rch & Prof#=Red Oak Branch,Reach-1,7
Up Type=0
Dn Type=3
Dn Slope=0.005

--- Red Oak Branch.g01 (geometry) ---

Geom Title=Existing Conditions

River Reach=Red Oak Branch,Reach-1
Reach XY= 30
      2772476.00      6801011.00      2772374.55      6800914.49
      2771996.15      6800810.64      2771446.03      6800811.07
      2770565.80      6800911.50      2770346.09      6800810.88
      2770231.28      6800866.52      2770218.00      6800958.01
      2770036.28      6800960.02      2769774.50      6800664.46
      2769486.64      6800710.36      2769324.54      6800564.54
      2769025.90      6800518.33      2768910.84      6800610.61
      2768375.90      6800568.34      2768276.09      6800653.63
      2768201.00      6800610.78      2767745.99      6800661.02
      2767676.00      6800611.00      2767610.06      6800710.87
      2767491.19      6800660.58      2767076.00      6800703.44
      2766781.93      6800658.76      2766236.54      6800460.46
      2765776.00      6800511.82      2765386.44      6800462.05
      2765069.55      6800618.75      2764974.75      6800757.56
      2764541.21      6800711.51      2764226.00      6800861.00

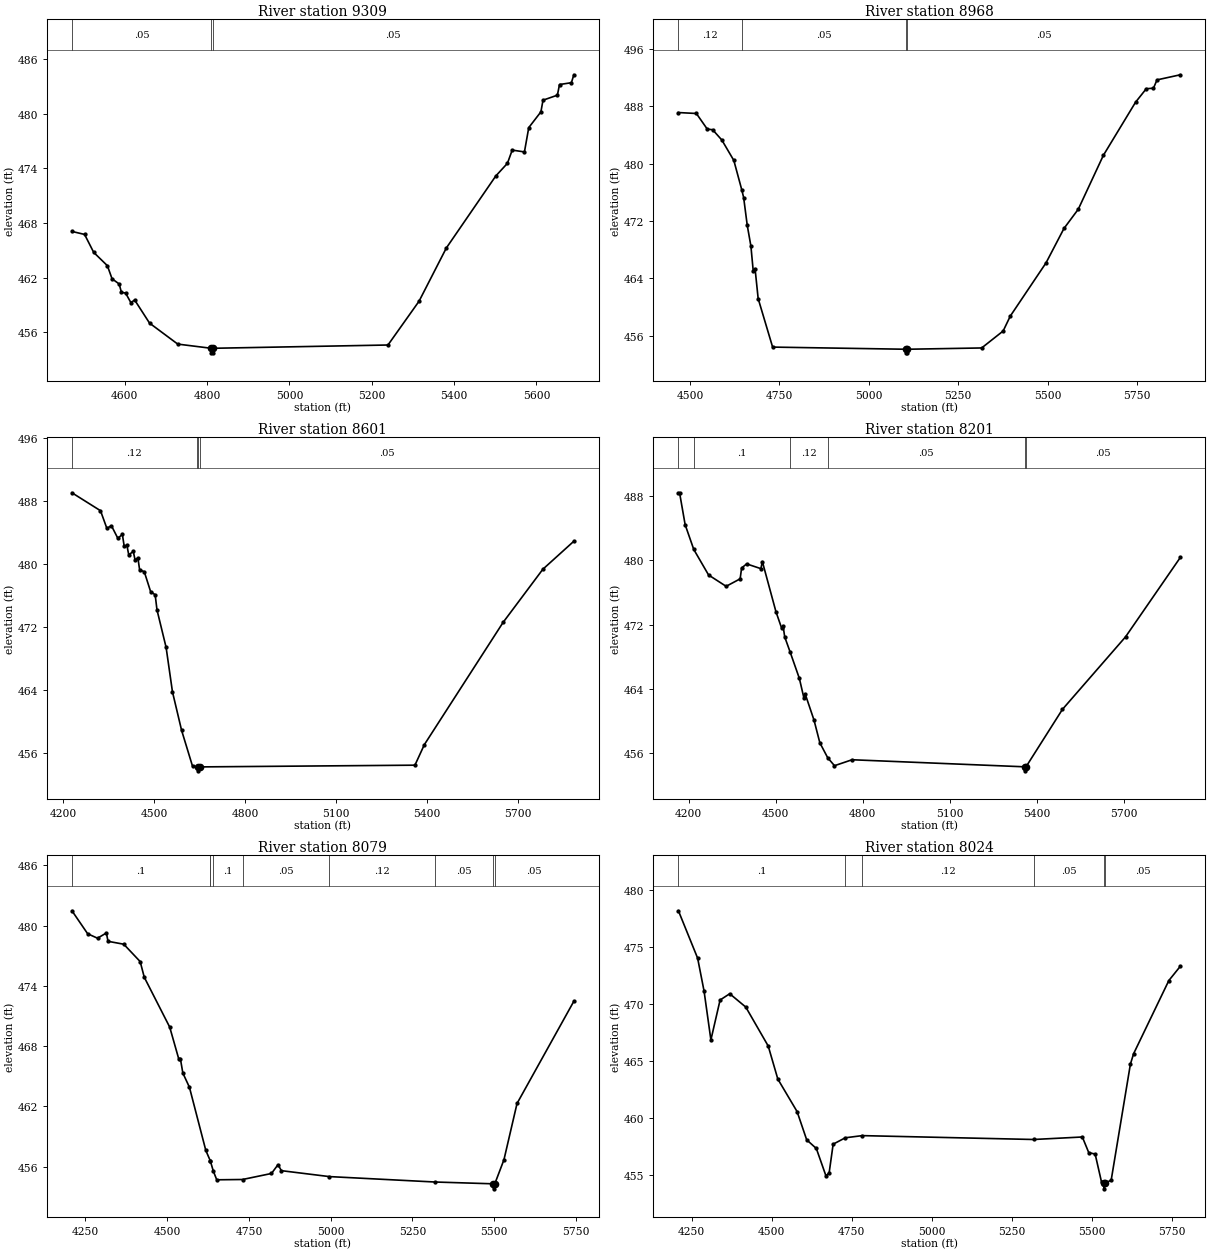
Type RM Length L Ch R = 1,9309,341,341,341
BEGIN DESCRIPTION:
2485
END DESCRIPTION:
XS GIS Cut Line= 4
      2772690.34      6800523.25      2772468.49      6800993.85
      2772378.57      6801303.67      2772281.20      6801666.76
#Sta/Elev= 30
  4472.0  467.07  4502.7  466.74  4524.8  464.77  4558.0  463.31  4569.4  461.87
  4586.7  461.30  4592.2  460.37  4602.2  460.31  4615.0  459.26  4624.3  459.54
  4660.5  457.00  4728.9  454.70  4810.2  454.24  4810.5  453.74  4814.0  453.74
  4814.2  454.24  5239.4  454.60  5314.9  459.41  5381.1  465.25  5501.1  473.15
  5529.5  474.55  5541.1  476.00  5570.8  475.80  5581.3  478.47  5610.8  480.20
  5615.9  481.48  5650.8  482.03  5656.0  483.20  5684.8  483.40  5690.8  484.27
#Mann=3,-1,0
  4472.0    0.05       0  4810.2    0.03       0  4814.2    0.05       0
Bank Sta=4810.2,4814.2
Exp/Cntr=0.3,0.1

Type RM Length L Ch R = 1,8968,367,367,367
BEGIN DESCRIPTION:
899
END DESCRIPTION:
XS GIS Cut Line= 3
      2772267.54      6800341.51      2772176.00      6800861.00
      2772196.22      6801736.08
#Sta/Elev= 30
  4467.8  487.10  4518.0  486.97  4548.5  484.79  4563.4  484.71  4589.1  483.28
  4622.7  480.43  4645.1  476.30  4650.1  475.27  4660.2  471.39  4670.4  468.51
  4676.9  465.03  4682.0  465.37  4690.7  461.19  4731.1  454.44  5103.3  454.14
  5103.6  453.64  5107.1  453.64  5107.3  454.14  5315.4  454.32  5375.4  456.68
  5395.4  458.76  5495.4  466.18  5545.4  470.96  5585.4  473.64  5655.5  481.14
  5745.5  488.54  5775.5  490.42  5795.5  490.49  5805.5  491.65  5870.6  492.36
#Mann=4,-1,0
  4467.8    0.12       0  4645.1    0.05       0  5103.3    0.03       0
  5107.3    0.05       0
Bank Sta=5103.3,5107.3
Exp/Cntr=0.3,0.1

Type RM Length L Ch R = 1,8601,400,400,400
BEGIN DESCRIPTION:
898
END DESCRIPTION:
XS GIS Cut Line= 3
      2772253.46      6800168.00      2771826.00      6800811.00
      2771765.20      6801692.99
#Sta/Elev= 30
  4227.9  489.03  4322.1  486.75  4343.1  484.51  4358.2  484.84  4379.2  483.25
  4394.3  483.73  4400.3  482.23  4409.3  482.33  4415.3  481.14  4430.3  481.57
  4436.3  480.47  4445.4  480.76  4451.4  479.19  4466.4  479.01  4487.5  476.46
  4502.5  476.06  4508.5  474.14  4538.6  469.37  4559.6  463.71  4589.7  458.82
  4625.7  454.27  4639.9  454.17  4644.8  454.17  4645.0  453.67  4648.8  454.17
  5359.7  454.39  5390.9  457.01  5650.5  472.54  5781.9  479.31  5884.1  482.87
#Mann=4,-1,0
  4227.9    0.12       0  4639.9    0.05       0  4644.8    0.03       0
  4648.8    0.05       0
Bank Sta=4644.8,4648.8
Exp/Cntr=0.3,0.1

Type RM Length L Ch R = 1,8201,122,122,122
BEGIN DESCRIPTION:
897
END DESCRIPTION:
XS GIS Cut Line= 3
      2771540.79      6799988.03      2771426.00      6800811.00
      2771580.80      6801697.04
#Sta/Elev= 30
  4164.8  488.42  4168.8  488.42  4188.0  484.45  4217.7  481.37  4268.8  478.19
  4329.3  476.78  4377.6  477.71  4382.7  479.06  4400.0  479.57  4449.1  478.98
  4454.2  479.86  4501.0  473.63  4520.7  471.57  4525.7  471.84  4531.3  470.48
  4549.8  468.62  4581.8  465.32  4597.3  462.91  4602.3  463.34  4632.3  460.13
  4652.4  457.31  4679.6  455.44  4702.9  454.46  4763.5  455.20  5359.2  454.32
  5359.4  453.82  5363.2  454.32  5488.8  461.47  5706.3  470.49  5895.2  480.37
#Mann=6,-1,0
  4164.8    0.12       0  4217.7     0.1       0  4549.8    0.12       0
  4679.6    0.05       0  5359.2    0.03       0  5363.2    0.05       0
Bank Sta=5359.2,5363.2
Exp/Cntr=0.3,0.1

Type RM Length L Ch R = 1,8079,55,55,55
BEGIN DESCRIPTION:
2405
END DESCRIPTION:
XS GIS Cut Line= 3
      2771390.64      6800073.13      2771319.70      6800859.40
      2771345.39      6801604.70
#Sta/Elev= 30
  4208.6  481.49  4256.7  479.20  4286.8  478.76  4313.9  479.28  4318.9  478.45
  4367.1  478.16  4417.3  476.43  4429.8  474.87  4507.7  469.90  4535.6  466.70
  4540.6  466.70  4547.8  465.33  4567.9  463.92  4618.1  457.62  4631.4  456.62
  4632.3  456.53  4641.1  455.56  4651.5  454.70  4730.4  454.73  4818.9  455.33
  4839.0  456.21  4849.1  455.61  4995.7  455.02  5319.0  454.48  5498.0  454.30
  5498.2  453.80  5502.0  454.30  5530.0  456.70  5570.0  462.30  5743.8  472.48
#Mann=9,-1,0
  4208.6     0.1       0  4631.4    0.12       0  4632.3    0.05       0
  4641.1     0.1       0  4730.4    0.05       0  4995.7    0.12       0
  5319.0    0.05       0  5498.0    0.07       0  5502.0    0.05       0
Bank Sta=5498,5502
Exp/Cntr=0.3,0.1

Type RM Length L Ch R = 1,8024,96,96,96
BEGIN DESCRIPTION:
2404
END DESCRIPTION:
XS GIS Cut Line= 3
      2771306.11      6800071.03      2771264.25      6800871.02
      2771278.37      6801636.81
#Sta/Elev= 30
  4208.9  478.19  4268.9  474.03  4289.0  471.14  4310.3  466.86  4339.0  470.36
  4369.1  470.91  4419.2  469.74  4489.3  466.32  4519.3  463.42  4579.4  460.57
  4609.4  458.09  4639.5  457.33  4669.5  454.93  4679.5  455.19  4692.0  457.71
  4729.9  458.27  4782.9  458.46  5317.7  458.12  5470.0  458.34  5490.0  456.97
  5510.0  456.84  5530.0  454.37  5538.1  454.29  5538.3  453.79  5542.1  454.29
  5560.1  454.56  5620.1  464.74  5630.1  465.65  5740.1  472.07  5775.9  473.32
#Mann=6,-1,0
  4208.9     0.1       0  4729.9    0.05       0  4782.9    0.12       0
  5317.7    0.05       0  5538.1    0.07       0  5542.1    0.05       0
Bank Sta=5538.1,5542.1
Exp/Cntr=0.3,0.1

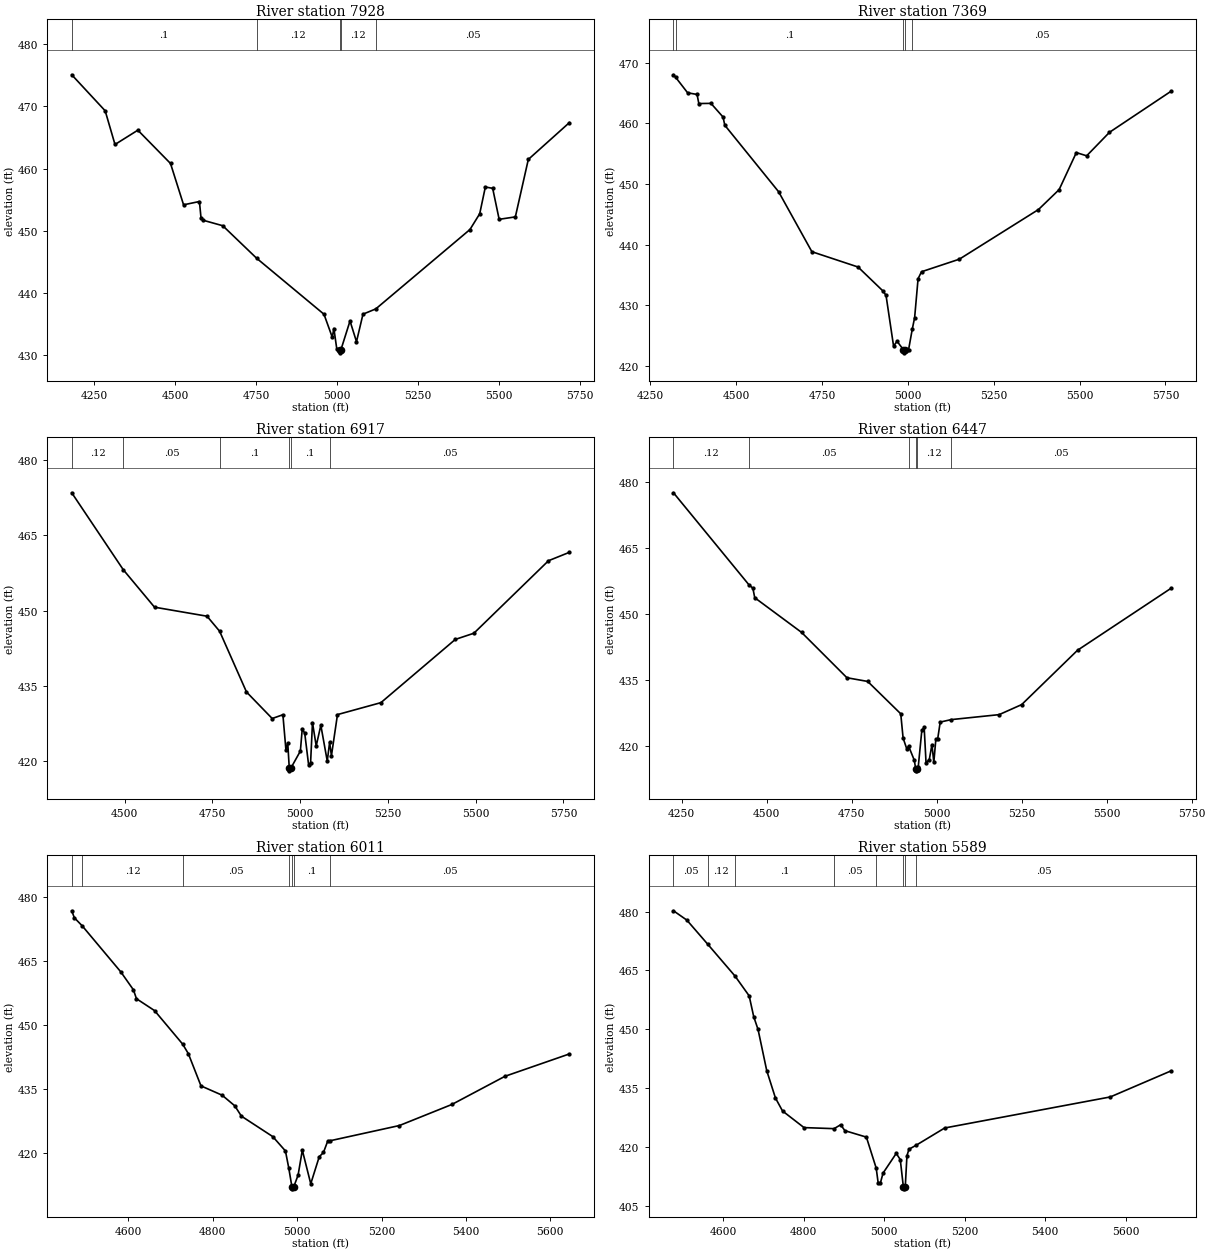
Type RM Length L Ch R = 1,7928,559,559,559
BEGIN DESCRIPTION:
896
END DESCRIPTION:
XS GIS Cut Line= 3
      2771269.89      6800048.54      2771168.81      6800864.32
      2771187.85      6801577.54
#Sta/Elev= 30
  4181.3  475.08  4284.5  469.29  4314.8  463.88  4385.3  466.18  4486.1  460.83
  4526.4  454.19  4575.3  454.72  4580.3  452.06  4586.8  451.71  4647.3  450.83
  4751.8  445.61  4959.7  436.61  4985.2  432.92  4990.2  434.32  4999.1  431.06
  5008.0  430.91  5008.3  430.41  5012.0  430.91  5040.0  435.53  5060.0  432.20
  5080.0  436.62  5119.6  437.47  5410.1  450.22  5440.2  452.75  5457.6  457.05
  5480.2  456.84  5500.2  451.86  5550.2  452.25  5590.2  461.48  5716.8  467.39
#Mann=5,-1,0
  4181.3     0.1       0  4751.8    0.12       0  5008.0    0.07       0
  5012.0    0.12       0  5119.6    0.05       0
Bank Sta=5008,5012
Exp/Cntr=0.3,0.1

Type RM Length L Ch R = 1,7369,452,452,452
BEGIN DESCRIPTION:
895
END DESCRIPTION:
XS GIS Cut Line= 3
      2770798.79      6800251.10      2770626.00      6800911.00
      2770671.59      6801676.40
#Sta/Elev= 30
  4317.7  468.00  4324.2  467.57  4358.9  465.03  4386.4  464.76  4391.5  463.26
  4426.8  463.29  4462.0  461.04  4467.2  459.68  4623.7  448.74  4720.7  438.85
  4855.1  436.33  4927.5  432.39  4936.6  431.66  4958.5  423.32  4968.8  424.09
  4987.4  422.69  4987.8  422.19  4991.6  422.69  5002.3  422.72  5013.0  426.09
  5019.9  428.00  5029.9  434.40  5039.9  435.55  5150.1  437.62  5380.5  445.80
  5440.6  449.08  5490.7  455.18  5520.8  454.65  5587.2  458.52  5766.6  465.29
#Mann=5,-1,0
  4317.7    0.12       0  4324.2     0.1       0  4987.4    0.07       0
  4991.6     0.1       0  5013.0    0.05       0
Bank Sta=4987.4,4991.6
Exp/Cntr=0.3,0.1

Type RM Length L Ch R = 1,6917,470,470,470
BEGIN DESCRIPTION:
894
END DESCRIPTION:
XS GIS Cut Line= 3
      2770339.65      6800228.94      2770226.00      6800861.00
      2770527.00      6801575.70
#Sta/Elev= 30
  4349.0  473.50  4495.8  458.18  4584.8  450.72  4734.5  448.92  4770.3  445.93
  4846.9  433.83  4920.1  428.55  4950.6  429.30  4959.3  422.24  4964.4  423.70
  4968.8  418.63  4969.1  418.13  4973.0  418.63  5000.4  422.07  5005.8  426.53
  5012.9  425.58  5023.8  419.35  5029.5  419.73  5034.9  427.73  5045.5  423.10
  5058.7  427.20  5077.0  420.07  5083.7  423.81  5088.9  421.14  5106.1  429.33
  5229.9  431.71  5441.8  444.30  5494.7  445.53  5707.3  459.97  5766.7  461.64
#Mann=6,-1,0
  4349.0    0.12       0  4495.8    0.05       0  4770.3     0.1       0
  4968.8    0.07       0  4973.0     0.1       0  5083.7    0.05       0
Bank Sta=4968.8,4973
Exp/Cntr=0.3,0.1

Type RM Length L Ch R = 1,6447,436,436,436
BEGIN DESCRIPTION:
893
END DESCRIPTION:
XS GIS Cut Line= 3
      2770250.69      6800107.70      2769926.00      6800811.00
      2769830.35      6801493.60
#Sta/Elev= 30
  4225.6  477.49  4446.9  456.68  4459.2  455.83  4464.7  453.68  4602.4  445.82
  4735.9  435.53  4797.0  434.69  4894.2  427.35  4901.1  421.86  4911.7  419.44
  4917.3  420.01  4934.2  416.79  4938.0  414.91  4938.3  414.41  4942.3  414.91
  4945.6  415.24  4956.2  423.59  4963.1  424.27  4968.6  416.24  4978.2  416.97
  4986.0  420.37  4991.5  416.34  4997.5  421.62  5002.8  421.62  5010.3  425.47
  5042.5  426.03  5183.7  427.16  5250.0  429.44  5414.2  441.76  5689.5  455.83
#Mann=6,-1,0
  4225.6    0.12       0  4446.9    0.05       0  4917.3    0.12       0
  4938.0    0.07       0  4942.3    0.12       0  5042.5    0.05       0
Bank Sta=4938,4942.3
Exp/Cntr=0.3,0.1

Type RM Length L Ch R = 1,6011,422,422,422
BEGIN DESCRIPTION:
892
END DESCRIPTION:
XS GIS Cut Line= 3
      2769597.29      6800134.82      2769576.00      6800661.00
      2769549.81      6801313.47
#Sta/Elev= 30
  4465.5  476.86  4471.7  475.22  4490.4  473.32  4581.8  462.54  4611.8  458.32
  4618.9  456.25  4661.8  453.46  4728.4  445.61  4741.9  443.37  4771.9  435.81
  4822.0  433.63  4852.0  431.14  4867.7  428.72  4942.1  423.92  4972.1  420.56
  4980.0  416.55  4987.4  412.18  4987.8  411.68  4991.9  412.18  5002.1  414.90
  5012.1  420.74  5032.1  412.87  5052.2  419.20  5062.2  420.20  5072.2  422.84
  5077.9  422.95  5242.3  426.52  5366.7  431.46  5492.5  438.06  5645.1  443.30
#Mann=7,-1,0
  4465.5    0.05       0  4490.4    0.12       0  4728.4    0.05       0
  4980.0     0.1       0  4987.4    0.07       0  4991.9     0.1       0
  5077.9    0.05       0
Bank Sta=4987.4,4991.9
Exp/Cntr=0.3,0.1

Type RM Length L Ch R = 1,5589,449,449,449
BEGIN DESCRIPTION:
891
END DESCRIPTION:
XS GIS Cut Line= 3
      2769424.05      6800076.42      2769226.00      6800561.00
      2769164.72      6801271.47
#Sta/Elev= 30
  4476.6  480.19  4509.8  477.81  4561.3  471.71  4629.4  463.56  4664.7  458.49
  4676.0  453.18  4686.8  449.91  4708.4  439.40  4730.0  432.44  4747.6  429.13
  4801.0  424.89  4875.7  424.62  4892.1  425.62  4902.5  424.11  4956.0  422.46
  4980.4  414.55  4985.4  410.67  4990.8  410.77  4997.4  413.28  5030.2  418.31
  5040.2  416.73  5047.9  409.77  5048.4  409.27  5052.6  409.77  5056.8  417.71
  5061.8  419.37  5079.8  420.40  5150.6  424.79  5562.2  432.71  5713.2  439.36
#Mann=8,-1,0
  4476.6    0.05       0  4561.3    0.12       0  4629.4     0.1       0
  4875.7    0.05       0  4980.4    0.12       0  5047.9    0.07       0
  5052.6    0.12       0  5079.8    0.05       0
Bank Sta=5047.9,5052.6
Exp/Cntr=0.3,0.1

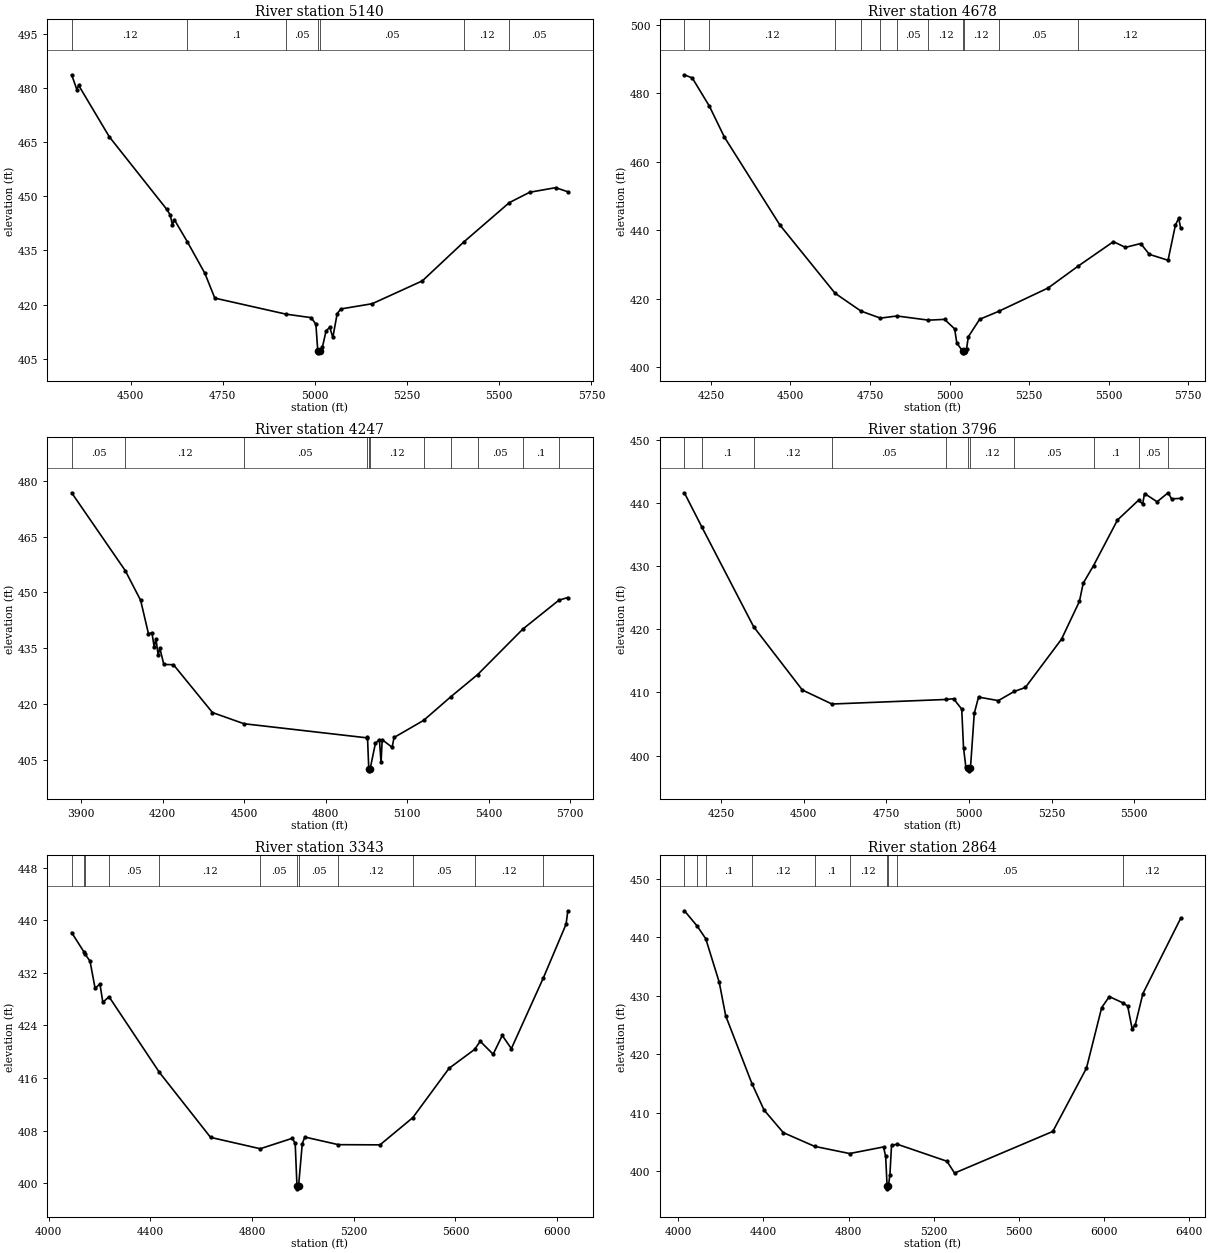
Type RM Length L Ch R = 1,5140,462,462,462
BEGIN DESCRIPTION:
890
END DESCRIPTION:
XS GIS Cut Line= 3
      2768903.00      6799955.30      2768826.00      6800611.00
      2768759.66      6801293.98
#Sta/Elev= 30
  4339.7  483.60  4353.7  479.52  4358.7  480.67  4441.8  466.44  4597.2  446.42
  4607.2  444.81  4613.2  441.99  4618.2  443.51  4653.7  437.36  4701.3  428.62
  4728.1  421.78  4921.7  417.33  4989.8  416.37  5002.4  414.53  5007.6  407.13
  5008.1  406.63  5012.4  407.13  5020.0  408.15  5030.1  412.71  5040.1  413.71
  5048.4  410.89  5060.2  417.48  5070.2  418.78  5155.4  420.23  5291.3  426.55
  5403.8  437.32  5527.3  448.21  5582.6  451.08  5653.0  452.35  5686.1  451.22
#Mann=7,-1,0
  4339.7    0.12       0  4653.7     0.1       0  4921.7    0.05       0
  5007.6    0.03       0  5012.4    0.05       0  5403.8    0.12       0
  5527.3    0.05       0
Bank Sta=5007.6,5012.4
Exp/Cntr=0.3,0.1

Type RM Length L Ch R = 1,4678,431,431,431
BEGIN DESCRIPTION:
889
END DESCRIPTION:
XS GIS Cut Line= 3
      2768804.33      6799855.49      2768376.00      6800561.00
      2768539.23      6801276.87
#Sta/Elev= 30
  4166.8  485.35  4191.6  484.40  4245.4  476.15  4292.5  467.14  4466.9  441.49
  4640.3  421.58  4721.8  416.37  4782.8  414.32  4834.8  414.95  4933.9  413.73
  4984.4  413.96  5016.2  411.18  5022.9  407.09  5041.0  404.69  5041.6  404.19
  5045.8  404.69  5053.7  405.44  5059.2  408.89  5094.7  413.98  5154.4  416.30
  5310.1  423.13  5405.3  429.57  5515.2  436.64  5552.8  434.97  5600.9  436.09
  5628.1  432.94  5686.9  431.21  5710.1  441.48  5720.4  443.48  5726.4  440.68
#Mann=11,-1,0
  4166.8    0.05       0  4245.4    0.12       0  4640.3     0.1       0
  4721.8    0.12       0  4782.8     0.1       0  4834.8    0.05       0
  4933.9    0.12       0  5041.0    0.07       0  5045.8    0.12       0
  5154.4    0.05       0  5405.3    0.12       0
Bank Sta=5041,5045.8
Exp/Cntr=0.3,0.1

Type RM Length L Ch R = 1,4247,451,451,451
BEGIN DESCRIPTION:
888
END DESCRIPTION:
XS GIS Cut Line= 3
      2768715.09      6799745.07      2768026.00      6800661.00
      2768133.56      6801332.64
#Sta/Elev= 30
  3864.7  476.74  4062.1  455.84  4118.6  447.88  4147.4  438.92  4160.2  439.20
  4168.6  435.30  4174.8  437.57  4183.1  433.27  4189.4  434.99  4204.0  430.67
  4239.4  430.61  4383.0  417.77  4499.0  414.77  4950.8  410.99  4953.6  411.22
  4958.4  402.63  4959.0  402.13  4963.3  402.63  4982.8  409.52  4997.4  410.53
  5003.6  404.38  5007.8  410.48  5044.4  408.44  5051.4  411.08  5160.3  415.67
  5259.9  421.98  5359.4  427.98  5525.9  440.20  5658.1  447.91  5691.1  448.64
#Mann=11,-1,0
  3864.7    0.05       0  4062.1    0.12       0  4499.0    0.05       0
  4950.8    0.12       0  4958.4    0.07       0  4963.3    0.12       0
  5160.3    0.05       0  5259.9    0.12       0  5359.4    0.05       0
  5525.9     0.1       0  5658.1    0.12       0
Bank Sta=4958.4,4963.3
Exp/Cntr=0.3,0.1

Type RM Length L Ch R = 1,3796,453,453,453
BEGIN DESCRIPTION:
887
END DESCRIPTION:
XS GIS Cut Line= 3
      2767326.01      6799861.04      2767626.00      6800661.00
      2767933.84      6801230.35
#Sta/Elev= 30
  4139.1  441.58  4191.8  436.19  4348.5  420.40  4495.9  410.38  4585.6  408.16
  4930.0  408.88  4953.4  409.00  4978.3  407.36  4983.7  401.26  4990.8  398.16
  4998.3  398.08  4999.4  397.58  5004.8  398.08  5016.2  406.66  5029.1  409.26
  5089.1  408.70  5137.2  410.15  5170.9  410.78  5280.3  418.43  5334.5  424.42
  5346.0  427.30  5377.3  430.09  5449.7  437.30  5513.6  440.44  5525.8  439.83
  5531.5  441.49  5569.6  440.19  5602.9  441.61  5613.4  440.65  5640.7  440.72
#Mann=11,-1,0
  4139.1    0.12       0  4191.8     0.1       0  4348.5    0.12       0
  4585.6    0.05       0  4930.0    0.12       0  4998.3    0.07       0
  5004.8    0.12       0  5137.2    0.05       0  5377.3     0.1       0
  5513.6    0.05       0  5602.9     0.1       0
Bank Sta=4998.3,5004.8
Exp/Cntr=0.3,0.1

Type RM Length L Ch R = 1,3343,479,479,479
BEGIN DESCRIPTION:
886
END DESCRIPTION:
XS GIS Cut Line= 3
      2767105.84      6799759.49      2767226.00      6800661.00
      2767816.36      6801519.64
#Sta/Elev= 30
  4090.6  438.13  4138.5  435.22  4142.1  434.91  4162.7  433.80  4182.9  429.64
  4201.7  430.33  4213.2  427.53  4237.6  428.37  4435.8  416.86  4636.9  406.98
  4832.3  405.25  4958.5  406.84  4969.8  406.05  4976.7  399.65  4977.7  399.15
  4983.2  399.65  4997.6  406.01  5007.5  407.03  5139.7  405.87  5303.2  405.84
  5432.1  409.97  5575.1  417.49  5675.2  420.35  5697.6  421.59  5748.3  419.63
  5784.2  422.48  5820.0  420.48  5945.9  431.25  6035.2  439.41  6042.1  441.45
#Mann=12,-1,0
  4090.6    0.12       0  4138.5     0.1       0  4142.1    0.12       0
  4237.6    0.05       0  4435.8    0.12       0  4832.3    0.05       0
  4976.7    0.05       0  4983.2    0.05       0  5139.7    0.12       0
  5432.1    0.05       0  5675.2    0.12       0  5945.9     0.1       0
Bank Sta=4976.7,4983.2
Exp/Cntr=0.3,0.1

Type RM Length L Ch R = 1,2864,529,529,529
BEGIN DESCRIPTION:
885
END DESCRIPTION:
XS GIS Cut Line= 3
      2766831.80      6799687.79      2766776.00      6800661.00
      2767551.88      6801771.74
#Sta/Elev= 30
  4029.6  444.58  4089.0  441.98  4129.7  439.79  4193.1  432.31  4223.2  426.59
  4346.6  414.95  4403.4  410.43  4493.6  406.56  4640.8  404.20  4805.3  402.97
  4964.3  404.10  4974.4  402.48  4981.1  397.42  4982.2  396.92  4987.6  397.42
  4994.4  399.37  5001.9  404.36  5028.4  404.57  5262.1  401.65  5297.9  399.62
  5759.3  406.76  5917.2  417.60  5988.7  427.98  6024.5  429.87  6089.4  428.78
  6110.8  428.23  6131.7  424.36  6146.6  425.05  6182.3  430.39  6359.3  443.26
#Mann=10,-1,0
  4029.6     0.1       0  4089.0    0.12       0  4129.7     0.1       0
  4346.6    0.12       0  4640.8     0.1       0  4805.3    0.12       0
  4981.1    0.07       0  4987.6    0.12       0  5028.4    0.05       0
  6089.4    0.12       0
Bank Sta=4981.1,4987.6
Exp/Cntr=0.3,0.1

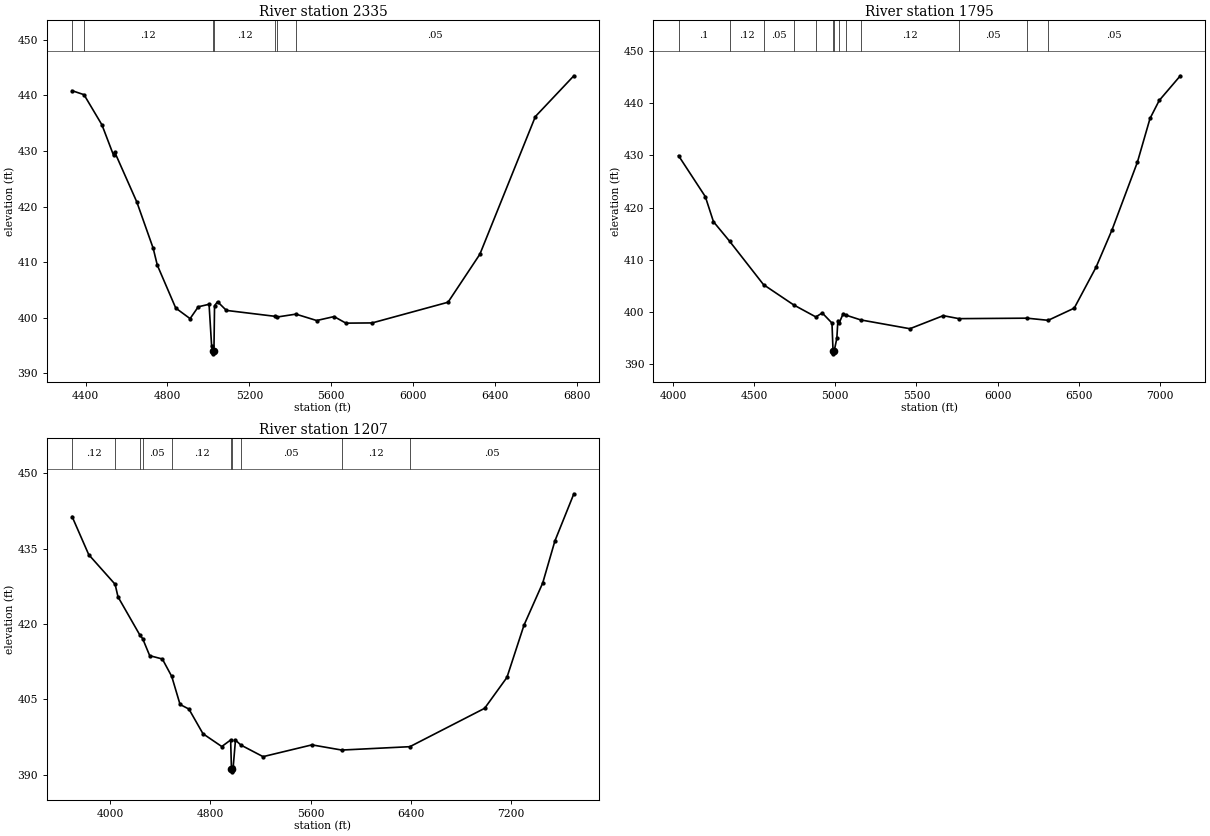
Type RM Length L Ch R = 1,2335,540,540,540
BEGIN DESCRIPTION:
2402
END DESCRIPTION:
XS GIS Cut Line= 3
      2766318.72      6799845.01      2766293.56      6800509.44
      2767397.51      6801913.39
#Sta/Elev= 30
  4333.9  440.83  4392.2  440.11  4480.0  434.67  4536.5  429.21  4541.5  429.84
  4650.1  420.82  4730.2  412.48  4750.2  409.46  4840.3  401.74  4910.3  399.84
  4950.3  401.97  5003.0  402.42  5015.4  395.00  5020.1  394.01  5021.1  393.51
  5026.8  394.01  5029.8  402.15  5044.3  402.89  5087.6  401.32  5326.6  400.25
  5335.3  400.13  5427.3  400.65  5528.6  399.50  5613.6  400.21  5671.4  399.03
  5799.7  399.07  6170.2  402.79  6325.7  411.42  6596.8  436.18  6784.8  443.51
#Mann=7,-1,0
  4333.9     0.1       0  4392.2    0.12       0  5020.1    0.07       0
  5026.8    0.12       0  5326.6    0.05       0  5335.3    0.12       0
  5427.3    0.05       0
Bank Sta=5020.1,5026.8
Exp/Cntr=0.3,0.1

Type RM Length L Ch R = 1,1795,588,588,588
BEGIN DESCRIPTION:
2401
END DESCRIPTION:
XS GIS Cut Line= 3
      2765778.85      6799545.99      2765803.26      6800528.57
      2767356.83      6801953.99
#Sta/Elev= 30
  4034.4  429.94  4199.5  422.09  4249.5  417.30  4348.4  413.58  4558.0  405.24
  4743.8  401.36  4880.2  399.06  4919.7  399.82  4979.7  397.88  4986.3  392.49
  4987.4  391.99  4993.1  392.49  5009.7  394.99  5016.0  398.36  5025.0  397.97
  5049.0  399.70  5064.0  399.42  5156.4  398.49  5459.7  396.80  5665.0  399.30
  5762.0  398.73  6181.6  398.82  6311.5  398.41  6472.1  400.74  6606.5  408.58
  6705.2  415.75  6861.2  428.69  6938.9  437.06  6995.6  440.51  7125.7  445.24
#Mann=13,-1,0
  4034.4     0.1       0  4348.4    0.12       0  4558.0    0.05       0
  4743.8    0.12       0  4880.2     0.1       0  4986.3    0.07       0
  4993.1     0.1       0  5025.0    0.12       0  5064.0    0.05       0
  5156.4    0.12       0  5762.0    0.05       0  6181.6    0.12       0
  6311.5    0.05       0
Bank Sta=4986.3,4993.1
Exp/Cntr=0.3,0.1

Type RM Length L Ch R = 1,1207,0,0,0
BEGIN DESCRIPTION:
884
END DESCRIPTION:
XS GIS Cut Line= 5
      2765069.75      6799269.67      2765163.26      6799814.12
      2765267.85      6800562.62      2765826.89      6801542.50
      2767325.96      6802010.99
#Sta/Elev= 30
  3695.4  441.37  3828.7  433.78  4039.1  427.90  4062.2  425.40  4237.6  417.77
  4258.9  417.11  4315.3  413.71  4416.3  413.05  4491.4  409.58  4557.7  404.01
  4628.4  403.10  4740.9  398.19  4890.9  395.65  4961.6  396.95  4968.3  391.12
  4969.4  390.62  4975.1  391.12  4981.8  391.52  5000.2  396.93  5043.1  395.95
  5220.5  393.64  5610.7  395.98  5848.9  394.95  6392.7  395.62  6989.9  403.25
  7168.0  409.39  7304.2  419.78  7453.5  428.15  7551.0  436.52  7702.3  445.89
#Mann=10,-1,0
  3695.4    0.12       0  4039.1    0.05       0  4237.6    0.12       0
  4258.9    0.05       0  4491.4    0.12       0  4968.3    0.07       0
  4975.1    0.12       0  5043.1    0.05       0  5848.9    0.12       0
  6392.7    0.05       0
Bank Sta=4968.3,4975.1
Exp/Cntr=0.3,0.1

Chan Stop Cuts=-1