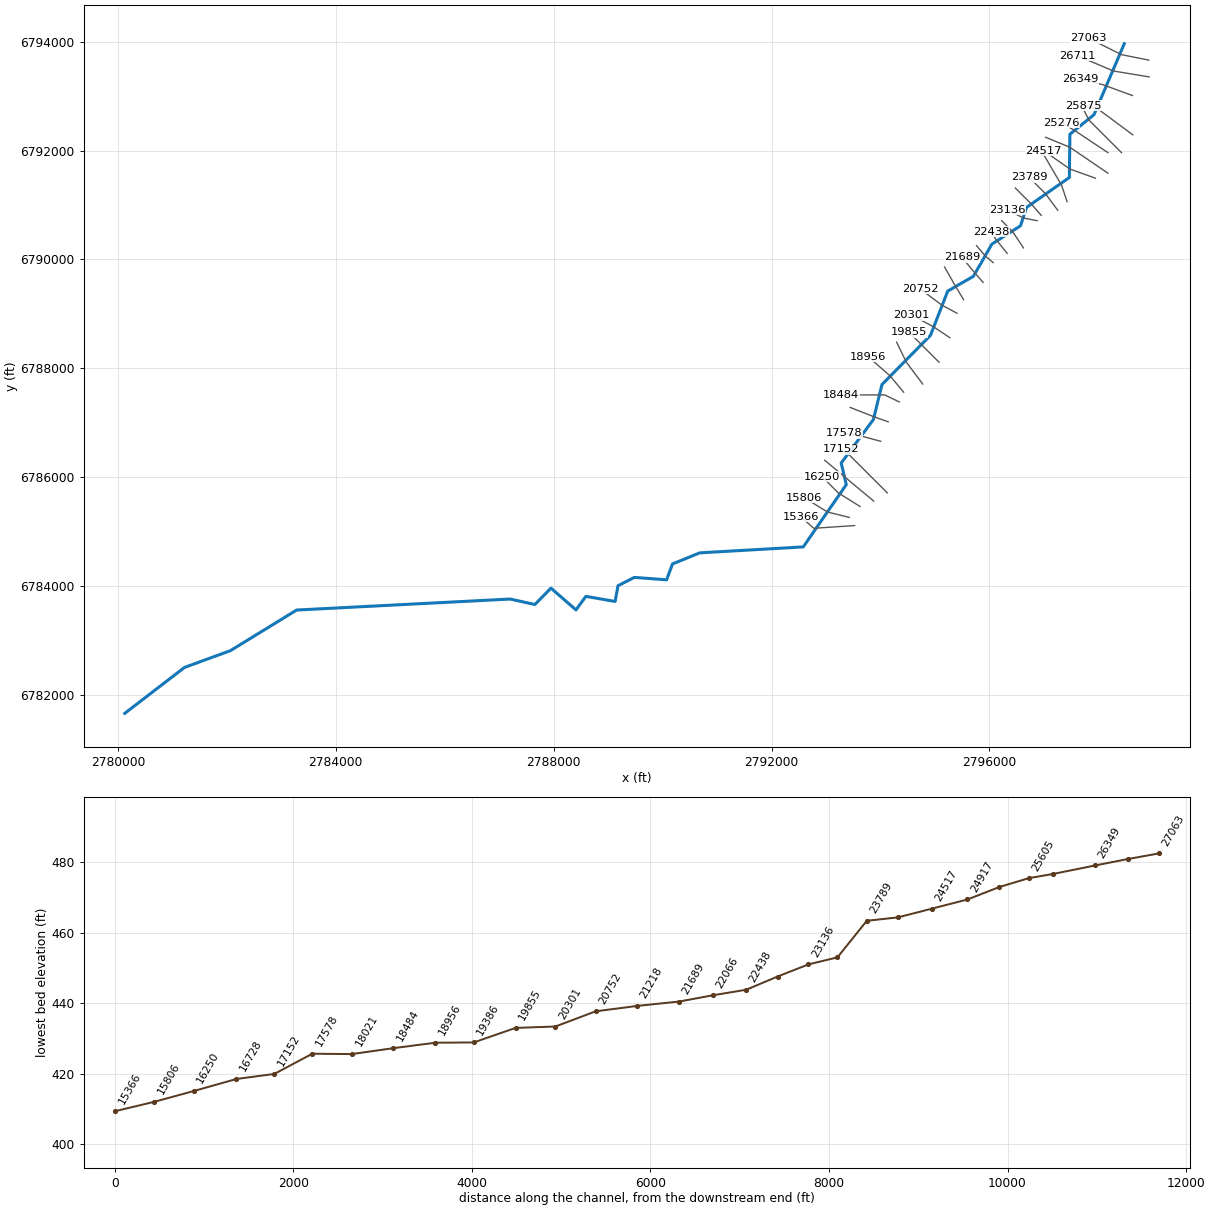
--- Second Caney Creek.prj (project) ---

Proj Title=Second Caney Creek Base Level Engineering
Current Plan=p01
Default Exp/Contr=0.3,0.1
English Units
Geom File=g01
Flow File=f01
Plan File=p01
Y Axis Title=Elevation
X Axis Title(PF)=Main Channel Distance
X Axis Title(XS)=Station
BEGIN DESCRIPTION:
Second Caney Creek
END DESCRIPTION:
DSS Export Rating Curves= 0
DSS Export Rating Curve Sorted= 0
DSS Export Volume Flow Curves= 0
DXF OffsetX= 0
DXF OffsetY= 0
DXF ScaleX= 1
DXF ScaleY= 10

--- Second Caney Creek.p01 (plan) ---

Plan Title=Multiple Run
Program Version=4.10
Short Identifier=Multiple
Geom File=g01
Flow File=f01
Subcritical Flow
K Sum by GR= 0
Std Step Tol= 0.01
Critical Tol= 0.01
Num of Std Step Trials= 20
Max Error Tol= 0.3
Flow Tol Ratio= 0.001
Split Flow NTrial= 30
Split Flow Tol= 0.02
Split Flow Ratio= 0.02
Log Output Level= 0
Friction Slope Method= 1
Unsteady Friction Slope Method= 2
Unsteady Bridges Friction Slope Method= 1
Parabolic Critical Depth
Global Vel Dist= 1 , 1 , 1
Global Log Level= 0
CheckData=True
Encroach Param=-1 ,0,0, 0
BEGIN DESCRIPTION:
Multiple Run
END DESCRIPTION:
Computation Interval=1HOUR
Output Interval=1HOUR
Run HTab= 0
Run UNet= 0
Run PostProcess= 0
Run WQNet= 0
UNET Theta= 1
UNET Theta Warmup= 1
UNET ZTol= 0.02
UNET ZSATol= 0.05
UNET MxIter= 20
UNET MaxInSteps= 0
UNET DtIC= 0
UNET DtMin= 0
UNET MaxCRTS= 20
UNET WFStab= 2
UNET SFStab= 1
UNET WFX= 1
UNET SFX= 1
UNET DSS MLevel= 4
UNET DZMax Abort= 100
UNET Convert EG Bridges= 0
UNET Use Existing IB Tables=-1
UNET Froude Reduction=False
UNET Froude Limit= 1
UNET Froude Power= 10
UNET Time Slicing=0,0, 5
UNET Junction Losses=0
Instantaneous Interval=1HOUR
Write IC File= 0
Write IC File at Sim End=0
Echo Input=False
Echo Parameters=False
Echo Output=False
Write Detailed= 0
WQ AD Non Conservative
WQ ULTIMATE=-1
WQ Max Comp Step=1HOUR
WQ Output Interval=15MIN
WQ Output Selected Increments= 0
WQ Output face flow=0
WQ Output face velocity=0
WQ Output face area=0
WQ Output face dispersion=0
WQ Output cell volume=0
WQ Output cell surface area=0
WQ Output cell continuity=0
WQ Output cumulative cell continuity=0
WQ Output face conc=0
WQ Output face dconc_dx=0
WQ Output face courant=0
WQ Output face peclet=0
WQ Output face adv mass=0
WQ Output face disp mass=0
WQ Output cell mass=0
WQ Output cell source sink temp=0
WQ Output cell source sink nsm=0
WQ Output MaxMinRange=-1
WQ Daily Max Min Mean=-1
WQ Daily Range=0
WQ Daily Time=0
WQ Create Restart=0
WQ Fixed Restart=0
WQ System Summary=0
WQ Use Fixed Temperature=0
Sorting and Armoring Iterations= 10
XS Update Threshold= 0.02
Hydraulics Update Threshold= 0.02
Energy Slope Method= 1
Volume Change Method= 0
XS Weighting Method= 0
Number of US Weighted Cross Sections= 1
Number of DS Weighted Cross Sections= 1
Upstream XS Weight=0.25
Main XS Weight=0.5
Downstream XS Weight=0.25
Number of DS XS's Weighted with US Boundary= 1
Upstream Boundary Weight= 1
Weight of XSs Associated with US Boundary= 0
Number of US XS's Weighted with DS Boundary= 1
Downstream Boundary Weight= 0.5
Weight of XSs Associated with DS Boundary= 0.5
Sediment Output Level= 4
Mass or Volume Output= 0
Output Increment Type= 1
Profile and TS Output Increment= 10
XS Output Flag= 0
XS Output Increment= 10
Disregard all LS=0
Disregard all Conn=0
Disregard all Breaches=0
Disregard all Pumps=0

--- Second Caney Creek.f01 (steady flow) ---

Flow Title=Multiple
Number of Profiles=7
Profile Names=10-year,25-year,50-year,1pct_min,100-year,1pct_plu,500-year
River Rch & RM= Second Caney Cre,Reach-1,27063
     661     903    1103     670    1338    2669    1971
River Rch & RM= Second Caney Cre,Reach-1,21218
     844    1161    1425     869    1734    3459    2571
River Rch & RM= Second Caney Cre,Reach-1,17152
    1285    1804    2244    1384    2760    5508    4192
River Rch & RM= Second Caney Cre,Reach-1,14895
    1975    2820    3547    2209    4408    8795    6828
River Rch & RM= Second Caney Cre,Reach-1,7131
    2097    2997    3772    2350    4690    9357    7272
River Rch & RM= Second Caney Cre,Reach-1,6681
    2631    3782    4780    2987    5960   11891    9297
Boundary for River Rch & Prof#=Second Caney Cre,Reach-1,1
Up Type=0
Dn Type=3
Dn Slope=0.00033
Boundary for River Rch & Prof#=Second Caney Cre,Reach-1,2
Up Type=0
Dn Type=3
Dn Slope=0.00033
Boundary for River Rch & Prof#=Second Caney Cre,Reach-1,3
Up Type=0
Dn Type=3
Dn Slope=0.00033
Boundary for River Rch & Prof#=Second Caney Cre,Reach-1,4
Up Type=0
Dn Type=3
Dn Slope=0.00033
Boundary for River Rch & Prof#=Second Caney Cre,Reach-1,5
Up Type=0
Dn Type=3
Dn Slope=0.00033
Boundary for River Rch & Prof#=Second Caney Cre,Reach-1,6
Up Type=0
Dn Type=3
Dn Slope=0.00033
Boundary for River Rch & Prof#=Second Caney Cre,Reach-1,7
Up Type=0
Dn Type=3
Dn Slope=0.00033

--- Second Caney Creek.g01 (geometry) ---

Geom Title=Existing Conditions

River Reach=Second Caney Cre,Reach-1
Reach XY= 30
      2798476.00      6793961.00      2797920.17      6792658.70
      2797477.62      6792299.17      2797468.17      6791504.81
      2796681.59      6790955.39      2796570.41      6790616.61
      2796045.77      6790281.13      2795706.57      6789690.36
      2795234.13      6789417.07      2794918.15      6788604.81
      2794028.50      6787702.85      2793870.17      6787058.70
      2793279.53      6786259.55      2793372.62      6785862.40
      2792582.21      6784718.81      2790681.87      6784609.50
      2790181.59      6784405.45      2790074.75      6784114.51
      2789481.90      6784158.77      2789181.41      6784005.82
      2789128.98      6783716.52      2788591.64      6783810.58
      2788410.75      6783561.36      2787951.01      6783961.59
      2787655.99      6783660.77      2787200.69      6783761.27
      2783281.71      6783559.06      2782068.03      6782813.93
      2781223.71      6782505.15      2780126.00      6781661.00

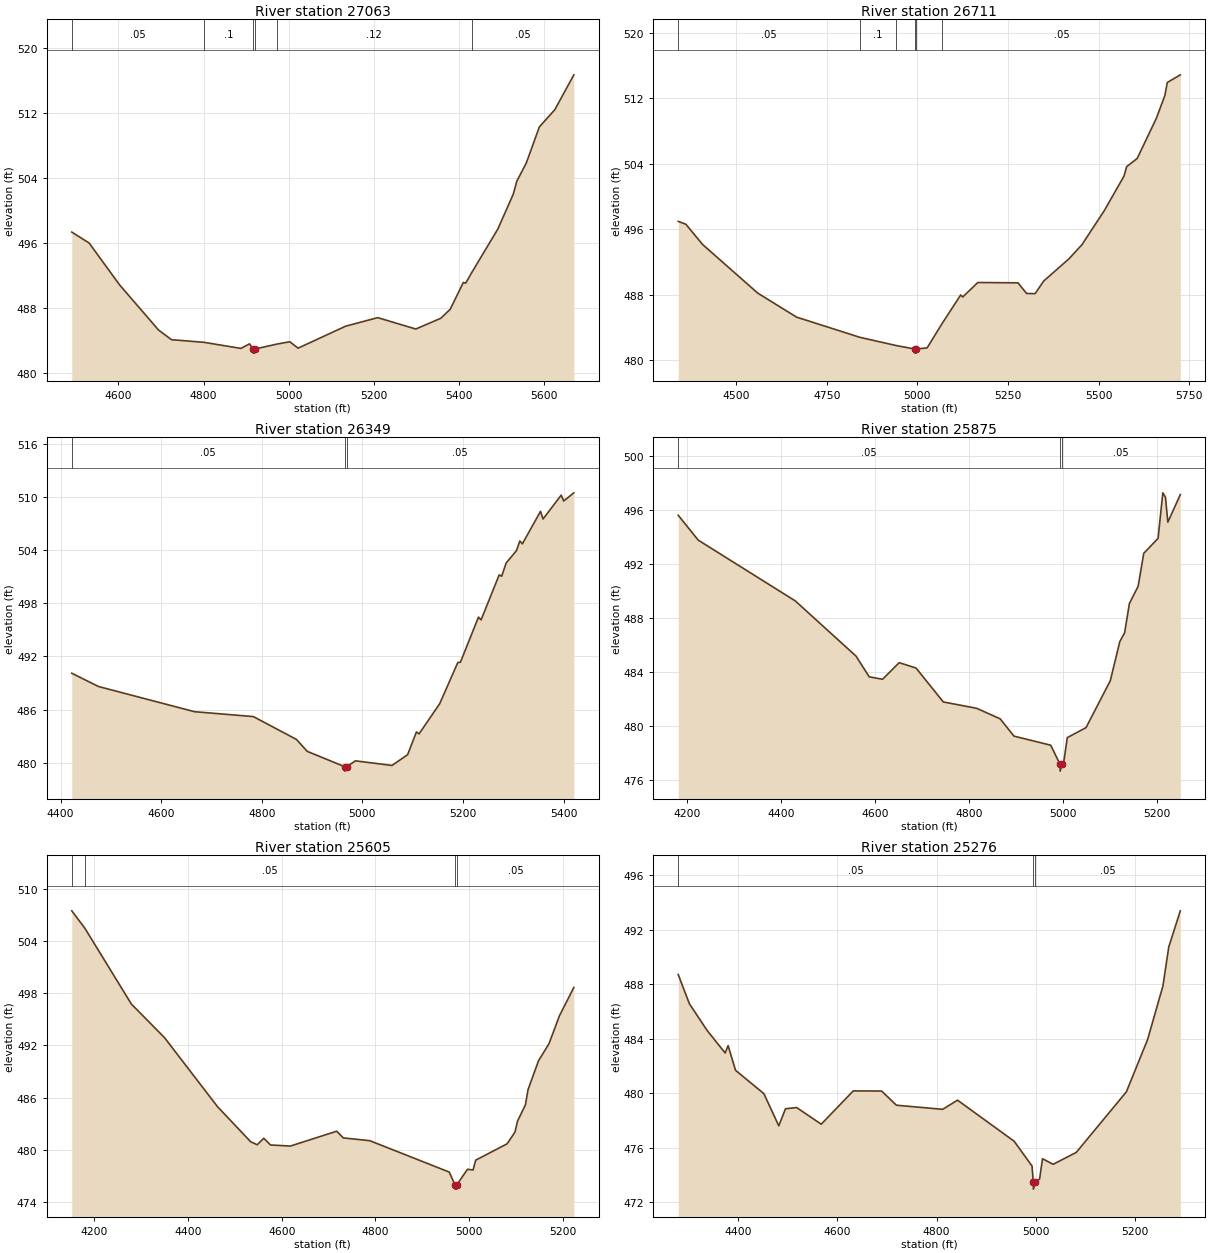
Type RM Length L Ch R = 1,27063,352,352,352
BEGIN DESCRIPTION:
Second Caney Creek 51.0
END DESCRIPTION:
XS GIS Cut Line= 3
      2798925.99      6793661.00      2798426.00      6793761.00
      2797826.01      6794061.00
#Sta/Elev= 30
  4490.2  497.35  4531.0  496.01  4602.4  490.88  4694.1  485.33  4724.7  484.13
  4800.9  483.81  4887.9  483.06  4908.3  483.62  4916.5  482.98  4916.8  482.48
  4920.3  482.48  4920.5  482.98  4971.8  483.58  5002.9  483.88  5022.4  483.09
  5134.3  485.79  5209.7  486.84  5299.2  485.44  5357.9  486.76  5380.2  487.87
  5411.0  491.16  5416.6  491.08  5430.8  492.38  5492.0  497.71  5528.4  502.00
  5536.7  503.59  5559.1  505.84  5589.8  510.27  5626.2  512.39  5670.9  516.67
#Mann=6,-1,0
  4490.2    0.05       0  4800.9     0.1       0  4916.5    0.07       0
  4920.5     0.1       0  4971.8    0.12       0  5430.8    0.05       0
Bank Sta=4916.5,4920.5
Exp/Cntr=0.3,0.1

Type RM Length L Ch R = 1,26711,362,362,362
BEGIN DESCRIPTION:
Second Caney Creek 50.0
END DESCRIPTION:
XS GIS Cut Line= 3
      2798932.34      6793352.65      2798276.00      6793461.00
      2797612.88      6793743.22
#Sta/Elev= 30
  4339.8  496.97  4360.9  496.62  4407.0  494.15  4559.1  488.21  4666.4  485.27
  4841.4  482.80  4942.1  481.79  4992.9  481.37  4993.1  480.87  4996.6  480.87
  4996.9  481.37  5026.8  481.51  5069.1  484.55  5119.5  487.98  5125.0  487.73
  5166.8  489.50  5277.7  489.46  5301.3  488.16  5324.9  488.14  5348.6  489.68
  5418.0  492.38  5454.0  494.11  5515.8  498.28  5570.2  502.50  5577.6  503.66
  5606.7  504.66  5659.4  509.55  5683.0  512.34  5689.7  513.94  5725.7  514.88
#Mann=6,-1,0
  4339.8    0.05       0  4841.4     0.1       0  4942.1    0.12       0
  4992.9    0.07       0  4996.9    0.12       0  5069.1    0.05       0
Bank Sta=4992.9,4996.9
Exp/Cntr=0.3,0.1

Type RM Length L Ch R = 1,26349,474,474,474
BEGIN DESCRIPTION:
Second Caney Creek 49.0
END DESCRIPTION:
XS GIS Cut Line= 3
      2798626.03      6793010.99      2798076.00      6793211.00
      2797675.37      6793311.86
#Sta/Elev= 30
  4422.1  490.11  4475.3  488.61  4666.2  485.77  4783.2  485.22  4869.0  482.64
  4890.3  481.30  4964.8  479.57  4965.0  479.07  4968.8  479.57  4986.1  480.23
  5058.9  479.71  5089.9  480.92  5107.5  483.49  5112.7  483.27  5153.8  486.68
  5189.8  491.32  5194.9  491.34  5230.9  496.44  5236.0  496.12  5272.0  501.19
  5277.1  501.05  5285.8  502.53  5306.4  503.93  5313.1  505.02  5318.2  504.70
  5354.2  508.36  5359.3  507.50  5395.3  510.19  5400.4  509.53  5420.5  510.45
#Mann=3,-1,0
  4422.1    0.05       0  4964.8    0.04       0  4968.8    0.05       0
Bank Sta=4964.8,4968.8
Exp/Cntr=0.3,0.1

Type RM Length L Ch R = 1,25875,270,270,270
BEGIN DESCRIPTION:
Second Caney Creek 48.0
END DESCRIPTION:
XS GIS Cut Line= 3
      2798632.21      6792288.51      2797975.49      6792776.21
      2797729.46      6792821.66
#Sta/Elev= 30
  4182.0  495.59  4224.5  493.75  4431.0  489.25  4560.4  485.16  4588.3  483.63
  4616.7  483.45  4652.1  484.68  4688.0  484.28  4746.0  481.77  4817.0  481.30
  4867.0  480.52  4896.3  479.24  4974.5  478.57  4994.4  477.15  4994.6  476.65
  4998.4  477.15  5002.3  477.34  5009.7  479.13  5049.6  479.87  5101.2  483.34
  5121.5  486.24  5131.7  486.89  5141.9  489.06  5160.5  490.33  5172.4  492.77
  5202.9  493.88  5213.0  497.25  5218.6  496.93  5223.7  495.08  5250.2  497.12
#Mann=3,-1,0
  4182.0    0.05       0  4994.4    0.04       0  4998.4    0.05       0
Bank Sta=4994.4,4998.4
Exp/Cntr=0.3,0.1

Type RM Length L Ch R = 1,25605,329,329,329
BEGIN DESCRIPTION:
Second Caney Creek 47.0
END DESCRIPTION:
XS GIS Cut Line= 3
      2798426.00      6791961.00      2797826.00      6792561.00
      2797726.01      6792760.97
#Sta/Elev= 30
  4151.5  507.47  4179.6  505.46  4278.8  496.75  4349.5  492.89  4462.6  484.96
  4533.3  480.93  4547.5  480.57  4561.6  481.32  4575.8  480.55  4618.2  480.42
  4717.2  482.13  4731.3  481.36  4787.9  481.04  4957.6  477.43  4969.7  475.97
  4970.0  475.47  4973.5  475.47  4973.7  475.97  4996.5  477.75  5008.4  477.67
  5014.0  478.80  5081.1  480.68  5097.9  482.03  5103.4  483.30  5120.2  485.16
  5125.8  486.91  5148.2  490.23  5170.5  492.19  5192.9  495.41  5223.6  498.66
#Mann=4,-1,0
  4151.5    0.12       0  4179.6    0.05       0  4969.7    0.05       0
  4973.7    0.05       0
Bank Sta=4969.7,4973.7
Exp/Cntr=0.3,0.1

Type RM Length L Ch R = 1,25276,359,359,359
BEGIN DESCRIPTION:
Second Caney Creek 46.0
END DESCRIPTION:
XS GIS Cut Line= 3
      2798175.97      6791961.02      2797576.00      6792361.00
      2797326.01      6792510.99
#Sta/Elev= 30
  4279.1  488.70  4301.6  486.56  4337.6  484.59  4373.7  482.95  4379.7  483.49
  4394.7  481.68  4451.8  479.97  4481.9  477.61  4495.4  478.86  4517.9  478.95
  4567.5  477.73  4632.1  480.17  4689.2  480.16  4719.2  479.12  4812.4  478.82
  4842.4  479.49  4956.6  476.48  4992.7  474.66  4995.2  473.47  4995.4  472.97
  4999.2  473.47  5007.9  473.71  5013.8  475.20  5035.2  474.79  5081.8  475.66
  5182.9  480.10  5225.6  483.92  5256.7  487.87  5268.4  490.72  5291.7  493.37
#Mann=3,-1,0
  4279.1    0.05       0  4995.2    0.04       0  4999.2    0.05       0
Bank Sta=4995.2,4999.2
Exp/Cntr=0.3,0.1

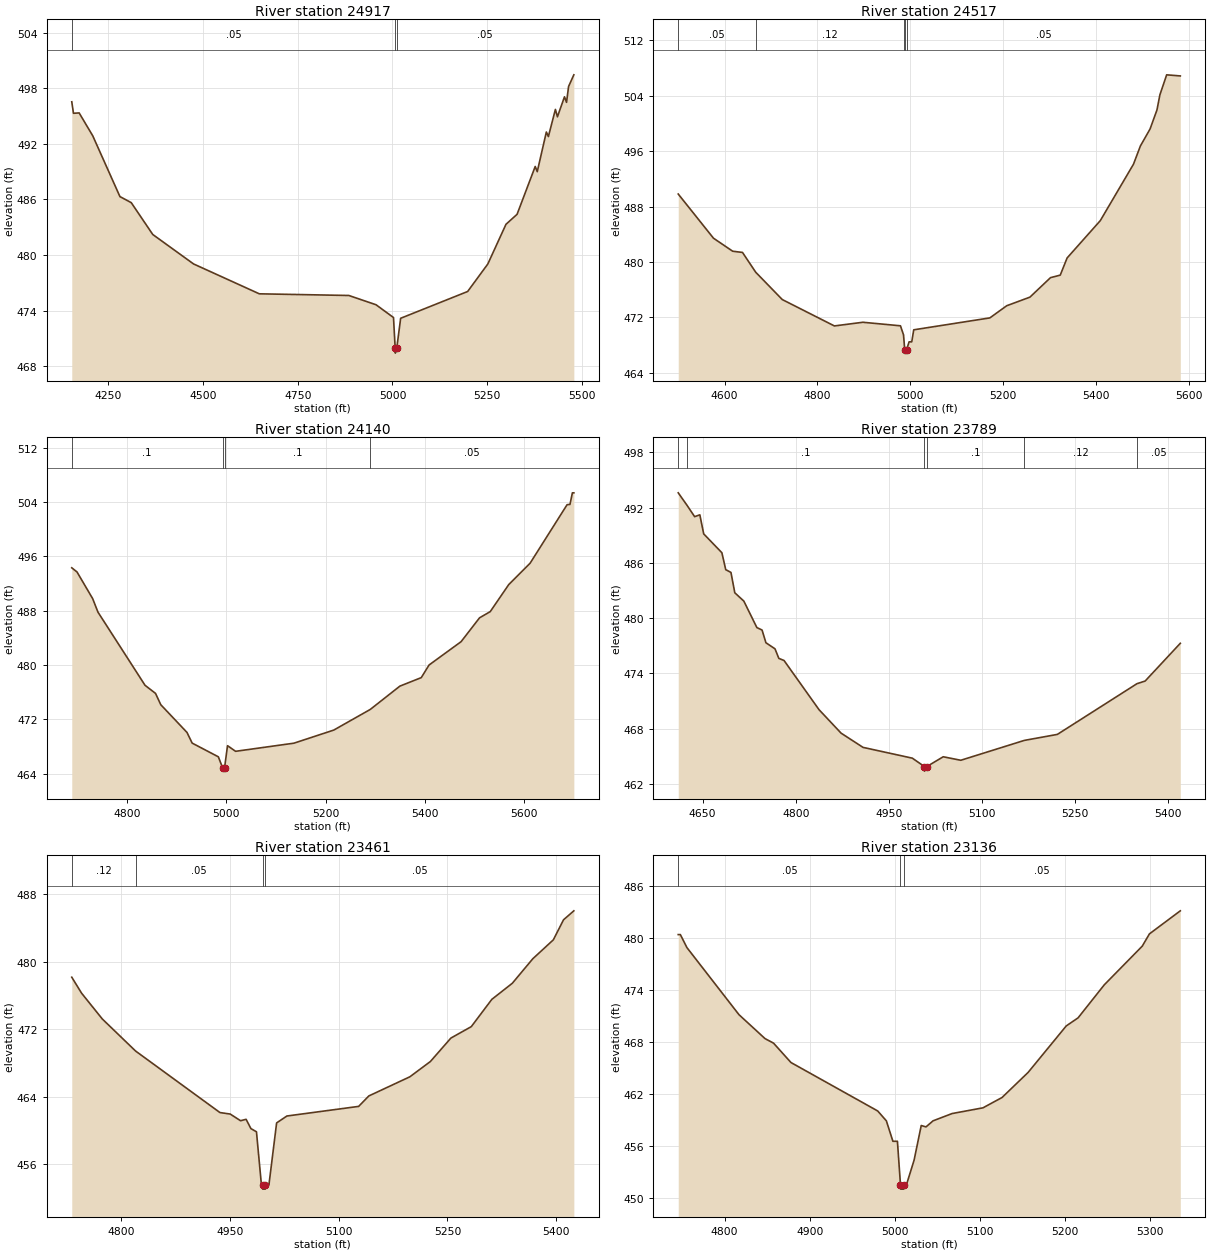
Type RM Length L Ch R = 1,24917,400,400,400
BEGIN DESCRIPTION:
Second Caney Creek 45.0
END DESCRIPTION:
XS GIS Cut Line= 3
      2798175.69      6791584.08      2797476.00      6792061.00
      2797033.15      6792243.36
#Sta/Elev= 30
  4153.2  496.54  4157.7  495.30  4172.7  495.34  4208.6  492.87  4280.4  486.31
  4310.2  485.66  4367.1  482.22  4474.9  479.04  4648.4  475.82  4884.8  475.64
  4956.6  474.64  5002.7  473.26  5007.2  469.92  5007.5  469.42  5011.2  469.92
  5021.6  473.18  5198.5  476.07  5251.8  479.04  5299.7  483.32  5329.0  484.40
  5376.9  489.56  5382.3  489.00  5406.3  493.28  5411.7  492.79  5430.2  495.72
  5435.6  494.92  5454.2  497.08  5459.6  496.48  5465.0  498.19  5478.9  499.45
#Mann=3,-1,0
  4153.2    0.05       0  5007.2    0.04       0  5011.2    0.05       0
Bank Sta=5007.2,5011.2
Exp/Cntr=0.3,0.1

Type RM Length L Ch R = 1,24517,377,377,377
BEGIN DESCRIPTION:
Second Caney Creek 44.0
END DESCRIPTION:
XS GIS Cut Line= 3
      2797946.25      6791491.65      2797476.00      6791661.00
      2797000.01      6791995.00
#Sta/Elev= 30
  4500.2  489.80  4576.1  483.42  4617.4  481.54  4638.6  481.36  4667.1  478.50
  4724.3  474.55  4836.5  470.74  4897.9  471.27  4978.8  470.76  4985.4  469.45
  4988.0  467.31  4988.2  466.81  4992.0  467.31  4997.4  468.44  5003.1  468.44
  5007.4  470.18  5171.3  471.90  5207.7  473.66  5257.6  474.90  5302.0  477.72
  5322.9  478.08  5337.7  480.56  5409.2  485.96  5480.7  494.12  5495.5  496.74
  5516.4  499.21  5531.2  501.95  5537.5  504.13  5552.1  507.03  5581.5  506.87
#Mann=5,-1,0
  4500.2    0.05       0  4667.1    0.12       0  4985.4    0.05       0
  4988.0    0.04       0  4992.0    0.05       0
Bank Sta=4988,4992
Exp/Cntr=0.3,0.1

Type RM Length L Ch R = 1,24140,351,351,351
BEGIN DESCRIPTION:
Second Caney Creek 43.0
END DESCRIPTION:
XS GIS Cut Line= 3
      2797425.99      6791061.04      2797326.00      6791361.00
      2796976.01      6791960.99
#Sta/Elev= 30
  4688.7  494.33  4699.2  493.72  4730.8  489.78  4741.4  487.80  4836.2  477.01
  4857.3  475.82  4867.9  474.15  4920.6  470.07  4931.1  468.49  4983.8  466.47
  4992.3  464.86  4992.6  464.36  4996.3  464.86  5002.3  468.11  5018.5  467.28
  5136.0  468.48  5216.2  470.41  5289.6  473.45  5349.3  476.89  5392.3  478.14
  5408.0  480.00  5472.5  483.44  5509.7  486.96  5531.2  487.87  5568.4  491.85
  5611.4  495.00  5685.9  503.63  5691.7  503.67  5696.6  505.38  5699.5  505.38
#Mann=4,-1,0
  4688.7     0.1       0  4992.3    0.07       0  4996.3     0.1       0
  5289.6    0.05       0
Bank Sta=4992.3,4996.3
Exp/Cntr=0.3,0.1

Type RM Length L Ch R = 1,23789,328,328,328
BEGIN DESCRIPTION:
Second Caney Creek 42.0
END DESCRIPTION:
XS GIS Cut Line= 3
      2797255.02      6790902.47      2797026.00      6791211.00
      2796726.01      6791510.99
#Sta/Elev= 30
  4610.7  493.61  4624.5  492.29  4637.1  491.02  4645.5  491.22  4651.7  489.15
  4681.0  487.10  4687.2  485.26  4695.6  484.96  4701.8  482.75  4716.4  481.84
  4737.3  478.97  4745.7  478.70  4751.9  477.32  4766.5  476.66  4772.7  475.62
  4781.1  475.39  4837.4  470.05  4872.9  467.50  4908.3  465.95  4987.6  464.78
  5007.1  463.87  5007.3  463.37  5011.1  463.87  5037.4  464.93  5065.7  464.55
  5168.1  466.71  5221.2  467.36  5349.4  472.87  5362.6  473.16  5419.2  477.26
#Mann=6,-1,0
  4610.7    0.05       0  4624.5     0.1       0  5007.1    0.07       0
  5011.1     0.1       0  5168.1    0.12       0  5349.4    0.05       0
Bank Sta=5007.1,5011.1
Exp/Cntr=0.3,0.1

Type RM Length L Ch R = 1,23461,325,325,325
BEGIN DESCRIPTION:
Second Caney Creek 41.0
END DESCRIPTION:
XS GIS Cut Line= 3
      2796952.08      6790808.17      2796776.00      6791011.00
      2796475.97      6791311.03
#Sta/Elev= 30
  4731.6  478.15  4745.2  476.25  4773.7  473.20  4819.6  469.40  4936.1  462.10
  4950.3  461.92  4964.6  461.13  4972.2  461.30  4978.8  460.20  4986.5  459.82
  4993.1  453.73  4994.9  453.52  4995.1  453.02  4998.6  453.02  4998.9  453.52
  5003.7  453.52  5014.3  460.87  5028.5  461.69  5127.5  462.83  5141.6  464.07
  5198.2  466.34  5226.5  468.15  5254.8  470.93  5283.0  472.29  5311.3  475.52
  5339.6  477.43  5367.9  480.34  5396.2  482.58  5410.3  484.96  5424.5  486.02
#Mann=4,-1,0
  4731.6    0.12       0  4819.6    0.05       0  4994.9    0.04       0
  4998.9    0.05       0
Bank Sta=4994.9,4998.9
Exp/Cntr=0.3,0.1

Type RM Length L Ch R = 1,23136,345,345,345
BEGIN DESCRIPTION:
Second Caney Creek 40.0
END DESCRIPTION:
XS GIS Cut Line= 3
      2796875.97      6790711.01      2796626.00      6790761.00
      2796326.03      6790910.99
#Sta/Elev= 30
  4745.4  480.39  4747.9  480.39  4755.6  478.89  4816.8  471.15  4847.4  468.39
  4857.5  467.86  4877.9  465.63  4979.9  460.04  4990.1  458.90  4997.8  456.54
  5003.1  456.54  5006.7  451.52  5007.0  451.02  5010.5  451.02  5010.7  451.52
  5014.3  451.71  5022.7  454.36  5031.1  458.36  5036.7  458.20  5045.0  458.90
  5067.4  459.74  5103.7  460.40  5126.1  461.59  5156.8  464.49  5201.6  469.85
  5215.5  470.78  5246.3  474.59  5291.0  479.06  5299.4  480.47  5335.7  483.13
#Mann=3,-1,0
  4745.4    0.05       0  5006.7    0.04       0  5010.7    0.05       0
Bank Sta=5006.7,5010.7
Exp/Cntr=0.3,0.1

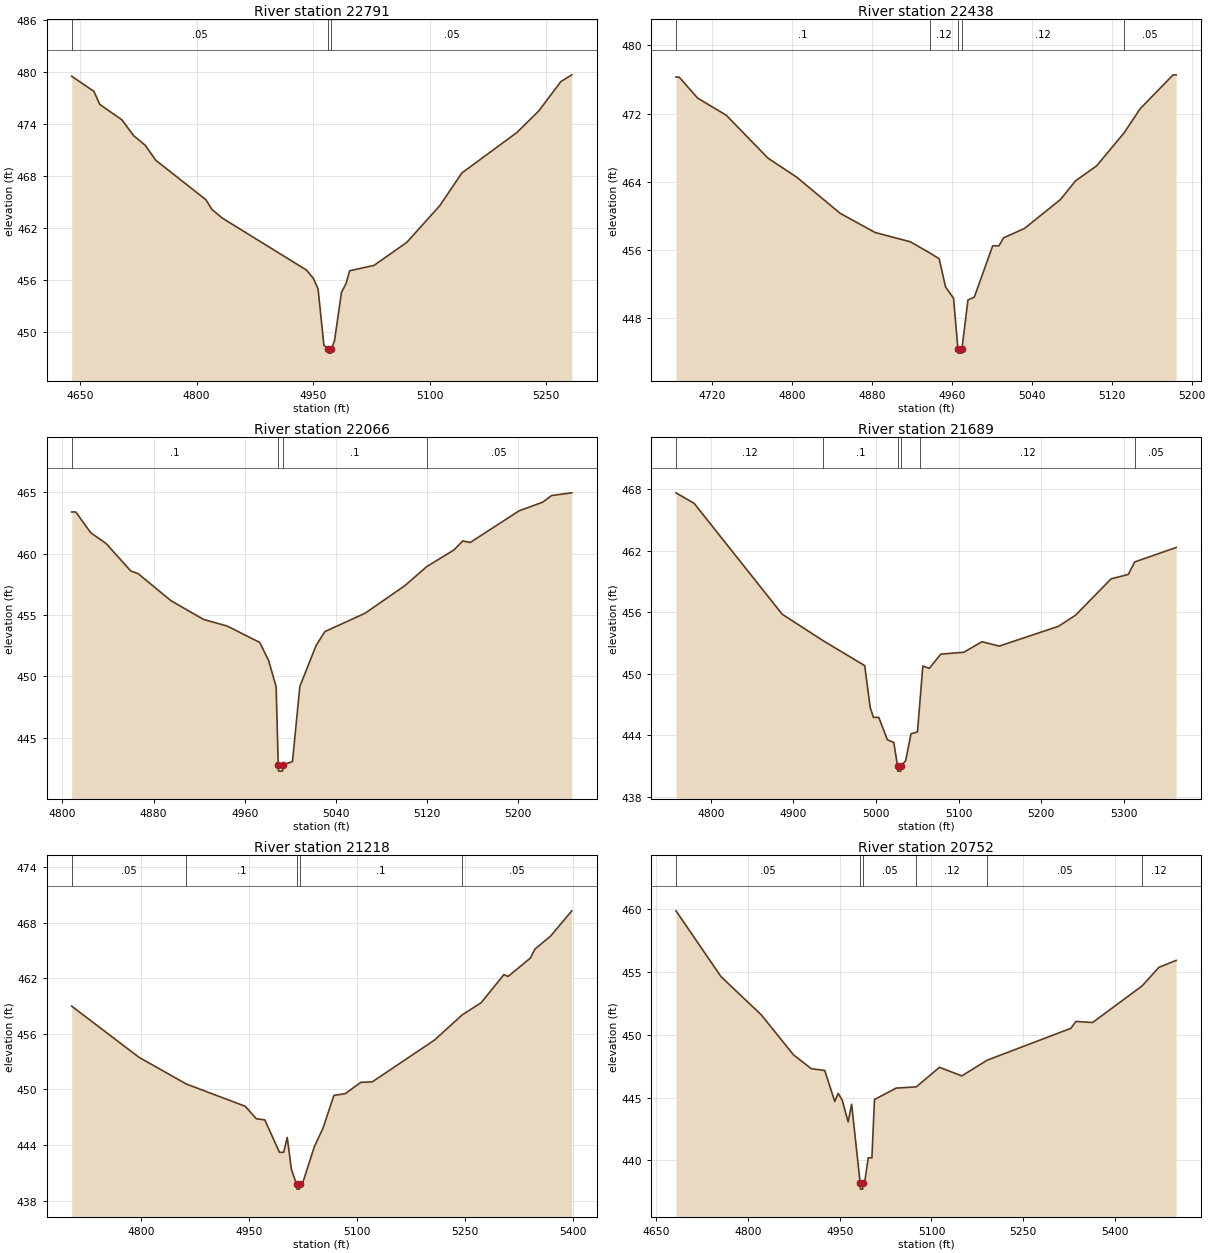
Type RM Length L Ch R = 1,22791,353,353,353
BEGIN DESCRIPTION:
Second Caney Creek 39.0
END DESCRIPTION:
XS GIS Cut Line= 3
      2796626.03      6790210.96      2796426.00      6790511.00
      2796226.03      6790710.97
#Sta/Elev= 30
  4639.4  479.48  4668.0  477.74  4675.5  476.24  4704.0  474.46  4719.1  472.64
  4734.1  471.52  4747.6  469.80  4812.2  465.25  4819.7  464.15  4833.2  463.14
  4941.4  457.16  4950.4  456.19  4956.4  454.98  4963.9  448.49  4969.5  448.09
  4969.7  447.59  4973.2  447.59  4973.5  448.09  4977.5  449.00  4986.5  454.58
  4992.5  455.63  4997.0  457.08  5028.3  457.69  5070.7  460.36  5113.1  464.59
  5141.4  468.34  5212.1  472.99  5240.4  475.49  5268.7  478.86  5282.8  479.64
#Mann=3,-1,0
  4639.4    0.05       0  4969.5    0.04       0  4973.5    0.05       0
Bank Sta=4969.5,4973.5
Exp/Cntr=0.3,0.1

Type RM Length L Ch R = 1,22438,372,372,372
BEGIN DESCRIPTION:
Second Caney Creek 38.0
END DESCRIPTION:
XS GIS Cut Line= 3
      2796326.00      6790111.01      2796126.00      6790361.00
      2796026.01      6790510.98
#Sta/Elev= 30
  4684.0  476.28  4687.2  476.28  4705.6  473.82  4734.4  471.79  4776.0  466.76
  4804.9  464.51  4848.1  460.28  4883.3  458.01  4918.5  456.92  4938.5  455.57
  4947.3  454.93  4953.7  451.62  4961.7  450.28  4966.1  444.33  4966.4  443.83
  4969.9  443.83  4970.1  444.33  4976.1  450.07  4982.5  450.42  5000.9  456.45
  5007.2  456.45  5011.7  457.38  5032.7  458.49  5068.7  461.89  5083.8  464.09
  5104.8  465.84  5132.4  469.73  5148.4  472.56  5181.4  476.55  5184.4  476.55
#Mann=5,-1,0
  4684.0     0.1       0  4938.5    0.12       0  4966.1    0.07       0
  4970.1    0.12       0  5132.4    0.05       0
Bank Sta=4966.1,4970.1
Exp/Cntr=0.3,0.1

Type RM Length L Ch R = 1,22066,377,377,377
BEGIN DESCRIPTION:
Second Caney Creek 37.0
END DESCRIPTION:
XS GIS Cut Line= 3
      2796069.21      6789941.36      2795926.00      6790061.00
      2795763.29      6790253.94
#Sta/Elev= 30
  4808.1  463.40  4811.7  463.40  4824.9  461.70  4838.3  460.83  4860.0  458.59
  4866.5  458.37  4895.2  456.17  4923.8  454.64  4944.6  454.10  4973.2  452.76
  4981.0  451.28  4987.6  449.14  4989.4  442.77  4989.7  442.27  4993.2  442.27
  4993.4  442.77  5001.9  443.05  5008.4  449.18  5022.7  452.52  5030.4  453.65
  5065.6  455.14  5100.7  457.40  5119.7  458.94  5143.6  460.30  5151.4  461.04
  5157.9  460.91  5200.8  463.49  5221.6  464.20  5229.4  464.74  5247.1  464.96
#Mann=4,-1,0
  4808.1     0.1       0  4989.4    0.07       0  4993.4     0.1       0
  5119.7    0.05       0
Bank Sta=4989.4,4993.4
Exp/Cntr=0.3,0.1

Type RM Length L Ch R = 1,21689,471,471,471
BEGIN DESCRIPTION:
Second Caney Creek 36.0
END DESCRIPTION:
XS GIS Cut Line= 3
      2795883.54      6789577.24      2795726.00      6789761.00
      2795492.88      6790039.19
#Sta/Elev= 30
  4758.0  467.64  4780.0  466.61  4886.5  455.80  4936.4  453.20  4986.3  450.79
  4992.9  446.72  4996.8  445.74  5003.3  445.74  5013.7  443.56  5021.5  443.29
  5026.0  441.00  5026.3  440.50  5029.8  440.50  5030.0  441.00  5035.8  441.51
  5042.3  444.14  5050.1  444.32  5053.5  447.68  5056.6  450.75  5064.4  450.52
  5078.3  451.91  5106.1  452.09  5128.2  453.12  5149.0  452.69  5220.6  454.62
  5241.4  455.71  5284.3  459.25  5305.1  459.68  5312.9  460.90  5363.0  462.31
#Mann=6,-1,0
  4758.0    0.12       0  4936.4     0.1       0  5026.0    0.07       0
  5030.0     0.1       0  5053.5    0.12       0  5312.9    0.05       0
Bank Sta=5026,5030
Exp/Cntr=0.3,0.1

Type RM Length L Ch R = 1,21218,466,466,466
BEGIN DESCRIPTION:
Second Caney Creek 35.0
END DESCRIPTION:
XS GIS Cut Line= 3
      2795525.98      6789261.03      2795376.00      6789511.00
      2795176.01      6789860.98
#Sta/Elev= 30
  4704.1  458.99  4797.4  453.48  4863.3  450.59  4945.1  448.19  4960.6  446.84
  4972.3  446.72  4992.7  443.22  4998.5  443.22  5003.5  444.83  5009.3  441.36
  5016.6  439.75  5016.9  439.25  5020.4  439.25  5020.7  439.75  5025.1  439.95
  5041.0  443.80  5053.2  445.83  5068.3  449.36  5084.1  449.55  5105.7  450.77
  5121.6  450.82  5208.0  455.33  5246.7  458.06  5272.7  459.35  5304.4  462.39
  5310.2  462.19  5341.1  464.17  5347.6  465.15  5369.2  466.54  5398.7  469.27
#Mann=5,-1,0
  4704.1    0.05       0  4863.3     0.1       0  5016.6    0.07       0
  5020.7     0.1       0  5246.7    0.05       0
Bank Sta=5016.6,5020.7
Exp/Cntr=0.3,0.1

Type RM Length L Ch R = 1,20752,451,451,451
BEGIN DESCRIPTION:
Second Caney Creek 34.0
END DESCRIPTION:
XS GIS Cut Line= 3
      2795405.04      6789010.83      2795126.00      6789161.00
      2794725.98      6789461.01
#Sta/Elev= 30
  4682.7  459.84  4756.2  454.61  4821.9  451.58  4874.7  448.39  4903.8  447.29
  4925.7  447.15  4942.0  444.69  4947.7  445.33  4954.2  444.80  4963.9  443.06
  4969.6  444.47  4983.5  438.22  4984.0  437.72  4987.6  437.72  4988.0  438.22
  4991.5  438.47  4996.7  440.21  5002.7  440.21  5006.9  444.84  5042.3  445.75
  5075.2  445.85  5113.1  447.40  5149.6  446.72  5191.0  447.97  5327.7  450.50
  5336.0  451.05  5363.1  450.96  5444.2  453.88  5471.5  455.35  5499.6  455.90
#Mann=6,-1,0
  4682.7    0.05       0  4983.5    0.04       0  4988.0    0.05       0
  5075.2    0.12       0  5191.0    0.05       0  5444.2    0.12       0
Bank Sta=4983.5,4988
Exp/Cntr=0.3,0.1

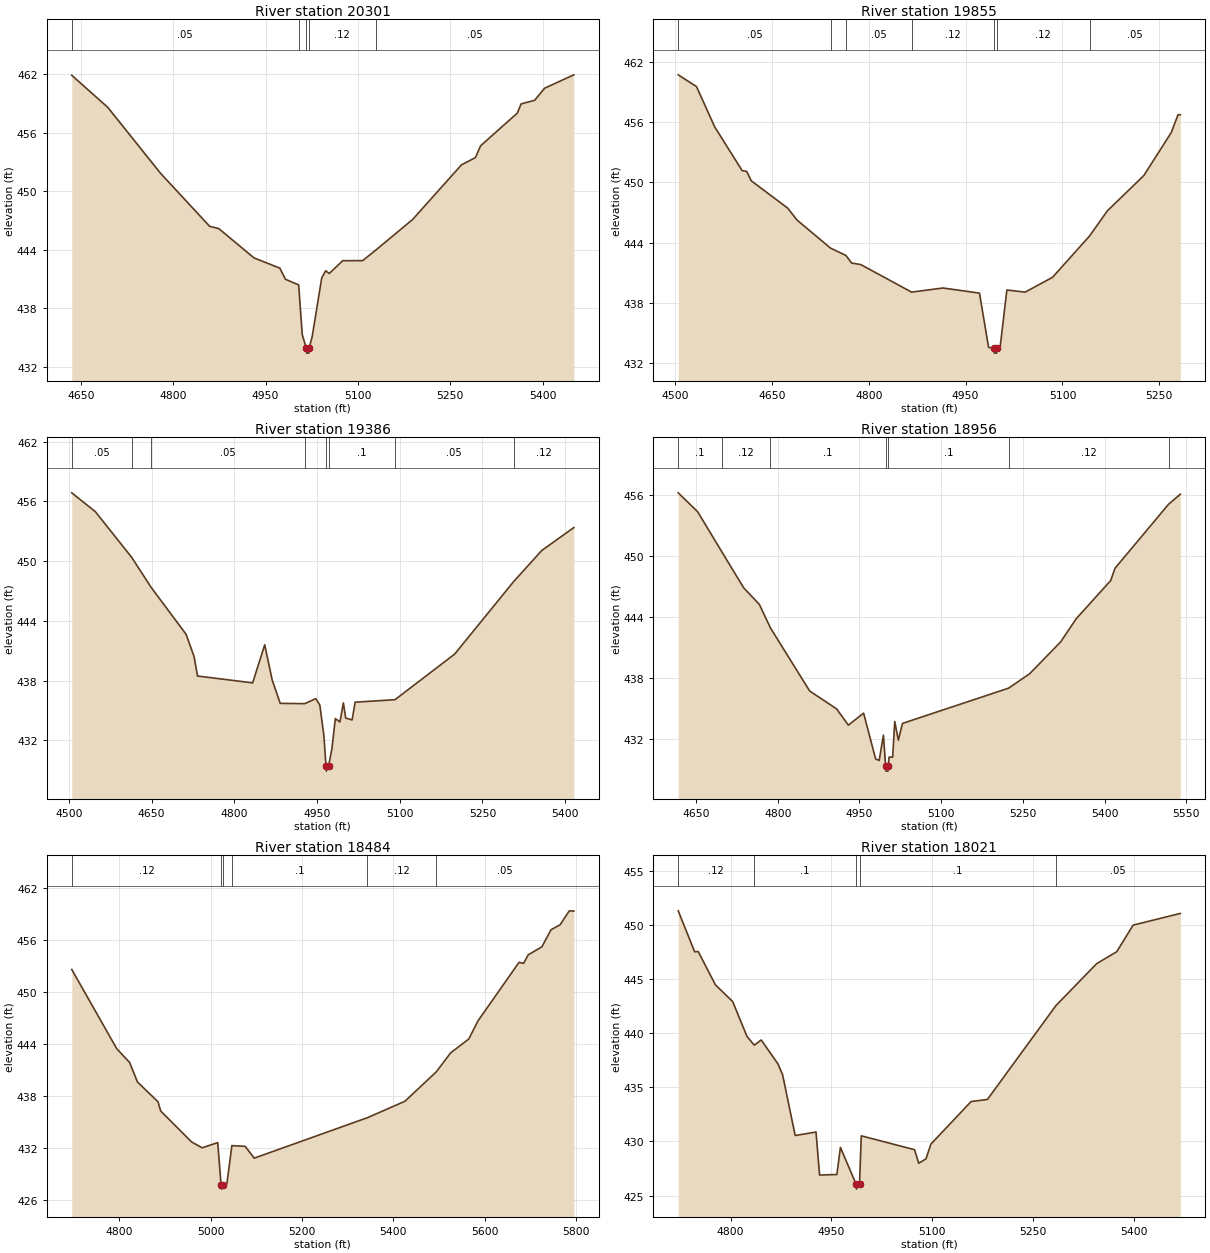
Type RM Length L Ch R = 1,20301,446,446,446
BEGIN DESCRIPTION:
Second Caney Creek 33.0
END DESCRIPTION:
XS GIS Cut Line= 3
      2795276.02      6788560.99      2794976.00      6788761.00
      2794575.15      6788976.33
#Sta/Elev= 30
  4635.2  461.88  4693.8  458.59  4779.4  451.84  4859.1  446.41  4874.1  446.17
  4931.2  443.17  4973.2  442.12  4982.3  440.98  5003.8  440.40  5009.6  435.31
  5016.2  433.91  5016.7  433.41  5020.3  433.41  5020.8  433.91  5025.8  435.12
  5041.2  441.10  5047.7  441.85  5053.4  441.57  5075.3  442.88  5107.8  442.89
  5128.7  443.95  5188.8  447.10  5268.2  452.70  5290.9  453.45  5299.4  454.66
  5359.0  458.01  5365.1  458.95  5387.1  459.32  5403.3  460.56  5450.8  461.93
#Mann=5,-1,0
  4635.2    0.05       0  5003.8    0.12       0  5016.2    0.04       0
  5020.8    0.12       0  5128.7    0.05       0
Bank Sta=5016.2,5020.8
Exp/Cntr=0.3,0.1

Type RM Length L Ch R = 1,19855,469,469,469
BEGIN DESCRIPTION:
Second Caney Creek 32.0
END DESCRIPTION:
XS GIS Cut Line= 3
      2795076.00      6788111.00      2794726.00      6788461.00
      2794526.01      6788660.99
#Sta/Elev= 30
  4504.8  460.71  4533.1  459.54  4561.4  455.52  4603.8  451.18  4610.9  451.10
  4617.9  450.17  4674.5  447.44  4688.7  446.27  4740.7  443.47  4764.5  442.74
  4773.5  441.98  4787.6  441.83  4866.3  439.09  4914.9  439.50  4971.5  438.99
  4985.6  433.59  4993.9  433.52  4994.4  433.02  4998.0  433.02  4998.5  433.52
  5003.3  433.52  5013.9  439.30  5042.2  439.09  5084.6  440.56  5142.1  444.68
  5169.5  447.17  5226.1  450.69  5268.5  454.96  5279.1  456.74  5282.6  456.74
#Mann=7,-1,0
  4504.8    0.05       0  4740.7    0.12       0  4764.5    0.05       0
  4866.3    0.12       0  4993.9    0.07       0  4998.5    0.12       0
  5142.1    0.05       0
Bank Sta=4993.9,4998.5
Exp/Cntr=0.3,0.1

Type RM Length L Ch R = 1,19386,430,430,430
BEGIN DESCRIPTION:
Second Caney Creek 31.0
END DESCRIPTION:
XS GIS Cut Line= 3
      2794775.99      6787711.01      2794476.00      6788111.00
      2794296.45      6788480.38
#Sta/Elev= 30
  4505.2  456.87  4547.9  454.98  4613.7  450.40  4649.4  447.35  4712.5  442.66
  4727.1  440.41  4733.3  438.46  4833.3  437.77  4855.2  441.60  4868.7  438.07
  4883.3  435.71  4927.9  435.68  4947.9  436.19  4955.2  435.53  4962.5  432.48
  4966.4  429.40  4966.9  428.90  4971.0  429.40  4977.1  431.17  4983.3  434.18
  4991.6  433.84  4997.9  435.76  5002.1  434.23  5013.7  434.05  5019.2  435.83
  5091.5  436.08  5199.7  440.66  5306.6  447.94  5357.6  451.07  5415.9  453.38
#Mann=8,-1,0
  4505.2    0.05       0  4613.7    0.12       0  4649.4    0.05       0
  4927.9     0.1       0  4966.4    0.07       0  4971.0     0.1       0
  5091.5    0.05       0  5306.6    0.12       0
Bank Sta=4966.4,4971
Exp/Cntr=0.3,0.1

Type RM Length L Ch R = 1,18956,472,472,472
BEGIN DESCRIPTION:
Second Caney Creek 30.0
END DESCRIPTION:
XS GIS Cut Line= 3
      2794425.98      6787561.02      2794176.00      6787861.00
      2793775.99      6788211.01
#Sta/Elev= 30
  4617.2  456.23  4653.0  454.36  4697.9  450.36  4737.6  446.86  4766.2  445.24
  4786.5  442.93  4858.6  436.71  4908.1  434.95  4929.6  433.35  4957.6  434.53
  4979.7  430.02  4986.2  429.87  4994.0  432.36  4998.1  429.32  4998.7  428.82
  5002.4  428.82  5002.9  429.32  5004.4  430.20  5011.0  430.20  5014.8  433.71
  5021.4  431.87  5029.0  433.52  5223.8  436.99  5262.5  438.41  5319.5  441.55
  5347.9  443.82  5411.5  447.60  5419.1  448.79  5517.7  455.11  5539.2  456.09
#Mann=7,-1,0
  4617.2     0.1       0  4697.9    0.12       0  4786.5     0.1       0
  4998.1    0.07       0  5002.9     0.1       0  5223.8    0.12       0
  5517.7     0.1       0
Bank Sta=4998.1,5002.9
Exp/Cntr=0.3,0.1

Type RM Length L Ch R = 1,18484,463,463,463
BEGIN DESCRIPTION:
Second Caney Creek 29.0
END DESCRIPTION:
XS GIS Cut Line= 3
      2794346.46      6787381.91      2794076.00      6787511.00
      2793275.99      6787511.00
#Sta/Elev= 30
  4695.8  452.57  4794.3  443.45  4822.6  441.85  4839.7  439.61  4884.7  437.33
  4890.6  436.27  4958.7  432.69  4981.4  432.03  5015.5  432.63  5022.8  427.77
  5023.6  427.27  5028.1  427.77  5035.5  427.87  5046.5  432.28  5075.5  432.20
  5095.5  430.84  5343.4  435.50  5425.5  437.39  5494.4  440.79  5525.5  442.96
  5565.5  444.57  5585.5  446.65  5675.5  453.40  5685.5  453.28  5695.5  454.26
  5725.5  455.18  5745.5  457.15  5765.5  457.73  5785.5  459.33  5795.5  459.30
#Mann=6,-1,0
  4695.8    0.12       0  5022.8    0.07       0  5028.1    0.12       0
  5046.5     0.1       0  5343.4    0.12       0  5494.4    0.05       0
Bank Sta=5022.8,5028.1
Exp/Cntr=0.3,0.1

Type RM Length L Ch R = 1,18021,443,443,443
BEGIN DESCRIPTION:
Second Caney Creek 28.0
END DESCRIPTION:
XS GIS Cut Line= 3
      2794142.37      6787017.35      2793876.00      6787111.00
      2793444.01      6787281.02
#Sta/Elev= 30
  4722.2  451.29  4746.6  447.51  4751.9  447.53  4777.5  444.46  4803.2  442.91
  4824.4  439.70  4835.3  438.89  4845.6  439.37  4870.5  437.16  4877.4  436.16
  4896.1  430.55  4927.1  430.87  4932.4  426.90  4958.1  426.95  4963.4  429.45
  4986.4  426.10  4987.2  425.60  4991.8  426.10  4994.4  430.52  5073.6  429.24
  5079.8  427.99  5090.5  428.39  5098.0  429.76  5157.6  433.68  5182.0  433.88
  5283.8  442.54  5344.5  446.42  5374.2  447.51  5398.6  449.97  5468.8  451.05
#Mann=5,-1,0
  4722.2    0.12       0  4835.3     0.1       0  4986.4    0.07       0
  4991.8     0.1       0  5283.8    0.05       0
Bank Sta=4986.4,4991.8
Exp/Cntr=0.3,0.1

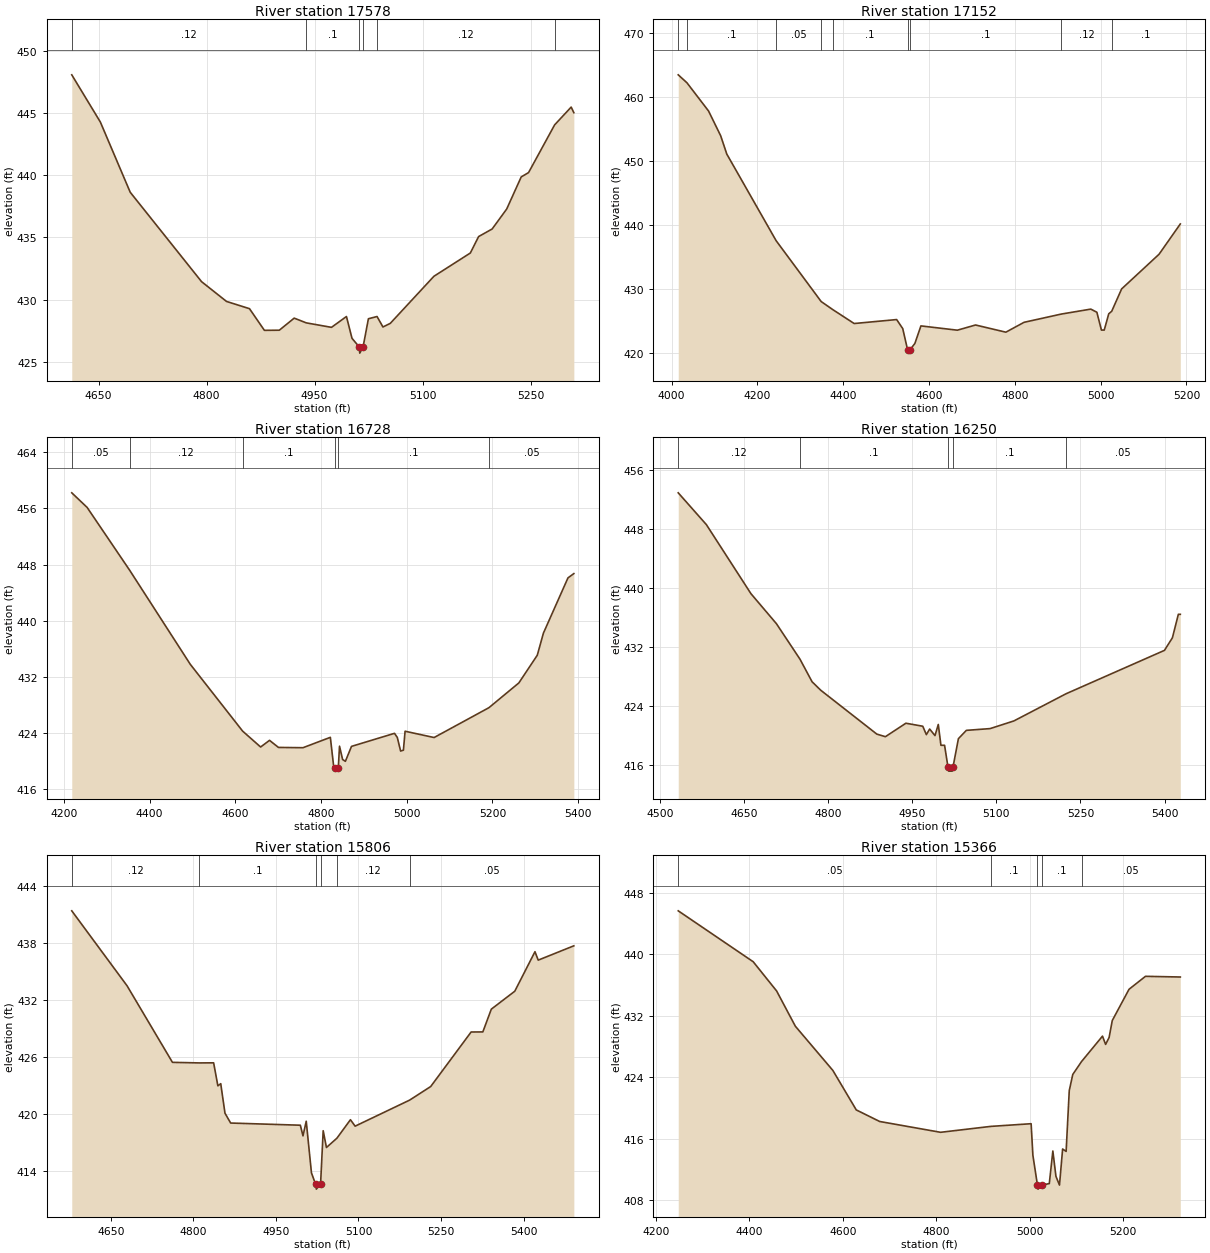
Type RM Length L Ch R = 1,17578,426,426,426
BEGIN DESCRIPTION:
Second Caney Creek 27.0
END DESCRIPTION:
XS GIS Cut Line= 3
      2794004.35      6786658.80      2793626.00      6786761.00
      2793323.74      6786806.02
#Sta/Elev= 30
  4612.7  448.05  4652.4  444.26  4693.9  438.62  4793.0  431.44  4827.7  429.85
  4859.6  429.27  4880.3  427.53  4901.0  427.54  4921.7  428.51  4938.5  428.13
  4973.5  427.77  4994.3  428.64  5002.0  426.89  5012.0  426.20  5012.8  425.70
  5017.4  426.20  5024.8  428.46  5036.8  428.64  5045.0  427.80  5055.2  428.09
  5115.8  431.87  5166.4  433.74  5177.9  435.06  5196.7  435.67  5216.9  437.27
  5237.1  439.85  5247.3  440.20  5283.5  444.03  5306.5  445.46  5310.2  445.01
#Mann=6,-1,0
  4612.7    0.12       0  4938.5     0.1       0  5012.0    0.07       0
  5017.4     0.1       0  5036.8    0.12       0  5283.5     0.1       0
Bank Sta=5012,5017.4
Exp/Cntr=0.3,0.1

Type RM Length L Ch R = 1,17152,424,424,424
BEGIN DESCRIPTION:
Second Caney Creek 26.0
END DESCRIPTION:
XS GIS Cut Line= 3
      2794126.02      6785710.98      2793426.00      6786411.00
      2793275.96      6786511.03
#Sta/Elev= 30
  4015.4  463.41  4035.7  462.17  4086.1  457.76  4114.4  453.89  4128.6  451.04
  4243.6  437.52  4348.6  428.02  4375.7  426.76  4425.5  424.59  4524.5  425.21
  4538.7  423.80  4550.1  420.47  4550.9  419.97  4555.5  420.47  4567.0  421.48
  4581.1  424.22  4666.0  423.55  4708.4  424.36  4779.1  423.24  4821.5  424.78
  4908.6  426.07  4977.1  426.84  4991.2  426.35  5001.8  423.57  5008.4  423.57
  5018.9  426.11  5025.8  426.50  5048.9  429.99  5136.1  435.40  5185.7  440.13
#Mann=9,-1,0
  4015.4    0.05       0  4035.7     0.1       0  4243.6    0.05       0
  4348.6    0.12       0  4375.7     0.1       0  4550.1    0.07       0
  4555.5     0.1       0  4908.6    0.12       0  5025.8     0.1       0
Bank Sta=4550.1,4555.5
Exp/Cntr=0.3,0.1

Type RM Length L Ch R = 1,16728,478,478,478
BEGIN DESCRIPTION:
Second Caney Creek 25.0
END DESCRIPTION:
XS GIS Cut Line= 3
      2793876.02      6785560.98      2793276.00      6786061.00
      2792975.97      6786311.02
#Sta/Elev= 30
  4218.4  458.23  4254.2  456.15  4353.7  447.17  4495.0  433.77  4617.2  424.24
  4659.1  421.98  4679.9  422.93  4700.7  421.92  4758.0  421.88  4821.8  423.36
  4829.6  419.19  4831.8  419.04  4833.0  418.54  4840.4  419.04  4843.2  422.10
  4850.4  420.20  4856.9  419.94  4871.2  422.07  4971.5  423.93  4978.0  423.35
  4985.8  421.40  4992.3  421.53  4996.2  424.23  5063.9  423.33  5191.9  427.59
  5261.7  431.12  5304.7  435.07  5319.0  438.22  5376.3  446.10  5390.0  446.71
#Mann=6,-1,0
  4218.4    0.05       0  4353.7    0.12       0  4617.2     0.1       0
  4831.8    0.07       0  4840.4     0.1       0  5191.9    0.05       0
Bank Sta=4831.8,4840.4
Exp/Cntr=0.3,0.1

Type RM Length L Ch R = 1,16250,444,444,444
BEGIN DESCRIPTION:
Second Caney Creek 24.0
END DESCRIPTION:
XS GIS Cut Line= 3
      2793626.03      6785460.98      2793226.00      6785711.00
      2792926.00      6786011.00
#Sta/Elev= 30
  4532.2  452.95  4582.4  448.63  4662.0  439.24  4707.4  435.17  4749.5  430.34
  4771.0  427.28  4786.4  426.13  4886.6  420.16  4901.9  419.81  4938.5  421.64
  4968.6  421.23  4975.0  420.09  4980.9  420.85  4990.4  419.96  4996.3  421.47
  5001.0  418.64  5007.5  418.64  5013.7  415.63  5015.0  415.13  5021.1  415.13
  5022.4  415.63  5032.2  419.54  5046.4  420.67  5088.8  420.91  5131.2  421.95
  5224.2  425.64  5399.9  431.54  5414.1  433.25  5424.7  436.44  5428.2  436.44
#Mann=5,-1,0
  4532.2    0.12       0  4749.5     0.1       0  5013.7    0.07       0
  5022.4     0.1       0  5224.2    0.05       0
Bank Sta=5013.7,5022.4
Exp/Cntr=0.3,0.1

Type RM Length L Ch R = 1,15806,440,440,440
BEGIN DESCRIPTION:
Second Caney Creek 23.0
END DESCRIPTION:
XS GIS Cut Line= 3
      2793425.98      6785261.00      2793026.00      6785361.00
      2792600.17      6785622.49
#Sta/Elev= 30
  4579.2  441.41  4679.7  433.50  4762.1  425.43  4811.2  425.37  4836.9  425.38
  4844.6  422.95  4849.8  423.18  4857.5  420.07  4867.8  419.03  4994.4  418.80
  4999.2  417.68  5005.1  419.22  5014.6  413.77  5022.2  412.56  5023.5  412.06
  5031.1  412.56  5035.9  418.22  5041.8  416.45  5060.8  417.43  5085.4  419.38
  5093.9  418.70  5193.0  421.45  5231.2  422.88  5304.6  428.63  5325.9  428.64
  5341.3  431.04  5383.9  432.93  5420.6  437.10  5426.5  436.21  5491.2  437.72
#Mann=6,-1,0
  4579.2    0.12       0  4811.2     0.1       0  5022.2    0.07       0
  5031.1     0.1       0  5060.8    0.12       0  5193.0    0.05       0
Bank Sta=5022.2,5031.1
Exp/Cntr=0.3,0.1

Type RM Length L Ch R = 1,15366,471,471,471
BEGIN DESCRIPTION:
Second Caney Creek 22.0
END DESCRIPTION:
XS GIS Cut Line= 3
      2793526.02      6785111.00      2792776.00      6785061.00
      2792534.66      6785274.94
#Sta/Elev= 30
  4247.9  445.69  4408.3  439.05  4458.4  435.24  4498.5  430.64  4578.7  424.88
  4628.8  419.73  4678.9  418.22  4809.2  416.81  4916.5  417.58  5002.9  417.93
  5006.7  413.81  5016.5  409.90  5017.8  409.40  5025.4  409.90  5041.8  410.13
  5049.4  414.37  5056.0  411.07  5063.6  409.93  5070.3  414.63  5077.8  414.32
  5084.5  422.24  5092.0  424.35  5110.7  426.03  5155.6  429.35  5162.3  428.27
  5169.8  429.18  5176.5  431.38  5212.4  435.46  5247.6  437.15  5322.1  437.06
#Mann=5,-1,0
  4247.9    0.05       0  4916.5     0.1       0  5016.5    0.07       0
  5025.4     0.1       0  5110.7    0.05       0
Bank Sta=5016.5,5025.4
Exp/Cntr=0.3,0.1