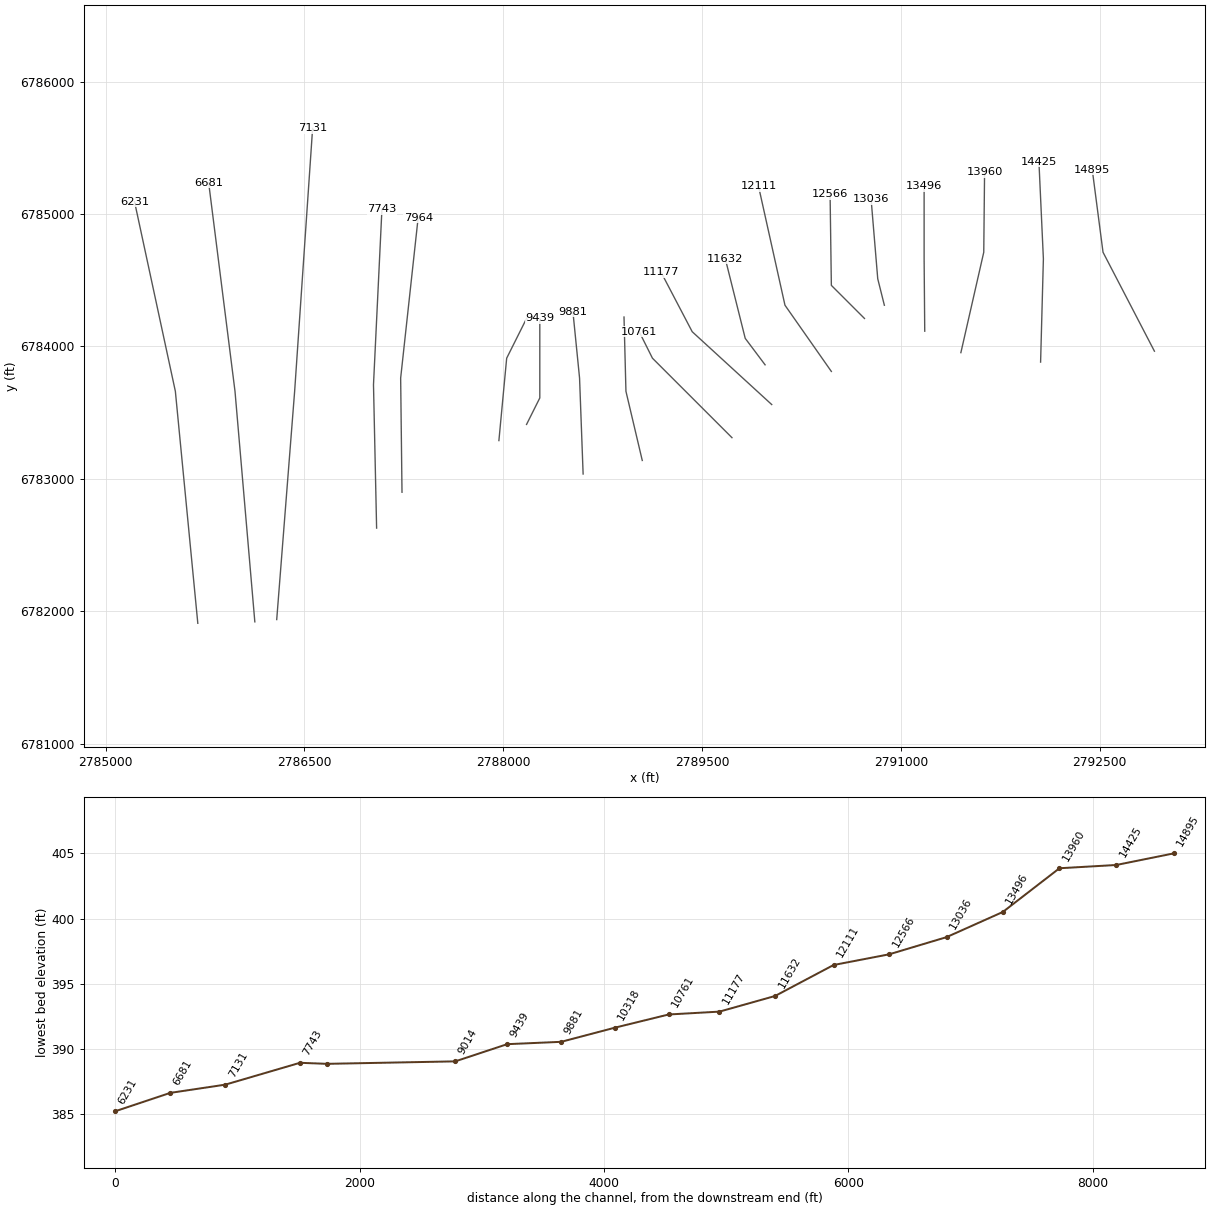
HEC-RAS study Second Caney Creek.prj: Second Caney Creek Base Level Engineering

--- Second Caney Creek.g01 (geometry) --- (continued)

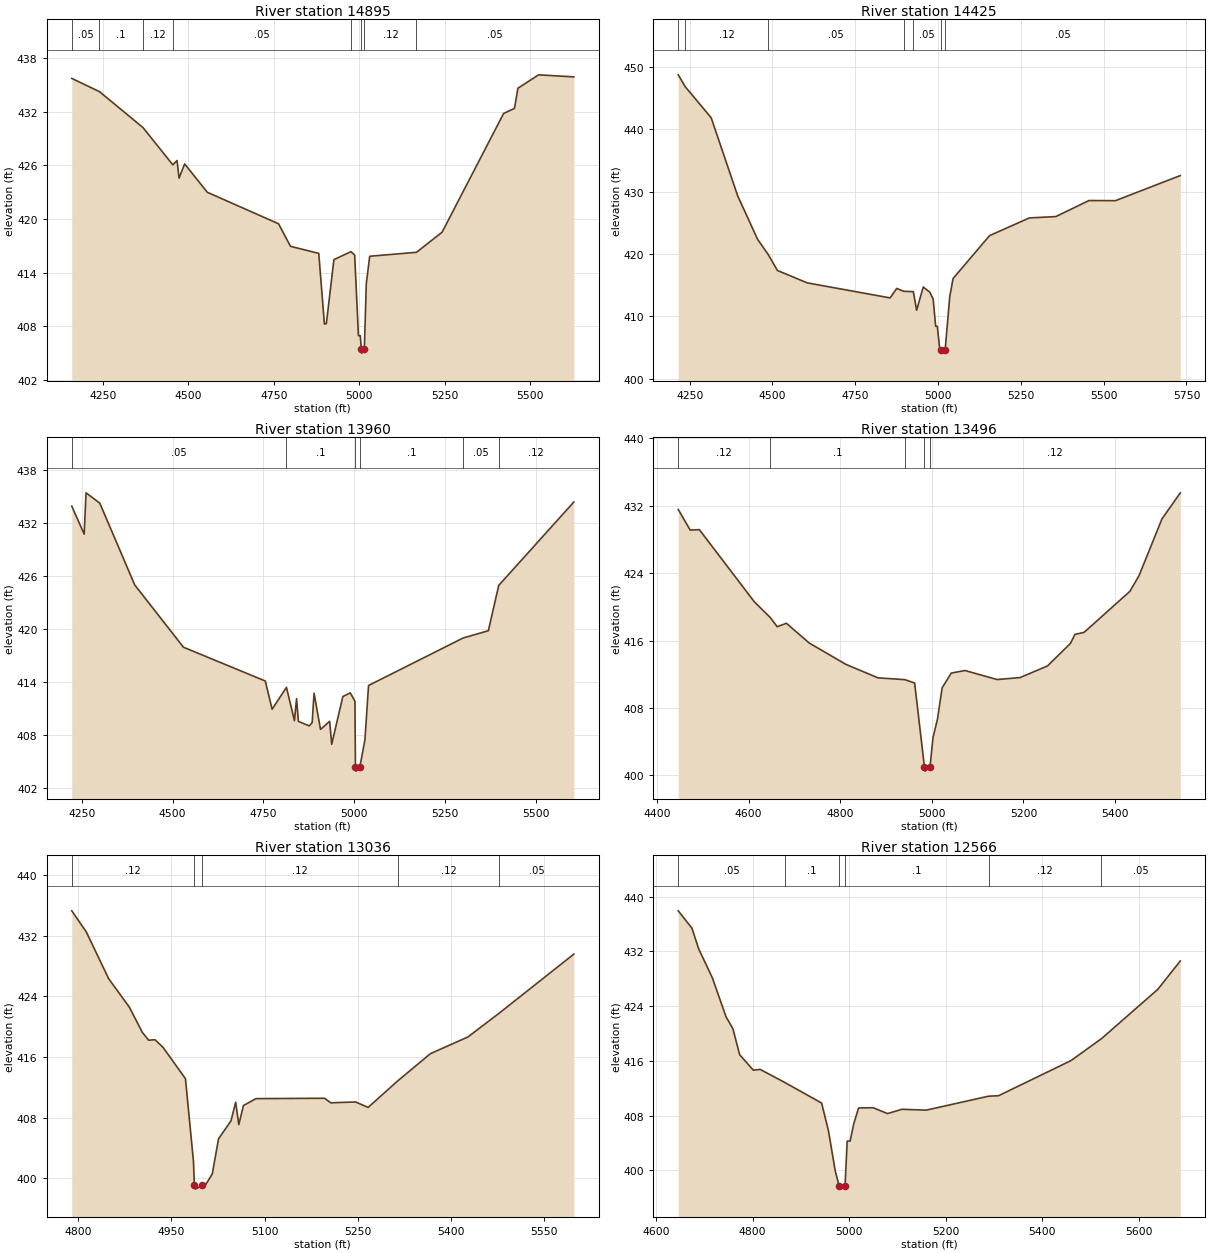
Type RM Length L Ch R = 1,14895,470,470,470
BEGIN DESCRIPTION:
Second Caney Creek 21.0
END DESCRIPTION:
XS GIS Cut Line= 3
      2792913.82      6783963.98      2792526.00      6784711.00
      2792444.88      6785333.25
#Sta/Elev= 30
  4158.7  435.71  4239.8  434.23  4367.0  430.22  4454.4  426.05  4466.9  426.53
  4472.6  424.56  4489.0  426.15  4555.4  422.98  4763.8  419.46  4798.7  416.94
  4881.5  416.15  4898.0  408.25  4903.7  408.30  4925.8  415.45  4975.5  416.34
  4986.5  415.97  4997.6  406.95  5002.9  406.95  5006.0  405.50  5007.3  405.00
  5014.9  405.50  5020.6  412.79  5030.6  415.83  5167.4  416.27  5242.4  418.52
  5422.4  431.79  5454.2  432.36  5464.3  434.61  5524.8  436.11  5627.9  435.88
#Mann=8,-1,0
  4158.7    0.05       0  4239.8     0.1       0  4367.0    0.12       0
  4454.4    0.05       0  4975.5    0.12       0  5006.0    0.07       0
  5014.9    0.12       0  5167.4    0.05       0
Bank Sta=5006,5014.9
Exp/Cntr=0.3,0.1

Type RM Length L Ch R = 1,14425,465,465,465
BEGIN DESCRIPTION:
Second Caney Creek 20.0
END DESCRIPTION:
XS GIS Cut Line= 3
      2792054.90      6783881.57      2792076.00      6784661.00
      2792042.25      6785396.31
#Sta/Elev= 30
  4215.6  448.76  4236.7  446.86  4315.1  441.87  4395.1  429.34  4455.1  422.38
  4487.6  419.90  4515.1  417.37  4605.2  415.38  4855.3  412.97  4875.3  414.49
  4896.2  414.03  4925.4  413.97  4935.3  410.99  4955.3  414.72  4975.3  413.88
  4985.3  412.75  4992.8  408.42  4997.8  408.42  5005.3  404.65  5009.3  404.61
  5010.9  404.11  5021.4  404.61  5035.4  413.21  5045.4  416.08  5155.5  422.96
  5275.6  425.80  5355.7  426.02  5455.8  428.59  5535.7  428.57  5731.4  432.60
#Mann=7,-1,0
  4215.6    0.05       0  4236.7    0.12       0  4487.6    0.05       0
  4896.2     0.1       0  4925.4    0.05       0  5009.3    0.04       0
  5021.4    0.05       0
Bank Sta=5009.3,5021.4
Exp/Cntr=0.3,0.1

Type RM Length L Ch R = 1,13960,464,464,464
BEGIN DESCRIPTION:
Second Caney Creek 19.0
END DESCRIPTION:
XS GIS Cut Line= 3
      2791453.34      6783952.92      2791626.00      6784711.00
      2791632.17      6785316.48
#Sta/Elev= 30
  4222.5  433.91  4256.7  430.74  4261.8  435.42  4299.7  434.25  4396.0  424.97
  4530.2  417.91  4755.6  414.08  4774.4  410.88  4813.9  413.36  4835.9  409.58
  4841.7  412.08  4846.8  409.50  4876.9  408.99  4884.7  409.38  4889.9  412.70
  4907.7  408.59  4932.9  409.51  4938.5  406.90  4969.2  412.32  4989.7  412.74
  5002.5  411.79  5003.9  404.36  5005.6  403.86  5016.1  404.36  5030.0  407.40
  5040.0  413.57  5300.6  418.96  5370.0  419.78  5398.6  424.92  5605.5  434.38
#Mann=6,-1,0
  4222.5    0.05       0  4813.9     0.1       0  5003.9    0.07       0
  5016.1     0.1       0  5300.6    0.05       0  5398.6    0.12       0
Bank Sta=5003.9,5016.1
Exp/Cntr=0.3,0.1

Type RM Length L Ch R = 1,13496,460,460,460
BEGIN DESCRIPTION:
Second Caney Creek 18.0
END DESCRIPTION:
XS GIS Cut Line= 3
      2791180.65      6784114.92      2791176.00      6784661.00
      2791176.00      6785211.00
#Sta/Elev= 30
  4446.3  431.56  4472.4  429.11  4492.4  429.16  4612.4  420.60  4646.8  418.75
  4662.4  417.64  4682.4  418.05  4732.4  415.70  4812.4  413.17  4882.4  411.57
  4940.6  411.36  4962.4  410.96  4983.8  401.00  4985.5  400.50  4996.0  401.00
  5002.4  404.45  5012.4  406.71  5022.4  410.38  5042.4  412.14  5072.4  412.44
  5142.4  411.37  5192.4  411.60  5252.4  412.98  5302.4  415.65  5312.4  416.73
  5332.4  416.97  5432.4  421.84  5452.4  423.71  5502.4  430.44  5542.4  433.53
#Mann=5,-1,0
  4446.3    0.12       0  4646.8     0.1       0  4940.6    0.12       0
  4983.8    0.07       0  4996.0    0.12       0
Bank Sta=4983.8,4996
Exp/Cntr=0.3,0.1

Type RM Length L Ch R = 1,13036,470,470,470
BEGIN DESCRIPTION:
Second Caney Creek 17.0
END DESCRIPTION:
XS GIS Cut Line= 3
      2790876.00      6784310.98      2790826.00      6784511.00
      2790776.00      6785111.05
#Sta/Elev= 30
  4789.7  435.29  4812.9  432.54  4849.0  426.35  4882.5  422.57  4903.1  419.28
  4913.4  418.22  4923.7  418.28  4936.6  417.28  4972.7  413.15  4985.6  402.25
  4987.1  399.07  4988.9  398.57  4999.4  399.07  5005.9  399.23  5015.9  400.57
  5026.0  405.21  5046.0  407.57  5053.6  410.04  5058.6  407.08  5066.1  409.60
  5086.2  410.51  5196.6  410.56  5206.6  409.96  5246.7  410.07  5266.8  409.35
  5314.2  412.83  5367.2  416.45  5427.4  418.64  5478.2  421.81  5598.0  429.58
#Mann=5,-1,0
  4789.7    0.12       0  4987.1    0.07       0  4999.4    0.12       0
  5314.2    0.12       0  5478.2    0.05       0
Bank Sta=4987.1,4999.4
Exp/Cntr=0.3,0.1

Type RM Length L Ch R = 1,12566,455,455,455
BEGIN DESCRIPTION:
Second Caney Creek 16.0
END DESCRIPTION:
XS GIS Cut Line= 3
      2790726.02      6784210.98      2790476.00      6784461.00
      2790466.44      6785147.46
#Sta/Elev= 30
  4646.1  437.92  4674.4  435.40  4688.5  432.36  4716.8  428.13  4745.1  422.44
  4759.3  420.70  4773.4  416.89  4801.7  414.63  4815.8  414.75  4866.4  412.85
  4943.1  409.83  4957.2  405.82  4971.4  399.89  4979.4  397.75  4981.1  397.25
  4991.7  397.75  4996.1  404.27  5002.2  404.27  5009.7  406.80  5019.7  409.11
  5049.7  409.15  5079.7  408.29  5109.7  408.92  5159.7  408.79  5289.0  410.83
  5309.7  410.90  5459.7  416.03  5522.9  419.24  5639.7  426.45  5686.2  430.60
#Mann=6,-1,0
  4646.1    0.05       0  4866.4     0.1       0  4979.4    0.07       0
  4991.7     0.1       0  5289.0    0.12       0  5522.9    0.05       0
Bank Sta=4979.4,4991.7
Exp/Cntr=0.3,0.1

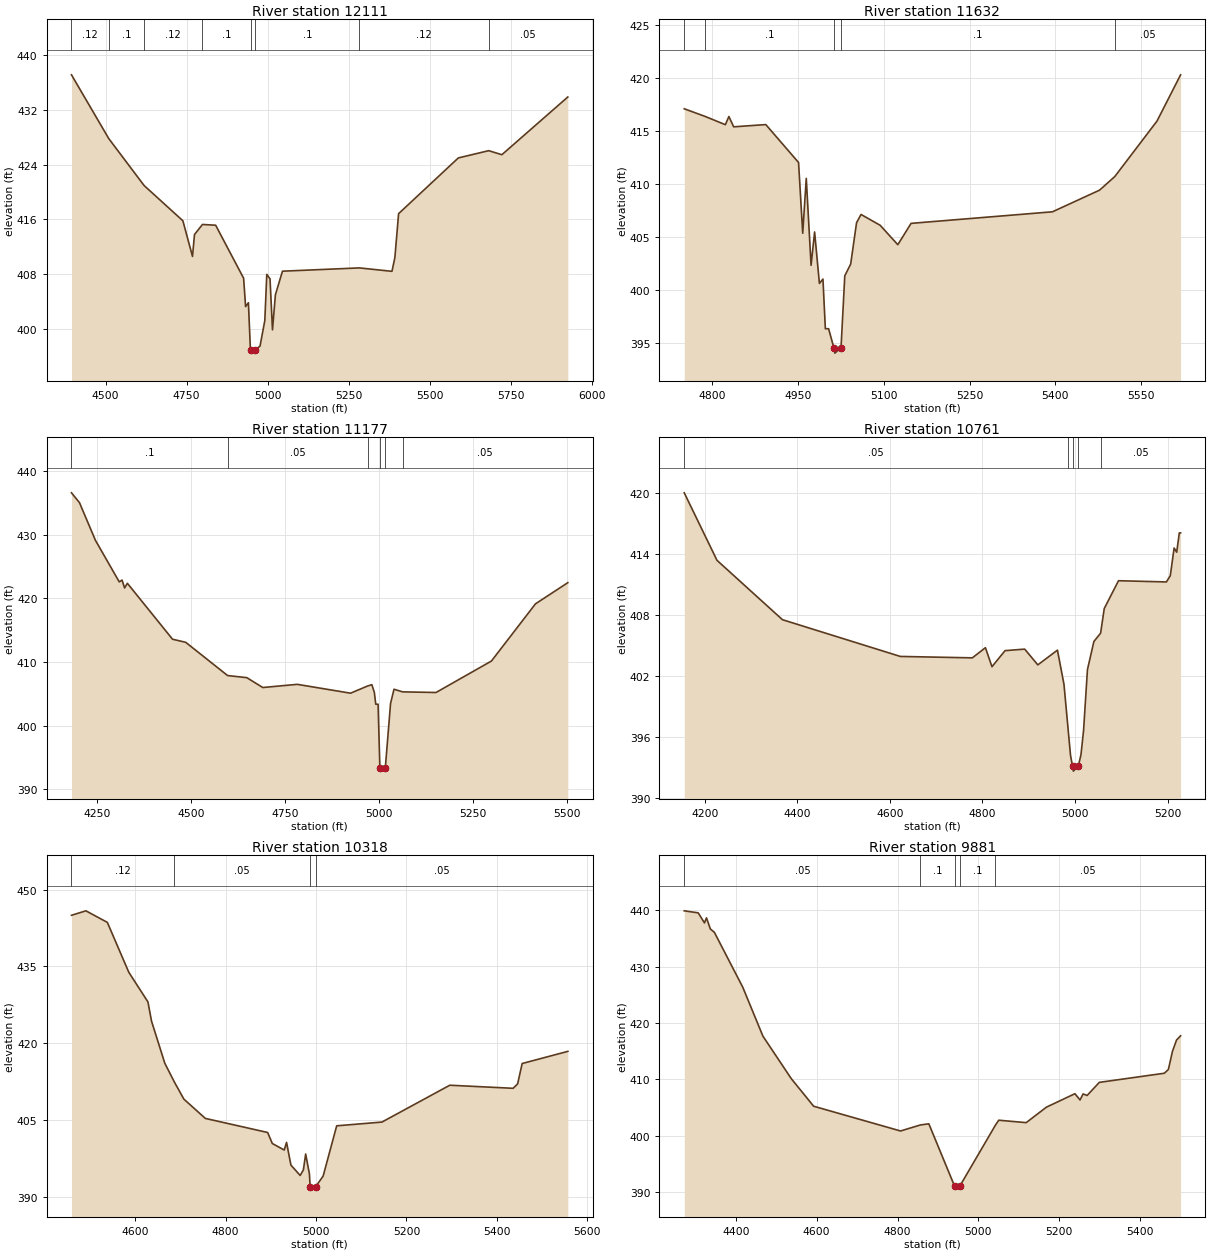
Type RM Length L Ch R = 1,12111,479,479,479
BEGIN DESCRIPTION:
Second Caney Creek 15.0
END DESCRIPTION:
XS GIS Cut Line= 3
      2790475.98      6783811.03      2790126.00      6784311.00
      2789926.01      6785210.95
#Sta/Elev= 30
  4394.7  437.12  4509.9  427.79  4618.8  420.94  4738.6  415.78  4768.3  410.57
  4774.4  413.77  4799.1  415.24  4839.8  415.13  4926.1  407.38  4932.2  403.23
  4940.9  403.80  4947.0  396.98  4949.5  396.93  4951.2  396.43  4961.9  396.93
  4976.7  397.45  4991.5  401.19  4997.6  407.94  5007.6  407.29  5015.2  399.84
  5024.2  404.96  5046.0  408.41  5283.5  408.89  5384.0  408.39  5393.0  410.39
  5404.5  416.82  5588.9  424.97  5682.7  426.03  5723.3  425.44  5926.9  433.88
#Mann=8,-1,0
  4394.7    0.12       0  4509.9     0.1       0  4618.8    0.12       0
  4799.1     0.1       0  4949.5    0.07       0  4961.9     0.1       0
  5283.5    0.12       0  5682.7    0.05       0
Bank Sta=4949.5,4961.9
Exp/Cntr=0.3,0.1

Type RM Length L Ch R = 1,11632,455,455,455
BEGIN DESCRIPTION:
Second Caney Creek 14.0
END DESCRIPTION:
XS GIS Cut Line= 3
      2789976.00      6783861.00      2789826.00      6784061.00
      2789675.99      6784661.03
#Sta/Elev= 30
  4750.6  417.08  4787.1  416.36  4822.5  415.58  4828.7  416.35  4837.1  415.38
  4893.3  415.59  4950.6  412.02  4957.9  405.35  4964.1  410.52  4972.5  402.33
  4978.7  405.47  4987.1  400.62  4993.3  401.03  4997.5  396.35  5003.2  396.35
  5012.4  394.55  5014.1  394.05  5024.9  394.55  5031.5  401.34  5041.8  402.44
  5052.1  406.34  5059.9  407.12  5093.4  406.10  5124.3  404.27  5147.5  406.28
  5394.9  407.37  5477.3  409.41  5503.9  410.69  5577.8  415.92  5619.1  420.28
#Mann=5,-1,0
  4750.6    0.05       0  4787.1     0.1       0  5012.4    0.07       0
  5024.9     0.1       0  5503.9    0.05       0
Bank Sta=5012.4,5024.9
Exp/Cntr=0.3,0.1

Type RM Length L Ch R = 1,11177,416,416,416
BEGIN DESCRIPTION:
Second Caney Creek 13.0
END DESCRIPTION:
XS GIS Cut Line= 3
      2790025.99      6783561.01      2789426.00      6784111.00
      2789190.42      6784561.27
#Sta/Elev= 30
  4181.2  436.56  4202.5  435.02  4245.0  429.10  4308.5  422.57  4315.9  422.86
  4322.7  421.62  4330.1  422.35  4450.3  413.57  4485.5  413.08  4597.1  407.86
  4648.3  407.53  4690.8  405.98  4782.7  406.48  4924.5  405.09  4970.0  406.22
  4981.3  406.43  4988.0  405.20  4991.7  403.36  4997.9  403.36  5002.7  393.35
  5004.5  392.85  5015.2  393.35  5017.7  393.74  5031.1  403.47  5040.3  405.71
  5063.3  405.30  5152.2  405.20  5299.8  410.14  5417.1  419.12  5503.3  422.45
#Mann=6,-1,0
  4181.2     0.1       0  4597.1    0.05       0  4970.0    0.12       0
  5002.7    0.07       0  5015.2    0.12       0  5063.3    0.05       0
Bank Sta=5002.7,5015.2
Exp/Cntr=0.3,0.1

Type RM Length L Ch R = 1,10761,443,443,443
BEGIN DESCRIPTION:
Second Caney Creek 12.0
END DESCRIPTION:
XS GIS Cut Line= 3
      2789725.99      6783311.01      2789126.00      6783911.00
      2789026.01      6784110.98
#Sta/Elev= 30
  4155.9  420.05  4226.6  413.40  4368.0  407.55  4622.6  403.93  4778.1  403.79
  4806.4  404.79  4820.6  402.92  4848.8  404.50  4891.3  404.65  4919.6  403.10
  4962.0  404.55  4976.1  401.18  4983.9  397.32  4990.3  394.16  4994.6  393.13
  4996.4  392.63  5007.1  393.13  5012.8  394.25  5018.4  396.63  5026.8  402.63
  5040.7  405.40  5055.2  406.22  5063.1  408.65  5093.9  411.39  5197.3  411.27
  5205.7  411.88  5214.0  414.61  5219.6  414.20  5225.2  416.10  5228.0  416.10
#Mann=5,-1,0
  4155.9    0.05       0  4983.9    0.12       0  4994.6    0.07       0
  5007.1    0.12       0  5055.2    0.05       0
Bank Sta=4994.6,5007.1
Exp/Cntr=0.3,0.1

Type RM Length L Ch R = 1,10318,437,437,437
BEGIN DESCRIPTION:
Second Caney Creek 11.0
END DESCRIPTION:
XS GIS Cut Line= 3
      2789049.19      6783138.71      2788926.00      6783661.00
      2788911.43      6784221.99
#Sta/Elev= 30
  4459.1  444.98  4491.0  445.85  4538.4  443.60  4585.9  433.87  4628.2  428.10
  4636.1  424.37  4665.4  416.17  4686.7  412.48  4707.7  409.15  4755.2  405.39
  4893.0  402.65  4903.3  400.50  4929.7  399.23  4934.8  400.72  4944.4  396.31
  4964.9  394.27  4972.0  395.36  4977.1  398.45  4985.4  394.55  4986.9  392.11
  4988.7  391.61  4999.4  392.11  5015.7  394.15  5045.7  403.95  5145.8  404.68
  5295.8  411.86  5435.9  411.26  5445.9  412.13  5455.9  416.09  5556.9  418.46
#Mann=4,-1,0
  4459.1    0.12       0  4686.7    0.05       0  4986.9    0.04       0
  4999.4    0.05       0
Bank Sta=4986.9,4999.4
Exp/Cntr=0.3,0.1

Type RM Length L Ch R = 1,9881,442,442,442
BEGIN DESCRIPTION:
Second Caney Creek 10.0
END DESCRIPTION:
XS GIS Cut Line= 3
      2788602.87      6783036.50      2788576.00      6783761.00
      2788526.00      6784261.01
#Sta/Elev= 30
  4272.5  439.88  4307.0  439.52  4322.5  437.74  4327.5  438.63  4337.0  436.67
  4347.0  436.07  4417.1  426.35  4467.1  417.65  4537.2  410.12  4592.5  405.23
  4807.4  400.84  4856.6  401.91  4877.4  402.11  4941.2  391.03  4943.0  390.53
  4953.7  391.03  5042.2  401.89  5050.3  402.75  5118.1  402.32  5168.3  405.07
  5238.7  407.45  5251.3  406.34  5258.8  407.41  5268.8  407.14  5299.0  409.46
  5459.8  411.08  5469.8  411.75  5479.9  414.96  5489.9  416.96  5500.0  417.72
#Mann=5,-1,0
  4272.5    0.05       0  4856.6     0.1       0  4941.2    0.07       0
  4953.7     0.1       0  5042.2    0.05       0
Bank Sta=4941.2,4953.7
Exp/Cntr=0.3,0.1

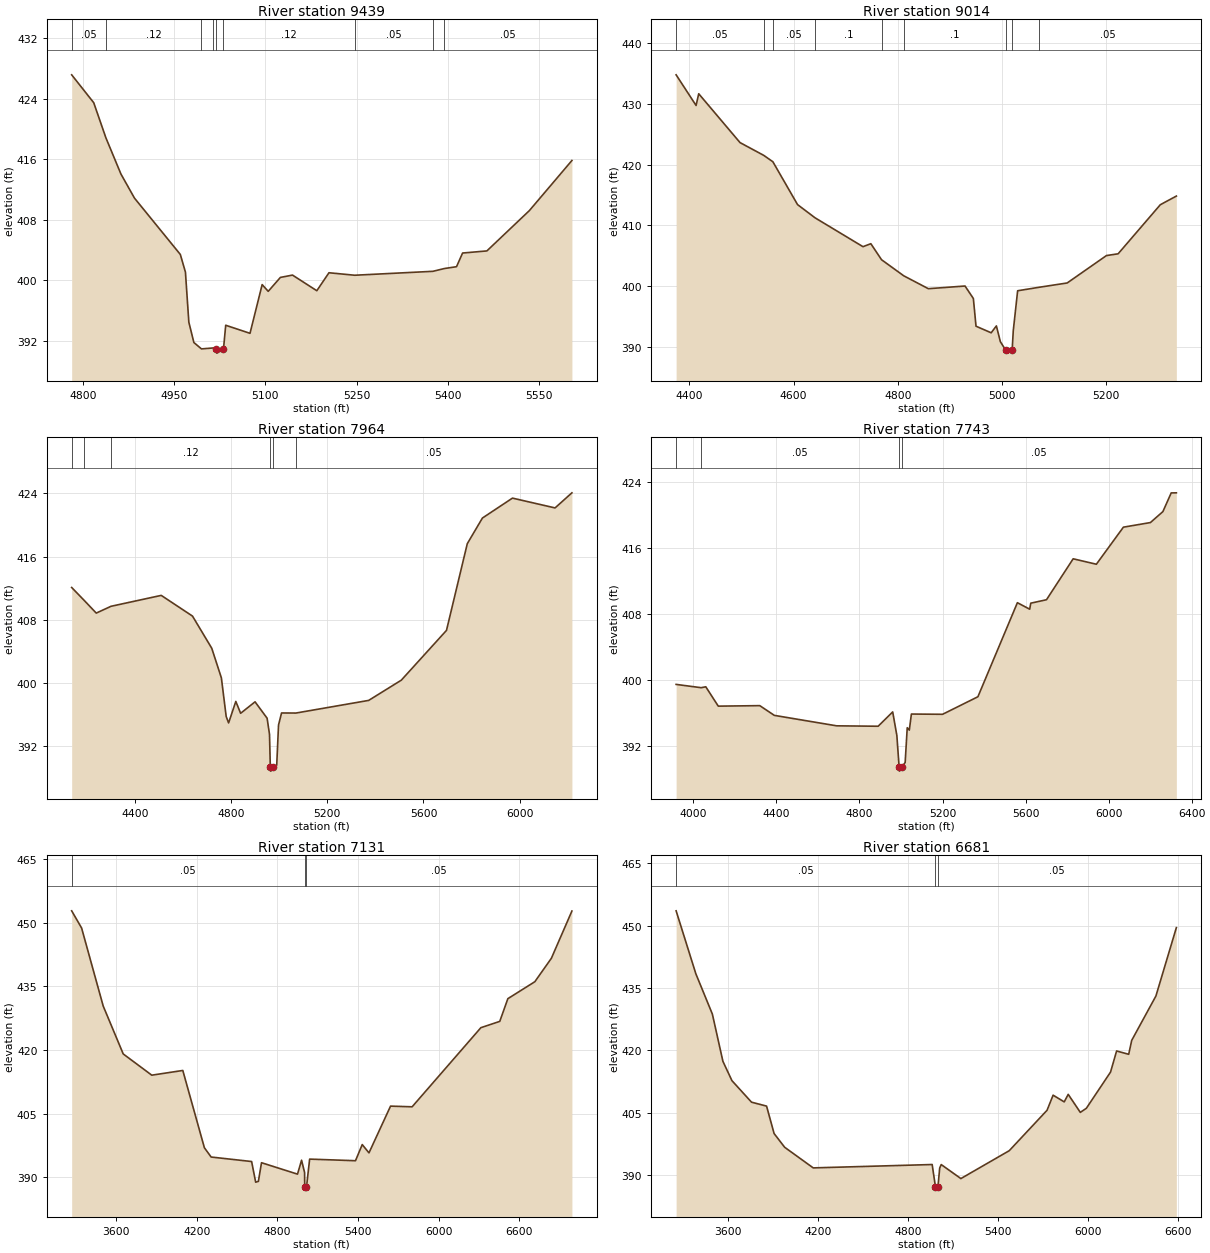
Type RM Length L Ch R = 1,9439,425,425,425
BEGIN DESCRIPTION:
Second Caney Creek 9.0
END DESCRIPTION:
XS GIS Cut Line= 3
      2788176.00      6783411.00      2788276.00      6783611.00
      2788276.00      6784211.00
#Sta/Elev= 30
  4781.0  427.19  4817.3  423.50  4837.4  418.84  4862.1  414.06  4884.4  410.87
  4959.9  403.41  4968.3  401.07  4973.9  394.45  4982.2  391.75  4994.7  390.91
  5013.4  391.03  5018.4  390.85  5020.1  390.35  5030.9  390.85  5034.6  394.04
  5074.6  392.97  5094.6  399.42  5104.6  398.53  5124.6  400.37  5144.6  400.68
  5184.6  398.61  5204.6  400.99  5246.9  400.66  5375.8  401.18  5394.7  401.55
  5414.6  401.79  5424.6  403.60  5464.6  403.88  5534.6  409.22  5604.6  415.85
#Mann=9,-1,0
  4781.0    0.05       0  4837.4    0.12       0  4994.7     0.1       0
  5013.4    0.12       0  5018.4    0.07       0  5030.9    0.12       0
  5246.9    0.05       0  5375.8     0.1       0  5394.7    0.05       0
Bank Sta=5018.4,5030.9
Exp/Cntr=0.3,0.1

Type RM Length L Ch R = 1,9014,1050,1050,1050
BEGIN DESCRIPTION:
Second Caney Creek 8.0
END DESCRIPTION:
XS GIS Cut Line= 3
      2787967.30      6783288.89      2788026.00      6783911.00
      2788176.01      6784211.02
#Sta/Elev= 30
  4374.6  434.73  4412.9  429.70  4418.0  431.62  4497.3  423.60  4542.7  421.51
  4560.3  420.46  4607.7  413.42  4641.3  411.25  4733.3  406.51  4748.4  407.00
  4768.9  404.37  4811.5  401.73  4858.8  399.61  4929.2  400.05  4945.2  398.00
  4950.3  393.45  4979.4  392.37  4989.4  393.50  4997.0  390.92  5007.1  389.53
  5008.9  389.03  5019.7  389.53  5021.8  392.70  5030.2  399.27  5071.2  399.84
  5125.3  400.55  5200.7  405.05  5223.1  405.34  5304.1  413.40  5334.9  414.82
#Mann=9,-1,0
  4374.6    0.05       0  4542.7     0.1       0  4560.3    0.05       0
  4641.3     0.1       0  4768.9    0.05       0  4811.5     0.1       0
  5007.1    0.07       0  5019.7     0.1       0  5071.2    0.05       0
Bank Sta=5007.1,5019.7
Exp/Cntr=0.3,0.1

Type RM Length L Ch R = 1,7964,221,221,221
BEGIN DESCRIPTION:
Second Caney Creek 7.0
END DESCRIPTION:
XS GIS Cut Line= 3
      2787236.16      6782898.86      2787226.00      6783761.00
      2787357.87      6784970.73
#Sta/Elev= 30
  4137.8  412.08  4187.8  410.51  4239.9  408.84  4301.4  409.70  4510.0  411.08
  4640.0  408.46  4720.0  404.39  4760.0  400.64  4780.0  395.75  4790.0  394.94
  4820.0  397.66  4840.0  396.16  4900.0  397.61  4950.0  395.54  4960.0  393.51
  4963.4  389.34  4965.3  388.84  4976.5  389.34  4990.0  389.58  4997.5  394.67
  5010.1  396.20  5069.7  396.19  5372.2  397.79  5507.8  400.35  5695.6  406.65
  5782.0  417.62  5845.0  420.87  5969.8  423.39  6146.8  422.15  6216.9  424.06
#Mann=6,-1,0
  4137.8    0.05       0  4187.8     0.1       0  4301.4    0.12       0
  4963.4    0.07       0  4976.5    0.12       0  5069.7    0.05       0
Bank Sta=4963.4,4976.5
Exp/Cntr=0.3,0.1

Type RM Length L Ch R = 1,7743,612,612,612
BEGIN DESCRIPTION:
Second Caney Creek 6.0
END DESCRIPTION:
XS GIS Cut Line= 3
      2787044.54      6782628.09      2787021.03      6783710.94
      2787084.71      6785035.81
#Sta/Elev= 30
  3916.9  399.45  4037.2  399.05  4059.8  399.16  4119.9  396.81  4319.9  396.87
  4389.9  395.69  4690.0  394.42  4890.0  394.37  4960.1  396.11  4980.1  393.25
  4991.0  389.42  4992.8  388.92  5004.1  389.42  5020.1  389.97  5030.1  394.19
  5040.1  393.90  5050.1  395.85  5200.3  395.82  5370.5  397.95  5560.7  409.37
  5620.0  408.58  5625.0  409.31  5700.9  409.73  5829.3  414.70  5941.1  414.04
  6071.3  418.54  6201.4  419.10  6261.5  420.43  6301.6  422.70  6326.4  422.71
#Mann=4,-1,0
  3916.9     0.1       0  4037.2    0.05       0  4991.0    0.05       0
  5004.1    0.05       0
Bank Sta=4991,5004.1
Exp/Cntr=0.3,0.1

Type RM Length L Ch R = 1,7131,450,450,450
BEGIN DESCRIPTION:
Second Caney Creek 5.0
END DESCRIPTION:
XS GIS Cut Line= 3
      2786290.75      6781937.38      2786426.00      6783661.00
      2786561.59      6785646.06
#Sta/Elev= 30
  3271.1  452.79  3344.9  448.74  3505.4  430.37  3654.3  419.08  3866.5  414.08
  4097.2  415.19  4257.7  396.98  4307.9  394.80  4608.8  393.74  4638.9  388.87
  4659.0  389.07  4682.2  393.46  4949.9  390.77  4980.0  394.05  5002.5  391.15
  5003.5  387.74  5005.3  387.24  5016.6  387.74  5040.1  394.31  5380.9  393.93
  5431.0  397.73  5481.1  395.78  5641.5  406.79  5801.9  406.63  6313.1  425.27
  6453.4  426.75  6513.5  432.10  6714.0  436.09  6836.8  441.60  6989.7  452.74
#Mann=3,-1,0
  3271.1    0.05       0  5003.5    0.04       0  5016.6    0.05       0
Bank Sta=5003.5,5016.6
Exp/Cntr=0.3,0.1

Type RM Length L Ch R = 1,6681,450,450,450
BEGIN DESCRIPTION:
Second Caney Creek 4.0
END DESCRIPTION:
XS GIS Cut Line= 3
      2786125.60      6781920.22      2785976.00      6783661.00
      2785777.23      6785236.31
#Sta/Elev= 30
  3252.8  453.59  3384.1  438.46  3494.5  428.73  3564.7  417.37  3624.9  412.72
  3755.4  407.54  3855.8  406.59  3906.0  399.99  3976.2  396.69  4166.9  391.72
  4959.8  392.53  4981.9  387.11  4983.9  386.61  4998.1  387.11  5010.1  391.69
  5020.2  392.52  5151.2  389.15  5473.7  395.86  5725.7  405.59  5766.0  409.22
  5840.2  407.61  5866.8  409.42  5947.4  405.08  5987.8  406.07  6149.0  414.78
  6189.4  419.86  6270.0  419.06  6290.1  422.41  6451.4  433.08  6587.8  449.54
#Mann=3,-1,0
  3252.8    0.05       0  4981.9    0.04       0  4998.1    0.05       0
Bank Sta=4981.9,4998.1
Exp/Cntr=0.3,0.1

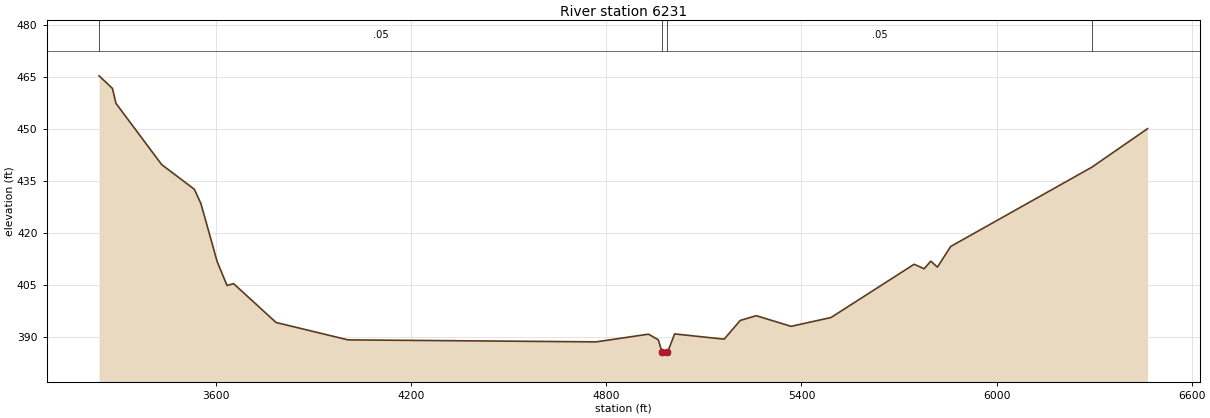
Type RM Length L Ch R = 1,6231,466,466,466
BEGIN DESCRIPTION:
Second Caney Creek 3.0
END DESCRIPTION:
XS GIS Cut Line= 3
      2785695.36      6781909.36      2785526.00      6783661.00
      2785217.89      6785092.62
#Sta/Elev= 30
  3240.1  465.37  3281.2  461.74  3292.0  457.44  3432.6  439.80  3533.1  432.69
  3553.2  428.59  3603.4  411.81  3633.6  404.96  3653.7  405.51  3784.3  394.32
  4005.3  389.31  4768.8  388.73  4929.6  390.95  4959.7  389.34  4971.6  385.70
  4973.6  385.20  4988.0  385.70  5010.1  391.02  5162.4  389.51  5211.7  394.90
  5261.0  396.27  5368.1  393.21  5490.9  395.74  5746.6  411.09  5777.3  409.79
  5797.8  411.98  5818.2  410.27  5859.1  416.22  6292.9  439.04  6464.3  450.14
#Mann=4,-1,0
  3240.1    0.05       0  4971.6    0.04       0  4988.0    0.05       0
  6292.9    0.12       0
Bank Sta=4971.6,4988
Exp/Cntr=0.3,0.1