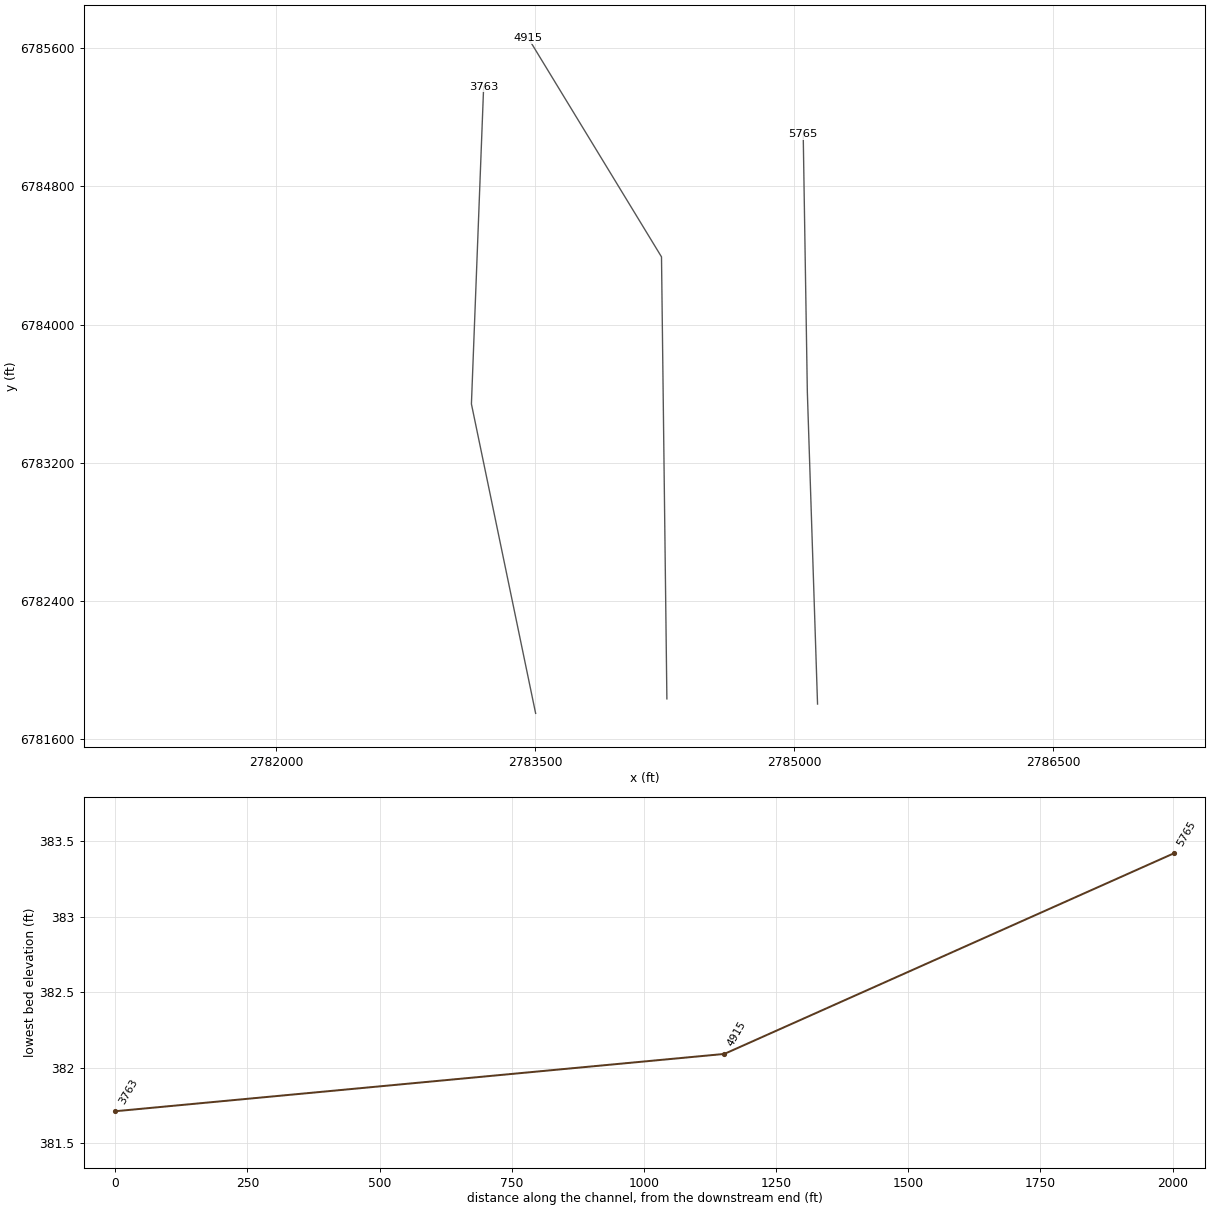
HEC-RAS study Second Caney Creek.prj: Second Caney Creek Base Level Engineering

--- Second Caney Creek.g01 (geometry) --- (continued)

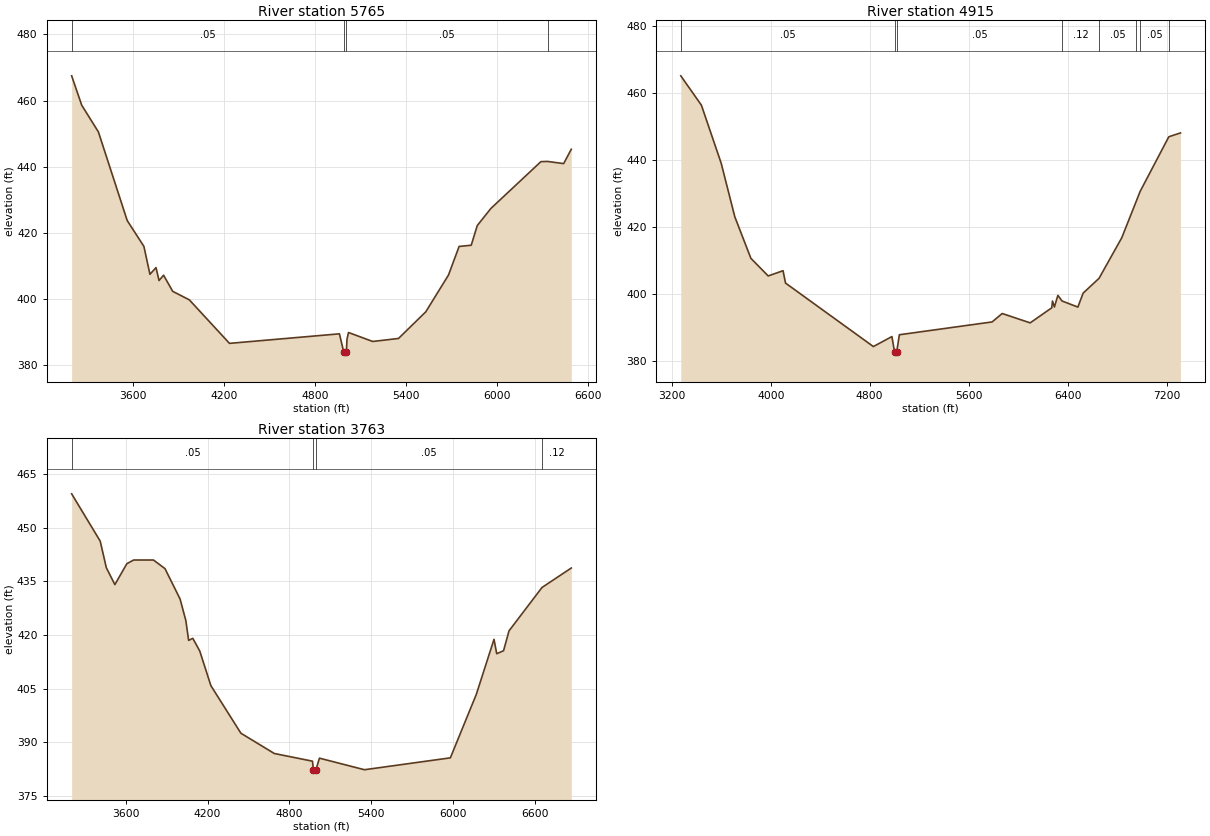
Type RM Length L Ch R = 1,5765,850,850,850
BEGIN DESCRIPTION:
Second Caney Creek 2.0
END DESCRIPTION:
XS GIS Cut Line= 3
      2785135.02      6781804.38      2785076.00      6783611.00
      2785052.09      6785101.53
#Sta/Elev= 30
  3192.4  467.48  3259.1  458.59  3369.1  450.53  3559.2  423.77  3669.3  415.97
  3709.3  407.53  3749.3  409.55  3769.3  405.65  3799.3  407.26  3859.4  402.39
  3969.4  399.81  4234.4  386.67  4960.0  389.55  4989.3  383.92  4991.3  383.42
  5005.7  383.92  5010.0  387.88  5020.0  389.95  5180.0  387.24  5350.0  388.15
  5530.0  396.19  5680.1  407.31  5750.1  415.94  5830.1  416.31  5870.1  422.26
  5960.1  427.43  6290.1  441.56  6334.1  441.62  6440.2  440.97  6490.7  445.30
#Mann=4,-1,0
  3192.4    0.05       0  4989.3    0.04       0  5005.7    0.05       0
  6334.1    0.12       0
Bank Sta=4989.3,5005.7
Exp/Cntr=0.3,0.1

Type RM Length L Ch R = 1,4915,1152,1152,1152
BEGIN DESCRIPTION:
Mapping XS 98cb2abe
END DESCRIPTION:
XS GIS Cut Line= 3
      2784263.10      6781834.33      2784231.95      6784392.37
      2783461.68      6785657.15
#Sta/Elev= 30
  3273.2  465.15  3439.9  456.39  3599.9  439.06  3709.9  423.08  3839.9  410.68
  3979.9  405.42  4099.9  406.99  4119.9  403.30  4830.0  384.35  4980.0  387.33
  5001.8  382.59  5003.8  382.09  5018.2  382.59  5040.0  387.87  5790.1  391.70
  5871.3  394.21  6097.8  391.42  6272.2  395.92  6278.0  397.94  6293.5  396.15
  6321.6  399.62  6355.4  397.95  6483.3  396.13  6525.9  400.30  6654.0  404.70
  6837.8  416.80  6953.1  427.52  6986.2  430.63  7218.3  446.96  7312.3  448.11
#Mann=8,-1,0
  3273.2    0.05       0  5001.8    0.04       0  5018.2    0.05       0
  6355.4    0.12       0  6654.0    0.05       0  6953.1    0.12       0
  6986.2    0.05       0  7218.3    0.12       0
Bank Sta=5001.8,5018.2
Exp/Cntr=0.3,0.1

Type RM Length L Ch R = 1,3763,0,0,0
BEGIN DESCRIPTION:
Second Caney Creek 1.0
END DESCRIPTION:
XS GIS Cut Line= 3
      2783503.52      6781750.34      2783131.84      6783541.00
      2783202.65      6785377.81
#Sta/Elev= 30
  3202.9  459.45  3412.5  446.24  3457.6  438.80  3520.2  434.09  3608.0  439.93
  3658.1  440.96  3803.4  440.96  3887.9  438.56  3998.8  430.06  4041.1  424.03
  4061.5  418.51  4092.1  419.09  4143.2  415.53  4224.9  405.86  4445.0  392.58
  4690.5  386.91  4970.4  384.77  4977.8  382.21  4979.8  381.71  4994.7  382.21
  5021.5  385.61  5352.0  382.38  5982.4  385.70  6172.6  403.41  6302.7  418.81
  6322.7  414.79  6372.7  415.62  6412.8  421.17  6654.7  433.28  6869.9  438.73
#Mann=4,-1,0
  3202.9    0.05       0  4977.8    0.04       0  4994.7    0.05       0
  6654.7    0.12       0
Bank Sta=4977.8,4994.7
Exp/Cntr=0.3,0.1

Chan Stop Cuts=-1