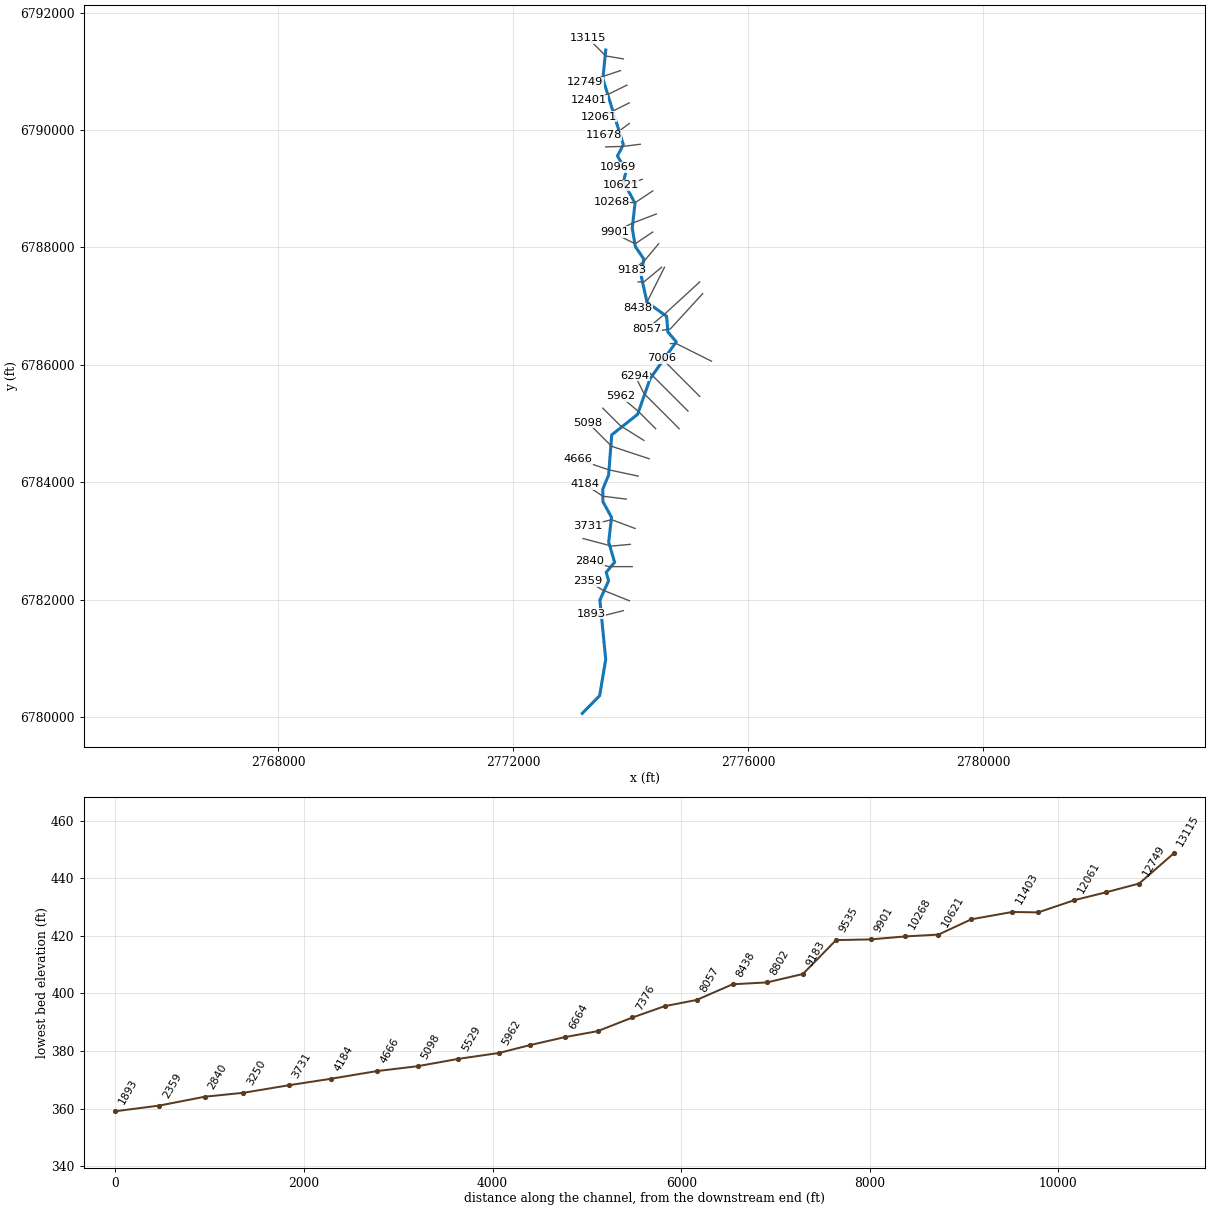
--- Shoat Branch.prj (project) ---

Proj Title=Shoat Branch Base Level Engineering
Current Plan=p01
Default Exp/Contr=0.3,0.1
English Units
Geom File=g01
Flow File=f01
Plan File=p01
BEGIN DESCRIPTION:
Shoat Branch
END DESCRIPTION:

--- Shoat Branch.p01 (plan) ---

Plan Title=Multiple Run
Short Identifier=Multiple
Geom File=g01
Flow File=f01
Subcritical Flow
K Sum by GR= 0
Std Step Tol= 0.01
Critical Tol= 0.01
Num of Std Step Trials= 20
Max Error Tol= 0.3
Flow Tol Ratio= 0.001
Split Flow NTrial= 30
Split Flow Tol= 0.02
Split Flow Ratio= 0.02
Log Output Level= 0
Friction Slope Method= 1
Unsteady Friction Slope Method= 2
Unsteady Bridges Friction Slope Method= 1
Parabolic Critical Depth
Global Vel Dist=  1 , 1 , 1
Global Log Level= 0
CheckData=True
Encroach Param= -1, 0, 0, 0
BEGIN DESCRIPTION:
Multiple Run
END DESCRIPTION:

--- Shoat Branch.f01 (steady flow) ---

Flow Title=Multiple
Number of Profiles=7
Profile Names=10-year,25-year,50-year,1pct_min,100-year,1pct_plu,500-year
River Rch & RM= Shoat Branch,Reach-1,13115
     694     959    1181     724    1444    2881    2164
River Rch & RM= Shoat Branch,Reach-1,5529
    1052    1472    1828    1127    2249    4487    3412
Boundary for River Rch & Prof#=Shoat Branch,Reach-1,1
Up Type=0
Dn Type=3
Dn Slope=0.005
Boundary for River Rch & Prof#=Shoat Branch,Reach-1,2
Up Type=0
Dn Type=3
Dn Slope=0.005
Boundary for River Rch & Prof#=Shoat Branch,Reach-1,3
Up Type=0
Dn Type=3
Dn Slope=0.005
Boundary for River Rch & Prof#=Shoat Branch,Reach-1,4
Up Type=0
Dn Type=3
Dn Slope=0.005
Boundary for River Rch & Prof#=Shoat Branch,Reach-1,5
Up Type=0
Dn Type=3
Dn Slope=0.005
Boundary for River Rch & Prof#=Shoat Branch,Reach-1,6
Up Type=0
Dn Type=3
Dn Slope=0.005
Boundary for River Rch & Prof#=Shoat Branch,Reach-1,7
Up Type=0
Dn Type=3
Dn Slope=0.005

--- Shoat Branch.g01 (geometry) ---

Geom Title=Existing Conditions

River Reach=Shoat Branch,Reach-1
Reach XY= 30
      2773576.00      6791361.00      2773527.10      6790871.55
      2773875.12      6789751.13      2773775.13      6789555.96
      2773923.86      6789305.03      2773877.92      6789116.70
      2774074.62      6788751.34      2774026.67      6788324.93
      2774079.75      6788012.55      2774224.79      6787801.41
      2774175.81      6787529.43      2774278.17      6787066.44
      2774612.47      6786824.41      2774633.83      6786557.60
      2774776.71      6786391.17      2774331.70      6785763.38
      2774117.94      6785154.67      2773678.09      6784805.74
      2773624.62      6784120.66      2773525.64      6783881.15
      2773528.26      6783666.94      2773674.94      6783400.56
      2773625.72      6782981.18      2773726.52      6782635.88
      2773584.03      6782464.35      2773624.90      6782320.64
      2773476.07      6781990.97      2773575.79      6780979.27
      2773472.46      6780362.46      2773176.00      6780061.00

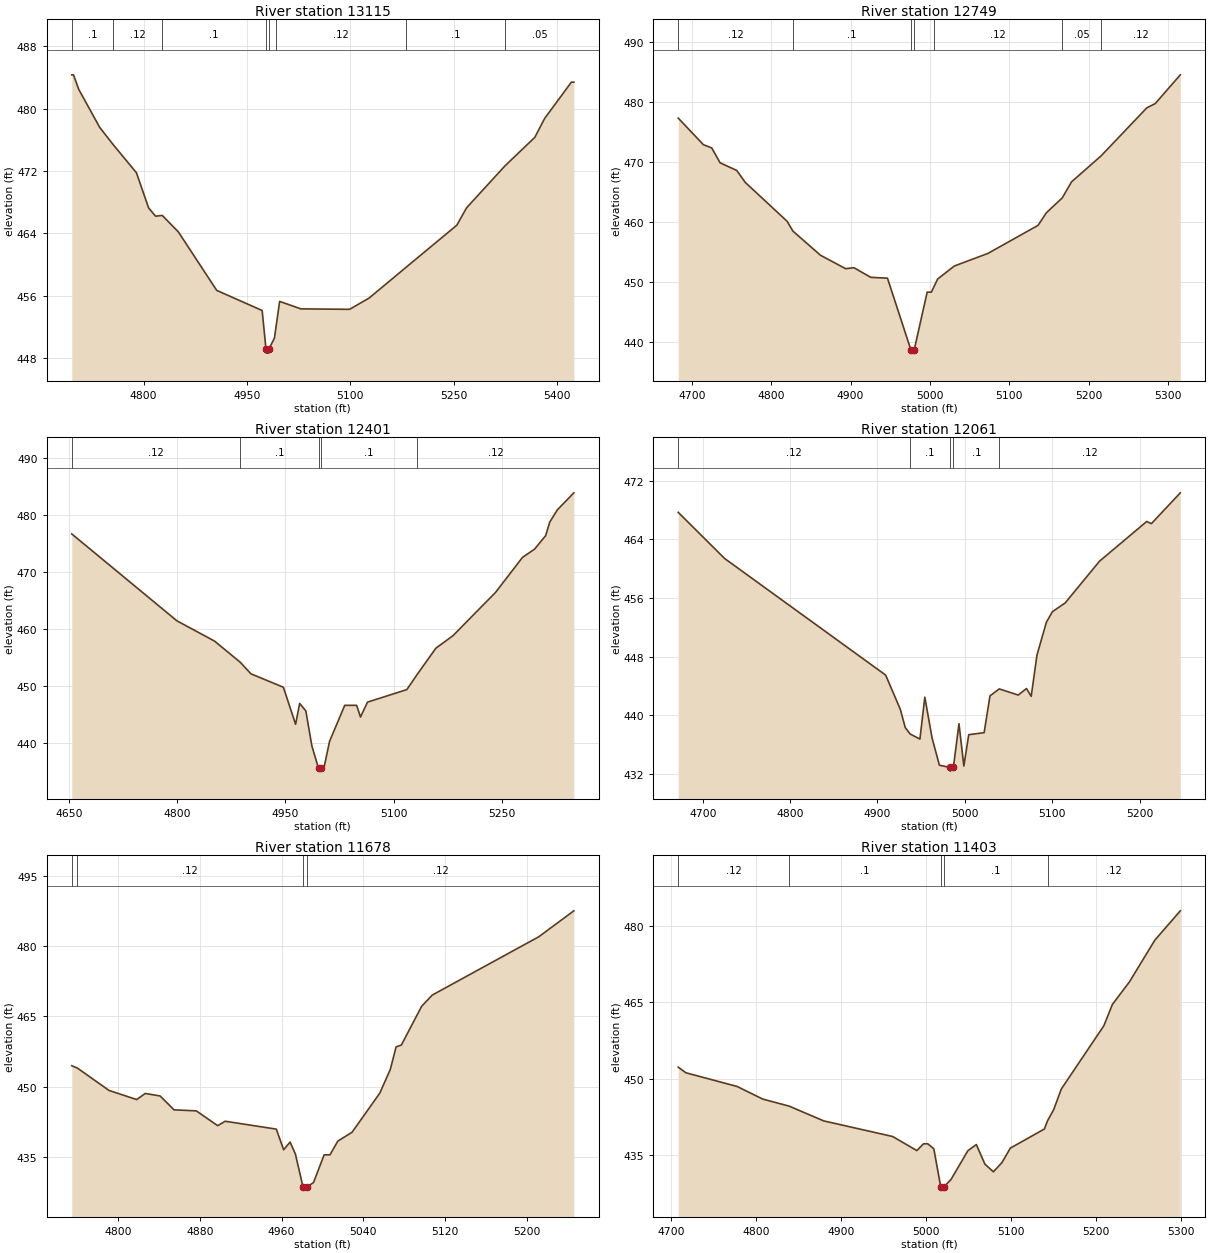
Type RM Length L Ch R = 1,13115,366,366,366
BEGIN DESCRIPTION:
Shoat Branch 32.0
END DESCRIPTION:
XS GIS Cut Line= 3
      2773875.98      6791211.00      2773576.00      6791261.00
      2773275.98      6791561.02
#Sta/Elev= 30
  4695.9  484.35  4698.4  484.35  4706.0  482.49  4736.4  477.61  4756.2  475.37
  4789.7  471.79  4807.4  467.27  4817.5  466.21  4827.2  466.31  4850.5  464.20
  4906.2  456.69  4972.1  454.11  4977.7  449.14  4978.0  448.64  4981.5  448.64
  4981.7  449.14  4989.9  450.56  4992.9  452.42  4997.5  455.28  5028.3  454.32
  5099.0  454.26  5127.3  455.71  5181.0  459.66  5254.6  465.06  5268.7  467.29
  5324.3  472.66  5367.7  476.33  5381.9  478.75  5420.7  483.41  5424.3  483.41
#Mann=8,-1,0
  4695.9     0.1       0  4756.2    0.12       0  4827.2     0.1       0
  4977.7    0.07       0  4981.7     0.1       0  4992.9    0.12       0
  5181.0     0.1       0  5324.3    0.05       0
Bank Sta=4977.7,4981.7
Exp/Cntr=0.3,0.1

Type RM Length L Ch R = 1,12749,348,348,348
BEGIN DESCRIPTION:
Shoat Branch 31.0
END DESCRIPTION:
XS GIS Cut Line= 3
      2773826.04      6791011.01      2773526.00      6790911.00
      2773226.00      6790811.00
#Sta/Elev= 30
  4682.9  477.34  4714.6  472.91  4725.1  472.37  4735.6  469.90  4756.7  468.61
  4767.3  466.63  4820.0  460.16  4827.4  458.51  4862.1  454.49  4893.8  452.25
  4904.3  452.41  4925.4  450.81  4946.5  450.67  4976.1  438.68  4976.3  438.18
  4980.1  438.68  4996.5  448.34  5001.8  448.34  5004.9  449.20  5009.7  450.53
  5030.8  452.70  5073.0  454.79  5136.2  459.47  5146.7  461.57  5166.7  464.05
  5178.4  466.72  5215.7  471.06  5273.2  479.05  5283.8  479.76  5315.4  484.55
#Mann=7,-1,0
  4682.9    0.12       0  4827.4     0.1       0  4976.1    0.07       0
  4980.1     0.1       0  5004.9    0.12       0  5166.7    0.05       0
  5215.7    0.12       0
Bank Sta=4976.1,4980.1
Exp/Cntr=0.3,0.1

Type RM Length L Ch R = 1,12401,340,340,340
BEGIN DESCRIPTION:
Shoat Branch 30.0
END DESCRIPTION:
XS GIS Cut Line= 3
      2773936.65      6790763.99      2773626.00      6790611.00
      2773294.24      6790503.88
#Sta/Elev= 30
  4654.2  476.76  4799.8  461.51  4851.7  457.97  4887.4  454.25  4902.2  452.22
  4947.1  449.86  4964.0  443.36  4969.6  447.03  4978.2  445.70  4986.5  439.58
  4995.7  435.65  4995.9  435.15  4999.7  435.65  5003.1  435.65  5011.0  440.37
  5032.0  446.69  5048.5  446.69  5053.8  444.64  5063.5  447.25  5117.9  449.45
  5132.1  452.08  5158.1  456.71  5181.9  458.92  5240.7  466.50  5278.0  472.64
  5294.7  474.09  5310.1  476.46  5315.7  478.82  5326.2  480.97  5349.1  483.97
#Mann=5,-1,0
  4654.2    0.12       0  4887.4     0.1       0  4995.7    0.07       0
  4999.7     0.1       0  5132.1    0.12       0
Bank Sta=4995.7,4999.7
Exp/Cntr=0.3,0.1

Type RM Length L Ch R = 1,12061,383,383,383
BEGIN DESCRIPTION:
Shoat Branch 29.0
END DESCRIPTION:
XS GIS Cut Line= 3
      2773975.96      6790460.98      2773676.00      6790311.00
      2773453.56      6790222.40
#Sta/Elev= 30
  4671.9  467.67  4725.0  461.38  4909.4  445.48  4926.2  440.80  4931.8  438.33
  4937.4  437.45  4948.6  436.76  4954.2  442.47  4962.5  436.91  4970.9  433.20
  4982.9  432.89  4983.2  432.39  4986.9  432.89  4993.3  438.85  4998.9  433.08
  5004.5  437.36  5022.1  437.63  5028.8  442.65  5039.4  443.60  5061.1  442.76
  5070.6  443.65  5076.0  442.59  5082.6  448.21  5093.4  452.69  5100.3  454.13
  5114.9  455.32  5154.2  461.01  5208.2  466.42  5213.6  466.13  5246.7  470.33
#Mann=5,-1,0
  4671.9    0.12       0  4937.4     0.1       0  4982.9    0.07       0
  4986.9     0.1       0  5039.4    0.12       0
Bank Sta=4982.9,4986.9
Exp/Cntr=0.3,0.1

Type RM Length L Ch R = 1,11678,275,275,275
BEGIN DESCRIPTION:
Shoat Branch 28.0
END DESCRIPTION:
XS GIS Cut Line= 3
      2773975.96      6790110.97      2773776.00      6789961.00
      2773540.93      6789907.66
#Sta/Elev= 30
  4754.8  454.45  4760.4  453.94  4791.2  449.19  4818.3  447.24  4826.6  448.54
  4841.2  448.01  4854.8  445.05  4876.6  444.83  4897.5  441.68  4904.8  442.62
  4954.8  440.94  4962.0  436.55  4968.3  438.18  4973.5  435.64  4980.9  428.65
  4981.1  428.15  4984.9  428.65  4991.2  429.55  5001.6  435.46  5007.3  435.46
  5015.0  438.39  5028.9  440.27  5056.0  448.60  5066.3  453.66  5072.0  458.48
  5077.1  458.86  5097.0  467.13  5107.3  469.51  5211.5  481.94  5245.8  487.47
#Mann=4,-1,0
  4754.8     0.1       0  4760.4    0.12       0  4980.9    0.07       0
  4984.9    0.12       0
Bank Sta=4980.9,4984.9
Exp/Cntr=0.3,0.1

Type RM Length L Ch R = 1,11403,434,434,434
BEGIN DESCRIPTION:
Shoat Branch 27.0
END DESCRIPTION:
XS GIS Cut Line= 3
      2774164.74      6789756.53      2773875.24      6789720.78
      2773576.00      6789711.00
#Sta/Elev= 30
  4708.3  452.23  4717.4  451.12  4777.6  448.44  4807.8  445.96  4838.7  444.59
  4879.6  441.68  4960.7  438.62  4989.2  435.86  4997.1  437.19  5002.1  437.19
  5009.2  436.21  5017.3  428.79  5017.5  428.29  5021.3  428.79  5029.3  430.14
  5049.3  435.83  5059.3  437.03  5069.3  433.21  5079.3  431.69  5089.3  433.47
  5099.3  436.34  5139.3  440.08  5143.1  441.71  5150.3  443.88  5159.3  447.94
  5209.4  460.36  5219.4  464.52  5239.4  468.94  5269.4  477.15  5299.4  482.91
#Mann=5,-1,0
  4708.3    0.12       0  4838.7     0.1       0  5017.3    0.07       0
  5021.3     0.1       0  5143.1    0.12       0
Bank Sta=5017.3,5021.3
Exp/Cntr=0.3,0.1

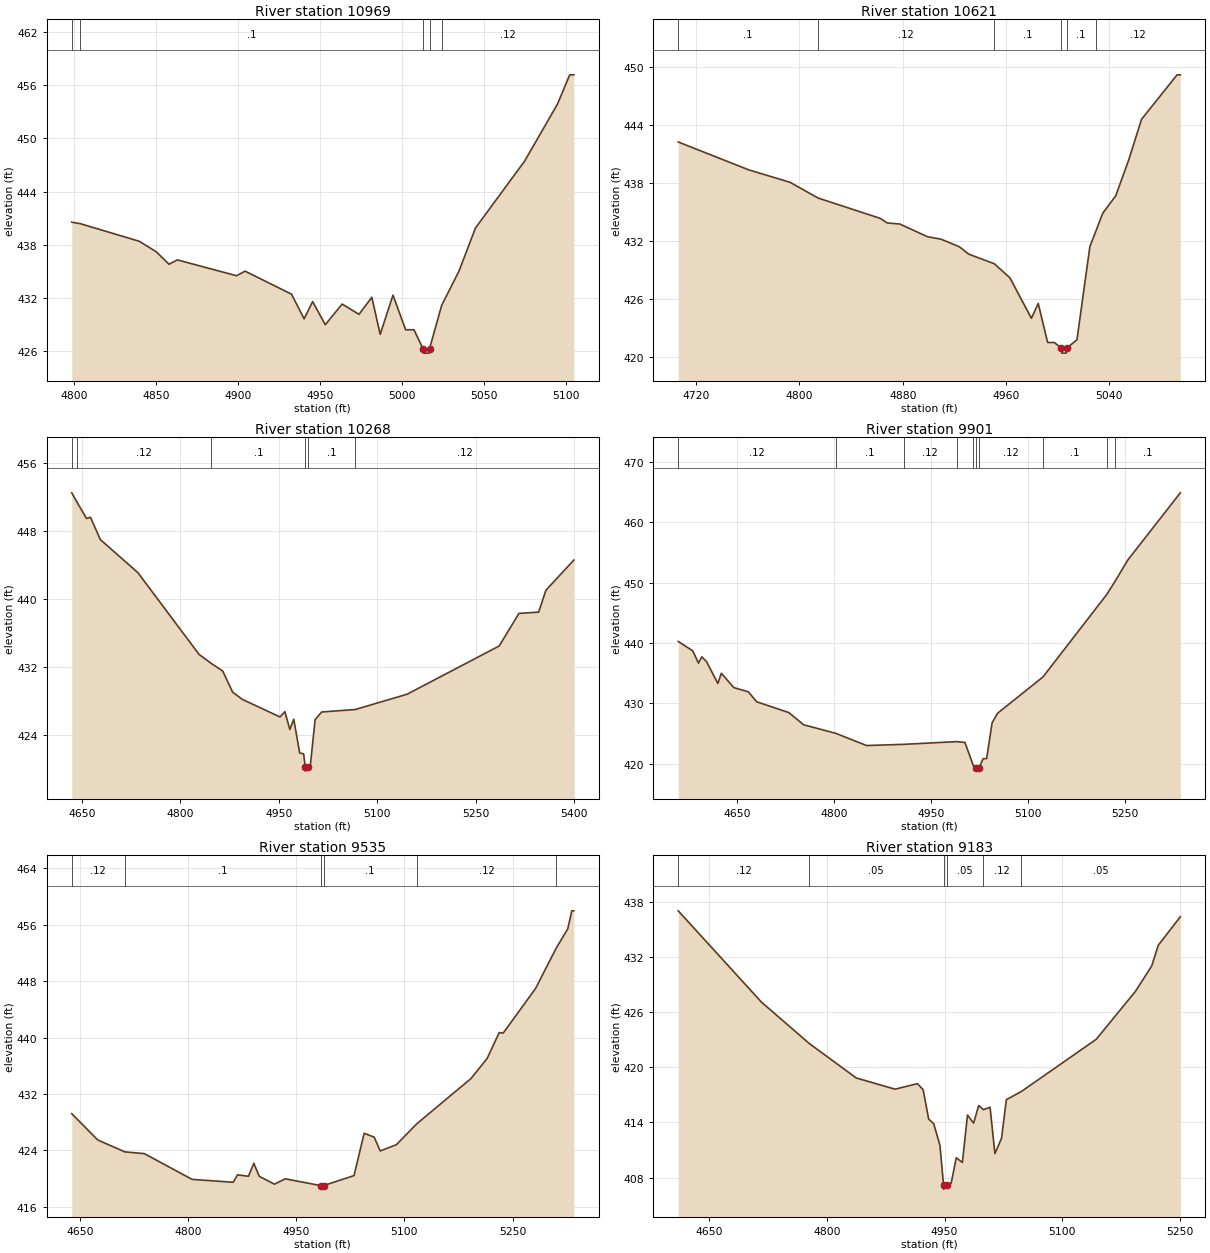
Type RM Length L Ch R = 1,10969,348,348,348
BEGIN DESCRIPTION:
Shoat Branch 26.0
END DESCRIPTION:
XS GIS Cut Line= 3
      2774076.01      6789411.00      2773876.00      6789361.00
      2773775.96      6789361.00
#Sta/Elev= 30
  4798.5  440.54  4803.7  440.37  4839.7  438.38  4850.0  437.20  4857.8  435.79
  4862.9  436.28  4899.0  434.49  4904.2  435.01  4932.5  432.41  4940.2  429.62
  4945.4  431.57  4953.1  428.96  4963.4  431.29  4973.7  430.13  4981.5  432.06
  4986.6  427.87  4994.4  432.30  5002.1  428.39  5007.2  428.39  5012.7  426.25
  5012.9  425.75  5016.4  425.75  5016.7  426.25  5024.1  431.15  5034.7  435.03
  5044.7  439.88  5074.7  447.44  5094.7  453.87  5102.2  457.18  5104.7  457.18
#Mann=5,-1,0
  4798.5    0.12       0  4803.7     0.1       0  5012.7    0.07       0
  5016.7     0.1       0  5024.1    0.12       0
Bank Sta=5012.7,5016.7
Exp/Cntr=0.3,0.1

Type RM Length L Ch R = 1,10621,353,353,353
BEGIN DESCRIPTION:
Shoat Branch 25.0
END DESCRIPTION:
XS GIS Cut Line= 3
      2774197.24      6789159.86      2773926.00      6789061.00
      2773826.00      6789061.00
#Sta/Elev= 30
  4706.2  442.28  4760.7  439.40  4792.7  438.11  4814.5  436.48  4862.7  434.37
  4868.0  433.90  4877.8  433.79  4899.1  432.48  4909.7  432.22  4923.8  431.44
  4931.0  430.68  4950.9  429.68  4963.0  428.22  4979.6  424.04  4984.9  425.57
  4992.2  421.53  4997.4  421.53  5002.9  420.93  5003.1  420.43  5006.6  420.43
  5006.9  420.93  5014.9  421.82  5024.9  431.46  5029.3  432.98  5034.9  434.92
  5044.9  436.71  5054.9  440.40  5064.9  444.63  5092.4  449.23  5094.9  449.23
#Mann=6,-1,0
  4706.2     0.1       0  4814.5    0.12       0  4950.9     0.1       0
  5002.9    0.07       0  5006.9     0.1       0  5029.3    0.12       0
Bank Sta=5002.9,5006.9
Exp/Cntr=0.3,0.1

Type RM Length L Ch R = 1,10268,367,367,367
BEGIN DESCRIPTION:
Shoat Branch 24.0
END DESCRIPTION:
XS GIS Cut Line= 3
      2774375.98      6788960.99      2774076.00      6788761.00
      2773672.49      6788777.95
#Sta/Elev= 30
  4634.8  452.46  4642.4  451.41  4657.3  449.45  4663.3  449.59  4678.3  446.97
  4735.4  443.10  4828.6  433.50  4847.5  432.42  4864.6  431.55  4879.7  429.07
  4894.7  428.21  4951.8  426.16  4959.3  426.78  4966.8  424.68  4972.8  425.89
  4981.8  421.93  4987.8  421.83  4990.3  420.30  4990.6  419.80  4994.3  420.30
  4997.8  420.30  5005.3  425.85  5015.3  426.74  5066.4  427.03  5145.5  428.83
  5285.6  434.49  5315.6  438.31  5345.6  438.46  5356.7  441.03  5399.2  444.57
#Mann=6,-1,0
  4634.8    0.05       0  4642.4    0.12       0  4847.5     0.1       0
  4990.3    0.07       0  4994.3     0.1       0  5066.4    0.12       0
Bank Sta=4990.3,4994.3
Exp/Cntr=0.3,0.1

Type RM Length L Ch R = 1,9901,366,366,366
BEGIN DESCRIPTION:
Shoat Branch 23.0
END DESCRIPTION:
XS GIS Cut Line= 3
      2774437.03      6788568.31      2774026.00      6788411.00
      2773726.01      6788261.01
#Sta/Elev= 30
  4559.4  440.26  4581.9  438.69  4590.6  436.67  4595.9  437.71  4603.3  436.87
  4620.6  433.29  4626.0  434.98  4645.3  432.60  4667.6  431.91  4680.7  430.25
  4730.1  428.47  4753.2  426.44  4802.9  425.02  4850.3  423.00  4907.9  423.20
  4989.3  423.65  5002.3  423.51  5015.3  419.63  5019.9  419.26  5020.1  418.76
  5023.9  419.26  5030.2  420.81  5035.8  420.85  5044.2  426.76  5052.6  428.35
  5122.8  434.37  5221.4  448.06  5233.3  450.08  5253.9  453.77  5334.9  464.89
#Mann=10,-1,0
  4559.4    0.12       0  4802.9     0.1       0  4907.9    0.12       0
  4989.3     0.1       0  5015.3    0.12       0  5019.9    0.07       0
  5023.9    0.12       0  5122.8     0.1       0  5221.4    0.12       0
  5233.3     0.1       0
Bank Sta=5019.9,5023.9
Exp/Cntr=0.3,0.1

Type RM Length L Ch R = 1,9535,352,352,352
BEGIN DESCRIPTION:
Shoat Branch 22.0
END DESCRIPTION:
XS GIS Cut Line= 3
      2774376.00      6788261.00      2774076.00      6788061.00
      2773775.96      6788211.02
#Sta/Elev= 30
  4639.0  429.21  4675.1  425.48  4712.6  423.80  4739.6  423.55  4805.8  419.90
  4862.8  419.49  4868.8  420.55  4883.9  420.34  4891.4  422.18  4898.9  420.34
  4919.9  419.22  4935.0  419.98  4984.0  419.02  4984.3  418.52  4988.0  419.02
  5030.3  420.44  5044.3  426.43  5058.2  425.89  5066.6  423.93  5089.0  424.82
  5117.3  427.78  5192.4  434.19  5214.8  437.04  5231.5  440.69  5237.1  440.64
  5281.9  446.95  5310.6  452.68  5326.6  455.42  5332.2  457.96  5335.0  457.96
#Mann=6,-1,0
  4639.0    0.12       0  4712.6     0.1       0  4984.0    0.07       0
  4988.0     0.1       0  5117.3    0.12       0  5310.6     0.1       0
Bank Sta=4984,4988
Exp/Cntr=0.3,0.1

Type RM Length L Ch R = 1,9183,381,381,381
BEGIN DESCRIPTION:
Shoat Branch 21.0
END DESCRIPTION:
XS GIS Cut Line= 3
      2774475.98      6788060.97      2774226.00      6787761.00
      2774025.98      6787610.99
#Sta/Elev= 30
  4610.2  437.06  4716.3  427.12  4777.0  422.63  4837.3  418.85  4886.8  417.63
  4915.4  418.23  4922.6  417.57  4929.7  414.38  4936.2  413.85  4944.1  411.49
  4948.6  407.24  4948.8  406.74  4952.6  407.24  4958.4  407.39  4964.9  410.16
  4972.7  409.65  4979.2  414.81  4987.0  413.93  4993.5  415.85  4999.6  415.40
  5008.0  415.66  5014.2  410.61  5022.6  412.27  5028.8  416.49  5047.8  417.37
  5143.4  423.06  5193.4  428.28  5214.2  431.05  5222.6  433.31  5250.7  436.41
#Mann=6,-1,0
  4610.2    0.12       0  4777.0    0.05       0  4948.6    0.07       0
  4952.6    0.05       0  4999.6    0.12       0  5047.8    0.05       0
Bank Sta=4948.6,4952.6
Exp/Cntr=0.3,0.1

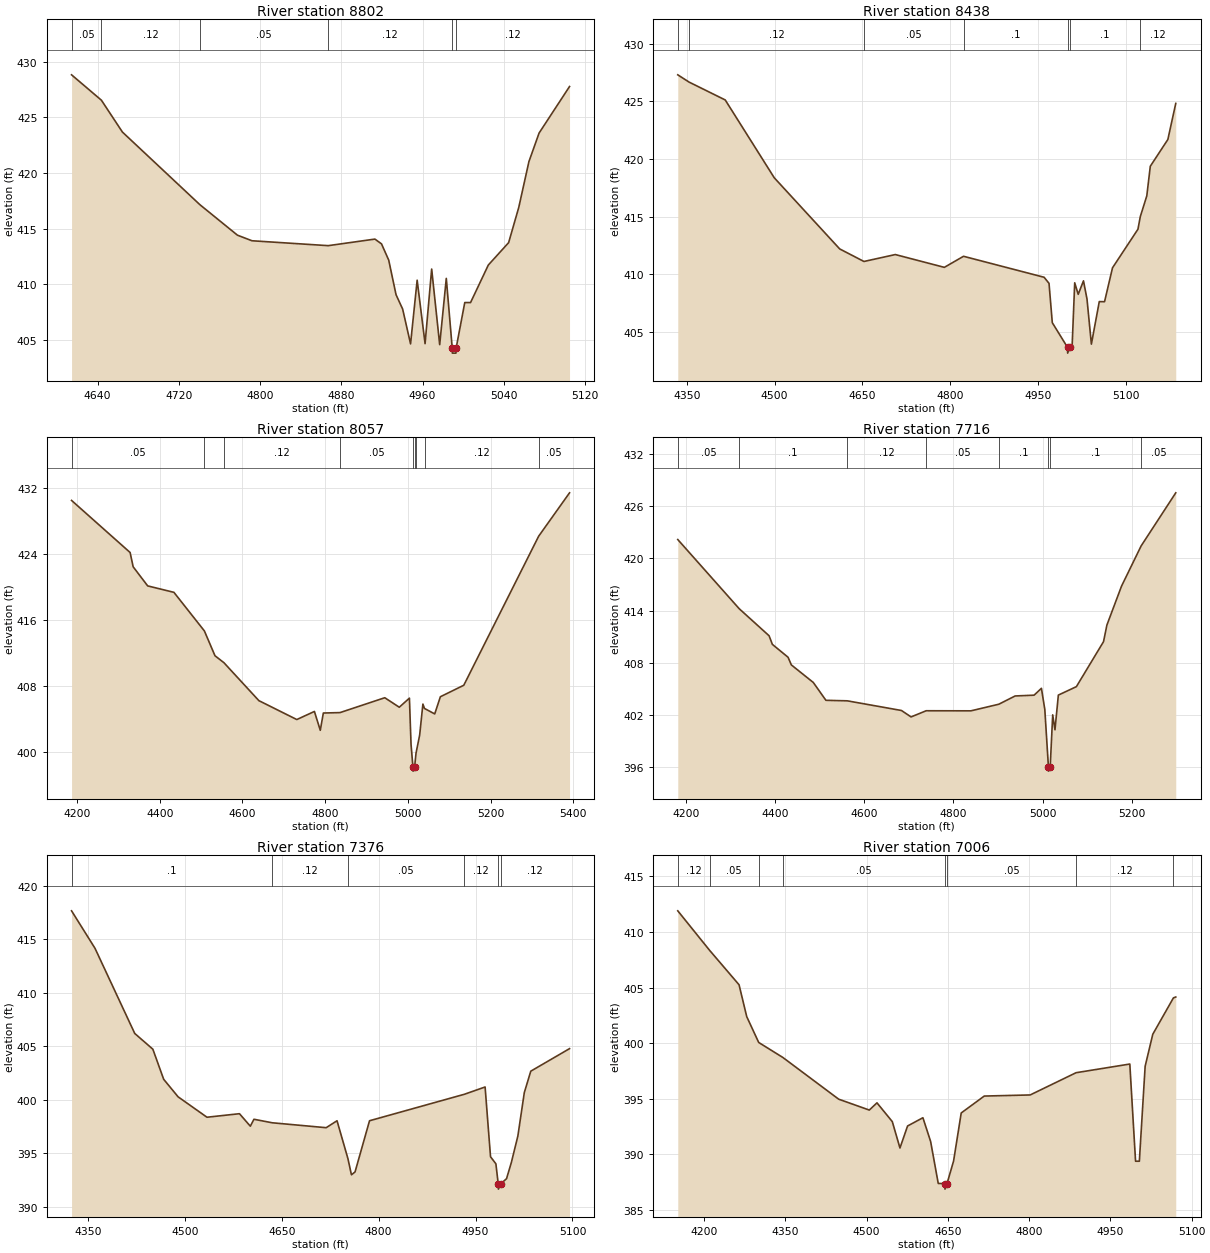
Type RM Length L Ch R = 1,8802,364,364,364
BEGIN DESCRIPTION:
Shoat Branch 20.0
END DESCRIPTION:
XS GIS Cut Line= 3
      2774526.03      6787661.02      2774226.00      6787411.00
      2774126.05      6787411.00
#Sta/Elev= 30
  4614.3  428.81  4643.7  426.53  4664.4  423.67  4740.7  417.15  4777.7  414.41
  4792.0  413.91  4867.1  413.47  4913.1  414.06  4919.6  413.63  4926.7  412.17
  4933.9  409.07  4940.4  407.78  4948.2  404.65  4954.7  410.37  4962.5  404.67
  4969.0  411.37  4976.9  404.58  4983.4  410.53  4989.2  404.32  4989.4  403.82
  4992.9  403.82  4993.2  404.32  5001.6  408.36  5007.3  408.36  5024.8  411.73
  5044.8  413.74  5054.8  416.91  5064.8  421.02  5074.8  423.58  5104.8  427.76
#Mann=6,-1,0
  4614.3    0.05       0  4643.7    0.12       0  4740.7    0.05       0
  4867.1    0.12       0  4989.2    0.07       0  4993.2    0.12       0
Bank Sta=4989.2,4993.2
Exp/Cntr=0.3,0.1

Type RM Length L Ch R = 1,8438,381,381,381
BEGIN DESCRIPTION:
Shoat Branch 19.0
END DESCRIPTION:
XS GIS Cut Line= 3
      2774576.01      6787661.03      2774276.00      6787061.00
      2774126.03      6786961.02
#Sta/Elev= 30
  4334.5  427.31  4353.8  426.68  4415.6  425.13  4499.4  418.38  4611.2  412.21
  4652.7  411.12  4706.3  411.72  4790.1  410.61  4822.9  411.57  4960.6  409.75
  4969.0  409.22  4974.6  405.81  5000.6  403.67  5000.8  403.17  5004.6  403.67
  5008.4  403.67  5012.9  409.27  5018.9  408.27  5027.9  409.44  5033.9  407.86
  5041.4  403.95  5054.9  407.64  5063.9  407.63  5077.5  410.57  5121.0  413.92
  5125.0  415.01  5136.1  416.81  5142.1  419.38  5172.1  421.70  5185.6  424.83
#Mann=7,-1,0
  4334.5    0.05       0  4353.8    0.12       0  4652.7    0.05       0
  4822.9     0.1       0  5000.6    0.07       0  5004.6     0.1       0
  5125.0    0.12       0
Bank Sta=5000.6,5004.6
Exp/Cntr=0.3,0.1

Type RM Length L Ch R = 1,8057,341,341,341
BEGIN DESCRIPTION:
Shoat Branch 18.0
END DESCRIPTION:
XS GIS Cut Line= 3
      2775176.03      6787411.03      2774576.00      6786861.00
      2774276.00      6786611.00
#Sta/Elev= 30
  4186.6  430.48  4328.2  424.18  4335.6  422.45  4370.7  420.14  4434.2  419.36
  4507.9  414.69  4533.5  411.69  4555.1  410.85  4639.6  406.26  4731.4  403.97
  4774.0  404.95  4788.2  402.67  4795.6  404.76  4835.9  404.81  4944.2  406.61
  4979.3  405.46  5003.8  406.56  5007.7  400.98  5012.3  398.23  5012.5  397.73
  5016.3  398.23  5019.8  399.91  5028.6  402.10  5036.4  405.84  5040.3  405.31
  5065.0  404.65  5078.7  406.73  5135.3  408.12  5316.4  426.15  5391.1  431.40
#Mann=9,-1,0
  4186.6    0.05       0  4507.9     0.1       0  4555.1    0.12       0
  4835.9    0.05       0  5012.3    0.04       0  5016.3    0.05       0
  5019.8     0.1       0  5040.3    0.12       0  5316.4    0.05       0
Bank Sta=5012.3,5016.3
Exp/Cntr=0.3,0.1

Type RM Length L Ch R = 1,7716,340,340,340
BEGIN DESCRIPTION:
Shoat Branch 17.0
END DESCRIPTION:
XS GIS Cut Line= 3
      2775225.99      6787210.99      2774676.00      6786611.00
      2774375.96      6786560.99
#Sta/Elev= 30
  4181.1  422.17  4319.0  414.22  4386.1  411.11  4393.5  410.12  4428.7  408.64
  4436.1  407.76  4485.4  405.74  4513.7  403.69  4561.7  403.63  4683.3  402.52
  4704.9  401.78  4738.8  402.49  4839.3  402.48  4901.9  403.24  4938.6  404.19
  4981.1  404.28  4997.6  405.07  5005.2  402.64  5013.3  396.05  5013.5  395.55
  5017.3  396.05  5022.9  402.02  5028.0  400.30  5035.6  404.29  5076.1  405.26
  5137.0  410.43  5144.6  412.34  5177.5  416.82  5221.4  421.43  5299.2  427.54
#Mann=8,-1,0
  4181.1    0.05       0  4319.0     0.1       0  4561.7    0.12       0
  4738.8    0.05       0  4901.9     0.1       0  5013.3    0.07       0
  5017.3     0.1       0  5221.4    0.05       0
Bank Sta=5013.3,5017.3
Exp/Cntr=0.3,0.1

Type RM Length L Ch R = 1,7376,370,370,370
BEGIN DESCRIPTION:
Shoat Branch 16.0
END DESCRIPTION:
XS GIS Cut Line= 3
      2775376.00      6786061.00      2774776.00      6786361.00
      2774676.02      6786361.00
#Sta/Elev= 30
  4324.7  417.68  4361.0  414.17  4422.5  406.20  4450.5  404.73  4467.3  401.91
  4489.6  400.27  4534.3  398.36  4584.6  398.69  4601.4  397.52  4607.0  398.17
  4635.3  397.84  4718.8  397.38  4735.6  398.03  4752.5  394.48  4757.9  392.97
  4763.5  393.24  4785.9  398.03  4932.8  400.51  4964.8  401.19  4973.2  394.66
  4981.5  394.00  4985.1  392.13  4985.4  391.63  4989.1  392.13  4998.0  392.61
  5005.5  394.14  5015.5  396.60  5025.5  400.67  5035.5  402.67  5095.5  404.78
#Mann=6,-1,0
  4324.7     0.1       0  4635.3    0.12       0  4752.5    0.05       0
  4932.8    0.12       0  4985.1    0.07       0  4989.1    0.12       0
Bank Sta=4985.1,4989.1
Exp/Cntr=0.3,0.1

Type RM Length L Ch R = 1,7006,342,342,342
BEGIN DESCRIPTION:
Shoat Branch 15.0
END DESCRIPTION:
XS GIS Cut Line= 3
      2775175.99      6785461.01      2774576.00      6786061.00
      2774526.01      6786110.99
#Sta/Elev= 30
  4151.5  411.91  4210.2  408.36  4264.6  405.26  4278.8  402.39  4300.9  400.07
  4345.5  398.72  4448.5  394.97  4505.0  393.99  4519.2  394.64  4547.5  392.95
  4561.6  390.58  4575.7  392.56  4604.0  393.30  4618.2  391.17  4632.3  387.39
  4644.5  387.38  4644.7  386.88  4648.5  387.38  4660.6  389.41  4674.7  393.73
  4717.2  395.25  4802.0  395.35  4886.7  397.35  4985.9  398.13  4996.5  389.39
  5003.5  389.39  5014.2  397.93  5028.3  400.81  5066.4  404.08  5070.7  404.16
#Mann=8,-1,0
  4151.5    0.12       0  4210.2    0.05       0  4300.9    0.12       0
  4345.5    0.05       0  4644.5    0.07       0  4648.5    0.05       0
  4886.7    0.12       0  5066.4    0.05       0
Bank Sta=4644.5,4648.5
Exp/Cntr=0.3,0.1

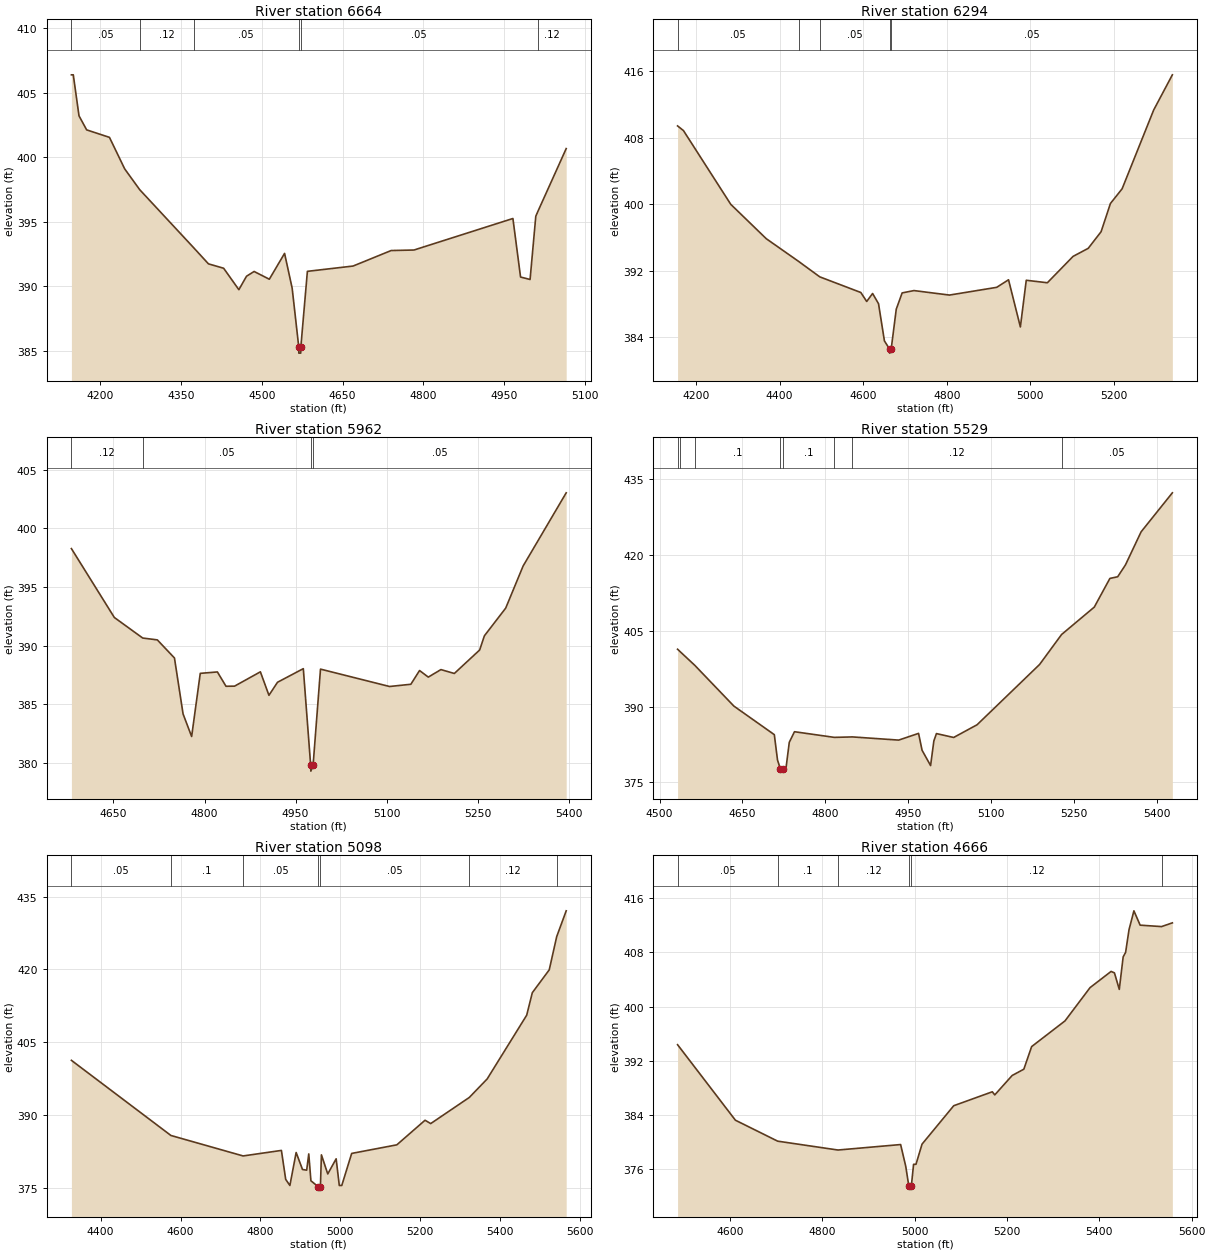
Type RM Length L Ch R = 1,6664,370,370,370
BEGIN DESCRIPTION:
Shoat Branch 14.0
END DESCRIPTION:
XS GIS Cut Line= 3
      2774975.99      6785211.01      2774376.00      6785811.00
      2774326.02      6785860.98
#Sta/Elev= 30
  4146.1  406.38  4149.6  406.38  4160.2  403.21  4174.4  402.12  4216.8  401.54
  4245.1  399.10  4273.0  397.49  4373.4  392.99  4400.7  391.75  4428.9  391.41
  4457.2  389.75  4471.4  390.79  4485.5  391.16  4513.8  390.56  4542.1  392.56
  4556.2  389.87  4568.4  385.34  4568.6  384.84  4572.1  384.84  4572.4  385.34
  4584.5  391.17  4669.4  391.58  4740.1  392.78  4782.5  392.82  4966.3  395.26
  4980.5  390.73  4998.2  390.54  5008.8  395.43  5012.4  395.78  5065.3  400.67
#Mann=6,-1,0
  4146.1    0.05       0  4273.0    0.12       0  4373.4    0.05       0
  4568.4    0.03       0  4572.4    0.05       0  5012.4    0.12       0
Bank Sta=4568.4,4572.4
Exp/Cntr=0.3,0.1

Type RM Length L Ch R = 1,6294,332,332,332
BEGIN DESCRIPTION:
Shoat Branch 13.0
END DESCRIPTION:
XS GIS Cut Line= 3
      2774826.03      6784910.97      2774226.00      6785511.00
      2774075.99      6785811.01
#Sta/Elev= 30
  4156.0  409.40  4170.2  408.83  4283.3  399.97  4368.2  395.84  4445.9  393.10
  4496.3  391.25  4594.5  389.37  4608.6  388.29  4622.7  389.25  4636.9  388.02
  4651.0  383.55  4663.2  382.58  4663.4  382.08  4667.2  382.58  4679.3  387.36
  4693.4  389.32  4721.7  389.60  4806.6  389.06  4919.7  389.99  4948.0  390.90
  4976.3  385.23  4990.4  390.84  5040.9  390.54  5102.4  393.71  5138.7  394.68
  5169.5  396.68  5191.8  400.07  5219.8  401.84  5295.3  411.31  5340.0  415.54
#Mann=5,-1,0
  4156.0    0.05       0  4445.9    0.12       0  4496.3    0.05       0
  4663.2    0.03       0  4667.2    0.05       0
Bank Sta=4663.2,4667.2
Exp/Cntr=0.3,0.1

Type RM Length L Ch R = 1,5962,433,433,433
BEGIN DESCRIPTION:
Shoat Branch 12.0
END DESCRIPTION:
XS GIS Cut Line= 3
      2774426.02      6784910.98      2774126.00      6785211.00
      2773826.00      6785461.00
#Sta/Elev= 30
  4580.8  398.27  4651.5  392.40  4698.2  390.65  4722.3  390.49  4750.5  388.95
  4764.7  384.18  4778.8  382.26  4793.0  387.64  4821.2  387.76  4835.4  386.54
  4849.5  386.55  4892.0  387.77  4906.1  385.77  4920.2  386.88  4962.7  388.04
  4974.8  379.81  4975.1  379.31  4978.8  379.81  4991.0  388.00  5104.7  386.52
  5139.8  386.71  5154.1  387.88  5168.5  387.32  5189.3  387.96  5211.4  387.63
  5253.1  389.63  5260.9  390.84  5296.0  393.20  5324.7  396.79  5395.6  403.02
#Mann=4,-1,0
  4580.8    0.12       0  4698.2    0.05       0  4974.8    0.03       0
  4978.8    0.05       0
Bank Sta=4974.8,4978.8
Exp/Cntr=0.3,0.1

Type RM Length L Ch R = 1,5529,431,431,431
BEGIN DESCRIPTION:
Shoat Branch 11.0
END DESCRIPTION:
XS GIS Cut Line= 3
      2774226.03      6784710.98      2773826.00      6784961.00
      2773526.00      6785261.00
#Sta/Elev= 30
  4532.7  401.38  4537.7  400.86  4563.9  398.19  4634.7  390.12  4707.9  384.47
  4713.7  379.44  4718.7  377.75  4719.5  377.25  4724.1  377.75  4729.1  377.88
  4735.0  382.95  4744.4  385.05  4816.6  383.93  4849.4  384.02  4933.1  383.39
  4969.1  384.72  4975.5  381.37  4990.9  378.35  4996.8  383.22  5001.5  384.68
  5032.7  383.91  5075.1  386.43  5188.3  398.36  5228.1  404.29  5287.3  409.71
  5315.6  415.39  5329.7  415.72  5343.8  418.07  5372.1  424.61  5428.7  432.33
#Mann=8,-1,0
  4532.7    0.05       0  4537.7    0.12       0  4563.9     0.1       0
  4718.7    0.07       0  4724.1     0.1       0  4816.6    0.05       0
  4849.4    0.12       0  5228.1    0.05       0
Bank Sta=4718.7,4724.1
Exp/Cntr=0.3,0.1

Type RM Length L Ch R = 1,5098,432,432,432
BEGIN DESCRIPTION:
Shoat Branch 10.0
END DESCRIPTION:
XS GIS Cut Line= 3
      2774315.38      6784398.46      2773676.00      6784611.00
      2773275.98      6785011.02
#Sta/Elev= 30
  4326.7  401.26  4576.0  385.77  4756.8  381.55  4852.8  382.69  4863.5  376.73
  4874.0  375.46  4889.7  382.26  4905.6  378.76  4916.1  378.62  4921.3  381.97
  4926.7  376.43  4945.0  375.21  4945.8  374.71  4950.5  375.21  4953.0  381.78
  4968.9  377.84  4989.9  380.96  4997.8  375.46  5004.0  375.46  5028.8  382.07
  5141.9  383.84  5212.6  388.91  5226.8  388.22  5323.5  393.61  5368.2  397.42
  5467.2  410.56  5481.3  415.20  5523.7  419.91  5542.4  426.76  5566.2  432.08
#Mann=7,-1,0
  4326.7    0.05       0  4576.0     0.1       0  4756.8    0.05       0
  4945.0    0.05       0  4950.5    0.05       0  5323.5    0.12       0
  5542.4    0.05       0
Bank Sta=4945,4950.5
Exp/Cntr=0.3,0.1

Type RM Length L Ch R = 1,4666,482,482,482
BEGIN DESCRIPTION:
Shoat Branch 9.0
END DESCRIPTION:
XS GIS Cut Line= 3
      2774128.49      6784102.87      2773626.00      6784211.00
      2773097.05      6784389.03
#Sta/Elev= 30
  4486.1  394.36  4611.4  383.20  4703.0  380.10  4833.7  378.79  4969.4  379.60
  4980.5  376.39  4987.1  373.51  4987.9  373.01  4992.7  373.51  4997.5  376.68
  5002.7  376.68  5015.8  379.66  5084.5  385.34  5168.1  387.40  5173.4  386.94
  5211.1  389.81  5236.4  390.74  5253.3  394.08  5325.6  397.88  5379.9  402.80
  5425.4  405.19  5432.7  404.98  5443.2  402.54  5451.6  407.34  5456.9  408.01
  5464.3  411.36  5474.9  414.15  5488.4  412.03  5534.8  411.82  5558.2  412.37
#Mann=6,-1,0
  4486.1    0.05       0  4703.0     0.1       0  4833.7    0.12       0
  4987.1    0.07       0  4992.7    0.12       0  5534.8    0.05       0
Bank Sta=4987.1,4992.7
Exp/Cntr=0.3,0.1

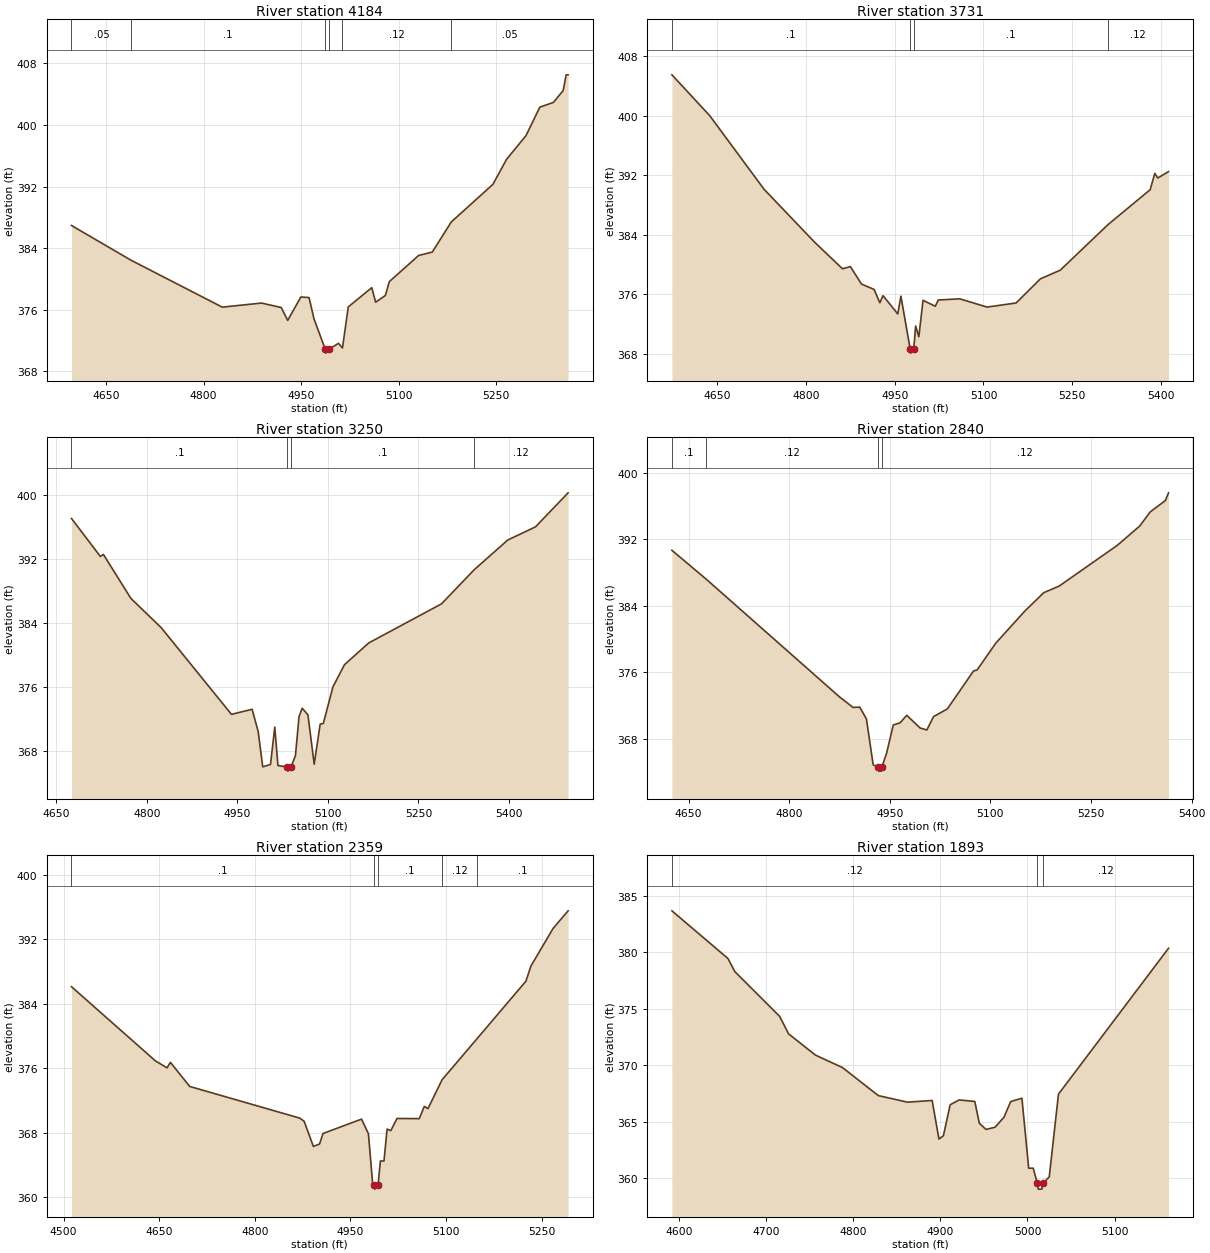
Type RM Length L Ch R = 1,4184,453,453,453
BEGIN DESCRIPTION:
Shoat Branch 8.0
END DESCRIPTION:
XS GIS Cut Line= 3
      2773925.97      6783711.00      2773526.00      6783761.00
      2773226.03      6783960.98
#Sta/Elev= 30
  4596.8  386.94  4688.6  382.42  4828.6  376.34  4889.0  376.87  4919.3  376.29
  4929.3  374.62  4949.5  377.66  4962.1  377.58  4969.7  374.82  4987.0  370.87
  4987.9  370.37  4992.6  370.87  5007.4  371.64  5013.5  371.04  5022.4  376.37
  5058.5  378.87  5064.5  376.98  5079.5  377.86  5085.5  379.65  5130.6  383.05
  5151.6  383.49  5180.8  387.40  5244.8  392.28  5265.8  395.53  5295.8  398.62
  5316.9  402.30  5337.9  402.92  5352.9  404.47  5357.4  406.50  5360.4  406.50
#Mann=6,-1,0
  4596.8    0.05       0  4688.6     0.1       0  4987.0    0.07       0
  4992.6     0.1       0  5013.5    0.12       0  5180.8    0.05       0
Bank Sta=4987,4992.6
Exp/Cntr=0.3,0.1

Type RM Length L Ch R = 1,3731,481,481,481
BEGIN DESCRIPTION:
Shoat Branch 7.0
END DESCRIPTION:
XS GIS Cut Line= 3
      2774075.95      6783211.02      2773676.00      6783361.00
      2773275.96      6783260.99
#Sta/Elev= 30
  4573.3  405.50  4637.3  400.00  4729.0  390.12  4814.4  383.01  4861.6  379.43
  4875.0  379.72  4893.7  377.38  4915.0  376.65  4924.8  374.86  4930.1  375.82
  4955.1  373.36  4960.4  375.75  4976.2  368.59  4977.1  368.09  4982.0  368.59
  4985.3  371.74  4990.7  370.29  4997.8  375.19  5018.5  374.39  5023.6  375.23
  5059.7  375.39  5106.1  374.28  5155.1  374.83  5196.3  378.08  5229.8  379.24
  5310.7  385.38  5381.8  390.06  5389.6  392.25  5394.7  391.63  5412.8  392.49
#Mann=4,-1,0
  4573.3     0.1       0  4976.2    0.07       0  4982.0     0.1       0
  5310.7    0.12       0
Bank Sta=4976.2,4982
Exp/Cntr=0.3,0.1

Type RM Length L Ch R = 1,3250,410,410,410
BEGIN DESCRIPTION:
Shoat Branch 6.0
END DESCRIPTION:
XS GIS Cut Line= 3
      2773993.90      6782940.93      2773676.00      6782911.00
      2773189.42      6783040.02
#Sta/Elev= 30
  4675.2  397.01  4723.0  392.27  4728.1  392.52  4773.5  387.04  4823.8  383.38
  4940.2  372.56  4974.4  373.19  4984.5  370.42  4992.0  366.01  5004.9  366.30
  5012.0  370.97  5017.2  366.17  5033.0  365.97  5033.9  365.47  5038.8  365.97
  5046.2  367.40  5052.2  372.29  5057.4  373.32  5066.9  372.50  5077.3  366.33
  5087.2  371.34  5092.4  371.42  5108.3  375.98  5127.4  378.75  5167.6  381.47
  5288.2  386.35  5342.2  390.60  5398.0  394.32  5443.9  395.96  5497.9  400.21
#Mann=4,-1,0
  4675.2     0.1       0  5033.0    0.07       0  5038.8     0.1       0
  5342.2    0.12       0
Bank Sta=5033,5038.8
Exp/Cntr=0.3,0.1

Type RM Length L Ch R = 1,2840,481,481,481
BEGIN DESCRIPTION:
Shoat Branch 5.0
END DESCRIPTION:
XS GIS Cut Line= 3
      2774026.04      6782561.00      2773626.00      6782561.00
      2773299.98      6782658.39
#Sta/Elev= 30
  4625.2  390.67  4676.3  387.20  4875.2  373.02  4895.2  371.77  4905.2  371.80
  4915.2  370.37  4925.2  364.86  4932.3  364.60  4933.2  364.10  4937.2  364.10
  4938.2  364.60  4945.2  366.25  4955.2  369.66  4965.2  369.90  4975.2  370.82
  4995.2  369.29  5005.2  369.05  5015.2  370.66  5035.7  371.58  5074.9  376.16
  5080.1  376.27  5108.1  379.51  5151.6  383.39  5179.5  385.57  5202.7  386.38
  5289.3  391.28  5322.5  393.59  5338.3  395.30  5360.8  396.66  5365.5  397.59
#Mann=4,-1,0
  4625.2     0.1       0  4676.3    0.12       0  4932.3    0.07       0
  4938.2    0.12       0
Bank Sta=4932.3,4938.2
Exp/Cntr=0.3,0.1

Type RM Length L Ch R = 1,2359,466,466,466
BEGIN DESCRIPTION:
Shoat Branch 4.0
END DESCRIPTION:
XS GIS Cut Line= 3
      2773977.99      6781979.37      2773526.00      6782161.00
      2773275.97      6782311.02
#Sta/Elev= 30
  4512.5  386.13  4644.0  376.94  4662.3  376.07  4667.6  376.75  4697.9  373.76
  4870.3  369.84  4877.3  369.45  4891.8  366.32  4901.5  366.63  4906.9  367.93
  4967.3  369.71  4978.1  367.90  4984.8  361.66  4987.2  361.53  4988.2  361.03
  4993.2  361.53  4996.9  364.52  5002.5  364.52  5007.4  368.48  5013.2  368.28
  5022.9  369.79  5057.9  369.77  5065.7  371.29  5071.5  371.02  5093.6  374.59
  5148.8  379.72  5225.1  386.82  5232.9  388.69  5267.8  393.37  5291.2  395.54
#Mann=5,-1,0
  4512.5     0.1       0  4987.2    0.07       0  4993.2     0.1       0
  5093.6    0.12       0  5148.8     0.1       0
Bank Sta=4987.2,4993.2
Exp/Cntr=0.3,0.1

Type RM Length L Ch R = 1,1893,460,460,460
BEGIN DESCRIPTION:
Shoat Branch 3.0
END DESCRIPTION:
XS GIS Cut Line= 3
      2773876.02      6781811.00      2773476.00      6781711.00
      2773326.04      6781760.99
#Sta/Elev= 30
  4591.6  383.67  4656.0  379.45  4663.8  378.30  4715.3  374.34  4725.6  372.79
  4756.5  370.91  4787.5  369.81  4828.7  367.33  4862.2  366.75  4890.5  366.90
  4898.3  363.49  4903.4  363.78  4911.2  366.52  4921.5  366.95  4939.5  366.81
  4944.7  364.88  4952.4  364.34  4962.7  364.53  4973.0  365.42  4980.7  366.80
  4993.6  367.10  5001.4  360.91  5006.6  360.91  5011.4  359.56  5012.4  359.06
  5016.5  359.06  5017.5  359.56  5025.0  360.14  5035.6  367.46  5162.0  380.36
#Mann=3,-1,0
  4591.6    0.12       0  5011.4    0.07       0  5017.5    0.12       0
Bank Sta=5011.4,5017.5
Exp/Cntr=0.3,0.1