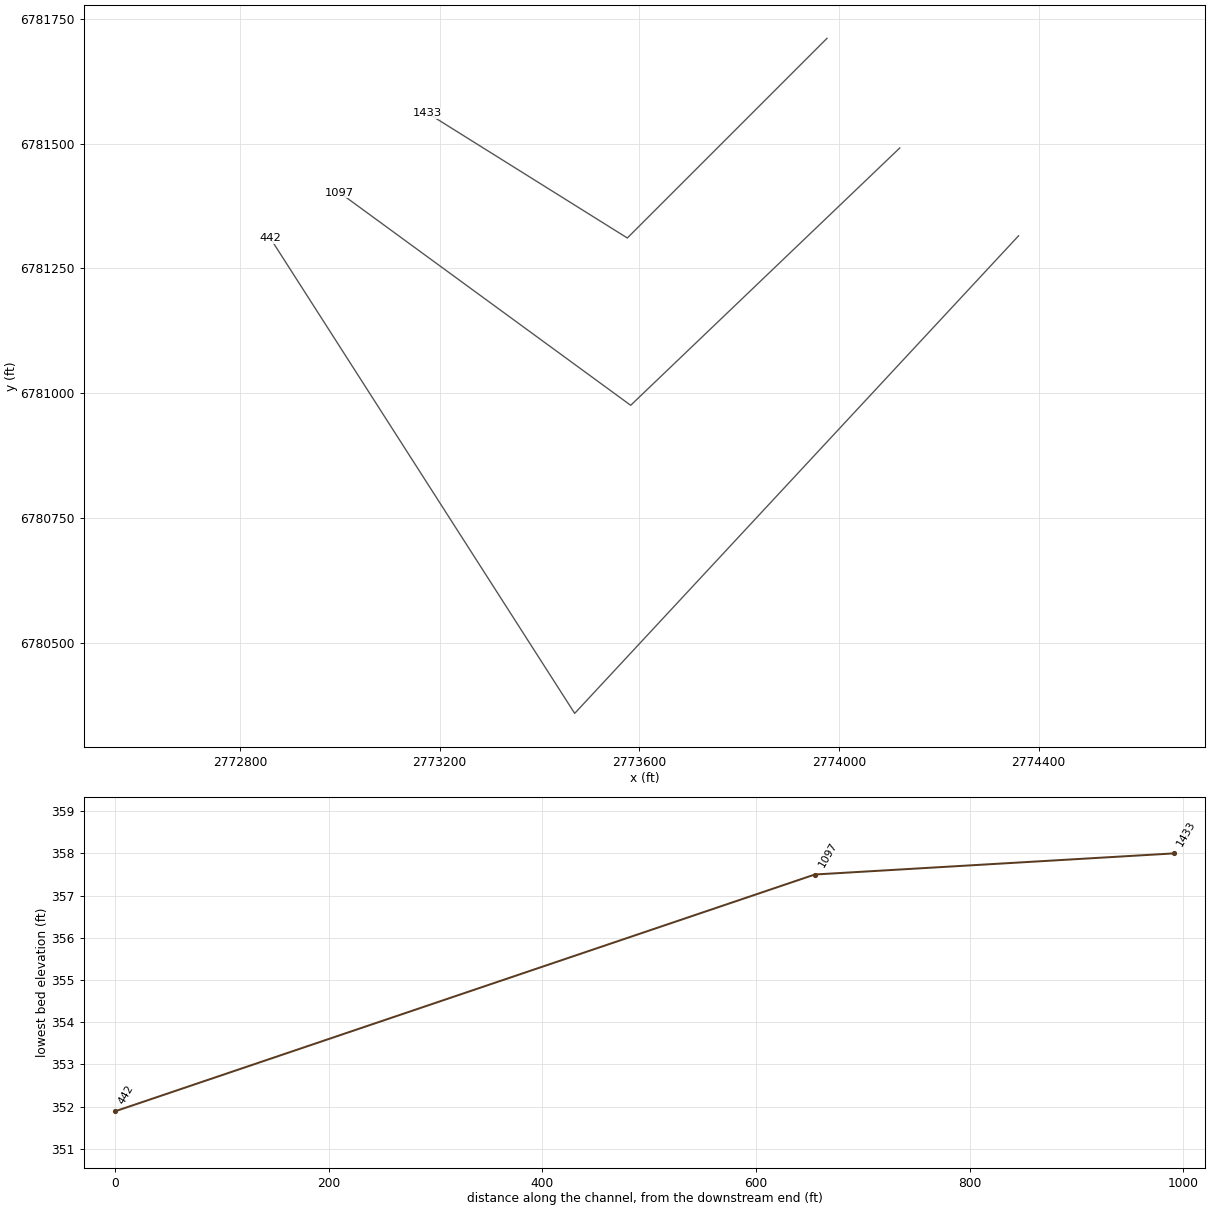
HEC-RAS study Shoat Branch.prj: Shoat Branch Base Level Engineering

--- Shoat Branch.g01 (geometry) --- (continued)

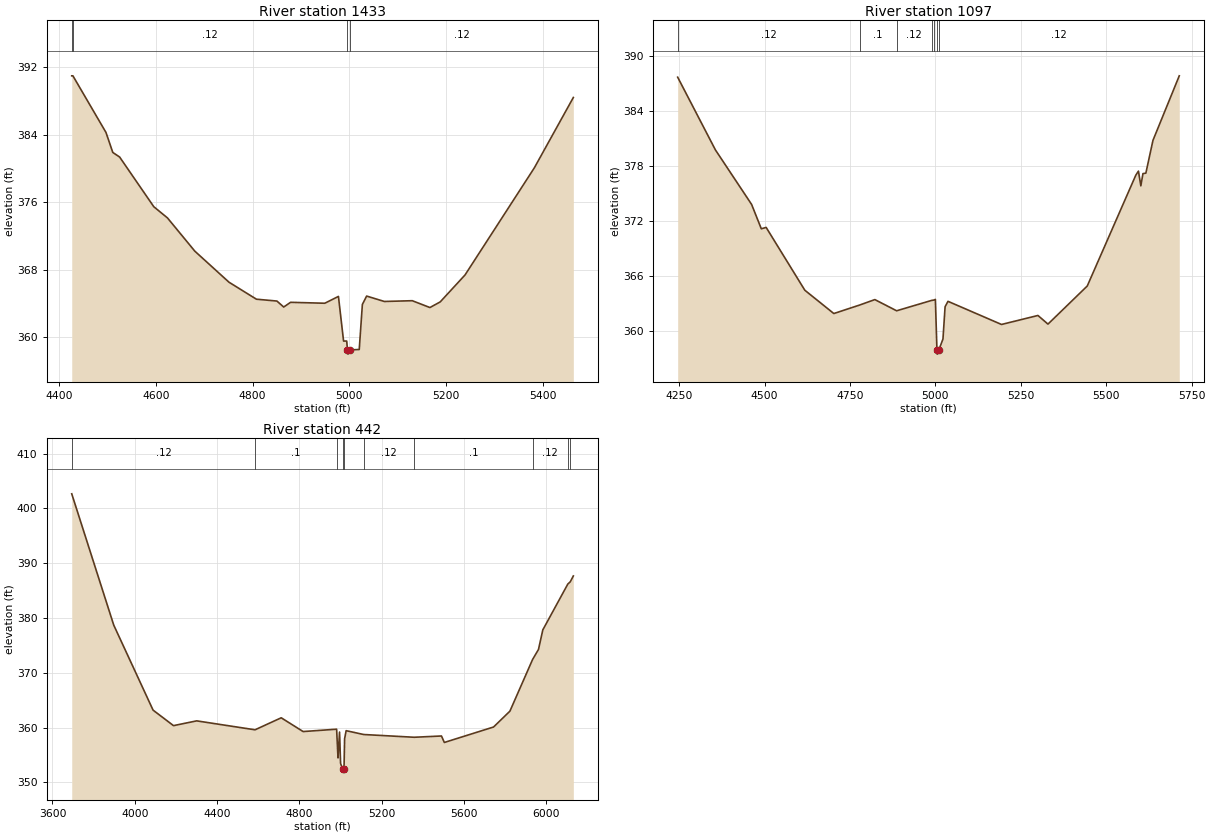
Type RM Length L Ch R = 1,1433,336,336,336
BEGIN DESCRIPTION:
Shoat Branch 2.0
END DESCRIPTION:
XS GIS Cut Line= 3
      2773976.03      6781711.03      2773576.00      6781311.00
      2773176.02      6781560.99
#Sta/Elev= 30
  4425.9  390.98  4428.3  390.98  4496.7  384.27  4510.8  381.90  4524.9  381.36
  4595.6  375.47  4623.9  374.14  4680.5  370.20  4751.2  366.52  4807.8  364.51
  4850.2  364.29  4864.3  363.58  4878.5  364.14  4949.2  364.03  4977.5  364.84
  4988.1  359.55  4994.6  359.55  4996.2  358.50  4997.2  358.00  5002.3  358.50
  5020.5  358.55  5027.0  363.89  5035.8  364.88  5072.4  364.24  5130.2  364.33
  5166.7  363.52  5188.0  364.19  5239.3  367.38  5382.5  380.06  5463.3  388.41
#Mann=4,-1,0
  4425.9     0.1       0  4428.3    0.12       0  4996.2    0.07       0
  5002.3    0.12       0
Bank Sta=4996.2,5002.3
Exp/Cntr=0.3,0.1

Type RM Length L Ch R = 1,1097,655,655,655
BEGIN DESCRIPTION:
Mapping XS 007d65d2
END DESCRIPTION:
XS GIS Cut Line= 3
      2774121.90      6781491.40      2773582.75      6780975.80
      2772999.54      6781401.91
#Sta/Elev= 30
  4245.5  387.66  4356.0  379.74  4462.0  373.80  4490.3  371.15  4504.5  371.30
  4617.7  364.46  4702.6  361.92  4778.4  362.85  4822.7  363.44  4886.4  362.22
  4988.9  363.35  4995.8  363.39  4999.9  363.46  5004.4  358.00  5005.4  357.50
  5010.5  358.00  5022.1  359.15  5028.3  362.66  5036.8  363.25  5193.5  360.73
  5300.1  361.71  5329.5  360.77  5444.5  364.92  5586.6  376.99  5594.3  377.43
  5601.3  375.83  5607.5  377.16  5616.0  377.21  5636.8  380.78  5713.8  387.81
#Mann=7,-1,0
  4245.5    0.12       0  4778.4     0.1       0  4886.4    0.12       0
  4988.9     0.1       0  4995.8    0.12       0  5004.4    0.07       0
  5010.5    0.12       0
Bank Sta=5004.4,5010.5
Exp/Cntr=0.3,0.1

Type RM Length L Ch R = 1,442,0,0,0
BEGIN DESCRIPTION:
Shoat Branch 1.0
END DESCRIPTION:
XS GIS Cut Line= 3
      2774359.92      6781315.46      2773470.54      6780358.55
      2772860.82      6781310.41
#Sta/Elev= 30
  3693.6  402.65  3897.7  378.70  4088.7  363.20  4187.9  360.37  4300.7  361.24
  4584.0  359.61  4711.2  361.80  4817.7  359.29  4980.4  359.72  4983.9  357.02
  4987.2  354.48  4994.6  359.20  4999.7  353.46  5010.2  352.39  5011.2  351.89
  5016.3  352.39  5019.2  357.98  5026.7  359.45  5111.9  358.75  5357.2  358.25
  5489.8  358.48  5503.7  357.30  5742.9  360.12  5822.3  363.01  5932.8  372.46
  5961.1  374.26  5982.2  377.84  6103.8  386.20  6115.4  386.60  6130.4  387.67
#Mann=10,-1,0
  3693.6    0.12       0  4584.0     0.1       0  4983.9    0.12       0
  5010.2    0.07       0  5016.3    0.12       0  5111.9    0.12       0
  5357.2     0.1       0  5932.8    0.12       0  6103.8     0.1       0
  6115.4    0.12       0
Bank Sta=5010.2,5016.3
Exp/Cntr=0.3,0.1

Chan Stop Cuts=-1