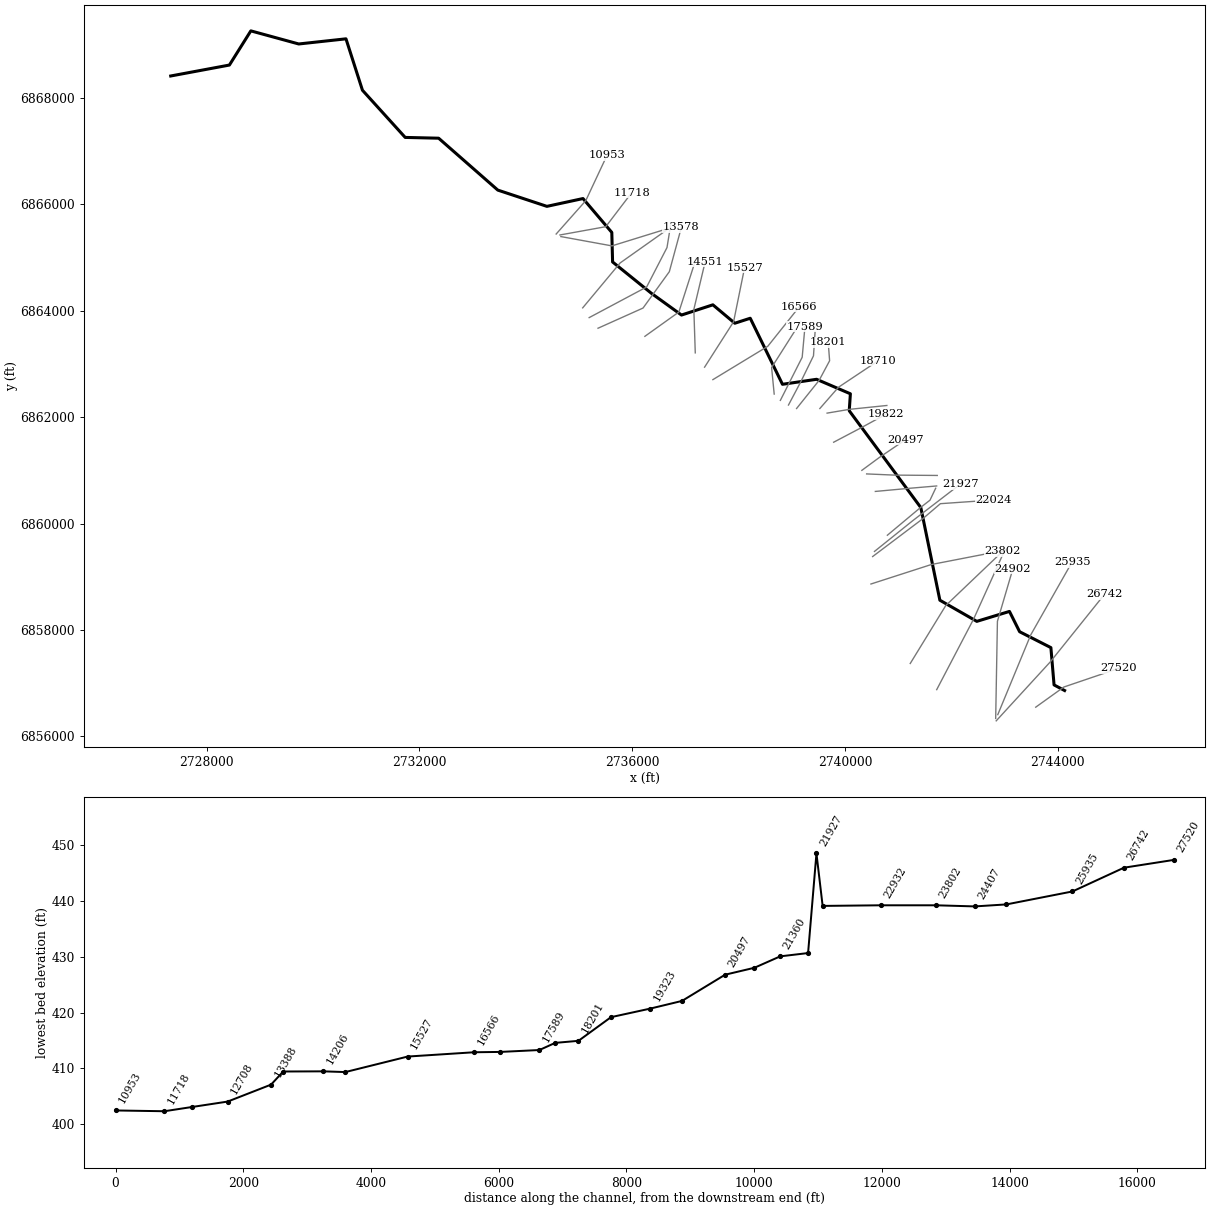
--- South Fork Lacy Fork.prj (project) ---

Proj Title=South Fork Lacy Fork Base Level Engineering
Current Plan=p01
Default Exp/Contr=0.3,0.1
English Units
Geom File=g01
Flow File=f01
Plan File=p01
BEGIN DESCRIPTION:
South Fork Lacy Fork
END DESCRIPTION:

--- South Fork Lacy Fork.p01 (plan) ---

Plan Title=Multiple Run
Short Identifier=Multiple
Geom File=g01
Flow File=f01
Subcritical Flow
K Sum by GR= 0
Std Step Tol= 0.01
Critical Tol= 0.01
Num of Std Step Trials= 20
Max Error Tol= 0.3
Flow Tol Ratio= 0.001
Split Flow NTrial= 30
Split Flow Tol= 0.02
Split Flow Ratio= 0.02
Log Output Level= 0
Friction Slope Method= 1
Unsteady Friction Slope Method= 2
Unsteady Bridges Friction Slope Method= 1
Parabolic Critical Depth
Global Vel Dist=  1 , 1 , 1
Global Log Level= 0
CheckData=True
Encroach Param= -1, 0, 0, 0
BEGIN DESCRIPTION:
Multiple Run
END DESCRIPTION:

--- South Fork Lacy Fork.f01 (steady flow) ---

Flow Title=Multiple
Number of Profiles=7
Profile Names=10-year,25-year,50-year,1pct_min,100-year,1pct_plu,500-year
River Rch & RM= South Fork Lacy ,Reach-1,27520
     276     348     404     232     464     925     613
River Rch & RM= South Fork Lacy ,Reach-1,25935
     456     597     708     417     833    1662    1155
River Rch & RM= South Fork Lacy ,Reach-1,24407
     693     928    1119     669    1334    2663    1904
River Rch & RM= South Fork Lacy ,Reach-1,18201
    2261    3225    4051    2513    5015   10006    7689
River Rch & RM= South Fork Lacy ,Reach-1,16566
    2712    3901    4927    3073    6131   12233    9498
River Rch & RM= South Fork Lacy ,Reach-1,14206
    2651    3796    4782    2973    5932   11836    9134
River Rch & RM= South Fork Lacy ,Reach-1,12156
    2760    3958    4989    3103    6192   12355    9544
River Rch & RM= South Fork Lacy ,Reach-1,11718
    2759    3947    4966    3084    6153   12276    9448
River Rch & RM= South Fork Lacy ,Reach-1,9937
    2824    4039    5081    3154    6293   12556    9657
River Rch & RM= South Fork Lacy ,Reach-1,8341
    2796    3987    5007    3101    6188   12347    9457
River Rch & RM= South Fork Lacy ,Reach-1,6684
    2633    3726    4653    2866    5719   11411    8642
River Rch & RM= South Fork Lacy ,Reach-1,3224
    2893    4121    5171    3200    6384   12738    9736
Boundary for River Rch & Prof#=South Fork Lacy ,Reach-1,1
Up Type=0
Dn Type=3
Dn Slope=0.005
Boundary for River Rch & Prof#=South Fork Lacy ,Reach-1,2
Up Type=0
Dn Type=3
Dn Slope=0.005
Boundary for River Rch & Prof#=South Fork Lacy ,Reach-1,3
Up Type=0
Dn Type=3
Dn Slope=0.005
Boundary for River Rch & Prof#=South Fork Lacy ,Reach-1,4
Up Type=0
Dn Type=3
Dn Slope=0.005
Boundary for River Rch & Prof#=South Fork Lacy ,Reach-1,5
Up Type=0
Dn Type=3
Dn Slope=0.005
Boundary for River Rch & Prof#=South Fork Lacy ,Reach-1,6
Up Type=0
Dn Type=3
Dn Slope=0.005
Boundary for River Rch & Prof#=South Fork Lacy ,Reach-1,7
Up Type=0
Dn Type=3
Dn Slope=0.005

--- South Fork Lacy Fork.g01 (geometry) ---

Geom Title=Existing Conditions

River Reach=South Fork Lacy ,Reach-1
Reach XY= 30
      2744126.00      6856861.00      2743928.06      6856966.45
      2743868.36      6857667.45      2743280.66      6857966.26
      2743089.75      6858347.76      2742476.00      6858161.00
      2741781.83      6858558.70      2741423.85      6860299.73
      2740078.44      6862119.11      2740099.96      6862438.19
      2739464.38      6862710.50      2738823.53      6862616.45
      2738217.98      6863857.87      2737927.62      6863764.12
      2737515.66      6864110.13      2736925.98      6863918.08
      2736362.79      6864324.63      2735630.79      6864915.79
      2735616.01      6865470.95      2735074.53      6866107.47
      2734396.21      6865960.79      2733473.29      6866266.40
      2732361.37      6867241.76      2731732.78      6867256.38
      2730929.60      6868143.01      2730619.96      6869109.42
      2729732.13      6869012.67      2728831.86      6869258.94
      2728428.98      6868616.52      2727326.00      6868411.00

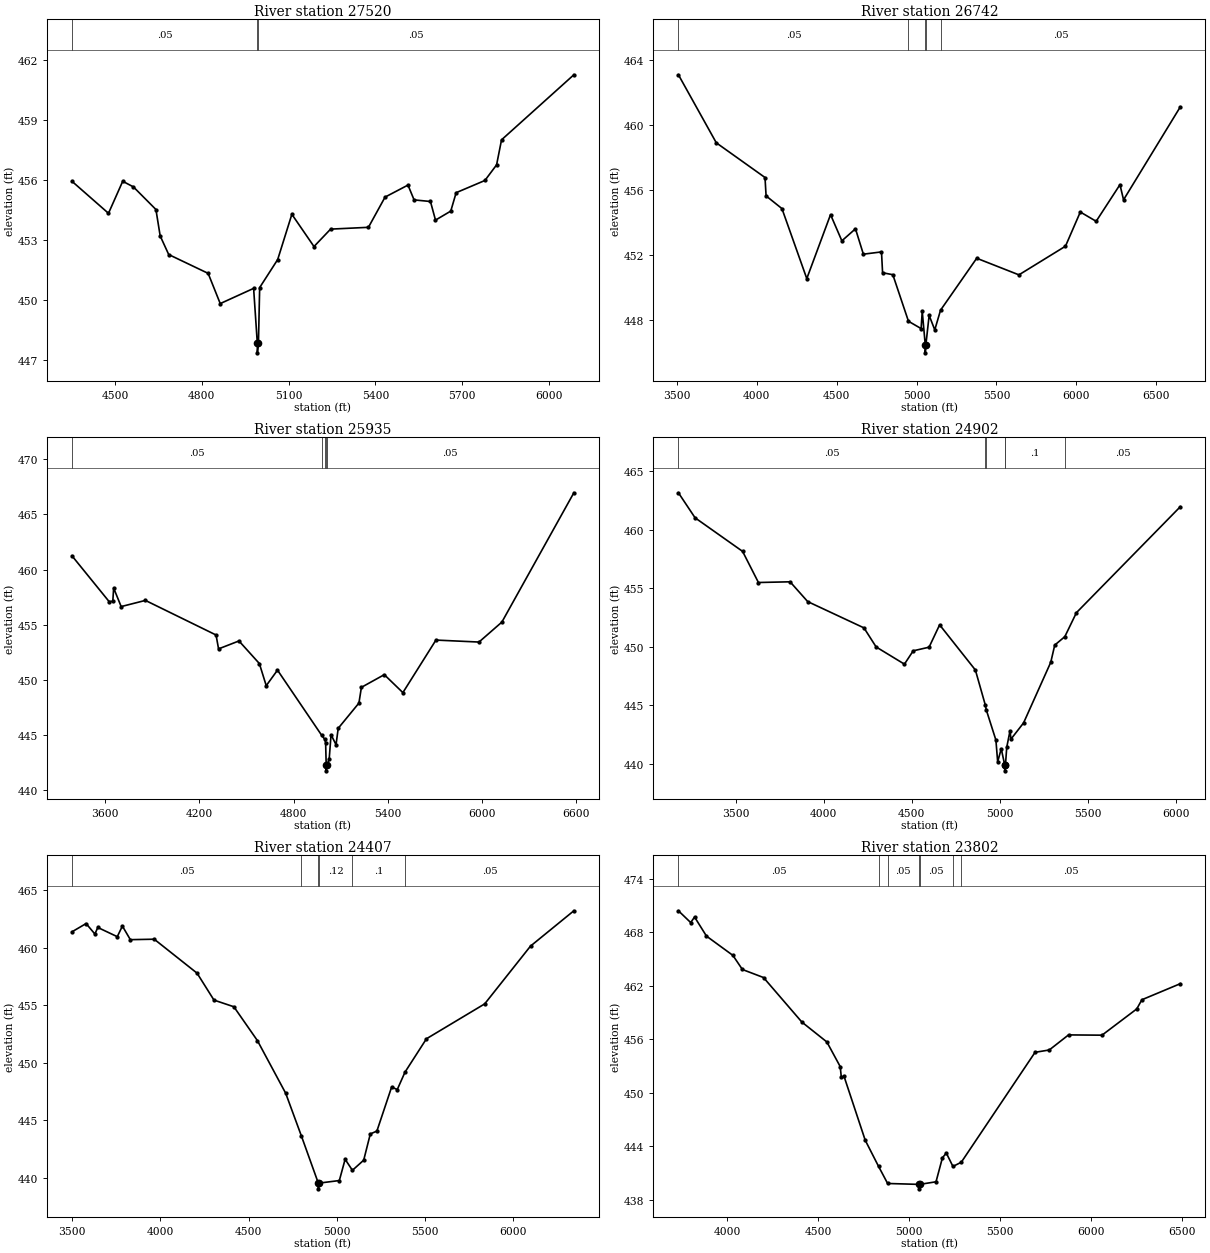
Type RM Length L Ch R = 1,27520,778,778,778
BEGIN DESCRIPTION:
South Fork Lacy Fork 1782
END DESCRIPTION:
XS GIS Cut Line= 4
      2743583.39      6856548.08      2744111.29      6856926.68
      2744571.55      6857083.18      2745138.88      6857276.09
#Sta/Elev= 30
  4351.1  455.95  4477.4  454.35  4526.6  455.95  4563.5  455.67  4641.4  454.54
  4656.1  453.22  4685.6  452.29  4821.9  451.35  4863.7  449.84  4979.1  450.60
  4991.8  447.88  4992.1  447.38  4995.8  447.88  5000.0  450.64  5062.3  452.04
  5111.3  454.30  5187.8  452.69  5245.2  453.56  5376.0  453.65  5433.5  455.16
  5512.7  455.76  5533.8  455.02  5590.4  454.94  5607.8  454.01  5660.6  454.46
  5679.2  455.38  5778.6  455.99  5819.0  456.77  5836.1  458.02  6086.1  461.27
#Mann=3,-1,0
  4351.1    0.05       0  4991.8    0.04       0  4995.8    0.05       0
Bank Sta=4991.8,4995.8
Exp/Cntr=0.3,0.1

Type RM Length L Ch R = 1,26742,807,807,807
BEGIN DESCRIPTION:
South Fork Lacy Fork 1786
END DESCRIPTION:
XS GIS Cut Line= 3
      2742840.68      6856291.35      2743856.25      6857398.55
      2744881.27      6858675.66
#Sta/Elev= 30
  3510.1  463.07  3747.2  458.89  4051.8  456.76  4058.6  455.63  4157.8  454.85
  4313.2  450.55  4461.8  454.48  4532.7  452.87  4617.8  453.61  4667.2  452.05
  4780.6  452.19  4787.4  450.91  4851.5  450.79  4949.3  447.93  5028.5  447.48
  5035.5  448.53  5054.3  446.49  5054.6  445.99  5058.3  446.49  5078.7  448.29
  5113.9  447.40  5150.0  448.61  5376.3  451.80  5640.4  450.78  5931.6  452.54
  6024.4  454.64  6123.6  454.07  6272.5  456.32  6294.9  455.39  6650.1  461.10
#Mann=5,-1,0
  3510.1    0.05       0  4949.3    0.12       0  5054.3    0.07       0
  5058.3    0.12       0  5150.0    0.05       0
Bank Sta=5054.3,5058.3
Exp/Cntr=0.3,0.1

Type RM Length L Ch R = 1,25935,1033,1033,1033
BEGIN DESCRIPTION:
South Fork Lacy Fork 3425
END DESCRIPTION:
XS GIS Cut Line= 3
      2742870.61      6856408.19      2743489.61      6857906.75
      2744266.46      6859275.95
#Sta/Elev= 30
  3388.0  461.25  3624.2  457.10  3648.1  457.12  3653.5  458.32  3701.4  456.64
  3855.7  457.20  4305.5  454.06  4321.5  452.80  4451.4  453.52  4581.2  451.47
  4625.0  449.46  4696.7  450.87  4977.8  444.96  4998.3  444.58  5003.1  444.28
  5006.9  442.23  5007.2  441.73  5011.0  442.23  5025.8  442.79  5037.7  445.01
  5069.5  444.10  5083.2  445.59  5215.1  447.88  5231.0  449.31  5376.7  450.46
  5495.0  448.83  5705.5  453.60  5979.6  453.42  6125.2  455.23  6583.6  466.97
#Mann=5,-1,0
  3388.0    0.05       0  4977.8    0.12       0  4998.3    0.05       0
  5006.9    0.04       0  5011.0    0.05       0
Bank Sta=5006.9,5011
Exp/Cntr=0.3,0.1

Type RM Length L Ch R = 1,24902,495,495,495
BEGIN DESCRIPTION:
South Fork Lacy Fork 1783
END DESCRIPTION:
XS GIS Cut Line= 3
      2742830.80      6856336.17      2742863.50      6858162.23
      2743153.61      6859147.66
#Sta/Elev= 30
  3173.8  463.18  3268.6  461.04  3538.7  458.17  3628.7  455.51  3808.7  455.57
  3908.7  453.88  4228.8  451.63  4298.0  450.00  4458.8  448.53  4508.8  449.67
  4598.9  449.98  4658.9  451.89  4862.2  448.03  4918.6  445.04  4924.2  444.62
  4978.9  442.04  4988.9  440.18  5009.3  441.30  5028.9  439.91  5029.2  439.41
  5033.1  439.91  5040.6  441.43  5059.2  442.84  5064.4  442.12  5136.3  443.51
  5290.8  448.69  5313.4  450.16  5370.7  450.88  5436.7  452.93  6027.4  461.99
#Mann=6,-1,0
  3173.8    0.05       0  4918.6    0.12       0  4924.2     0.1       0
  5028.9    0.07       0  5033.1     0.1       0  5370.7    0.05       0
Bank Sta=5028.9,5033.1
Exp/Cntr=0.3,0.1

Type RM Length L Ch R = 1,24407,605,605,605
BEGIN DESCRIPTION:
South Fork Lacy Fork 1781
END DESCRIPTION:
XS GIS Cut Line= 3
      2741722.44      6856877.66      2742418.47      6858209.29
      2742971.06      6859432.28
#Sta/Elev= 30
  3498.2  461.38  3578.4  462.10  3628.2  461.19  3644.6  461.76  3755.0  460.96
  3784.1  461.88  3829.2  460.70  3964.5  460.74  4207.3  457.79  4303.1  455.45
  4415.9  454.87  4549.3  451.93  4709.5  447.36  4799.2  443.62  4894.4  439.55
  4895.0  439.05  4899.3  439.55  5013.6  439.77  5046.5  441.62  5087.7  440.66
  5151.7  441.54  5189.2  443.82  5226.5  444.07  5309.9  447.89  5342.1  447.68
  5385.8  449.19  5507.4  452.09  5837.4  455.12  6097.1  460.14  6342.8  463.21
#Mann=6,-1,0
  3498.2    0.05       0  4799.2    0.12       0  4894.4    0.07       0
  4899.3    0.12       0  5087.7     0.1       0  5385.8    0.05       0
Bank Sta=4894.4,4899.3
Exp/Cntr=0.3,0.1

Type RM Length L Ch R = 1,23802,870,870,870
BEGIN DESCRIPTION:
South Fork Lacy Fork 3426
END DESCRIPTION:
XS GIS Cut Line= 3
      2741225.14      6857369.47      2741892.68      6858458.27
      2742964.94      6859480.66
#Sta/Elev= 30
  3733.4  470.41  3800.9  469.09  3822.2  469.71  3887.7  467.57  4032.9  465.41
  4085.1  463.83  4201.1  462.93  4411.9  457.94  4549.3  455.71  4622.7  452.95
  4628.6  451.79  4644.0  451.84  4760.1  444.70  4833.4  441.77  4883.3  439.85
  5054.7  439.75  5055.3  439.25  5059.6  439.75  5149.3  440.04  5184.5  442.73
  5205.9  443.26  5242.3  441.76  5288.2  442.23  5693.7  454.55  5771.7  454.81
  5877.7  456.50  6061.7  456.47  6252.6  459.41  6280.9  460.44  6492.1  462.24
#Mann=7,-1,0
  3733.4    0.05       0  4833.4    0.12       0  4883.3    0.05       0
  5054.7    0.03       0  5059.6    0.05       0  5242.3    0.12       0
  5288.2    0.05       0
Bank Sta=5054.7,5059.6
Exp/Cntr=0.3,0.1

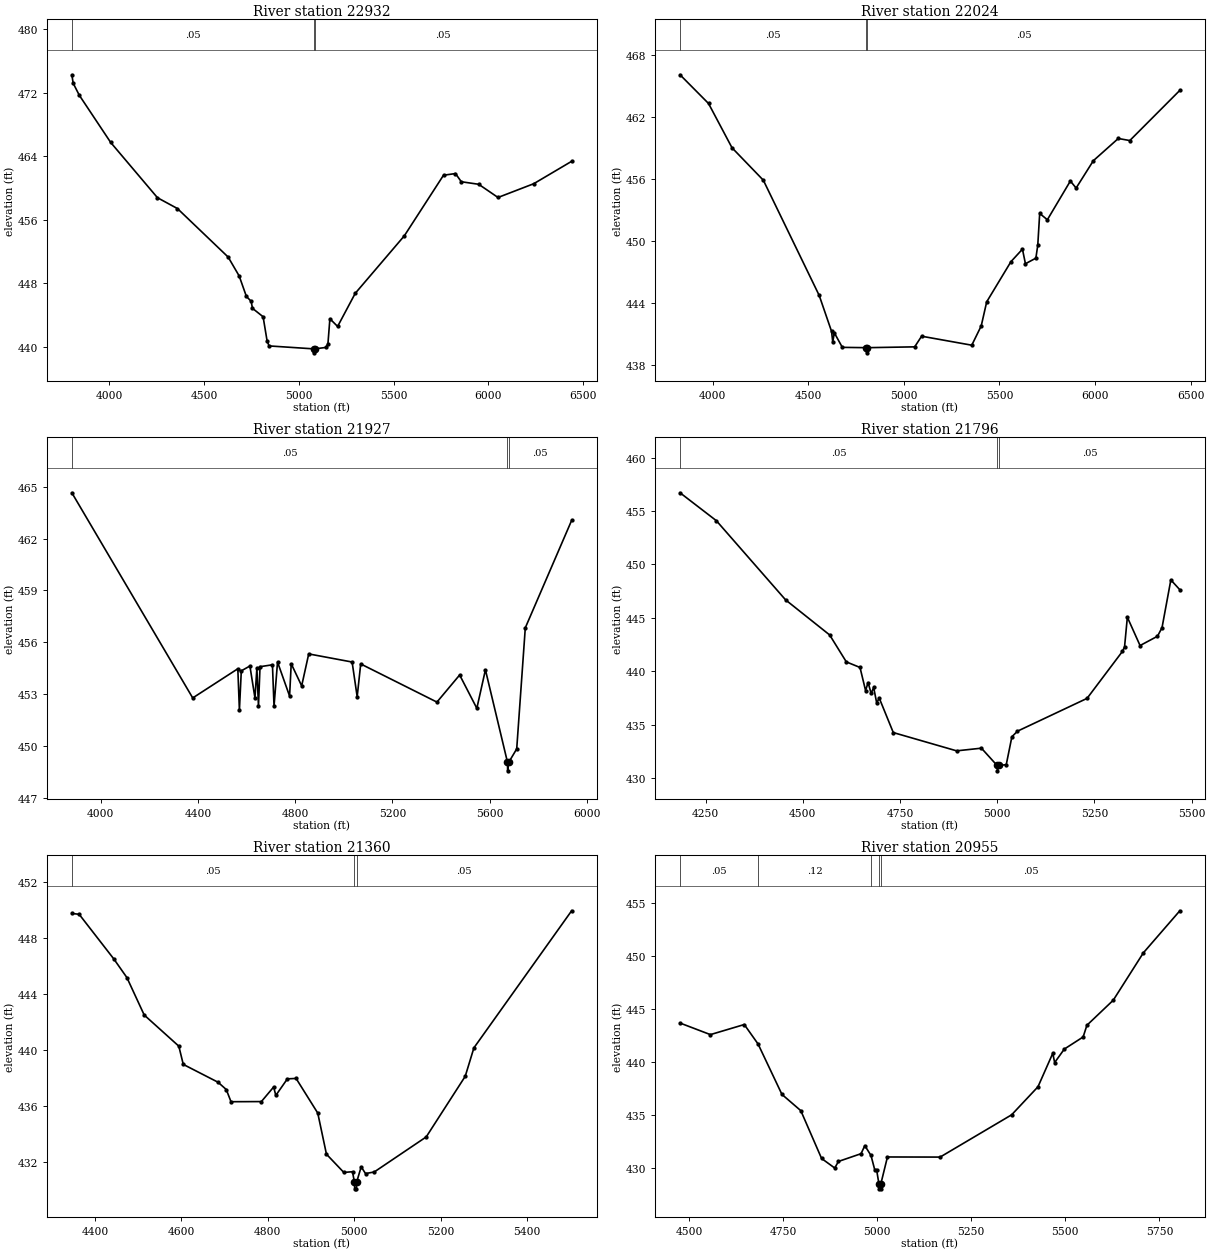
Type RM Length L Ch R = 1,22932,908,908,908
BEGIN DESCRIPTION:
South Fork Lacy Fork 1779
END DESCRIPTION:
XS GIS Cut Line= 3
      2740486.48      6858863.15      2741621.80      6859229.34
      2743036.95      6859504.18
#Sta/Elev= 30
  3803.9  474.24  3810.9  473.18  3843.0  471.67  4008.5  465.73  4255.2  458.77
  4360.3  457.41  4627.9  451.30  4686.0  448.92  4724.1  446.34  4749.0  445.74
  4756.1  444.85  4812.1  443.79  4833.1  440.75  4843.6  440.12  5078.3  439.75
  5078.9  439.25  5083.4  439.75  5143.7  439.93  5153.9  440.41  5164.1  443.54
  5204.8  442.57  5297.8  446.74  5556.3  453.97  5763.0  461.60  5826.2  461.81
  5856.8  460.78  5948.5  460.46  6050.3  458.80  6238.5  460.53  6438.4  463.35
#Mann=3,-1,0
  3803.9    0.05       0  5078.3    0.03       0  5083.4    0.05       0
Bank Sta=5078.3,5083.4
Exp/Cntr=0.3,0.1

Type RM Length L Ch R = 1,22024,97,97,97
BEGIN DESCRIPTION:
South Fork Lacy Fork 1778
END DESCRIPTION:
XS GIS Cut Line= 4
      2740518.28      6859379.13      2741456.74      6860086.58
      2741791.64      6860372.72      2742786.99      6860442.04
#Sta/Elev= 30
  3829.8  466.07  3978.8  463.29  4101.6  459.00  4265.3  455.86  4557.5  444.70
  4622.1  441.22  4628.4  440.19  4636.6  441.08  4678.5  439.67  4804.8  439.64
  4805.5  439.14  4810.0  439.64  5056.8  439.72  5093.0  440.75  5355.4  439.88
  5404.8  441.75  5433.4  444.08  5560.2  447.97  5620.3  449.18  5636.0  447.77
  5690.5  448.31  5700.5  449.57  5710.5  452.64  5750.6  452.03  5870.9  455.78
  5901.0  455.10  5991.2  457.75  6121.5  459.90  6181.7  459.70  6443.3  464.56
#Mann=3,-1,0
  3829.8    0.05       0  4804.8    0.03       0  4810.0    0.05       0
Bank Sta=4804.8,4810
Exp/Cntr=0.3,0.1

Type RM Length L Ch R = 1,21927,131,131,131
BEGIN DESCRIPTION:
South Fork Lacy Fork 1775
END DESCRIPTION:
XS GIS Cut Line= 4
      2740552.68      6859475.19      2741269.73      6860051.48
      2741424.76      6860170.68      2742170.46      6860743.34
#Sta/Elev= 30
  3881.6  464.65  4378.8  452.77  4564.3  454.46  4570.8  452.06  4578.6  454.34
  4614.0  454.62  4634.8  452.77  4642.7  454.50  4649.2  452.29  4655.6  454.58
  4706.7  454.69  4713.2  452.29  4727.6  454.85  4777.2  452.88  4783.9  454.75
  4826.9  453.47  4855.9  455.32  5034.4  454.85  5055.2  452.84  5069.7  454.74
  5383.3  452.53  5476.7  454.10  5547.4  452.17  5582.7  454.40  5673.4  449.05
  5674.1  448.55  5678.8  449.05  5711.4  449.82  5746.7  456.83  5937.3  463.05
#Mann=3,-1,0
  3881.6    0.05       0  5673.4    0.04       0  5678.8    0.05       0
Bank Sta=5673.4,5678.8
Exp/Cntr=0.3,0.1

Type RM Length L Ch R = 1,21796,436,436,436
BEGIN DESCRIPTION:
South Fork Lacy Fork 1777
END DESCRIPTION:
XS GIS Cut Line= 4
      2740795.04      6859779.72      2741417.67      6860300.15
      2741596.22      6860438.77      2741702.78      6860662.90
#Sta/Elev= 30
  4184.0  456.70  4277.4  454.09  4455.6  446.68  4568.9  443.40  4611.8  440.88
  4647.0  440.36  4661.3  438.20  4667.8  438.95  4675.6  437.93  4682.1  438.49
  4689.9  437.04  4696.4  437.50  4732.6  434.27  4895.5  432.56  4959.3  432.81
  4999.7  431.19  5000.4  430.69  5005.1  431.19  5023.2  431.27  5037.7  433.88
  5052.1  434.40  5231.1  437.47  5322.0  441.86  5327.5  442.28  5334.7  445.06
  5367.4  442.41  5412.2  443.28  5423.9  444.08  5446.6  448.55  5469.7  447.63
#Mann=3,-1,0
  4184.0    0.05       0  4999.7    0.04       0  5005.1    0.05       0
Bank Sta=4999.7,5005.1
Exp/Cntr=0.3,0.1

Type RM Length L Ch R = 1,21360,405,405,405
BEGIN DESCRIPTION:
South Fork Lacy Fork 1776
END DESCRIPTION:
XS GIS Cut Line= 3
      2740569.16      6860602.85      2741225.16      6860663.28
      2741721.37      6860705.74
#Sta/Elev= 30
  4346.7  449.73  4363.6  449.67  4444.0  446.48  4474.1  445.16  4514.2  442.49
  4594.3  440.27  4604.6  438.97  4685.0  437.70  4704.1  437.18  4715.1  436.31
  4785.4  436.32  4813.8  437.36  4818.8  436.76  4845.6  437.94  4865.7  437.97
  4915.9  435.50  4936.0  432.57  4976.2  431.27  4996.3  431.32  5000.6  430.60
  5001.4  430.10  5005.3  430.10  5006.1  430.60  5016.4  431.67  5026.4  431.19
  5046.5  431.30  5166.9  433.80  5257.2  438.12  5277.3  440.15  5503.5  449.92
#Mann=3,-1,0
  4346.7    0.05       0  5000.6    0.04       0  5006.1    0.05       0
Bank Sta=5000.6,5006.1
Exp/Cntr=0.3,0.1

Type RM Length L Ch R = 1,20955,458,458,458
BEGIN DESCRIPTION:
South Fork Lacy Fork 1773
END DESCRIPTION:
XS GIS Cut Line= 3
      2740405.42      6860932.17      2740923.46      6860909.88
      2741732.91      6860903.28
#Sta/Elev= 30
  4476.3  443.66  4557.0  442.57  4647.0  443.52  4683.6  441.69  4747.1  436.94
  4797.2  435.41  4852.4  430.91  4887.3  430.01  4897.3  430.63  4957.3  431.36
  4967.3  432.12  4983.7  431.19  4993.6  429.85  4998.6  429.85  5004.6  428.55
  5005.4  428.05  5009.3  428.05  5010.1  428.55  5027.4  431.05  5167.4  431.04
  5357.4  435.02  5427.4  437.66  5466.7  440.81  5471.7  439.94  5497.4  441.21
  5547.4  442.35  5557.4  443.45  5627.4  445.81  5707.4  450.27  5804.3  454.23
#Mann=5,-1,0
  4476.3    0.05       0  4683.6    0.12       0  4983.7    0.05       0
  5004.6    0.04       0  5010.1    0.05       0
Bank Sta=5004.6,5010.1
Exp/Cntr=0.3,0.1

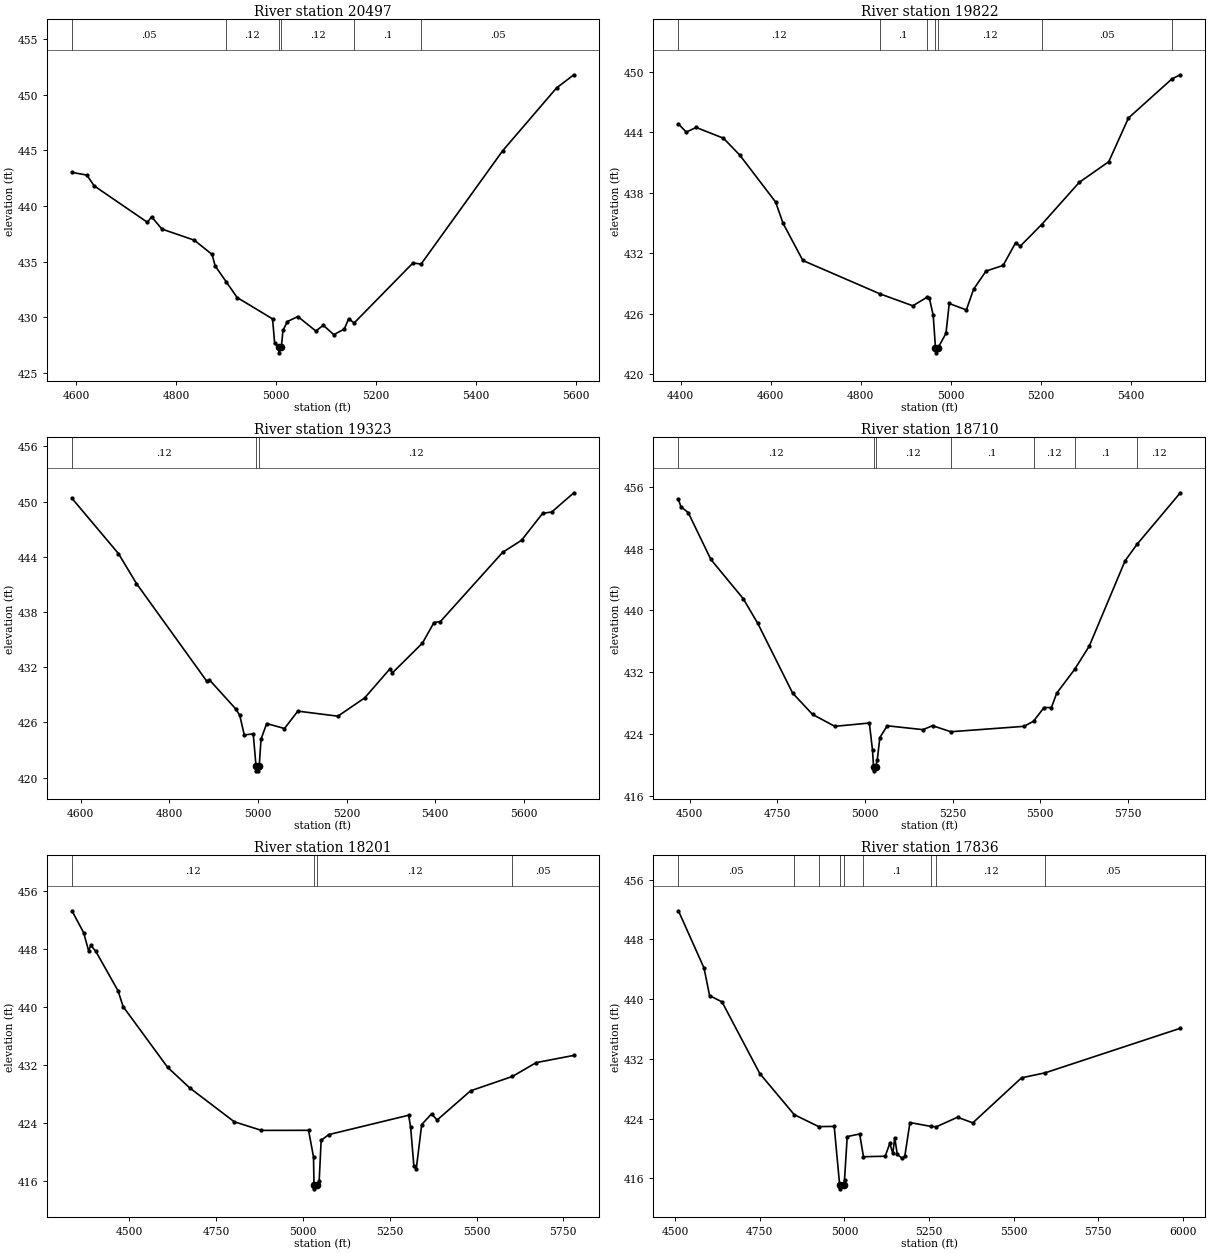
Type RM Length L Ch R = 1,20497,675,675,675
BEGIN DESCRIPTION:
South Fork Lacy Fork 1774
END DESCRIPTION:
XS GIS Cut Line= 3
      2740315.67      6860999.28      2740643.95      6861240.92
      2741137.75      6861576.74
#Sta/Elev= 30
  4591.9  443.02  4621.7  442.78  4636.4  441.81  4742.9  438.54  4751.3  439.03
  4772.1  437.93  4836.9  436.93  4872.4  435.65  4878.6  434.62  4900.9  433.18
  4922.6  431.78  4993.5  429.86  4997.7  427.68  5005.5  427.31  5006.4  426.81
  5011.1  427.31  5014.4  428.84  5023.2  429.62  5044.2  430.07  5080.2  428.77
  5095.1  429.29  5116.1  428.44  5137.1  428.95  5146.0  429.88  5156.8  429.49
  5274.7  434.89  5290.8  434.78  5454.3  444.97  5562.1  450.61  5596.7  451.79
#Mann=6,-1,0
  4591.9    0.05       0  4900.9    0.12       0  5005.5    0.07       0
  5011.1    0.12       0  5156.8     0.1       0  5290.8    0.05       0
Bank Sta=5005.5,5011.1
Exp/Cntr=0.3,0.1

Type RM Length L Ch R = 1,19822,499,499,499
BEGIN DESCRIPTION:
South Fork Lacy Fork 1772
END DESCRIPTION:
XS GIS Cut Line= 3
      2739785.58      6861527.86      2740311.20      6861804.48
      2740767.74      6862053.49
#Sta/Elev= 30
  4395.2  444.83  4412.7  444.03  4434.7  444.49  4495.2  443.42  4531.3  441.75
  4611.0  437.08  4627.4  434.98  4671.4  431.28  4842.4  427.97  4915.5  426.78
  4946.2  427.61  4952.3  427.52  4960.7  425.84  4965.8  422.61  4966.7  422.11
  4971.5  422.61  4989.1  424.05  4996.3  427.01  5034.3  426.37  5050.4  428.43
  5078.0  430.23  5115.9  430.79  5143.5  433.03  5153.9  432.70  5201.2  434.84
  5284.9  439.04  5350.4  441.09  5394.1  445.43  5490.6  449.31  5509.2  449.72
#Mann=7,-1,0
  4395.2    0.12       0  4842.4     0.1       0  4946.2    0.12       0
  4965.8    0.07       0  4971.5    0.12       0  5201.2    0.05       0
  5490.6    0.12       0
Bank Sta=4965.8,4971.5
Exp/Cntr=0.3,0.1

Type RM Length L Ch R = 1,19323,613,613,613
BEGIN DESCRIPTION:
South Fork Lacy Fork 1771
END DESCRIPTION:
XS GIS Cut Line= 3
      2739662.45      6862074.77      2740079.19      6862145.31
      2740785.85      6862218.44
#Sta/Elev= 30
  4580.1  450.35  4685.1  444.34  4725.7  441.09  4885.0  430.44  4890.1  430.64
  4950.4  427.43  4959.0  426.75  4969.1  424.63  4989.4  424.75  4995.7  421.23
  4996.6  420.73  5000.6  420.73  5001.5  421.23  5002.8  421.23  5007.0  424.17
  5019.7  425.87  5059.9  425.33  5090.0  427.22  5180.5  426.67  5240.8  428.65
  5298.5  431.84  5303.6  431.38  5371.5  434.62  5397.4  436.85  5411.8  436.95
  5552.5  444.48  5595.1  445.79  5643.0  448.73  5663.1  448.85  5713.2  450.95
#Mann=3,-1,0
  4580.1    0.12       0  4995.7    0.07       0  5001.5    0.12       0
Bank Sta=4995.7,5001.5
Exp/Cntr=0.3,0.1

Type RM Length L Ch R = 1,18710,509,509,509
BEGIN DESCRIPTION:
South Fork Lacy Fork 29
END DESCRIPTION:
XS GIS Cut Line= 3
      2739525.97      6862160.96      2739876.00      6862561.00
      2740625.97      6863060.98
#Sta/Elev= 30
  4467.5  454.41  4474.7  453.43  4495.5  452.68  4560.1  446.61  4652.2  441.54
  4693.9  438.33  4793.6  429.28  4850.5  426.51  4914.1  424.97  5012.6  425.40
  5021.6  421.88  5024.6  419.70  5025.6  419.20  5030.5  419.70  5035.1  420.56
  5042.6  423.52  5063.7  425.04  5165.8  424.54  5192.9  425.05  5245.4  424.27
  5454.3  424.97  5481.5  425.64  5511.3  427.41  5532.4  427.40  5547.4  429.26
  5598.6  432.35  5640.5  435.38  5742.7  446.43  5776.8  448.57  5900.4  455.25
#Mann=7,-1,0
  4467.5    0.12       0  5024.6    0.07       0  5030.5    0.12       0
  5245.4     0.1       0  5481.5    0.12       0  5598.6     0.1       0
  5776.8    0.12       0
Bank Sta=5024.6,5030.5
Exp/Cntr=0.3,0.1

Type RM Length L Ch R = 1,18201,365,365,365
BEGIN DESCRIPTION:
South Fork Lacy Fork 1619
END DESCRIPTION:
XS GIS Cut Line= 4
      2739088.69      6862161.35      2739512.85      6862690.98
      2739709.61      6863059.34      2739683.06      6863407.68
#Sta/Elev= 30
  4334.7  453.26  4368.3  450.25  4382.7  447.75  4389.1  448.49  4403.5  447.67
  4467.6  442.22  4482.0  440.07  4610.0  431.71  4674.0  428.86  4802.1  424.20
  4880.5  423.01  5016.1  423.02  5030.4  419.36  5031.8  415.46  5033.0  414.96
  5040.4  415.46  5046.7  416.02  5052.4  421.64  5074.3  422.43  5304.4  425.10
  5310.1  423.46  5319.4  418.14  5326.4  417.72  5342.0  423.82  5370.3  425.28
  5386.5  424.44  5482.7  428.46  5603.2  430.44  5671.9  432.35  5780.2  433.34
#Mann=4,-1,0
  4334.7    0.12       0  5031.8    0.07       0  5040.4    0.12       0
  5603.2    0.05       0
Bank Sta=5031.8,5040.4
Exp/Cntr=0.3,0.1

Type RM Length L Ch R = 1,17836,247,247,247
BEGIN DESCRIPTION:
South Fork Lacy Fork 1617
END DESCRIPTION:
XS GIS Cut Line= 4
      2738936.65      6862227.00      2739175.48      6862678.62
      2739406.46      6863151.70      2739436.12      6863597.17
#Sta/Elev= 30
  4509.2  451.84  4585.0  444.16  4601.3  440.48  4638.2  439.63  4749.7  430.04
  4851.6  424.53  4923.7  422.93  4969.8  422.95  4985.9  415.09  4987.6  414.59
  4997.7  415.09  5000.2  415.75  5008.2  421.59  5045.0  421.94  5056.3  418.89
  5120.6  418.96  5134.0  420.67  5143.1  419.36  5148.7  421.43  5156.3  419.20
  5171.2  418.66  5178.5  418.97  5193.7  423.47  5256.1  422.95  5271.4  422.90
  5334.4  424.18  5379.5  423.43  5523.5  429.46  5594.0  430.14  5993.0  436.10
#Mann=9,-1,0
  4509.2    0.05       0  4851.6     0.1       0  4923.7    0.05       0
  4985.9    0.03       0  4997.7    0.05       0  5056.3     0.1       0
  5256.1    0.05       0  5271.4    0.12       0  5594.0    0.05       0
Bank Sta=4985.9,4997.7
Exp/Cntr=0.3,0.1

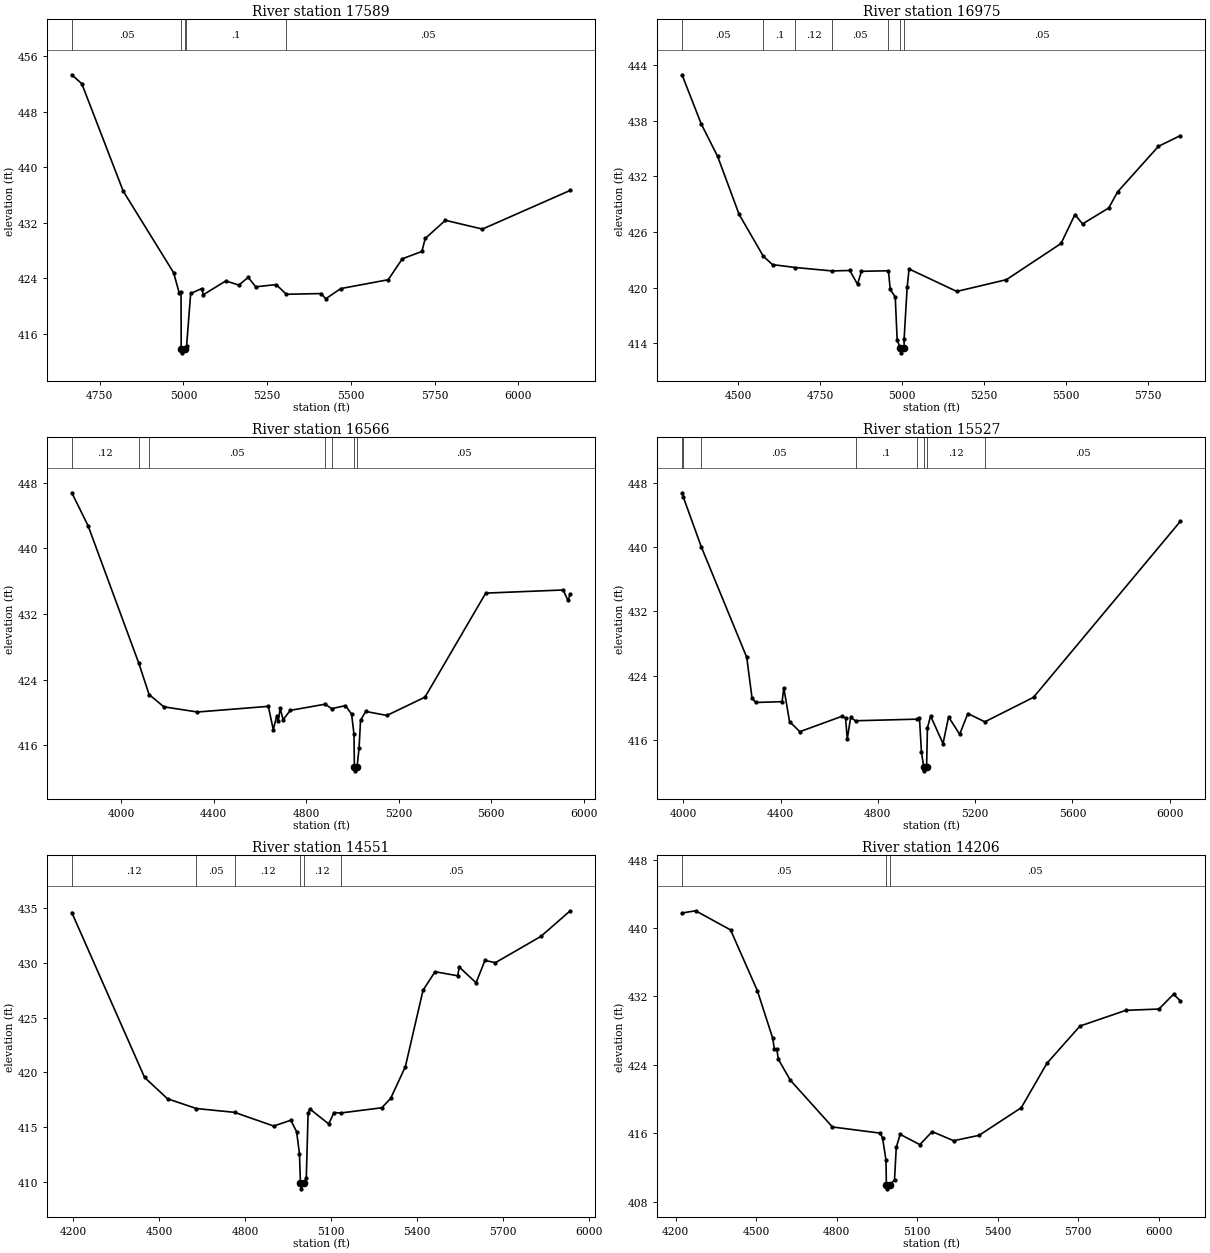
Type RM Length L Ch R = 1,17589,614,614,614
BEGIN DESCRIPTION:
South Fork Lacy Fork 1618
END DESCRIPTION:
XS GIS Cut Line= 3
      2738784.10      6862314.32      2739194.22      6863125.00
      2739246.56      6863702.11
#Sta/Elev= 30
  4666.8  453.28  4696.7  452.00  4820.3  436.56  4970.7  424.84  4987.3  421.97
  4993.0  422.11  4993.4  413.81  4995.0  413.31  5005.2  413.81  5006.7  413.99
  5009.6  414.33  5021.7  421.84  5054.2  422.54  5059.8  421.67  5126.7  423.65
  5165.6  423.05  5193.5  424.16  5215.8  422.80  5277.0  423.12  5307.3  421.73
  5410.7  421.83  5425.1  421.09  5470.0  422.55  5611.5  423.82  5653.5  426.83
  5711.9  427.88  5721.9  429.75  5782.2  432.36  5892.6  431.10  6154.8  436.66
#Mann=5,-1,0
  4666.8    0.05       0  4993.4    0.05       0  5005.2    0.05       0
  5006.7     0.1       0  5307.3    0.05       0
Bank Sta=4993.4,5005.2
Exp/Cntr=0.3,0.1

Type RM Length L Ch R = 1,16975,409,409,409
BEGIN DESCRIPTION:
South Fork Lacy Fork 1702
END DESCRIPTION:
XS GIS Cut Line= 4
      2738667.95      6862432.73      2738619.35      6862931.63
      2739150.49      6863767.61      2739169.71      6863791.41
#Sta/Elev= 30
  4328.0  442.95  4386.5  437.66  4436.8  434.14  4502.4  427.89  4576.2  423.39
  4604.3  422.48  4674.4  422.17  4786.2  421.80  4840.4  421.85  4863.9  420.36
  4875.9  421.76  4958.4  421.82  4963.8  419.80  4979.1  419.00  4985.0  414.38
  4994.3  413.47  4996.0  412.97  5006.1  413.47  5006.2  414.42  5015.5  420.03
  5021.4  422.01  5167.1  419.59  5318.7  420.86  5485.5  424.76  5527.9  427.88
  5551.2  426.87  5631.2  428.59  5658.3  430.33  5782.8  435.23  5850.3  436.40
#Mann=7,-1,0
  4328.0    0.05       0  4576.2     0.1       0  4674.4    0.12       0
  4786.2    0.05       0  4958.4    0.12       0  4994.3    0.04       0
  5006.1    0.05       0
Bank Sta=4994.3,5006.1
Exp/Cntr=0.3,0.1

Type RM Length L Ch R = 1,16566,1039,1039,1039
BEGIN DESCRIPTION:
South Fork Lacy Fork 1621
END DESCRIPTION:
XS GIS Cut Line= 3
      2737515.95      6862704.13      2738547.06      6863330.41
      2739138.64      6864071.81
#Sta/Elev= 30
  3786.9  446.75  3857.2  442.75  4076.8  425.99  4121.1  422.20  4184.8  420.70
  4330.4  420.07  4636.6  420.76  4658.0  417.92  4673.5  419.64  4679.3  418.95
  4687.9  420.51  4700.6  419.13  4731.6  420.27  4882.1  421.02  4910.7  420.48
  4970.0  420.85  4996.5  419.82  5006.9  417.37  5008.6  413.41  5010.2  412.91
  5020.4  413.41  5028.9  415.69  5035.3  419.07  5057.7  420.14  5149.0  419.65
  5313.9  421.88  5576.5  434.54  5911.2  434.92  5932.0  433.65  5941.8  434.43
#Mann=7,-1,0
  3786.9    0.12       0  4076.8     0.1       0  4121.1    0.05       0
  4882.1     0.1       0  4910.7    0.05       0  5008.6    0.04       0
  5020.4    0.05       0
Bank Sta=5008.6,5020.4
Exp/Cntr=0.3,0.1

Type RM Length L Ch R = 1,15527,976,976,976
BEGIN DESCRIPTION:
South Fork Lacy Fork 1620
END DESCRIPTION:
XS GIS Cut Line= 3
      2737359.88      6862938.52      2737904.84      6863791.39
      2738111.52      6864807.67
#Sta/Elev= 30
  3995.0  446.79  4000.3  446.25  4074.2  440.05  4261.0  426.29  4282.8  421.21
  4297.4  420.66  4406.5  420.76  4413.3  422.48  4437.0  418.28  4479.3  417.02
  4651.8  418.93  4667.1  418.74  4674.4  416.12  4688.2  418.79  4708.2  418.38
  4960.5  418.58  4971.0  418.78  4979.2  414.50  4988.5  412.64  4990.1  412.14
  5000.4  412.64  5003.9  417.51  5016.9  418.97  5067.9  415.54  5090.8  418.87
  5136.3  416.69  5170.0  419.28  5239.9  418.25  5439.9  421.30  6044.2  443.25
#Mann=8,-1,0
  3995.0     0.1       0  4000.3    0.12       0  4074.2    0.05       0
  4708.2     0.1       0  4960.5    0.12       0  4988.5    0.07       0
  5000.4    0.12       0  5239.9    0.05       0
Bank Sta=4988.5,5000.4
Exp/Cntr=0.3,0.1

Type RM Length L Ch R = 1,14551,345,345,345
BEGIN DESCRIPTION:
South Fork Lacy Fork 1615
END DESCRIPTION:
XS GIS Cut Line= 3
      2737184.69      6863207.13      2737157.95      6864024.77
      2737371.26      6864920.54
#Sta/Elev= 30
  4195.7  434.61  4449.7  419.54  4529.7  417.59  4630.2  416.70  4763.4  416.35
  4899.9  415.10  4960.0  415.63  4980.0  414.58  4990.0  412.57  4993.5  409.86
  4995.3  409.36  5006.5  409.86  5013.8  410.36  5020.2  416.30  5026.1  416.66
  5092.1  415.29  5110.4  416.33  5133.6  416.29  5277.2  416.77  5308.0  417.62
  5359.4  420.52  5421.1  427.51  5463.0  429.20  5542.1  428.83  5547.3  429.63
  5606.1  428.19  5637.0  430.23  5673.7  430.03  5832.3  432.43  5934.6  434.77
#Mann=6,-1,0
  4195.7    0.12       0  4630.2    0.05       0  4763.4    0.12       0
  4993.5    0.07       0  5006.5    0.12       0  5133.6    0.05       0
Bank Sta=4993.5,5006.5
Exp/Cntr=0.3,0.1

Type RM Length L Ch R = 1,14206,628,628,628
BEGIN DESCRIPTION:
South Fork Lacy Fork 1616
END DESCRIPTION:
XS GIS Cut Line= 3
      2736237.78      6863518.06      2736876.54      6863974.80
      2737204.64      6864995.71
#Sta/Elev= 30
  4224.3  441.77  4274.9  442.03  4405.1  439.79  4504.9  432.69  4562.4  427.10
  4568.5  425.80  4577.1  425.89  4583.3  424.65  4627.5  422.22  4784.8  416.73
  4963.0  416.01  4971.6  415.44  4984.3  412.88  4985.9  409.99  4987.7  409.49
  4999.0  409.99  5016.1  410.52  5022.7  414.33  5037.1  415.87  5110.6  414.66
  5156.4  416.19  5236.6  415.12  5331.2  415.75  5488.7  418.99  5584.1  424.18
  5707.3  428.54  5878.3  430.38  6001.4  430.53  6055.9  432.26  6081.9  431.47
#Mann=3,-1,0
  4224.3    0.05       0  4985.9    0.04       0  4999.0    0.05       0
Bank Sta=4985.9,4999
Exp/Cntr=0.3,0.1

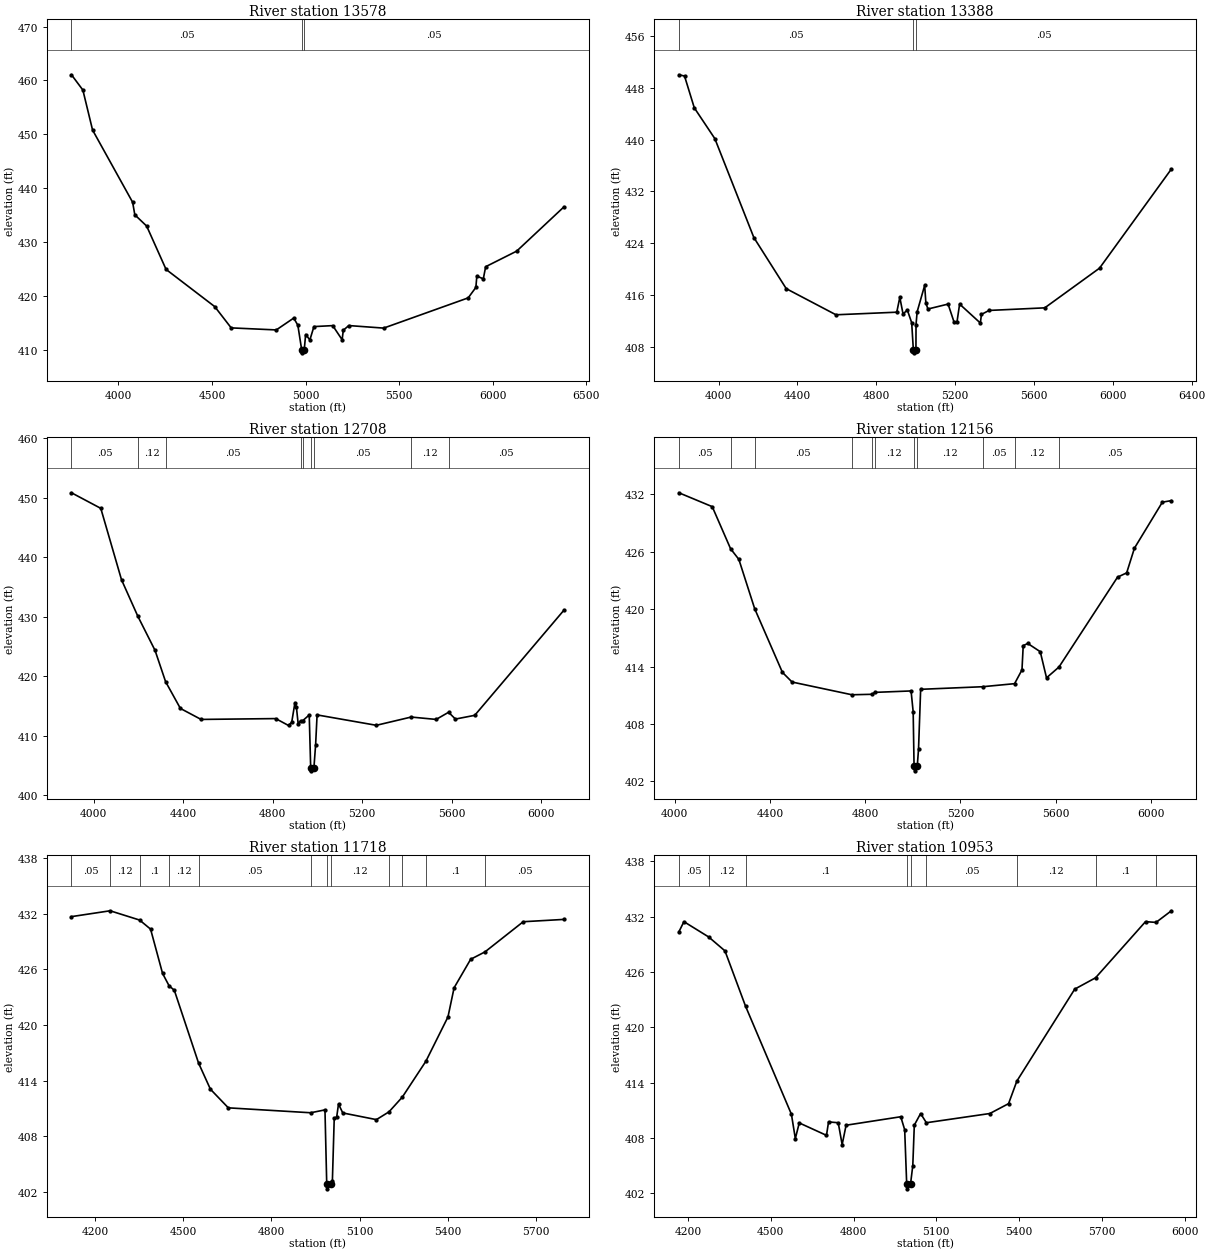
Type RM Length L Ch R = 1,13578,190,190,190
BEGIN DESCRIPTION:
South Fork Lacy Fork 1614
END DESCRIPTION:
XS GIS Cut Line= 4
      2735357.02      6863670.37      2736203.14      6864049.75
      2736697.08      6864732.53      2736923.23      6865564.85
#Sta/Elev= 30
  3748.8  461.05  3809.7  458.22  3861.5  450.80  4075.7  437.40  4087.4  435.07
  4150.7  432.98  4254.4  424.94  4514.8  418.03  4602.5  414.09  4843.6  413.71
  4936.8  415.91  4958.9  414.58  4979.6  409.96  4981.5  409.46  4992.8  409.96
  5000.6  412.86  5023.2  411.86  5044.8  414.33  5145.3  414.51  5195.6  411.89
  5201.8  413.65  5231.2  414.52  5417.6  414.05  5869.5  419.66  5910.5  421.60
  5915.6  423.70  5950.3  423.19  5962.8  425.44  6128.6  428.33  6381.3  436.54
#Mann=3,-1,0
  3748.8    0.05       0  4979.6    0.05       0  4992.8    0.05       0
Bank Sta=4979.6,4992.8
Exp/Cntr=0.3,0.1

Type RM Length L Ch R = 1,13388,680,680,680
BEGIN DESCRIPTION:
South Fork Lacy Fork 1613
END DESCRIPTION:
XS GIS Cut Line= 4
      2735190.80      6863869.91      2736270.83      6864445.33
      2736653.29      6865186.08      2736723.72      6865620.70
#Sta/Elev= 30
  3799.1  450.00  3827.6  449.81  3877.2  444.90  3981.4  440.15  4179.1  424.90
  4343.5  417.01  4595.7  412.98  4904.1  413.38  4919.5  415.67  4935.8  413.12
  4957.8  413.70  4979.7  411.76  4988.1  407.61  4990.0  407.11  5001.3  407.61
  5001.7  411.45  5007.4  413.44  5045.6  417.52  5051.7  414.79  5062.1  413.87
  5164.3  414.63  5195.0  411.82  5209.3  411.83  5222.8  414.63  5327.9  411.71
  5333.6  413.04  5372.2  413.65  5654.6  414.05  5932.4  420.17  6296.8  435.46
#Mann=3,-1,0
  3799.1    0.05       0  4988.1    0.05       0  5001.3    0.05       0
Bank Sta=4988.1,5001.3
Exp/Cntr=0.3,0.1

Type RM Length L Ch R = 1,12708,552,552,552
BEGIN DESCRIPTION:
South Fork Lacy Fork 1612
END DESCRIPTION:
XS GIS Cut Line= 3
      2735069.01      6864053.19      2735772.03      6864896.76
      2736670.78      6865532.87
#Sta/Elev= 30
  3901.3  450.85  4032.2  448.23  4124.7  436.22  4197.7  430.07  4274.4  424.34
  4321.6  419.07  4387.6  414.57  4480.0  412.72  4813.3  412.86  4870.5  411.70
  4884.9  412.25  4899.2  415.55  4905.7  414.82  4913.5  412.02  4924.1  412.49
  4933.7  412.50  4963.0  413.47  4969.5  404.58  4970.7  404.57  4972.6  404.07
  4983.9  404.57  4991.6  408.49  4998.1  413.48  5262.7  411.73  5418.2  413.12
  5529.8  412.72  5585.2  413.92  5616.0  412.78  5702.1  413.41  6100.5  431.10
#Mann=9,-1,0
  3901.3    0.05       0  4197.7    0.12       0  4321.6    0.05       0
  4924.1    0.12       0  4933.7    0.05       0  4970.7    0.04       0
  4983.9    0.05       0  5418.2    0.12       0  5585.2    0.05       0
Bank Sta=4970.7,4983.9
Exp/Cntr=0.3,0.1

Type RM Length L Ch R = 1,12156,438,438,438
BEGIN DESCRIPTION:
South Fork Lacy Fork 1611
END DESCRIPTION:
XS GIS Cut Line= 3
      2734658.28      6865392.93      2735617.62      6865217.82
      2736662.08      6865540.98
#Sta/Elev= 30
  4017.5  432.17  4157.5  430.72  4234.6  426.32  4269.3  425.21  4335.7  420.06
  4452.3  413.40  4492.9  412.39  4744.3  411.06  4828.6  411.11  4840.1  411.31
  4992.7  411.46  5001.5  409.27  5005.2  403.61  5007.1  403.11  5018.7  403.61
  5024.0  405.38  5032.9  411.63  5292.8  411.90  5427.4  412.22  5458.5  413.66
  5463.7  416.20  5483.0  416.42  5535.3  415.56  5561.6  412.83  5613.9  413.96
  5859.8  423.35  5898.2  423.80  5930.8  426.38  6048.2  431.19  6086.0  431.35
#Mann=11,-1,0
  4017.5    0.05       0  4234.6    0.12       0  4335.7    0.05       0
  4744.3    0.12       0  4828.6    0.05       0  4840.1    0.12       0
  5005.2    0.07       0  5018.7    0.12       0  5292.8    0.05       0
  5427.4    0.12       0  5613.9    0.05       0
Bank Sta=5005.2,5018.7
Exp/Cntr=0.3,0.1

Type RM Length L Ch R = 1,11718,765,765,765
BEGIN DESCRIPTION:
South Fork Lacy Fork 1610
END DESCRIPTION:
XS GIS Cut Line= 3
      2734641.49      6865422.97      2735502.65      6865578.77
      2735986.69      6866213.65
#Sta/Elev= 30
  4120.6  431.68  4251.9  432.31  4352.1  431.31  4389.4  430.33  4430.1  425.56
  4452.2  424.23  4470.1  423.74  4552.4  415.90  4592.7  413.08  4653.6  411.07
  4933.5  410.54  4982.0  410.85  4988.0  402.84  4990.0  402.34  5001.8  402.84
  5007.2  403.18  5013.5  409.97  5021.7  410.05  5028.0  411.48  5042.5  410.52
  5156.8  409.80  5199.6  410.64  5244.9  412.23  5324.9  416.09  5400.0  420.87
  5420.8  424.01  5477.0  427.08  5525.8  427.88  5655.7  431.13  5794.1  431.38
#Mann=12,-1,0
  4120.6    0.05       0  4251.9    0.12       0  4352.1     0.1       0
  4452.2    0.12       0  4552.4    0.05       0  4933.5    0.12       0
  4988.0    0.07       0  5001.8    0.12       0  5199.6     0.1       0
  5244.9    0.12       0  5324.9     0.1       0  5525.8    0.05       0
Bank Sta=4988,5001.8
Exp/Cntr=0.3,0.1

Type RM Length L Ch R = 1,10953,1016,1016,1016
BEGIN DESCRIPTION:
South Fork Lacy Fork 1567
END DESCRIPTION:
XS GIS Cut Line= 3
      2734570.25      6865440.95      2735126.35      6866067.25
      2735528.77      6866925.32
#Sta/Elev= 30
  4166.7  430.36  4184.9  431.46  4274.6  429.80  4333.7  428.29  4408.3  422.29
  4574.6  410.57  4588.8  407.93  4603.0  409.63  4701.7  408.28  4709.2  409.74
  4744.3  409.65  4758.5  407.28  4772.8  409.38  4971.0  410.30  4985.2  408.89
  4992.5  402.98  4994.4  402.48  5006.3  402.98  5014.6  405.01  5020.1  409.39
  5042.9  410.65  5063.8  409.65  5293.9  410.65  5361.8  411.72  5391.9  414.17
  5601.6  424.14  5677.1  425.37  5858.2  431.46  5896.4  431.38  5952.0  432.64
#Mann=9,-1,0
  4166.7    0.05       0  4274.6    0.12       0  4408.3     0.1       0
  4992.5    0.07       0  5006.3     0.1       0  5063.8    0.05       0
  5391.9    0.12       0  5677.1     0.1       0  5896.4    0.05       0
Bank Sta=4992.5,5006.3
Exp/Cntr=0.3,0.1