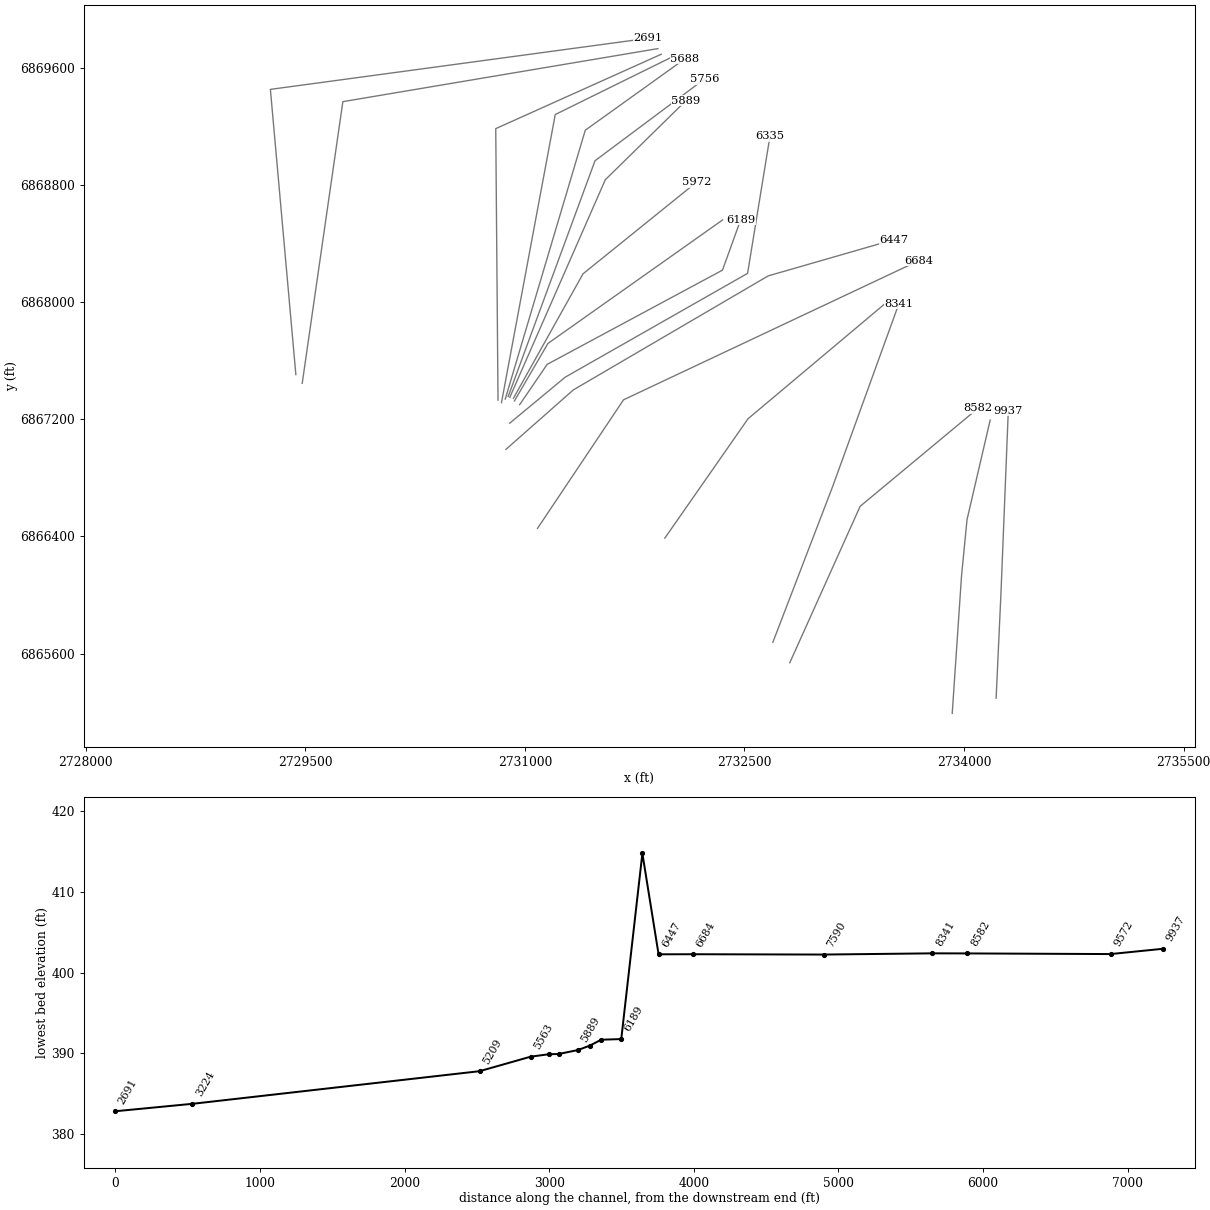
HEC-RAS study South Fork Lacy Fork.prj: South Fork Lacy Fork Base Level Engineering

--- South Fork Lacy Fork.g01 (geometry) --- (continued)

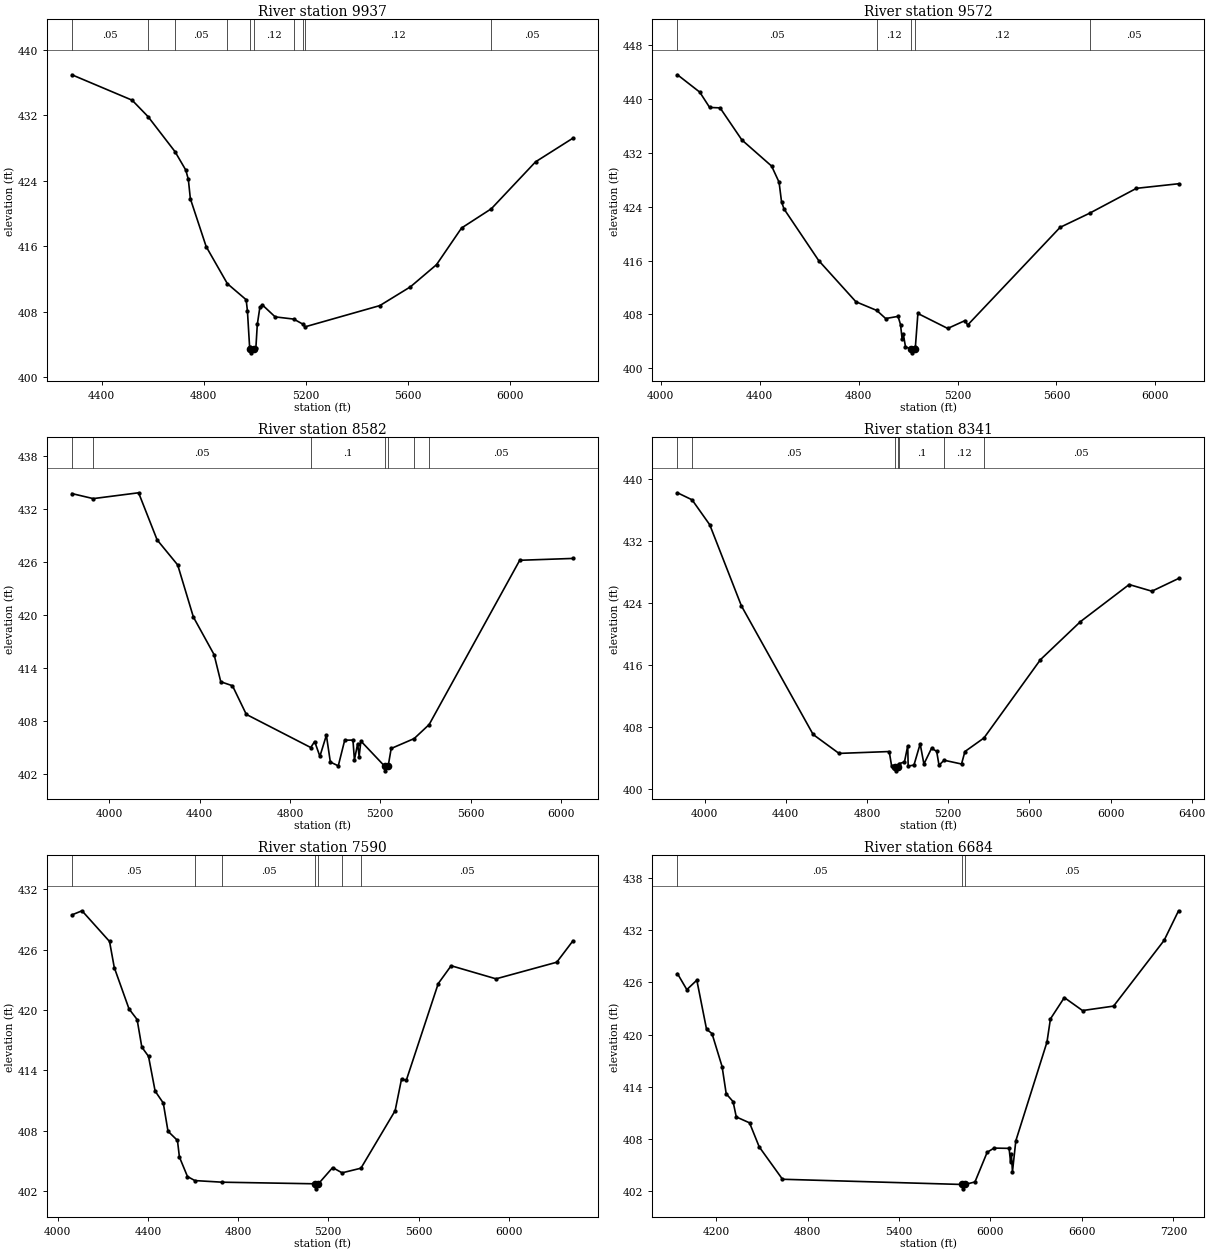
Type RM Length L Ch R = 1,9937,365,365,365
BEGIN DESCRIPTION:
South Fork Lacy Fork 1566
END DESCRIPTION:
XS GIS Cut Line= 3
      2734219.50      6865295.12      2734252.69      6866015.41
      2734302.59      6867257.55
#Sta/Elev= 30
  4283.3  436.98  4519.4  433.87  4581.8  431.86  4687.6  427.57  4729.7  425.32
  4739.7  424.18  4747.6  421.82  4809.7  415.95  4892.7  411.42  4966.3  409.46
  4971.3  408.10  4979.9  403.65  4983.0  403.46  4985.0  402.96  4996.8  403.46
  5004.4  403.53  5010.0  406.43  5020.0  408.51  5030.0  408.82  5080.0  407.36
  5152.7  407.09  5187.5  406.49  5196.9  406.14  5490.3  408.74  5610.4  411.04
  5712.6  413.75  5810.6  418.23  5927.5  420.59  6100.8  426.33  6247.5  429.23
#Mann=10,-1,0
  4283.3    0.05       0  4581.8    0.12       0  4687.6    0.05       0
  4892.7    0.12       0  4983.0    0.04       0  4996.8    0.12       0
  5152.7    0.12       0  5187.5    0.05       0  5196.9    0.12       0
  5927.5    0.05       0
Bank Sta=4983,4996.8
Exp/Cntr=0.3,0.1

Type RM Length L Ch R = 1,9572,990,990,990
BEGIN DESCRIPTION:
South Fork Lacy Fork 1565
END DESCRIPTION:
XS GIS Cut Line= 4
      2733919.56      6865191.16      2733982.89      6866126.79
      2734020.46      6866513.78      2734178.89      6867195.02
#Sta/Elev= 30
  4067.7  443.56  4157.7  440.99  4197.8  438.71  4240.0  438.65  4328.1  433.89
  4448.4  430.01  4478.5  427.62  4488.5  424.71  4498.5  423.65  4638.8  415.99
  4789.2  409.88  4873.6  408.59  4909.5  407.39  4959.6  407.71  4969.6  406.49
  4976.0  404.35  4981.0  405.04  4989.6  403.22  5012.6  402.80  5014.6  402.30
  5026.8  402.80  5029.8  403.23  5039.8  408.14  5160.4  405.92  5230.7  407.09
  5240.8  406.42  5614.8  420.92  5733.7  423.01  5923.3  426.71  6093.7  427.39
#Mann=5,-1,0
  4067.7    0.05       0  4873.6    0.12       0  5012.6    0.07       0
  5026.8    0.12       0  5733.7    0.05       0
Bank Sta=5012.6,5026.8
Exp/Cntr=0.3,0.1

Type RM Length L Ch R = 1,8582,241,241,241
BEGIN DESCRIPTION:
South Fork Lacy Fork 1564
END DESCRIPTION:
XS GIS Cut Line= 3
      2732809.81      6865536.96      2733290.47      6866605.73
      2734094.95      6867274.60
#Sta/Elev= 30
  3834.9  433.76  3929.2  433.19  4130.1  433.85  4212.1  428.52  4303.2  425.68
  4372.6  419.79  4464.3  415.53  4493.9  412.46  4545.7  412.01  4606.9  408.77
  4892.1  405.02  4909.5  405.70  4932.6  404.02  4961.3  406.41  4978.9  403.38
  5014.0  402.94  5042.5  405.85  5079.0  405.86  5085.5  403.62  5099.8  405.46
  5106.3  404.00  5114.1  405.75  5220.2  402.88  5222.2  402.38  5234.6  402.88
  5248.2  404.91  5349.9  406.03  5416.3  407.62  5817.2  426.21  6053.0  426.42
#Mann=7,-1,0
  3834.9    0.12       0  3929.2    0.05       0  4892.1     0.1       0
  5220.2    0.07       0  5234.6     0.1       0  5349.9    0.12       0
  5416.3    0.05       0
Bank Sta=5220.2,5234.6
Exp/Cntr=0.3,0.1

Type RM Length L Ch R = 1,8341,751,751,751
BEGIN DESCRIPTION:
South Fork Lacy Fork 1563
END DESCRIPTION:
XS GIS Cut Line= 3
      2732694.20      6865676.93      2733102.34      6866739.83
      2733555.37      6867990.65
#Sta/Elev= 30
  3866.3  438.27  3938.3  437.36  4025.4  434.14  4181.3  423.68  4534.8  407.08
  4662.2  404.64  4909.7  404.88  4921.6  402.99  4939.1  402.89  4941.1  402.39
  4953.5  402.89  4956.1  403.30  4984.7  403.53  5000.9  405.63  5003.0  403.01
  5031.5  403.13  5062.1  405.87  5080.6  403.27  5118.1  405.30  5143.4  404.91
  5155.0  403.11  5179.9  403.76  5265.9  403.27  5282.6  404.88  5376.4  406.63
  5654.9  416.74  5852.1  421.65  6091.9  426.43  6203.8  425.57  6335.2  427.21
#Mann=7,-1,0
  3866.3    0.12       0  3938.3    0.05       0  4939.1    0.07       0
  4953.5    0.05       0  4956.1     0.1       0  5179.9    0.12       0
  5376.4    0.05       0
Bank Sta=4939.1,4953.5
Exp/Cntr=0.3,0.1

Type RM Length L Ch R = 1,7590,906,906,906
BEGIN DESCRIPTION:
South Fork Lacy Fork 1562
END DESCRIPTION:
XS GIS Cut Line= 3
      2731956.03      6866388.32      2732524.78      6867204.17
      2733464.61      6867993.59
#Sta/Elev= 30
  4063.1  429.45  4107.9  429.86  4230.0  426.81  4251.0  424.22  4316.4  420.11
  4352.2  419.06  4373.1  416.32  4402.8  415.40  4432.1  411.95  4468.3  410.76
  4489.2  407.96  4531.1  407.05  4539.8  405.40  4575.6  403.46  4608.5  403.06
  4729.8  402.90  5141.7  402.74  5143.7  402.24  5156.2  402.74  5219.2  404.35
  5261.1  403.83  5344.7  404.29  5496.3  410.00  5524.9  413.17  5545.7  413.01
  5687.5  422.63  5744.7  424.40  5943.7  423.10  6213.0  424.75  6285.0  426.88
#Mann=7,-1,0
  4063.1    0.05       0  4608.5    0.12       0  4729.8    0.05       0
  5141.7    0.03       0  5156.2    0.05       0  5261.1    0.12       0
  5344.7    0.05       0
Bank Sta=5141.7,5156.2
Exp/Cntr=0.3,0.1

Type RM Length L Ch R = 1,6684,237,237,237
BEGIN DESCRIPTION:
South Fork Lacy Fork 1561
END DESCRIPTION:
XS GIS Cut Line= 3
      2731086.50      6866455.42      2731674.16      6867333.45
      2733691.45      6868284.09
#Sta/Elev= 30
  3947.1  427.00  4008.5  425.16  4074.1  426.25  4137.7  420.62  4173.7  420.11
  4239.7  416.33  4266.8  413.20  4311.8  412.30  4332.8  410.54  4419.9  409.86
  4483.3  407.10  4636.0  403.38  5816.4  402.78  5818.4  402.28  5831.1  402.78
  5898.3  403.07  5978.5  406.48  6023.3  406.96  6122.2  406.93  6131.7  405.40
  6137.2  406.27  6144.3  404.24  6166.4  407.80  6370.6  419.13  6393.4  421.80
  6484.5  424.25  6603.9  422.76  6807.6  423.27  7139.0  430.82  7233.7  434.22
#Mann=3,-1,0
  3947.1    0.05       0  5816.4    0.03       0  5831.1    0.05       0
Bank Sta=5816.4,5831.1
Exp/Cntr=0.3,0.1

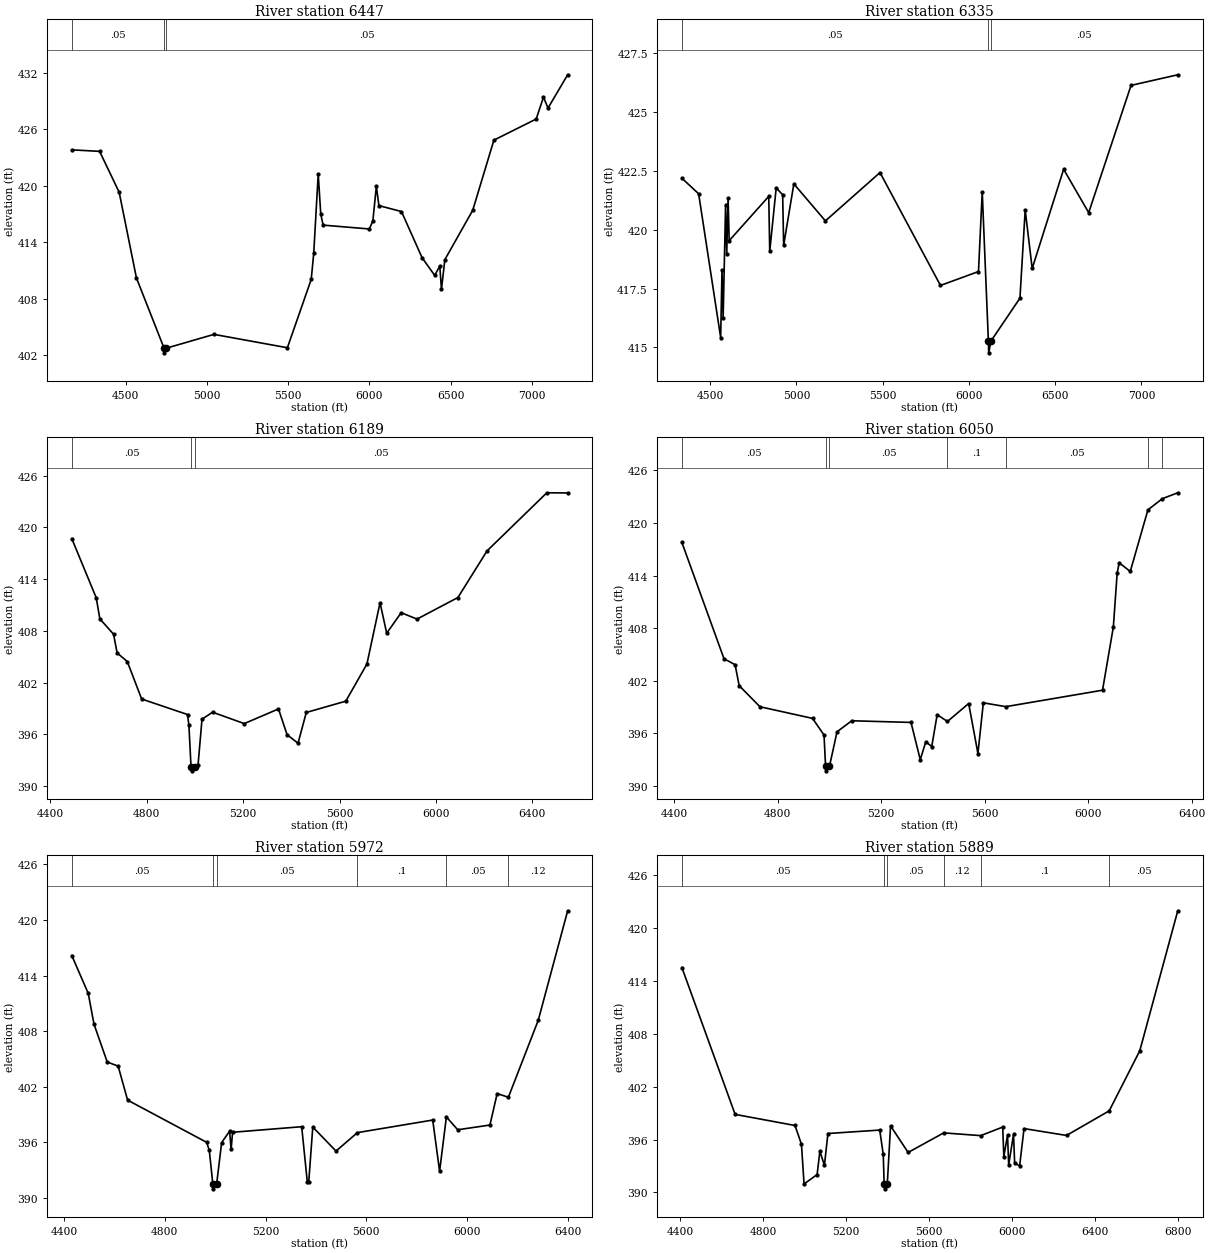
Type RM Length L Ch R = 1,6447,112,112,112
BEGIN DESCRIPTION:
South Fork Lacy Fork 1560
END DESCRIPTION:
XS GIS Cut Line= 4
      2730870.47      6866994.69      2731331.17      6867401.16
      2732662.48      6868179.99      2733522.22      6868427.78
#Sta/Elev= 30
  4168.5  423.82  4339.7  423.66  4460.1  419.32  4566.4  410.22  4736.3  402.77
  4738.3  402.27  4751.2  402.77  5043.4  404.23  5495.2  402.81  5642.0  410.07
  5657.4  412.84  5685.0  421.25  5700.7  416.98  5715.3  415.83  5999.8  415.42
  6021.3  416.29  6042.8  419.94  6058.5  417.90  6197.3  417.27  6324.4  412.36
  6401.8  410.49  6433.0  411.48  6443.4  409.02  6464.2  412.16  6635.9  417.41
  6766.0  424.85  7026.2  427.09  7071.1  429.41  7099.1  428.26  7220.0  431.79
#Mann=3,-1,0
  4168.5    0.05       0  4736.3    0.03       0  4751.2    0.05       0
Bank Sta=4736.3,4751.2
Exp/Cntr=0.3,0.1

Type RM Length L Ch R = 1,6335,146,146,146
BEGIN DESCRIPTION:
South Fork Lacy Fork 1550
END DESCRIPTION:
XS GIS Cut Line= 4
      2730896.48      6867173.66      2731275.91      6867488.18
      2732521.54      6868197.27      2732674.51      6869134.20
#Sta/Elev= 30
  4335.4  422.18  4432.6  421.52  4560.3  415.42  4568.1  418.29  4574.6  416.24
  4588.9  421.06  4595.4  418.95  4603.3  421.34  4609.7  419.53  4839.1  421.41
  4844.8  419.08  4882.3  421.77  4919.8  421.48  4925.5  419.33  4984.6  421.94
  5167.6  420.37  5484.2  422.42  5834.9  417.63  6055.3  418.22  6077.0  421.60
  6112.7  415.27  6114.7  414.77  6127.6  415.27  6295.7  417.09  6326.1  420.83
  6366.7  418.35  6549.0  422.56  6694.3  420.72  6940.0  426.12  7210.9  426.57
#Mann=3,-1,0
  4335.4    0.05       0  6112.7    0.04       0  6127.6    0.05       0
Bank Sta=6112.7,6127.6
Exp/Cntr=0.3,0.1

Type RM Length L Ch R = 1,6189,139,139,139
BEGIN DESCRIPTION:
South Fork Lacy Fork 1551
END DESCRIPTION:
XS GIS Cut Line= 4
      2730964.74      6867300.76      2731152.03      6867575.31
      2732350.02      6868219.20      2732474.01      6868562.37
#Sta/Elev= 30
  4489.0  418.71  4590.5  411.84  4605.4  409.40  4662.3  407.62  4677.2  405.44
  4719.3  404.45  4778.9  400.10  4969.2  398.30  4974.9  397.06  4983.7  392.27
  4985.7  391.77  4998.6  392.27  5013.0  392.50  5029.3  397.76  5073.1  398.57
  5204.6  397.25  5346.6  398.95  5382.1  395.97  5427.6  394.97  5461.9  398.54
  5625.8  399.85  5713.5  404.16  5767.9  411.27  5795.5  407.73  5855.6  410.11
  5921.3  409.37  6090.9  411.87  6211.8  417.28  6459.8  424.02  6546.3  424.00
#Mann=3,-1,0
  4489.0    0.05       0  4983.7    0.04       0  4998.6    0.05       0
Bank Sta=4983.7,4998.6
Exp/Cntr=0.3,0.1

Type RM Length L Ch R = 1,6050,78,78,78
BEGIN DESCRIPTION:
South Fork Lacy Fork 1552
END DESCRIPTION:
XS GIS Cut Line= 3
      2730928.92      6867325.90      2731157.46      6867718.31
      2732350.75      6868562.12
#Sta/Elev= 30
  4430.6  417.78  4593.2  404.50  4636.2  403.81  4651.9  401.42  4732.2  399.01
  4935.4  397.68  4979.7  395.78  4985.7  392.19  4987.7  391.69  5000.6  392.19
  5029.9  396.15  5086.8  397.41  5315.7  397.22  5351.4  392.97  5372.8  395.01
  5395.8  394.47  5416.7  398.10  5456.6  397.33  5538.5  399.38  5574.2  393.67
  5595.1  399.46  5682.0  399.02  6055.5  400.90  6097.3  408.12  6112.1  414.29
  6119.9  415.46  6162.6  414.46  6230.9  421.50  6286.8  422.78  6346.2  423.45
#Mann=7,-1,0
  4430.6    0.05       0  4985.7    0.04       0  5000.6    0.05       0
  5456.6     0.1       0  5682.0    0.05       0  6230.9    0.12       0
  6286.8    0.05       0
Bank Sta=4985.7,5000.6
Exp/Cntr=0.3,0.1

Type RM Length L Ch R = 1,5972,83,83,83
BEGIN DESCRIPTION:
South Fork Lacy Fork 1553
END DESCRIPTION:
XS GIS Cut Line= 3
      2730921.88      6867343.90      2731397.26      6868194.14
      2732171.94      6868819.49
#Sta/Elev= 30
  4430.4  416.16  4495.8  412.07  4518.7  408.74  4571.2  404.66  4614.6  404.21
  4652.2  400.54  4966.3  395.98  4976.6  395.12  4990.8  391.46  4992.8  390.96
  5005.7  391.46  5025.7  395.96  5057.2  397.18  5063.4  395.23  5069.1  397.07
  5343.6  397.67  5366.0  391.68  5371.7  391.74  5387.7  397.63  5480.0  395.04
  5564.8  397.03  5864.1  398.39  5891.4  392.86  5918.4  398.73  5963.3  397.34
  6091.3  397.85  6120.0  401.25  6164.6  400.85  6283.2  409.16  6400.1  420.99
#Mann=6,-1,0
  4430.4    0.05       0  4990.8    0.04       0  5005.7    0.05       0
  5564.8     0.1       0  5918.4    0.05       0  6164.6    0.12       0
Bank Sta=4990.8,5005.7
Exp/Cntr=0.3,0.1

Type RM Length L Ch R = 1,5889,133,133,133
BEGIN DESCRIPTION:
South Fork Lacy Fork 1554
END DESCRIPTION:
XS GIS Cut Line= 3
      2730897.49      6867351.11      2731549.45      6868836.75
      2732099.82      6869376.55
#Sta/Elev= 30
  4406.8  415.53  4663.8  398.86  4952.7  397.60  4983.9  395.47  4996.4  390.96
  5059.5  392.03  5072.8  394.68  5094.7  393.08  5111.7  396.69  5361.7  397.08
  5378.6  394.32  5383.1  390.91  5385.1  390.41  5398.0  390.91  5413.9  397.56
  5498.7  394.54  5670.3  396.76  5849.0  396.45  5955.2  397.42  5960.6  394.06
  5978.5  396.51  5984.0  393.13  6007.4  396.59  6012.8  393.32  6036.9  393.02
  6058.0  397.25  6263.1  396.47  6469.1  399.26  6616.7  406.08  6800.1  421.97
#Mann=6,-1,0
  4406.8    0.05       0  5383.1    0.04       0  5398.0    0.05       0
  5670.3    0.12       0  5849.0     0.1       0  6469.1    0.05       0
Bank Sta=5383.1,5398
Exp/Cntr=0.3,0.1

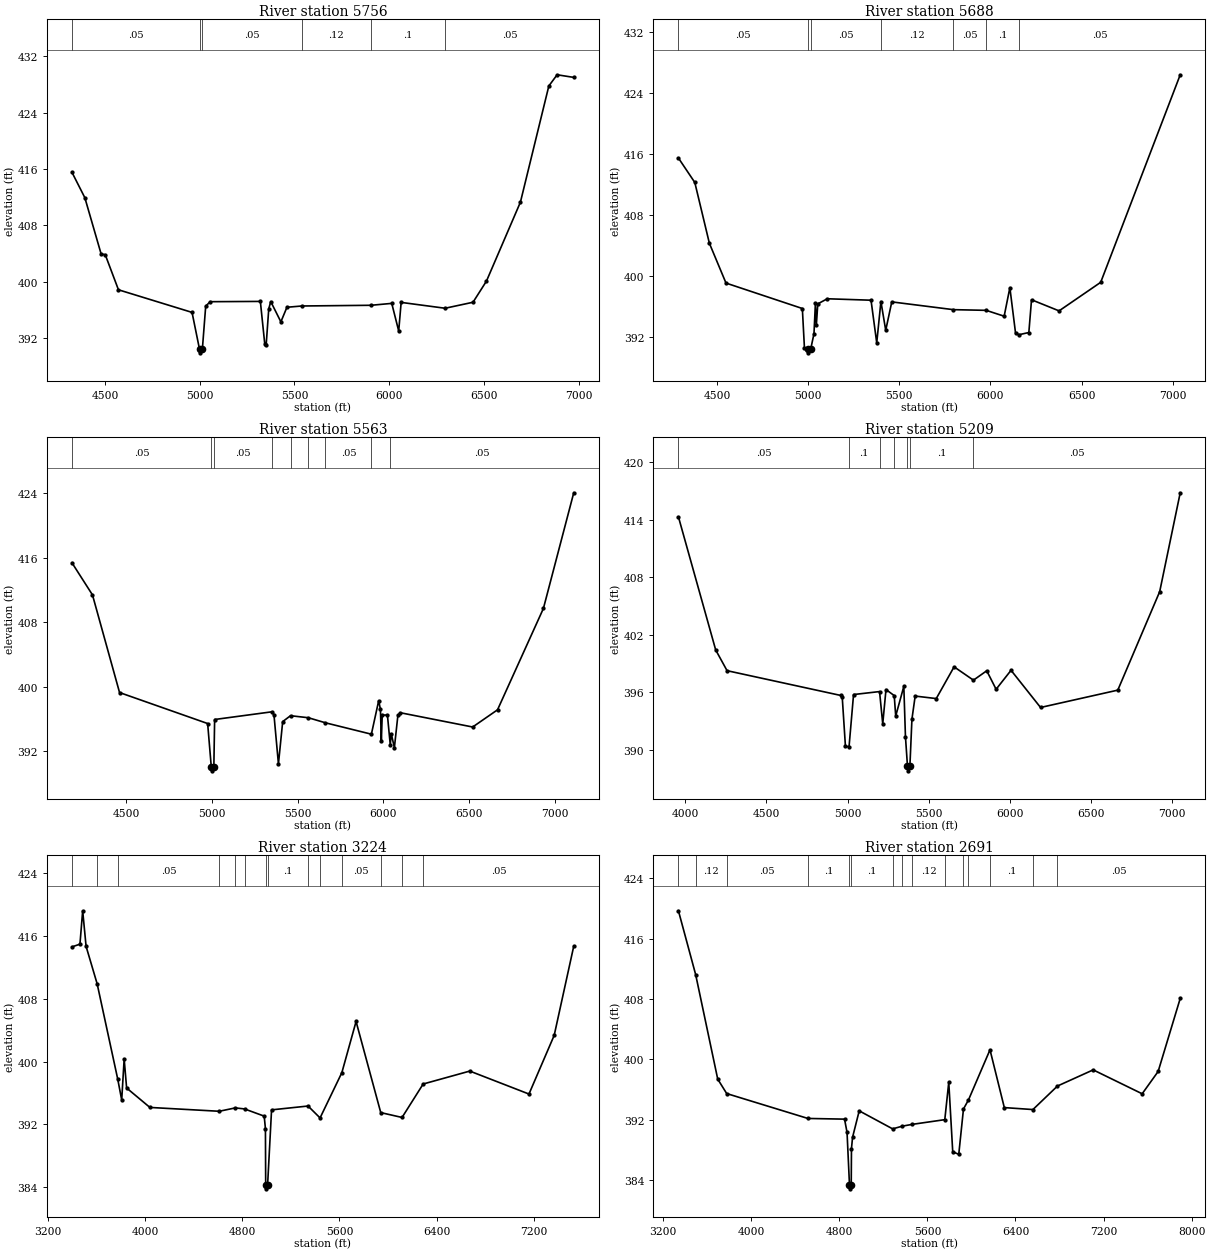
Type RM Length L Ch R = 1,5756,68,68,68
BEGIN DESCRIPTION:
South Fork Lacy Fork 1555
END DESCRIPTION:
XS GIS Cut Line= 3
      2730886.00      6867356.04      2731479.23      6868966.71
      2732226.37      6869524.62
#Sta/Elev= 30
  4325.3  415.55  4393.4  411.94  4479.4  403.95  4501.1  403.85  4570.8  398.87
  4959.3  395.66  4998.8  390.42  5000.8  389.92  5013.7  390.42  5031.4  396.55
  5055.2  397.18  5319.9  397.22  5343.0  391.22  5350.4  390.99  5364.3  396.19
  5374.9  397.19  5428.2  394.32  5460.2  396.39  5538.9  396.57  5904.1  396.67
  6013.5  396.94  6050.2  393.02  6063.1  397.08  6295.2  396.25  6442.5  397.10
  6513.4  400.10  6692.7  411.31  6842.7  427.80  6886.4  429.39  6974.2  429.02
#Mann=6,-1,0
  4325.3    0.05       0  4998.8    0.04       0  5013.7    0.05       0
  5538.9    0.12       0  5904.1     0.1       0  6295.2    0.05       0
Bank Sta=4998.8,5013.7
Exp/Cntr=0.3,0.1

Type RM Length L Ch R = 1,5688,125,125,125
BEGIN DESCRIPTION:
South Fork Lacy Fork 1558
END DESCRIPTION:
XS GIS Cut Line= 3
      2730865.86      6867338.21      2731412.63      6869175.11
      2732092.45      6869662.44
#Sta/Elev= 30
  4288.5  415.47  4378.4  412.26  4458.3  404.28  4549.5  399.05  4968.4  395.71
  4980.0  390.47  4999.3  390.39  5001.3  389.89  5014.3  390.39  5032.2  392.40
  5040.0  396.37  5045.2  393.54  5053.1  396.32  5105.2  396.99  5345.2  396.80
  5376.5  391.20  5399.4  396.63  5425.8  392.85  5459.0  396.58  5796.9  395.56
  5976.9  395.47  6075.6  394.70  6106.9  398.45  6138.2  392.45  6157.0  392.27
  6211.0  392.56  6225.7  396.86  6376.8  395.40  6605.2  399.15  7041.5  426.40
#Mann=7,-1,0
  4288.5    0.05       0  4999.3    0.04       0  5014.3    0.05       0
  5399.4    0.12       0  5796.9    0.05       0  5976.9     0.1       0
  6157.0    0.05       0
Bank Sta=4999.3,5014.3
Exp/Cntr=0.3,0.1

Type RM Length L Ch R = 1,5563,354,354,354
BEGIN DESCRIPTION:
South Fork Lacy Fork 1559
END DESCRIPTION:
XS GIS Cut Line= 3
      2730840.04      6867313.42      2731207.60      6869282.42
      2732034.58      6869689.81
#Sta/Elev= 30
  4184.7  415.37  4304.3  411.39  4462.2  399.29  4975.7  395.45  4996.8  390.09
  4998.8  389.59  5011.8  390.09  5016.4  395.95  5352.3  396.91  5362.3  396.52
  5388.3  390.45  5413.1  395.69  5458.7  396.42  5562.5  396.17  5662.6  395.54
  5930.1  394.13  5972.6  398.28  5982.8  397.21  5988.1  393.31  5993.2  396.49
  6023.5  396.51  6040.1  392.83  6045.9  394.18  6064.2  392.47  6084.5  396.45
  6098.5  396.79  6520.4  395.02  6665.3  397.15  6932.8  409.71  7109.6  424.04
#Mann=9,-1,0
  4184.7    0.05       0  4996.8    0.04       0  5011.8    0.05       0
  5352.3    0.12       0  5458.7    0.05       0  5562.5    0.12       0
  5662.6    0.05       0  5930.1     0.1       0  6040.1    0.05       0
Bank Sta=4996.8,5011.8
Exp/Cntr=0.3,0.1

Type RM Length L Ch R = 1,5209,1985,1985,1985
BEGIN DESCRIPTION:
South Fork Lacy Fork 1557
END DESCRIPTION:
XS GIS Cut Line= 3
      2730816.50      6867331.07      2730801.00      6869186.00
      2731931.58      6869694.09
#Sta/Elev= 30
  3957.0  414.29  4186.9  400.40  4256.9  398.24  4957.0  395.66  4967.0  395.54
  4987.0  390.33  5009.3  390.32  5037.0  395.75  5197.3  396.06  5217.0  392.69
  5237.0  396.27  5287.8  395.64  5297.0  393.51  5347.0  396.60  5357.0  391.37
  5369.5  388.29  5371.5  387.79  5384.5  388.29  5397.0  393.18  5417.0  395.59
  5547.0  395.33  5657.0  398.64  5776.4  397.25  5858.3  398.23  5916.1  396.30
  6008.2  398.28  6190.2  394.40  6666.5  396.21  6924.8  406.48  7051.5  416.80
#Mann=7,-1,0
  3957.0    0.05       0  5009.3     0.1       0  5197.3    0.12       0
  5287.8     0.1       0  5369.5    0.04       0  5384.5     0.1       0
  5776.4    0.05       0
Bank Sta=5369.5,5384.5
Exp/Cntr=0.3,0.1

Type RM Length L Ch R = 1,3224,533,533,533
BEGIN DESCRIPTION:
South Fork Lacy Fork 1556
END DESCRIPTION:
XS GIS Cut Line= 3
      2729478.78      6867445.92      2729756.47      6869370.37
      2731909.20      6869732.76
#Sta/Elev= 30
  3400.0  414.63  3465.8  414.98  3488.3  419.24  3516.3  414.70  3607.3  409.92
  3776.4  397.77  3809.3  395.09  3829.5  400.32  3849.7  396.62  4041.2  394.14
  4611.5  393.65  4743.4  394.08  4819.3  393.95  4981.3  393.03  4991.4  391.45
  4993.6  384.25  4995.6  383.75  5009.3  384.25  5041.9  393.83  5341.9  394.32
  5440.8  392.80  5620.1  398.58  5737.0  405.11  5940.0  393.48  6115.1  392.86
  6288.8  397.13  6672.3  398.78  7159.1  395.85  7366.6  403.34  7527.4  414.72
#Mann=14,-1,0
  3400.0    0.05       0  3607.3    0.12       0  3776.4    0.05       0
  4611.5     0.1       0  4743.4    0.12       0  4819.3     0.1       0
  4993.6    0.07       0  5009.3     0.1       0  5341.9    0.05       0
  5440.8     0.1       0  5620.1    0.05       0  5940.0     0.1       0
  6115.1    0.12       0  6288.8    0.05       0
Bank Sta=4993.6,5009.3
Exp/Cntr=0.3,0.1

Type RM Length L Ch R = 1,2691,0,0,0
BEGIN DESCRIPTION:
South Fork Lacy Fork 3451
END DESCRIPTION:
XS GIS Cut Line= 3
      2729435.47      6867505.35      2729261.40      6869454.18
      2731839.43      6869802.91
#Sta/Elev= 30
  3338.3  419.69  3494.9  411.23  3695.4  397.37  3776.8  395.46  4514.6  392.16
  4847.3  392.07  4870.0  390.31  4892.2  383.33  4894.2  382.83  4908.0  383.33
  4910.2  388.17  4920.2  389.67  4980.5  393.17  5284.2  390.78  5372.3  391.14
  5463.1  391.38  5757.9  392.00  5794.0  396.96  5830.0  387.74  5884.8  387.41
  5927.6  393.42  5973.2  394.62  6168.5  401.26  6298.6  393.60  6558.4  393.34
  6781.5  396.46  7105.8  398.60  7550.7  395.43  7695.9  398.39  7896.4  408.07
#Mann=15,-1,0
  3338.3    0.05       0  3494.9    0.12       0  3776.8    0.05       0
  4514.6     0.1       0  4892.2    0.07       0  4908.0     0.1       0
  5284.2    0.12       0  5372.3     0.1       0  5463.1    0.12       0
  5757.9    0.05       0  5927.6     0.1       0  5973.2    0.05       0
  6168.5     0.1       0  6558.4    0.12       0  6781.5    0.05       0
Bank Sta=4892.2,4908
Exp/Cntr=0.3,0.1

Chan Stop Cuts=-1