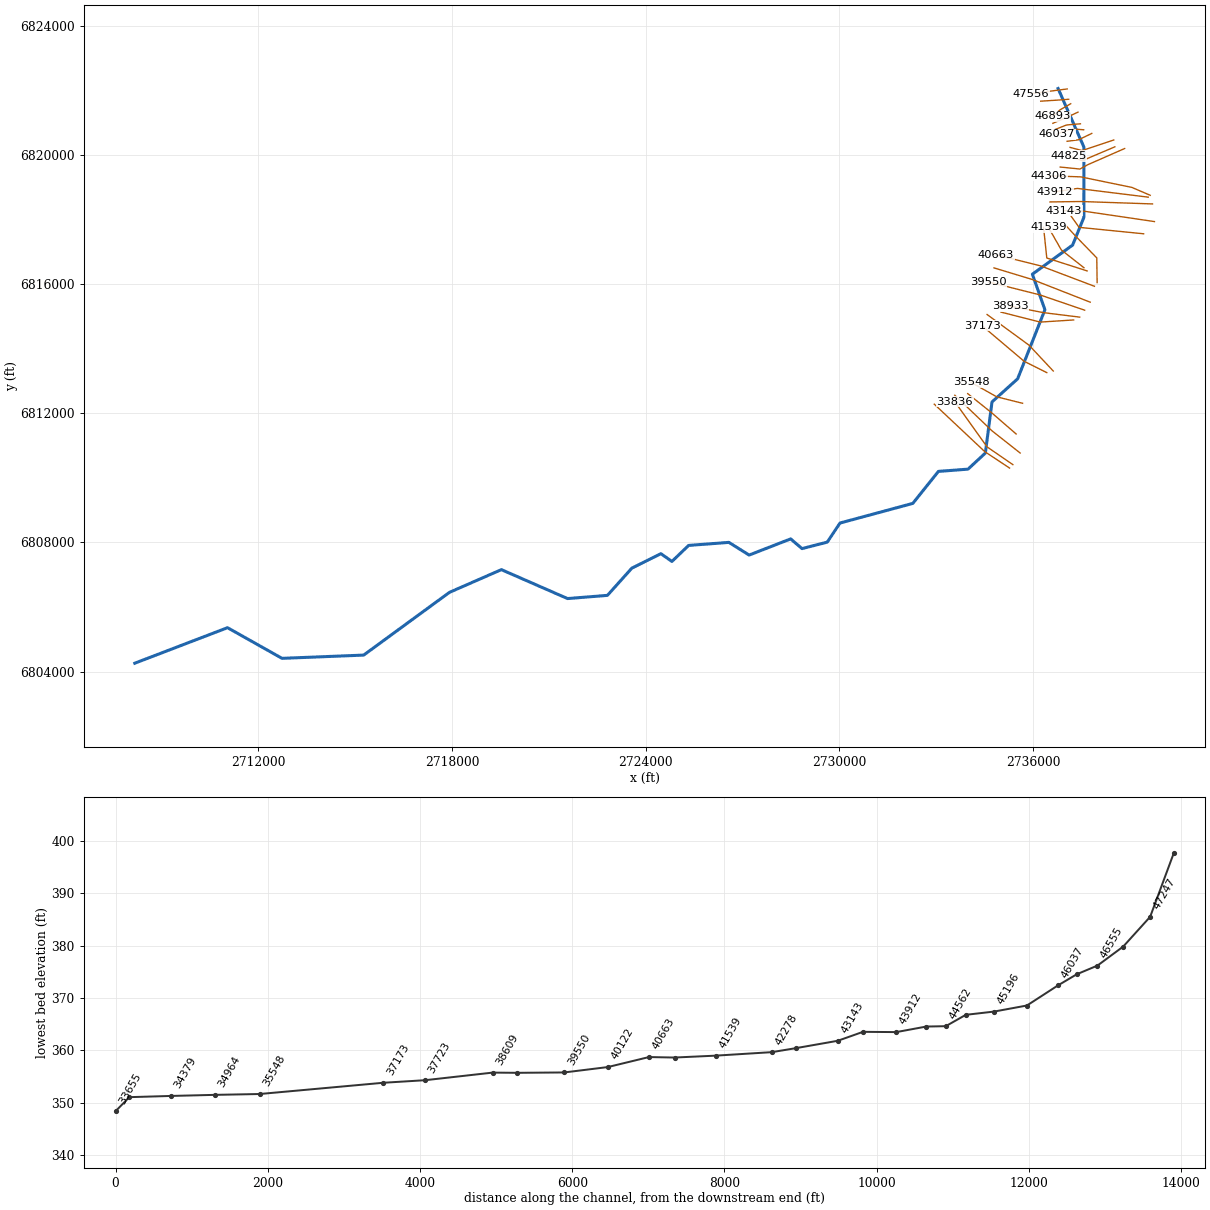
--- South Twin Creek.prj (project) ---

Proj Title=South Twin Creek Base Level Engineering
Current Plan=p01
Default Exp/Contr=0.3,0.1
English Units
Geom File=g01
Flow File=f01
Plan File=p01
BEGIN DESCRIPTION:
South Twin Creek
END DESCRIPTION:

--- South Twin Creek.p01 (plan) ---

Plan Title=Multiple Run
Short Identifier=Multiple
Geom File=g01
Flow File=f01
Subcritical Flow
K Sum by GR= 0
Std Step Tol= 0.01
Critical Tol= 0.01
Num of Std Step Trials= 20
Max Error Tol= 0.3
Flow Tol Ratio= 0.001
Split Flow NTrial= 30
Split Flow Tol= 0.02
Split Flow Ratio= 0.02
Log Output Level= 0
Friction Slope Method= 1
Unsteady Friction Slope Method= 2
Unsteady Bridges Friction Slope Method= 1
Parabolic Critical Depth
Global Vel Dist=  1 , 1 , 1
Global Log Level= 0
CheckData=True
Encroach Param= -1, 0, 0, 0
BEGIN DESCRIPTION:
Multiple Run
END DESCRIPTION:

--- South Twin Creek.f01 (steady flow) ---

Flow Title=Multiple
Number of Profiles=7
Profile Names=10-year,25-year,50-year,1pct_min,100-year,1pct_plu,500-year
River Rch & RM= South Twin Creek,Reach-1,47556
     431     570     682     406     810    1616    1139
River Rch & RM= South Twin Creek,Reach-1,44562
    3204    4610    5823    3627    7236   14438   11183
River Rch & RM= South Twin Creek,Reach-1,44306
    3255    4686    5921    3688    7359   14684   11381
River Rch & RM= South Twin Creek,Reach-1,42278
    5308    7774    9939    6259   12488   24916   19725
River Rch & RM= South Twin Creek,Reach-1,40663
    5357    7844   10028    6314   12598   25136   19893
River Rch & RM= South Twin Creek,Reach-1,37723
    5682    8335   10669    6725   13418   26773   21236
River Rch & RM= South Twin Creek,Reach-1,35548
    5702    8360   10698    6741   13449   26835   21269
River Rch & RM= South Twin Creek,Reach-1,34964
    5667    8291   10592    6663   13294   26526   20954
River Rch & RM= South Twin Creek,Reach-1,31922
    5656    8269   10560    6640   13248   26434   20863
River Rch & RM= South Twin Creek,Reach-1,31260
    5799    8483   10837    6816   13600   27136   21430
River Rch & RM= South Twin Creek,Reach-1,29932
    5828    8512   10863    6824   13617   27169   21404
River Rch & RM= South Twin Creek,Reach-1,26876
    5966    8709   11109    6975   13916   27766   21848
River Rch & RM= South Twin Creek,Reach-1,23340
    5967    8706   11101    6968   13902   27738   21811
River Rch & RM= South Twin Creek,Reach-1,21857
    6140    8959   11425    7171   14307   28547   22446
River Rch & RM= South Twin Creek,Reach-1,19705
    6145    8963   11427    7170   14306   28544   22431
River Rch & RM= South Twin Creek,Reach-1,19312
    6168    8988   11451    7179   14325   28582   22426
River Rch & RM= South Twin Creek,Reach-1,18087
    6128    8934   11386    7141   14249   28430   22323
River Rch & RM= South Twin Creek,Reach-1,15571
    6162    8971   11423    7157   14281   28494   22329
River Rch & RM= South Twin Creek,Reach-1,13438
    6312    9189   11699    7329   14624   29179   22857
River Rch & RM= South Twin Creek,Reach-1,11423
    6350    9235   11751    7356   14678   29286   22906
River Rch & RM= South Twin Creek,Reach-1,6822
    6320    9164   11635    7268   14501   28933   22529
River Rch & RM= South Twin Creek,Reach-1,5983
    6352    9234   11745    7350   14665   29261   22872
Boundary for River Rch & Prof#=South Twin Creek,Reach-1,1
Up Type=0
Dn Type=3
Dn Slope=0.005
Boundary for River Rch & Prof#=South Twin Creek,Reach-1,2
Up Type=0
Dn Type=3
Dn Slope=0.005
Boundary for River Rch & Prof#=South Twin Creek,Reach-1,3
Up Type=0
Dn Type=3
Dn Slope=0.005
Boundary for River Rch & Prof#=South Twin Creek,Reach-1,4
Up Type=0
Dn Type=3
Dn Slope=0.005
Boundary for River Rch & Prof#=South Twin Creek,Reach-1,5
Up Type=0
Dn Type=3
Dn Slope=0.005
Boundary for River Rch & Prof#=South Twin Creek,Reach-1,6
Up Type=0
Dn Type=3
Dn Slope=0.005
Boundary for River Rch & Prof#=South Twin Creek,Reach-1,7
Up Type=0
Dn Type=3
Dn Slope=0.005

--- South Twin Creek.g01 (geometry) ---

Geom Title=Existing Conditions

River Reach=South Twin Creek,Reach-1
Reach XY= 30
      2736776.00      6822061.00      2737575.75      6820244.98
      2737573.88      6818066.88      2737226.00      6817211.00
      2735979.55      6816309.53      2736367.96      6815207.68
      2735522.57      6813069.34      2734728.95      6812352.86
      2734522.61      6810769.38      2733986.38      6810271.97
      2733068.99      6810201.97      2732276.00      6809211.00
      2730019.47      6808602.12      2729626.00      6808011.00
      2728844.28      6807810.92      2728492.02      6808110.83
      2727205.79      6807610.45      2726579.35      6808003.40
      2725331.89      6807909.04      2724814.17      6807412.61
      2724472.59      6807653.19      2723573.25      6807205.71
      2722816.41      6806362.21      2721581.52      6806263.35
      2719531.72      6807159.12      2717923.52      6806455.58
      2715266.41      6804512.20      2712736.40      6804411.96
      2711048.69      6805361.13      2708176.00      6804261.00

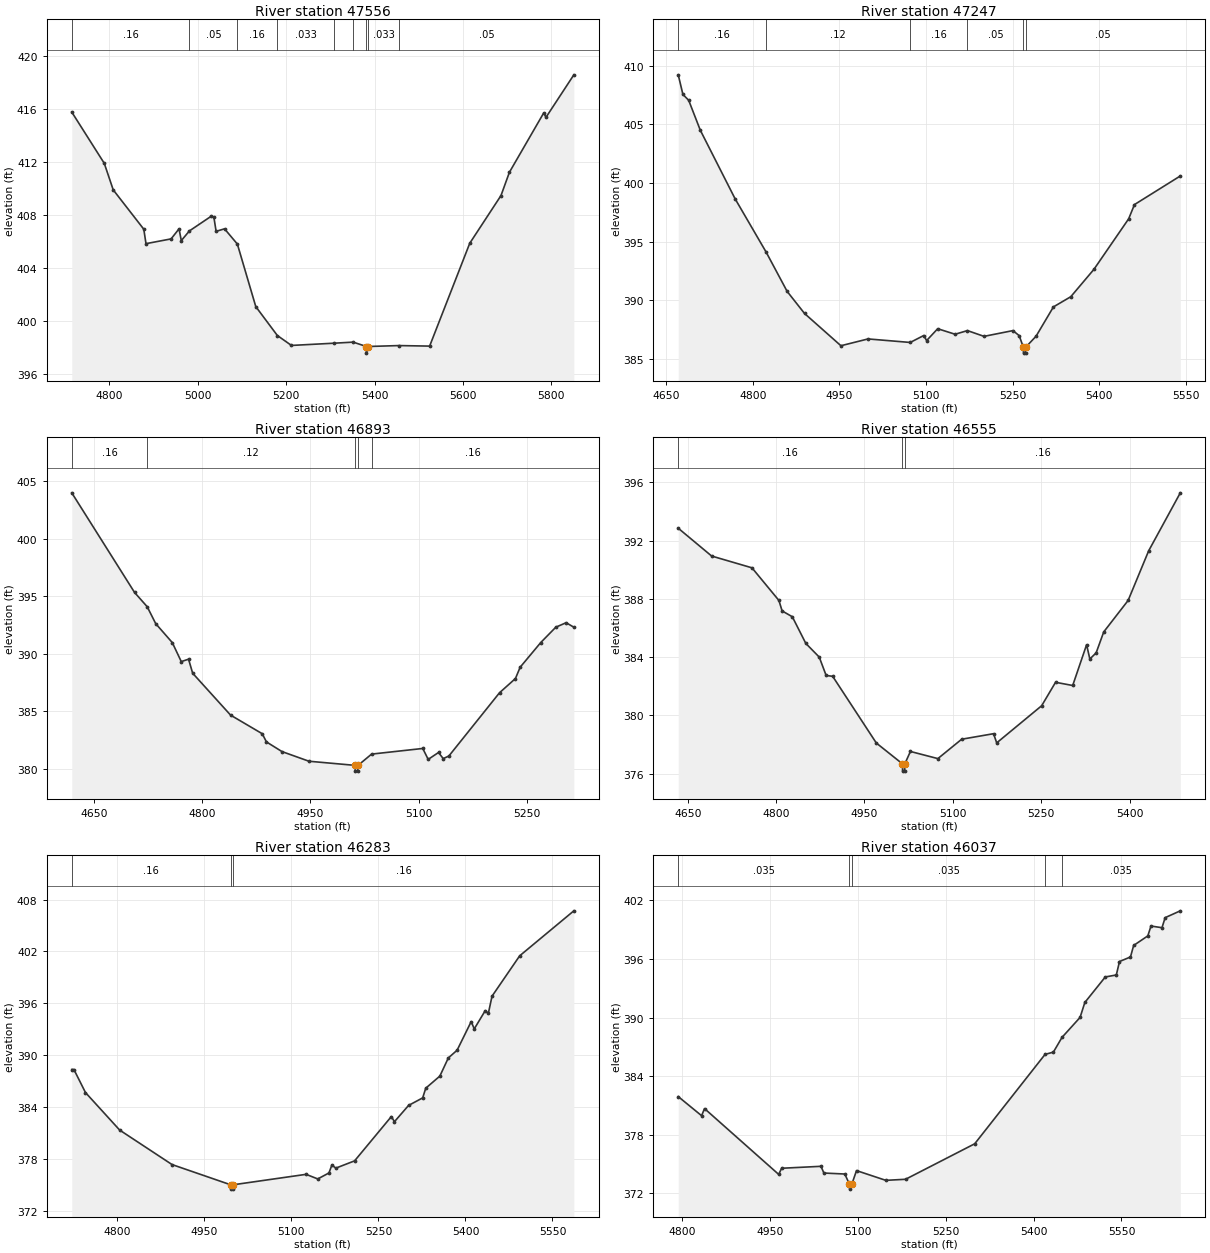
Type RM Length L Ch R = 1,47556,309,309,309
BEGIN DESCRIPTION:
South Twin Creek47556.113
END DESCRIPTION:
XS GIS Cut Line= 3
      2737059.01      6822047.06      2736776.00      6822011.00
      2735932.57      6821897.00
#Sta/Elev= 30
  4714.7  415.80  4788.3  411.93  4808.5  409.93  4877.7  406.96  4882.7  405.87
  4939.5  406.23  4957.5  406.99  4962.6  406.10  4980.9  406.83  5030.3  407.94
  5036.3  407.88  5041.4  406.80  5060.5  406.99  5089.5  405.84  5131.2  401.12
  5180.0  398.94  5211.9  398.19  5308.8  398.36  5351.7  398.44  5381.5  398.11
  5381.7  397.61  5385.5  398.11  5455.0  398.18  5524.7  398.14  5615.5  405.90
  5686.2  409.50  5705.3  411.26  5783.0  415.74  5788.0  415.40  5851.1  418.61
#Mann=9,-1,0
  4714.7    0.16       0  4980.9    0.05       0  5089.5    0.16       0
  5180.0   0.033       0  5308.8    0.16       0  5351.7   0.033       0
  5381.5    0.05       0  5385.5   0.033       0  5455.0    0.05       0
Bank Sta=5381.5,5385.5
Exp/Cntr=0.3,0.1

Type RM Length L Ch R = 1,47247,354,354,354
BEGIN DESCRIPTION:
South Twin Creek47247.22
END DESCRIPTION:
XS GIS Cut Line= 3
      2737104.07      6821727.84      2736771.71      6821701.78
      2736236.74      6821668.33
#Sta/Elev= 30
  4670.8  409.22  4678.9  407.55  4688.9  407.05  4709.0  404.50  4769.2  398.66
  4822.9  394.12  4859.4  390.76  4889.5  388.88  4952.5  386.13  4999.5  386.71
  5072.5  386.41  5095.9  387.00  5100.9  386.57  5120.1  387.58  5150.2  387.11
  5171.6  387.42  5200.3  386.93  5250.4  387.42  5261.2  386.99  5268.4  386.00
  5268.7  385.50  5272.2  385.50  5272.4  386.00  5290.4  386.94  5320.5  389.44
  5350.6  390.31  5390.6  392.64  5450.8  396.95  5460.8  398.16  5540.2  400.60
#Mann=6,-1,0
  4670.8    0.16       0  4822.9    0.12       0  5072.5    0.16       0
  5171.6    0.05       0  5268.4    0.07       0  5272.4    0.05       0
Bank Sta=5268.4,5272.4
Exp/Cntr=0.3,0.1

Type RM Length L Ch R = 1,46893,338,338,338
BEGIN DESCRIPTION:
South Twin Creek46893.14
END DESCRIPTION:
XS GIS Cut Line= 3
      2737166.86      6821589.06      2736836.20      6821399.38
      2736596.24      6821196.25
#Sta/Elev= 30
  4619.6  404.00  4706.6  395.34  4724.1  394.10  4735.9  392.63  4758.9  390.98
  4771.3  389.33  4781.4  389.54  4787.1  388.32  4839.6  384.68  4883.5  383.06
  4889.3  382.35  4910.8  381.51  4948.2  380.67  5012.2  380.31  5012.4  379.81
  5015.9  379.81  5016.2  380.31  5035.0  381.29  5105.9  381.78  5113.4  380.83
  5127.7  381.43  5134.2  380.90  5142.0  381.12  5212.2  386.62  5234.3  387.86
  5240.8  388.84  5269.4  390.99  5290.2  392.32  5304.5  392.71  5315.2  392.32
#Mann=5,-1,0
  4619.6    0.16       0  4724.1    0.12       0  5012.2    0.07       0
  5016.2    0.12       0  5035.0    0.16       0
Bank Sta=5012.2,5016.2
Exp/Cntr=0.3,0.1

Type RM Length L Ch R = 1,46555,272,272,272
BEGIN DESCRIPTION:
South Twin Creek46554.96
END DESCRIPTION:
XS GIS Cut Line= 3
      2737393.50      6821329.46      2737059.84      6821173.48
      2736614.52      6820983.69
#Sta/Elev= 30
  4633.8  392.86  4690.5  390.95  4759.0  390.14  4804.7  387.90  4810.2  387.18
  4827.5  386.78  4850.4  384.95  4873.2  384.01  4884.9  382.75  4896.0  382.69
  4970.1  378.11  5014.5  376.68  5014.7  376.18  5018.2  376.18  5018.5  376.68
  5028.0  377.53  5074.6  377.04  5115.0  378.37  5169.1  378.75  5174.5  378.12
  5250.8  380.67  5274.4  382.28  5303.5  382.06  5327.1  384.86  5332.6  383.88
  5343.3  384.30  5356.2  385.74  5397.6  387.90  5432.5  391.31  5486.2  395.29
#Mann=3,-1,0
  4633.8    0.16       0  5014.5    0.07       0  5018.5    0.16       0
Bank Sta=5014.5,5018.5
Exp/Cntr=0.3,0.1

Type RM Length L Ch R = 1,46283,246,246,246
BEGIN DESCRIPTION:
South Twin Creek46282.79
END DESCRIPTION:
XS GIS Cut Line= 4
      2737468.26      6820967.56      2737186.52      6820945.29
      2737030.37      6820928.60      2736635.02      6820771.18
#Sta/Elev= 30
  4721.6  388.35  4725.3  388.35  4745.2  385.69  4804.1  381.35  4894.4  377.36
  4995.5  375.02  4995.7  374.52  4999.2  374.52  4999.5  375.02  5125.4  376.23
  5145.5  375.70  5164.8  376.39  5169.8  377.30  5176.7  376.95  5209.0  377.79
  5272.3  382.91  5277.7  382.32  5302.0  384.20  5326.3  385.07  5331.6  386.19
  5355.9  387.59  5370.5  389.69  5385.6  390.58  5409.9  393.89  5415.2  393.05
  5434.1  395.16  5439.5  394.85  5445.8  396.83  5493.5  401.50  5586.8  406.70
#Mann=3,-1,0
  4721.6    0.16       0  4995.5    0.07       0  4999.5    0.16       0
Bank Sta=4995.5,4999.5
Exp/Cntr=0.3,0.1

Type RM Length L Ch R = 1,46037,409,409,409
BEGIN DESCRIPTION:
South Twin Creek46036.6
END DESCRIPTION:
XS GIS Cut Line= 5
      2737569.67      6820782.92      2737359.78      6820798.73
      2737146.26      6820783.28      2737012.39      6820756.73
      2736737.16      6820646.29
#Sta/Elev= 30
  4792.9  381.89  4832.8  379.93  4837.8  380.66  4964.5  373.91  4969.5  374.54
  5036.7  374.74  5041.7  374.05  5077.4  373.95  5085.4  372.90  5085.6  372.40
  5089.4  372.90  5097.4  374.30  5147.5  373.30  5181.2  373.41  5299.3  377.05
  5419.5  386.22  5433.7  386.45  5448.4  387.96  5479.3  390.01  5487.4  391.54
  5522.4  394.16  5541.2  394.36  5546.6  395.74  5565.4  396.21  5570.8  397.39
  5595.0  398.37  5600.4  399.38  5619.2  399.21  5624.6  400.24  5650.5  400.94
#Mann=5,-1,0
  4792.9   0.035       0  5085.4   0.035       0  5089.4   0.035       0
  5419.5    0.05       0  5448.4   0.035       0
Bank Sta=5085.4,5089.4
Exp/Cntr=0.3,0.1

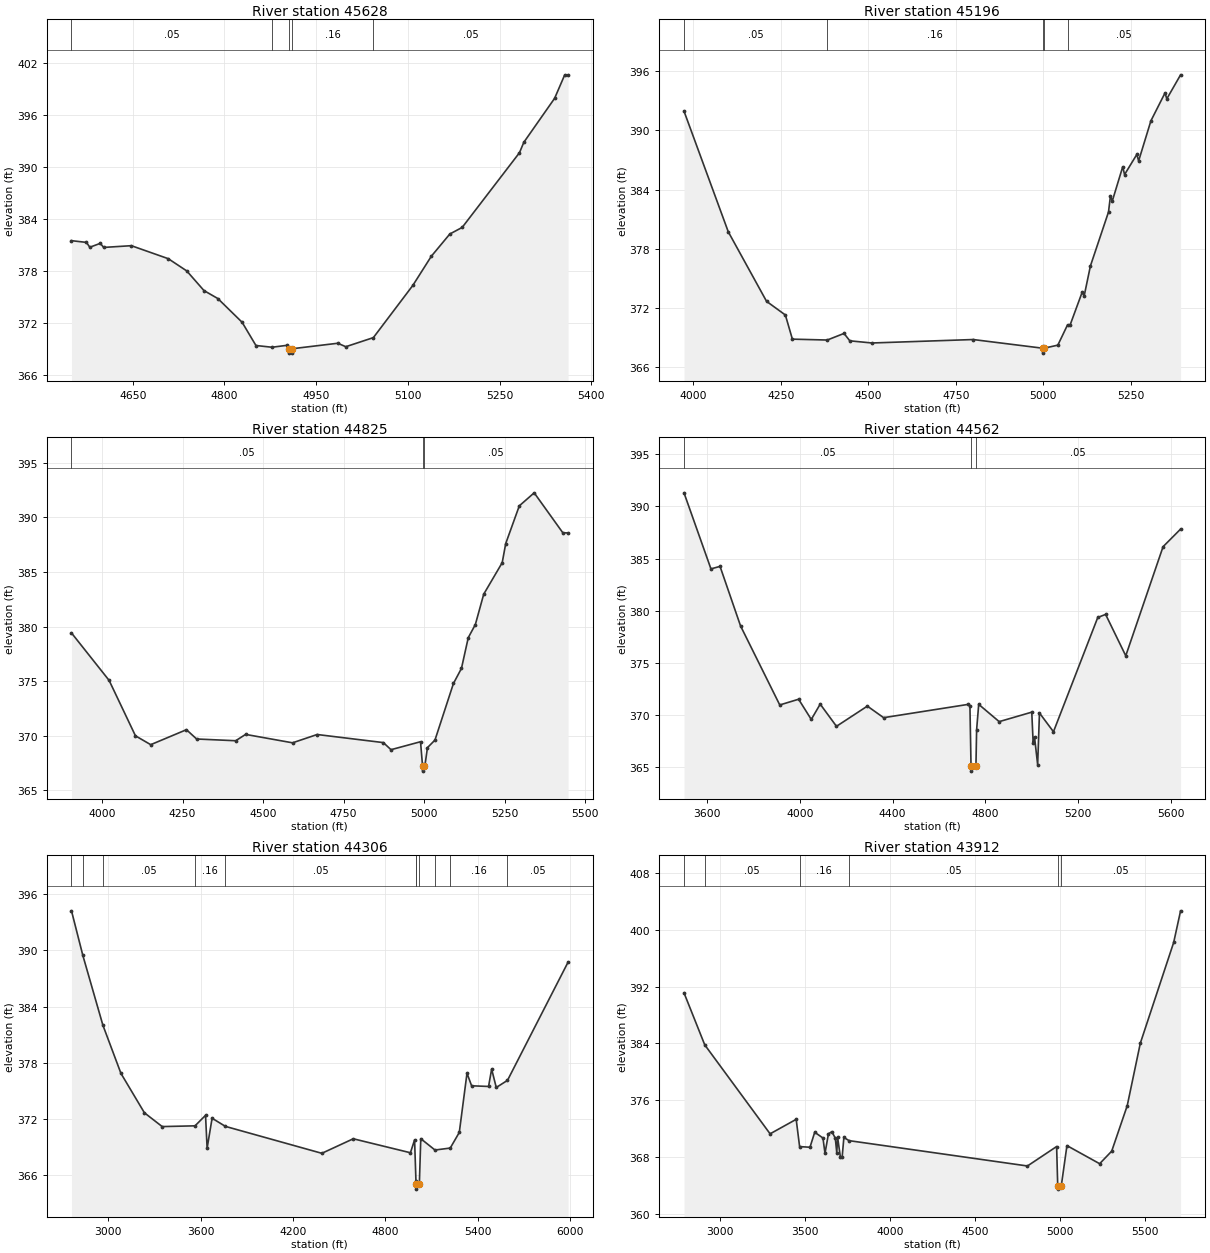
Type RM Length L Ch R = 1,45628,432,432,432
BEGIN DESCRIPTION:
South Twin Creek45627.83
END DESCRIPTION:
XS GIS Cut Line= 3
      2737818.72      6820668.65      2737408.84      6820471.89
      2737054.24      6820425.39
#Sta/Elev= 30
  4549.8  381.53  4574.2  381.33  4579.8  380.77  4596.9  381.22  4602.4  380.75
  4647.7  380.95  4708.1  379.45  4738.3  378.04  4766.5  375.77  4789.2  374.85
  4828.9  372.11  4851.5  369.43  4877.7  369.23  4902.4  369.45  4905.9  369.05
  4906.2  368.55  4909.7  368.55  4909.9  369.05  4985.4  369.69  4998.5  369.29
  5043.6  370.34  5108.2  376.37  5138.4  379.73  5168.7  382.30  5188.9  383.06
  5282.6  391.68  5289.7  392.88  5340.1  397.96  5356.4  400.63  5362.1  400.67
#Mann=5,-1,0
  4549.8    0.05       0  4877.7    0.16       0  4905.9    0.07       0
  4909.9    0.16       0  5043.6    0.05       0
Bank Sta=4905.9,4909.9
Exp/Cntr=0.3,0.1

Type RM Length L Ch R = 1,45196,371,371,371
BEGIN DESCRIPTION:
South Twin Creek45195.94
END DESCRIPTION:
XS GIS Cut Line= 3
      2738499.69      6820466.60      2737519.64      6820138.55
      2737146.84      6820237.09
#Sta/Elev= 30
  3973.0  391.96  4099.5  379.71  4208.9  372.65  4262.7  371.26  4282.7  368.81
  4382.4  368.72  4430.3  369.39  4446.8  368.64  4510.0  368.42  4799.4  368.77
  4997.8  367.89  4998.0  367.39  5001.8  367.89  5041.3  368.20  5069.2  370.27
  5076.1  370.22  5111.2  373.61  5116.4  373.17  5134.4  376.24  5186.1  381.72
  5191.7  383.36  5196.9  382.83  5226.8  386.32  5232.0  385.52  5267.1  387.57
  5272.2  386.91  5307.3  390.98  5347.6  393.81  5352.7  393.21  5392.1  395.65
#Mann=5,-1,0
  3973.0    0.05       0  4382.4    0.16       0  4997.8    0.07       0
  5001.8    0.16       0  5069.2    0.05       0
Bank Sta=4997.8,5001.8
Exp/Cntr=0.3,0.1

Type RM Length L Ch R = 1,44825,263,263,263
BEGIN DESCRIPTION:
South Twin Creek44824.911
END DESCRIPTION:
XS GIS Cut Line= 3
      2738533.63      6820253.69      2737525.90      6819826.09
      2737102.72      6819970.38
#Sta/Elev= 30
  3905.3  379.41  4022.1  375.07  4103.9  370.00  4151.3  369.19  4262.2  370.56
  4293.8  369.71  4415.1  369.55  4445.9  370.13  4591.6  369.36  4668.0  370.12
  4873.6  369.38  4897.3  368.73  4989.0  369.46  4995.2  367.27  4995.5  366.77
  4999.2  367.27  5002.6  367.27  5010.5  368.92  5033.8  369.61  5091.2  374.79
  5116.1  376.17  5137.2  378.98  5159.2  380.18  5185.2  382.96  5242.6  385.84
  5253.5  387.59  5295.7  391.04  5341.9  392.23  5430.7  388.58  5447.1  388.56
#Mann=3,-1,0
  3905.3    0.05       0  4995.2    0.05       0  4999.2    0.05       0
Bank Sta=4995.2,4999.2
Exp/Cntr=0.3,0.1

Type RM Length L Ch R = 1,44562,256,256,256
BEGIN DESCRIPTION:
South Twin Creek44561.714
END DESCRIPTION:
XS GIS Cut Line= 4
      2738838.15      6820202.33      2737689.53      6819697.47
      2737453.78      6819566.82      2736840.88      6819628.48
#Sta/Elev= 30
  3501.2  391.31  3617.3  384.01  3656.5  384.25  3745.0  378.53  3913.9  370.95
  3995.1  371.50  4049.7  369.56  4088.2  371.03  4158.3  368.90  4291.4  370.84
  4361.5  369.73  4727.0  371.01  4733.5  370.85  4738.2  365.10  4738.7  364.60
  4759.4  365.10  4762.3  368.56  4771.3  371.01  4859.6  369.35  5000.0  370.26
  5006.1  367.27  5011.8  367.88  5025.4  365.22  5033.2  370.18  5093.5  368.38
  5284.5  379.35  5318.3  379.64  5405.1  375.67  5565.9  386.14  5641.4  387.83
#Mann=3,-1,0
  3501.2    0.05       0  4738.2    0.05       0  4759.4    0.05       0
Bank Sta=4738.2,4759.4
Exp/Cntr=0.3,0.1

Type RM Length L Ch R = 1,44306,394,394,394
BEGIN DESCRIPTION:
South Twin Creek44306.386
END DESCRIPTION:
XS GIS Cut Line= 4
      2739631.14      6818752.63      2739062.56      6818997.37
      2737471.28      6819324.79      2736489.74      6819356.88
#Sta/Elev= 30
  2761.2  394.21  2834.8  389.46  2965.0  382.02  3082.5  376.87  3234.9  372.67
  3350.4  371.20  3563.7  371.28  3631.9  372.40  3642.2  368.89  3674.5  372.09
  3761.2  371.22  4387.4  368.35  4591.6  369.90  4962.8  368.41  4989.8  369.78
  4998.8  365.37  4999.5  365.03  5000.0  364.53  5020.7  365.03  5030.1  369.91
  5122.4  368.70  5221.5  368.91  5280.3  370.58  5330.3  376.89  5360.3  375.55
  5470.4  375.48  5490.4  377.33  5520.4  375.37  5593.4  376.13  5986.9  388.74
#Mann=11,-1,0
  2761.2    0.12       0  2834.8    0.16       0  2965.0    0.05       0
  3563.7    0.16       0  3761.2    0.05       0  4998.8    0.16       0
  4999.5    0.07       0  5020.7    0.16       0  5122.4    0.05       0
  5221.5    0.16       0  5593.4    0.05       0
Bank Sta=4999.5,5020.7
Exp/Cntr=0.3,0.1

Type RM Length L Ch R = 1,43912,437,437,437
BEGIN DESCRIPTION:
South Twin Creek43911.521
END DESCRIPTION:
XS GIS Cut Line= 3
      2739567.80      6818695.70      2737375.52      6818966.20
      2736675.99      6818861.00
#Sta/Elev= 30
  2791.1  391.12  2912.9  383.79  3296.7  371.26  3449.9  373.30  3470.0  369.46
  3531.0  369.37  3558.7  371.48  3607.1  370.67  3619.1  368.51  3639.3  371.26
  3659.4  371.56  3679.6  370.65  3688.2  368.61  3693.3  370.75  3709.8  367.93
  3719.9  367.99  3730.0  370.75  3760.3  370.30  4808.1  366.73  4979.4  369.47
  4985.8  363.97  4986.3  363.47  5007.0  363.97  5040.0  369.60  5232.1  367.05
  5302.9  368.82  5393.9  375.21  5470.9  384.02  5666.9  398.22  5707.4  402.67
#Mann=6,-1,0
  2791.1    0.16       0  2912.9    0.05       0  3470.0    0.16       0
  3760.3    0.05       0  4985.8    0.05       0  5007.0    0.05       0
Bank Sta=4985.8,5007
Exp/Cntr=0.3,0.1

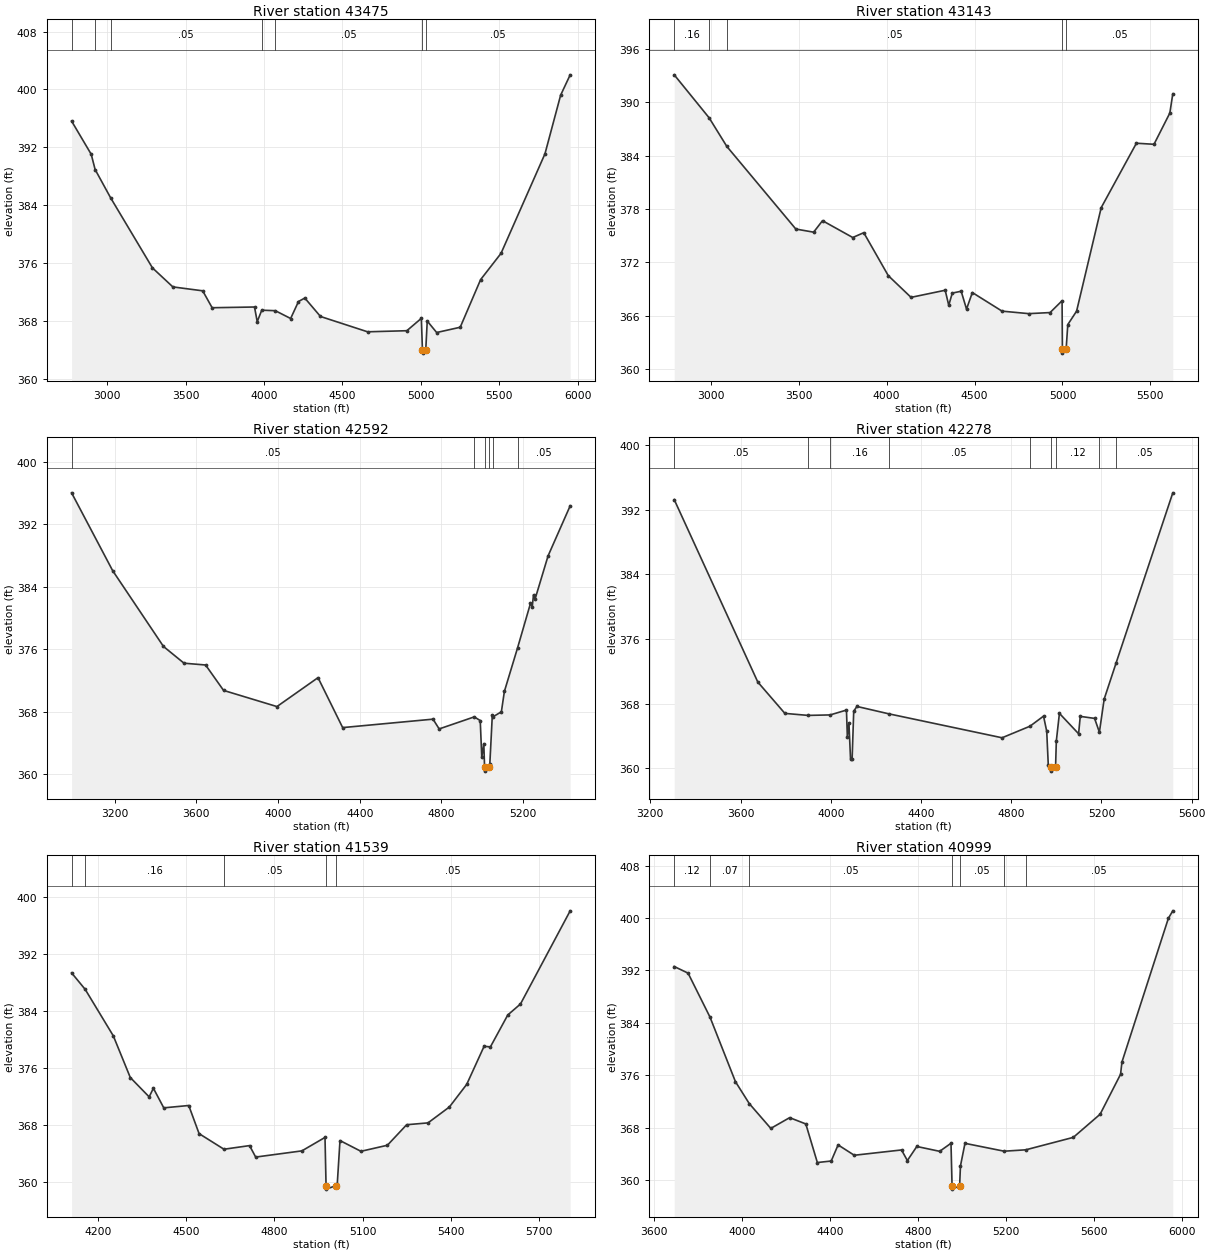
Type RM Length L Ch R = 1,43475,332,332,332
BEGIN DESCRIPTION:
South Twin Creek43474.727
END DESCRIPTION:
XS GIS Cut Line= 3
      2739700.97      6818486.00      2737476.33      6818561.14
      2736525.34      6818547.31
#Sta/Elev= 30
  2774.1  395.62  2899.1  391.03  2924.0  388.92  3023.2  384.99  3289.4  375.31
  3419.4  372.68  3609.5  372.14  3669.6  369.80  3939.7  369.90  3956.9  367.87
  3985.8  369.46  4072.3  369.39  4169.9  368.31  4219.9  370.66  4260.1  371.14
  4360.0  368.59  4660.1  366.47  4910.3  366.62  5002.7  368.33  5009.6  364.02
  5010.1  363.52  5031.0  364.02  5040.3  367.96  5100.3  366.37  5250.4  367.10
  5380.4  373.69  5510.4  377.32  5790.4  391.09  5890.4  399.21  5951.1  402.02
#Mann=7,-1,0
  2774.1    0.16       0  2924.0    0.07       0  3023.2    0.05       0
  3985.8    0.16       0  4072.3    0.05       0  5009.6    0.05       0
  5031.0    0.05       0
Bank Sta=5009.6,5031
Exp/Cntr=0.3,0.1

Type RM Length L Ch R = 1,43143,551,551,551
BEGIN DESCRIPTION:
South Twin Creek43142.737
END DESCRIPTION:
XS GIS Cut Line= 3
      2739760.15      6817939.46      2737576.00      6818261.00
      2736949.13      6818274.43
#Sta/Elev= 30
  2792.7  393.10  2991.4  388.26  3091.8  385.05  3484.2  375.76  3585.3  375.41
  3635.8  376.70  3807.7  374.81  3870.4  375.35  4009.8  370.52  4139.2  368.08
  4333.3  368.88  4353.5  367.19  4373.7  368.56  4424.2  368.77  4454.6  366.76
  4487.7  368.62  4656.7  366.53  4808.3  366.25  4929.6  366.37  4997.9  367.70
  4999.7  362.31  5000.2  361.81  5021.1  362.31  5030.4  365.02  5080.4  366.53
  5220.4  378.17  5420.5  385.41  5520.5  385.29  5610.5  388.80  5627.4  390.97
#Mann=5,-1,0
  2792.7    0.16       0  2991.4    0.07       0  3091.8    0.05       0
  4999.7    0.05       0  5021.1    0.05       0
Bank Sta=4999.7,5021.1
Exp/Cntr=0.3,0.1

Type RM Length L Ch R = 1,42592,314,314,314
BEGIN DESCRIPTION:
South Twin Creek42592.214
END DESCRIPTION:
XS GIS Cut Line= 3
      2739426.00      6817561.00      2737426.00      6817761.00
      2737176.00      6818111.01
#Sta/Elev= 30
  2990.0  396.01  3191.0  386.05  3439.7  376.35  3540.2  374.21  3645.8  373.98
  3733.7  370.73  3995.0  368.66  4196.0  372.36  4316.6  365.97  4758.8  367.05
  4788.9  365.80  4960.6  367.34  4989.9  366.87  4997.5  362.18  5007.3  363.92
  5011.2  360.90  5011.7  360.40  5032.9  360.90  5036.8  361.27  5049.1  367.59
  5054.2  367.38  5093.4  367.99  5108.1  370.60  5172.5  376.16  5235.9  381.87
  5244.5  381.45  5250.7  382.97  5258.0  382.39  5321.9  387.94  5430.1  394.35
#Mann=6,-1,0
  2990.0    0.05       0  4960.6    0.12       0  5011.2    0.07       0
  5032.9    0.12       0  5054.2    0.16       0  5172.5    0.05       0
Bank Sta=5011.2,5032.9
Exp/Cntr=0.3,0.1

Type RM Length L Ch R = 1,42278,739,739,739
BEGIN DESCRIPTION:
South Twin Creek42277.749
END DESCRIPTION:
XS GIS Cut Line= 4
      2737984.90      6816050.46      2737974.58      6816814.04
      2737325.77      6817481.09      2736976.00      6817861.00
#Sta/Elev= 30
  3305.8  393.26  3676.4  370.67  3796.4  366.79  3899.3  366.54  3997.2  366.60
  4069.5  367.20  4073.4  363.89  4080.4  365.63  4087.5  361.17  4094.5  361.08
  4101.7  367.06  4115.8  367.65  4256.5  366.74  4759.4  363.77  4883.1  365.20
  4943.3  366.45  4957.4  364.57  4964.4  360.35  4974.9  360.14  4975.4  359.64
  4996.6  360.14  5000.0  363.38  5013.7  366.79  5098.7  364.27  5106.1  366.42
  5169.6  366.17  5190.9  364.46  5212.1  368.56  5265.7  373.09  5516.4  394.10
#Mann=9,-1,0
  3305.8    0.05       0  3899.3    0.12       0  3997.2    0.16       0
  4256.5    0.05       0  4883.1    0.12       0  4974.9    0.07       0
  4996.6    0.12       0  5190.9    0.16       0  5265.7    0.05       0
Bank Sta=4974.9,4996.6
Exp/Cntr=0.3,0.1

Type RM Length L Ch R = 1,41539,540,540,540
BEGIN DESCRIPTION:
South Twin Creek41538.84
END DESCRIPTION:
XS GIS Cut Line= 3
      2737575.98      6816511.01      2736876.00      6817061.00
      2736476.02      6817760.97
#Sta/Elev= 30
  4109.8  389.33  4156.1  387.01  4251.7  380.49  4309.5  374.64  4373.7  371.92
  4388.1  373.13  4423.4  370.38  4508.4  370.71  4543.6  366.76  4628.3  364.57
  4715.3  365.08  4736.1  363.47  4893.4  364.34  4972.0  366.23  4975.6  359.47
  4976.3  358.97  5010.0  359.47  5013.7  359.67  5023.0  365.79  5094.3  364.28
  5184.3  365.13  5249.8  368.01  5322.5  368.27  5395.2  370.50  5454.2  373.68
  5513.3  379.02  5534.8  378.94  5593.9  383.42  5637.1  384.96  5806.2  398.04
#Mann=5,-1,0
  4109.8    0.12       0  4156.1    0.16       0  4628.3    0.05       0
  4975.6    0.05       0  5010.0    0.05       0
Bank Sta=4975.6,5010
Exp/Cntr=0.3,0.1

Type RM Length L Ch R = 1,40999,336,336,336
BEGIN DESCRIPTION:
South Twin Creek40998.963
END DESCRIPTION:
XS GIS Cut Line= 3
      2737675.98      6816411.01      2736426.00      6816811.00
      2736326.00      6817761.03
#Sta/Elev= 30
  3692.2  392.59  3755.2  391.58  3854.9  384.87  3970.7  375.01  4033.7  371.66
  4131.5  367.88  4217.2  369.52  4290.7  368.56  4343.2  362.67  4406.2  362.90
  4437.6  365.36  4511.1  363.78  4726.1  364.59  4752.6  362.97  4795.6  365.12
  4899.6  364.38  4951.1  365.61  4955.9  359.11  4956.6  358.61  4990.3  359.11
  4994.1  362.15  5014.7  365.60  5192.8  364.40  5291.1  364.61  5507.4  366.51
  5629.3  370.04  5722.3  376.14  5728.6  378.01  5939.8  399.95  5959.9  401.09
#Mann=7,-1,0
  3692.2    0.12       0  3854.9    0.07       0  4033.7    0.05       0
  4955.9    0.05       0  4990.3    0.05       0  5192.8    0.07       0
  5291.1    0.05       0
Bank Sta=4955.9,4990.3
Exp/Cntr=0.3,0.1

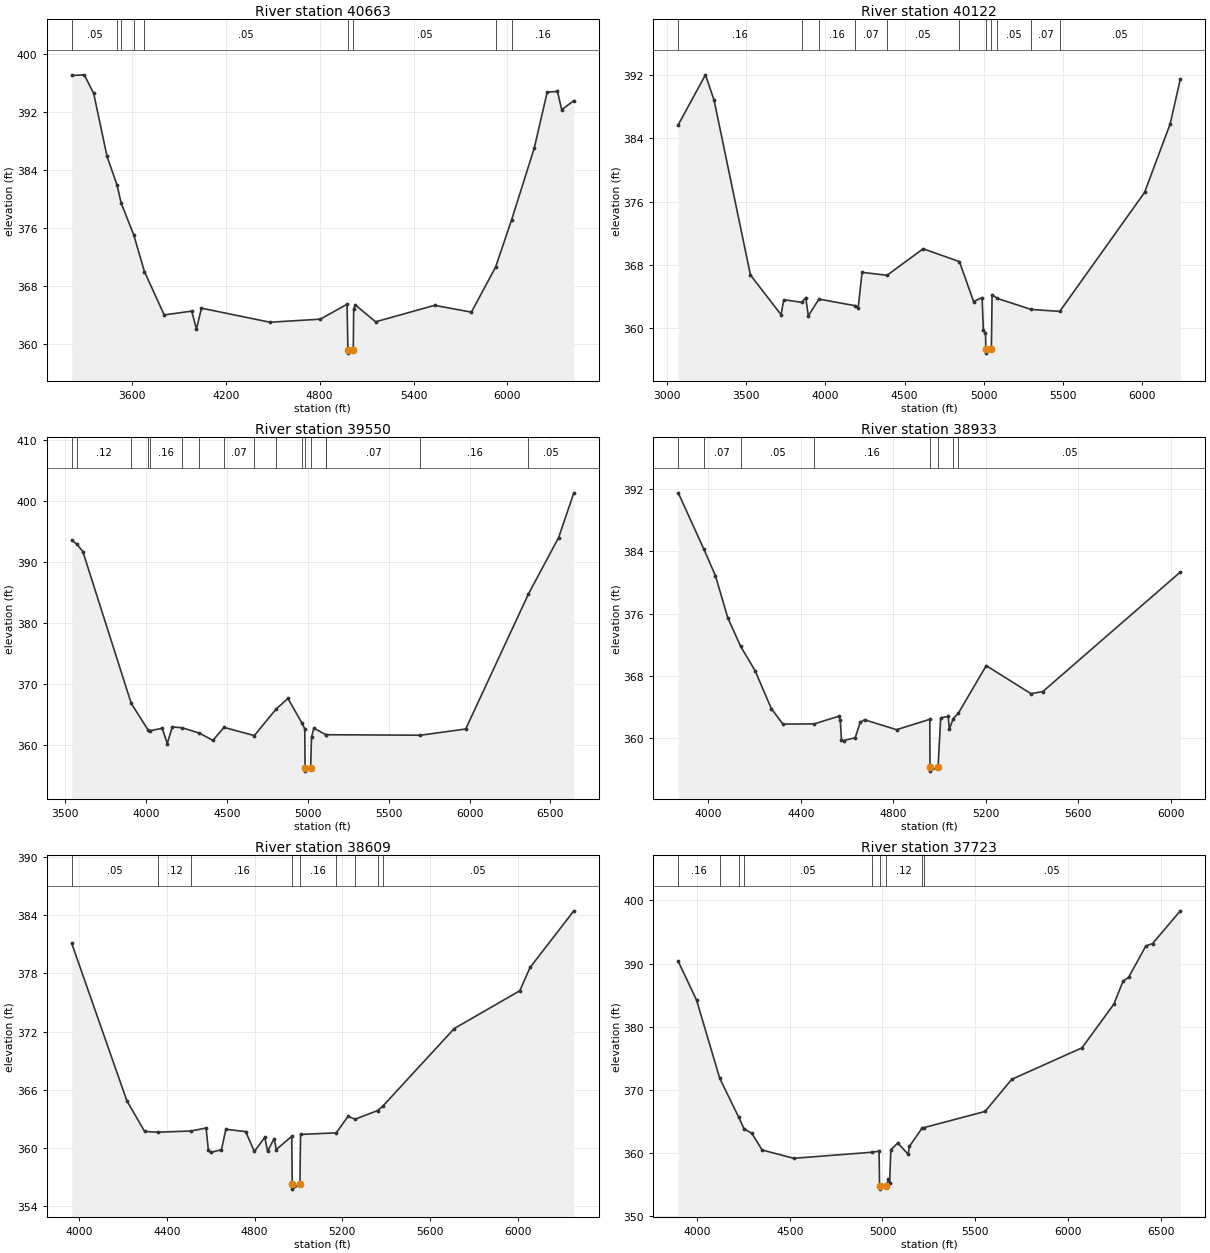
Type RM Length L Ch R = 1,40663,541,541,541
BEGIN DESCRIPTION:
South Twin Creek40663.31
END DESCRIPTION:
XS GIS Cut Line= 3
      2737901.01      6815936.00      2736232.69      6816567.65
      2734850.76      6816911.66
#Sta/Elev= 30
  3216.1  396.98  3295.9  397.07  3356.2  394.50  3441.4  385.82  3505.9  381.85
  3531.0  379.43  3612.6  374.97  3680.3  369.95  3806.7  363.97  3982.3  364.49
  4012.7  362.02  4044.8  364.90  4482.4  362.96  4804.0  363.38  4975.1  365.44
  4980.5  359.20  4981.2  358.70  5014.9  359.20  5017.2  364.78  5027.5  365.35
  5157.5  363.02  5534.5  365.29  5769.5  364.35  5924.3  370.57  6026.9  377.11
  6171.4  386.99  6253.8  394.68  6319.3  394.79  6346.6  392.26  6424.1  393.52
#Mann=9,-1,0
  3216.1    0.05       0  3505.9    0.07       0  3531.0    0.12       0
  3612.6    0.07       0  3680.3    0.05       0  4980.5    0.05       0
  5014.9    0.05       0  5924.3    0.12       0  6026.9    0.16       0
Bank Sta=4980.5,5014.9
Exp/Cntr=0.3,0.1

Type RM Length L Ch R = 1,40122,572,572,572
BEGIN DESCRIPTION:
South Twin Creek40122.17
END DESCRIPTION:
XS GIS Cut Line= 3
      2737769.75      6815443.01      2735975.85      6816145.94
      2734790.28      6816504.82
#Sta/Elev= 30
  3073.3  385.73  3244.9  392.07  3299.1  388.87  3528.4  366.70  3721.7  361.66
  3738.6  363.56  3853.2  363.23  3876.9  363.84  3893.6  361.52  3960.5  363.64
  4189.2  362.80  4207.9  362.56  4232.3  367.03  4389.9  366.66  4617.5  370.02
  4846.2  368.39  4935.4  363.33  4989.1  363.84  4997.2  359.66  5010.3  359.28
  5013.1  357.29  5013.8  356.79  5047.5  357.29  5052.1  364.19  5084.6  363.73
  5297.6  362.33  5478.6  362.08  6013.3  377.16  6174.5  385.83  6238.7  391.53
#Mann=11,-1,0
  3073.3    0.16       0  3853.2    0.12       0  3960.5    0.16       0
  4189.2    0.07       0  4389.9    0.05       0  4846.2    0.16       0
  5013.1    0.07       0  5047.5    0.16       0  5084.6    0.05       0
  5297.6    0.07       0  5478.6    0.05       0
Bank Sta=5013.1,5047.5
Exp/Cntr=0.3,0.1

Type RM Length L Ch R = 1,39550,617,617,617
BEGIN DESCRIPTION:
South Twin Creek39550.061
END DESCRIPTION:
XS GIS Cut Line= 3
      2737599.18      6815194.79      2736217.89      6815667.07
      2734623.39      6816069.91
#Sta/Elev= 30
  3540.2  393.62  3571.1  393.01  3609.0  391.75  3907.7  366.88  4013.2  362.46
  4023.0  362.37  4099.4  362.79  4130.7  360.29  4162.0  363.02  4224.1  362.86
  4329.6  361.99  4412.4  360.80  4481.9  362.93  4669.0  361.59  4802.9  365.92
  4876.8  367.68  4962.3  363.70  4980.9  362.70  4982.8  356.26  4983.5  355.76
  5017.2  356.26  5022.6  361.36  5037.3  362.80  5110.6  361.74  5114.4  361.73
  5696.3  361.65  5976.0  362.67  6363.5  384.79  6550.6  394.07  6644.6  401.40
#Mann=17,-1,0
  3540.2    0.05       0  3571.1    0.12       0  3907.7    0.16       0
  4013.2    0.07       0  4023.0    0.16       0  4224.1    0.12       0
  4329.6    0.16       0  4481.9    0.07       0  4669.0    0.16       0
  4802.9    0.05       0  4962.3    0.07       0  4982.8    0.07       0
  5017.2    0.07       0  5110.6    0.16       0  5114.4    0.07       0
  5696.3    0.16       0  6363.5    0.05       0
Bank Sta=4982.8,5017.2
Exp/Cntr=0.3,0.1

Type RM Length L Ch R = 1,38933,324,324,324
BEGIN DESCRIPTION:
South Twin Creek38932.5
END DESCRIPTION:
XS GIS Cut Line= 3
      2737445.45      6814979.85      2736317.40      6815119.39
      2735302.65      6815318.78
#Sta/Elev= 30
  3869.7  391.55  3980.5  384.29  4030.4  380.88  4084.2  375.42  4139.8  371.75
  4201.7  368.65  4272.2  363.75  4322.3  361.75  4457.9  361.78  4564.4  362.77
  4570.4  362.22  4575.5  359.68  4584.6  359.62  4634.9  360.00  4656.5  361.98
  4675.2  362.31  4813.6  361.03  4957.4  362.37  4958.2  356.19  4959.0  355.69
  4993.0  356.19  5004.5  362.55  5036.9  362.75  5042.0  361.10  5058.7  362.46
  5080.8  363.15  5201.4  369.28  5395.0  365.67  5446.0  365.94  6040.5  381.34
#Mann=8,-1,0
  3869.7    0.05       0  3980.5    0.07       0  4139.8    0.05       0
  4457.9    0.16       0  4958.2    0.07       0  4993.0    0.16       0
  5058.7    0.07       0  5080.8    0.05       0
Bank Sta=4958.2,4993
Exp/Cntr=0.3,0.1

Type RM Length L Ch R = 1,38609,886,886,886
BEGIN DESCRIPTION:
South Twin Creek38608.93
END DESCRIPTION:
XS GIS Cut Line= 3
      2737257.90      6814892.29      2736222.89      6814826.21
      2735007.04      6815135.16
#Sta/Elev= 30
  3965.5  381.09  4217.0  364.85  4298.1  361.68  4358.0  361.61  4509.8  361.73
  4578.6  362.04  4588.7  359.81  4598.7  359.52  4648.8  359.80  4668.8  361.91
  4759.0  361.67  4799.1  359.62  4846.6  361.08  4859.2  359.64  4889.3  360.95
  4899.3  359.82  4969.4  361.18  4972.0  356.23  4972.8  355.73  5006.9  356.23
  5009.7  361.38  5173.1  361.54  5226.4  363.25  5258.5  362.95  5361.3  363.84
  5384.0  364.27  5711.3  372.31  6010.5  376.21  6057.2  378.61  6257.1  384.46
#Mann=9,-1,0
  3965.5    0.05       0  4358.0    0.12       0  4509.8    0.16       0
  4972.0    0.07       0  5006.9    0.16       0  5173.1    0.12       0
  5258.5    0.16       0  5361.3    0.12       0  5384.0    0.05       0
Bank Sta=4972,5006.9
Exp/Cntr=0.3,0.1

Type RM Length L Ch R = 1,37723,550,550,550
BEGIN DESCRIPTION:
South Twin Creek37723.412
END DESCRIPTION:
XS GIS Cut Line= 3
      2736626.02      6813310.98      2735876.00      6814111.00
      2734576.04      6815060.97
#Sta/Elev= 30
  3899.1  390.34  3998.1  384.19  4123.1  371.80  4225.7  365.63  4254.4  363.81
  4295.5  363.13  4351.7  360.47  4521.7  359.16  4942.4  360.12  4981.8  360.28
  4984.5  354.78  4985.4  354.28  5021.7  354.78  5032.4  355.89  5038.6  355.31
  5045.3  360.51  5082.4  361.58  5139.0  359.80  5145.2  361.04  5213.4  363.93
  5221.4  364.00  5553.1  366.58  5697.3  371.67  6075.7  376.65  6247.2  383.55
  6297.3  387.21  6326.7  387.80  6420.1  392.78  6456.4  393.16  6605.8  398.34
#Mann=9,-1,0
  3899.1    0.16       0  4123.1    0.05       0  4225.7    0.07       0
  4254.4    0.05       0  4942.4    0.12       0  4984.5    0.07       0
  5021.7    0.12       0  5213.4    0.16       0  5221.4    0.05       0
Bank Sta=4984.5,5021.7
Exp/Cntr=0.3,0.1

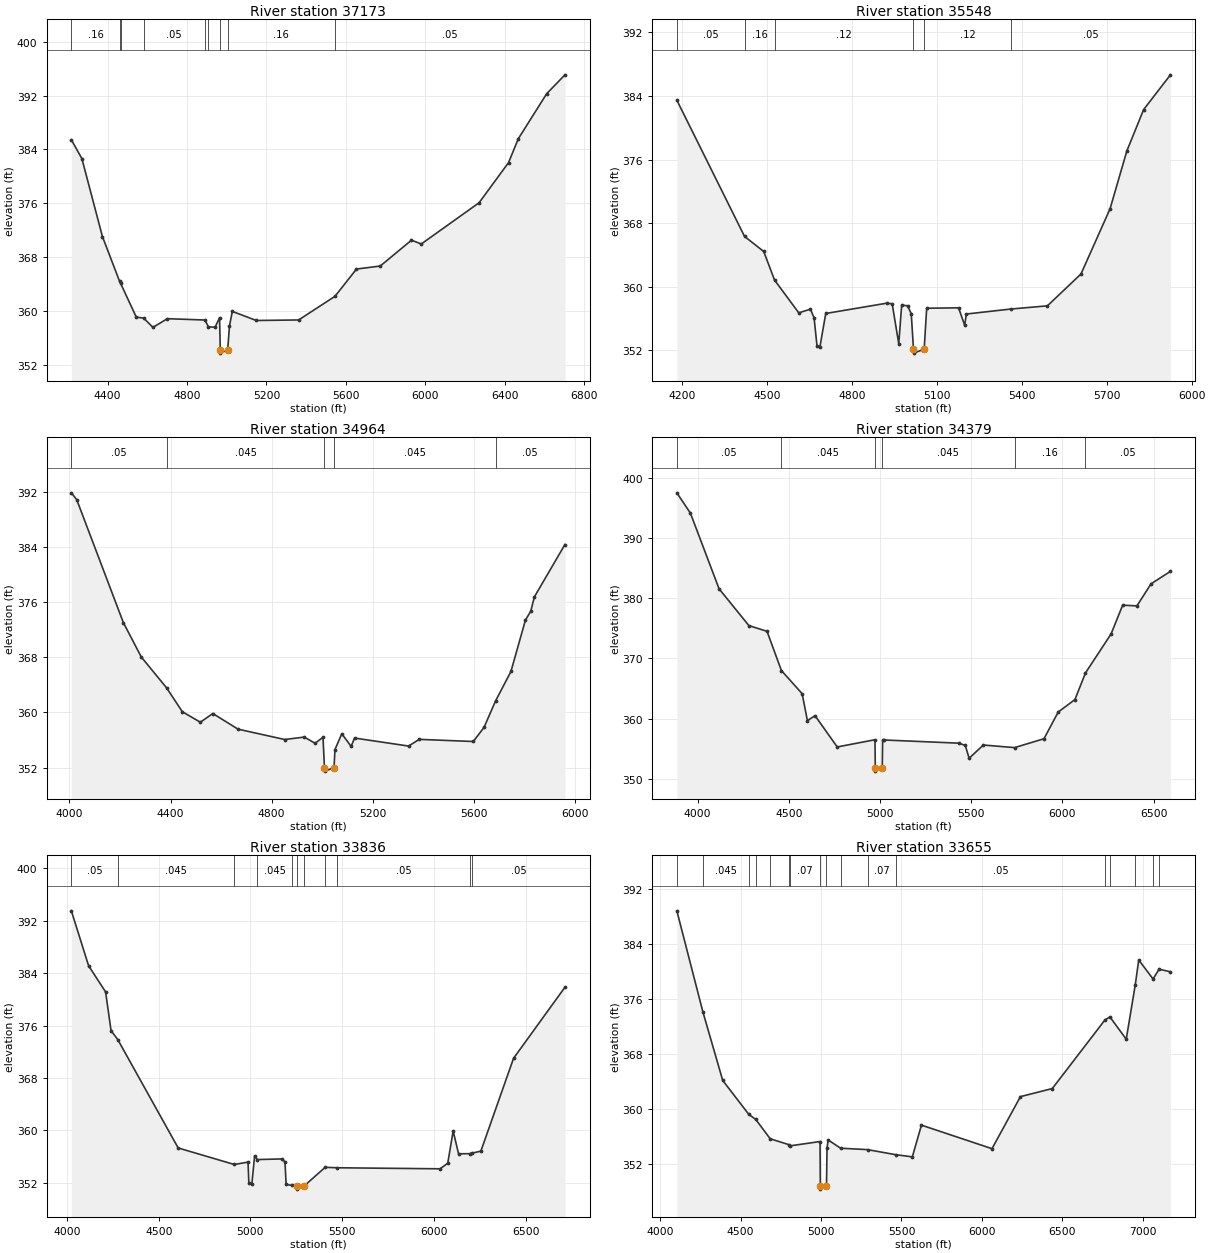
Type RM Length L Ch R = 1,37173,1625,1625,1625
BEGIN DESCRIPTION:
South Twin Creek37173.031
END DESCRIPTION:
XS GIS Cut Line= 3
      2736425.98      6813261.01      2735726.00      6813611.00
      2734426.03      6814710.97
#Sta/Elev= 30
  4217.4  385.44  4270.5  382.64  4373.9  371.08  4460.2  364.45  4465.6  364.13
  4544.4  359.13  4581.8  358.98  4628.3  357.61  4700.9  358.90  4889.8  358.70
  4907.9  357.69  4941.3  357.63  4963.7  359.05  4967.4  354.29  4968.3  353.79
  5004.6  354.29  5013.7  357.83  5028.0  359.98  5148.9  358.63  5362.0  358.71
  5545.1  362.22  5653.2  366.26  5772.9  366.71  5930.1  370.54  5979.5  369.98
  6270.7  376.10  6418.9  382.05  6468.3  385.60  6611.2  392.28  6702.9  395.07
#Mann=9,-1,0
  4217.4    0.16       0  4460.2    0.05       0  4465.6    0.07       0
  4581.8    0.05       0  4889.8    0.12       0  4907.9    0.16       0
  4967.4    0.07       0  5004.6    0.16       0  5545.1    0.05       0
Bank Sta=4967.4,5004.6
Exp/Cntr=0.3,0.1

Type RM Length L Ch R = 1,35548,584,584,584
BEGIN DESCRIPTION:
South Twin Creek35548.37
END DESCRIPTION:
XS GIS Cut Line= 3
      2735676.04      6812310.99      2734876.00      6812511.00
      2734076.03      6812960.98
#Sta/Elev= 30
  4182.6  383.47  4421.5  366.33  4489.3  364.43  4527.4  360.84  4613.0  356.71
  4654.2  357.17  4667.1  356.08  4677.4  352.56  4687.7  352.43  4708.3  356.63
  4924.8  357.93  4942.8  357.84  4966.0  352.82  4976.3  357.68  4997.0  357.60
  5010.1  356.60  5018.0  352.14  5019.0  351.64  5055.7  352.14  5064.6  357.29
  5177.1  357.34  5198.8  355.14  5204.5  356.56  5361.6  357.19  5490.7  357.59
  5609.3  361.60  5711.9  369.80  5771.2  377.08  5830.5  382.29  5925.1  386.66
#Mann=6,-1,0
  4182.6    0.05       0  4421.5    0.16       0  4527.4    0.12       0
  5018.0    0.07       0  5055.7    0.12       0  5361.6    0.05       0
Bank Sta=5018,5055.7
Exp/Cntr=0.3,0.1

Type RM Length L Ch R = 1,34964,585,585,585
BEGIN DESCRIPTION:
South Twin Creek34964.343
END DESCRIPTION:
XS GIS Cut Line= 3
      2735475.97      6811361.03      2734726.00      6812011.00
      2733976.00      6812611.00
#Sta/Elev= 30
  4007.6  391.87  4028.9  390.88  4213.2  373.05  4284.4  368.04  4384.1  363.58
  4446.8  360.10  4518.0  358.58  4567.4  359.84  4667.2  357.57  4851.4  356.07
  4929.3  356.42  4972.0  355.52  5003.2  356.39  5009.1  351.98  5010.1  351.48
  5047.0  351.98  5050.5  354.61  5077.7  356.90  5114.5  355.07  5128.1  356.28
  5341.8  355.12  5384.2  356.09  5597.9  355.78  5640.3  357.82  5686.3  361.69
  5746.8  365.94  5804.4  373.42  5825.2  374.68  5839.6  376.77  5960.5  384.37
#Mann=5,-1,0
  4007.6    0.05       0  4384.1   0.045       0  5009.1   0.045       0
  5047.0   0.045       0  5686.3    0.05       0
Bank Sta=5009.1,5047
Exp/Cntr=0.3,0.1

Type RM Length L Ch R = 1,34379,543,543,543
BEGIN DESCRIPTION:
South Twin Creek34378.913
END DESCRIPTION:
XS GIS Cut Line= 3
      2735600.85      6810771.31      2734726.00      6811461.00
      2733576.00      6812561.00
#Sta/Elev= 30
  3886.5  397.55  3960.7  394.18  4117.9  381.59  4281.4  375.47  4380.8  374.52
  4459.5  368.00  4573.2  364.15  4602.1  359.67  4644.0  360.49  4765.6  355.29
  4972.5  356.49  4974.2  351.77  4975.2  351.27  5012.4  351.77  5014.5  356.39
  5021.7  356.45  5431.9  355.92  5467.4  355.55  5488.5  353.41  5566.5  355.61
  5737.6  355.18  5898.9  356.66  5976.6  361.09  6068.4  363.17  6126.2  367.60
  6266.5  374.08  6330.1  378.87  6408.1  378.75  6485.8  382.42  6591.9  384.49
#Mann=6,-1,0
  3886.5    0.05       0  4459.5   0.045       0  4974.2   0.045       0
  5012.4   0.045       0  5737.6    0.16       0  6126.2    0.05       0
Bank Sta=4974.2,5012.4
Exp/Cntr=0.3,0.1

Type RM Length L Ch R = 1,33836,181,181,181
BEGIN DESCRIPTION:
South Twin Creek33835.851
END DESCRIPTION:
XS GIS Cut Line= 3
      2735376.00      6810411.00      2734576.00      6810961.00
      2733576.00      6812361.01
#Sta/Elev= 30
  4023.6  393.50  4117.7  385.12  4210.3  381.13  4240.1  375.23  4276.9  373.85
  4606.1  357.32  4911.9  354.80  4987.0  355.16  4991.4  352.03  5007.9  351.84
  5022.7  356.11  5037.1  355.55  5173.8  355.65  5188.6  355.16  5194.7  351.75
  5228.1  351.60  5255.5  351.54  5256.5  351.04  5293.7  351.54  5407.6  354.37
  5472.7  354.30  6034.1  354.14  6075.9  354.99  6105.4  359.91  6134.9  356.43
  6196.2  356.45  6208.9  356.53  6256.5  356.84  6434.7  371.00  6714.9  381.84
#Mann=11,-1,0
  4023.6    0.05       0  4276.9   0.045       0  4911.9    0.07       0
  5037.1   0.045       0  5228.1    0.07       0  5255.5    0.07       0
  5293.7    0.07       0  5407.6   0.045       0  5472.7    0.05       0
  6196.2    0.16       0  6208.9    0.05       0
Bank Sta=5255.5,5293.7
Exp/Cntr=0.3,0.1

Type RM Length L Ch R = 1,33655,299,299,299
BEGIN DESCRIPTION:
South Twin Creek33654.77
END DESCRIPTION:
XS GIS Cut Line= 3
      2735273.69      6810304.65      2734504.34      6810814.69
      2732940.76      6812284.18
#Sta/Elev= 30
  4103.5  388.88  4265.0  374.20  4388.7  364.18  4551.2  359.23  4594.1  358.50
  4684.1  355.68  4801.0  354.82  4806.7  354.65  4993.7  355.28  4995.6  348.85
  4996.6  348.35  5033.9  348.85  5037.1  354.28  5044.0  355.51  5121.6  354.31
  5289.8  354.10  5465.7  353.36  5567.6  353.05  5624.2  357.67  6062.8  354.24
  6239.6  361.82  6437.8  363.00  6764.8  372.98  6796.0  373.43  6897.5  370.18
  6953.4  378.07  6975.2  381.72  7064.4  378.95  7101.6  380.38  7172.3  380.00
#Mann=17,-1,0
  4103.5    0.05       0  4265.0   0.045       0  4551.2    0.05       0
  4594.1   0.045       0  4684.1    0.05       0  4801.0   0.045       0
  4806.7    0.07       0  4995.6    0.07       0  5033.9    0.07       0
  5121.6   0.045       0  5289.8    0.07       0  5465.7    0.05       0
  6764.8    0.07       0  6796.0    0.05       0  6953.4    0.07       0
  7064.4    0.05       0  7101.6    0.07       0
Bank Sta=4995.6,5033.9
Exp/Cntr=0.3,0.1