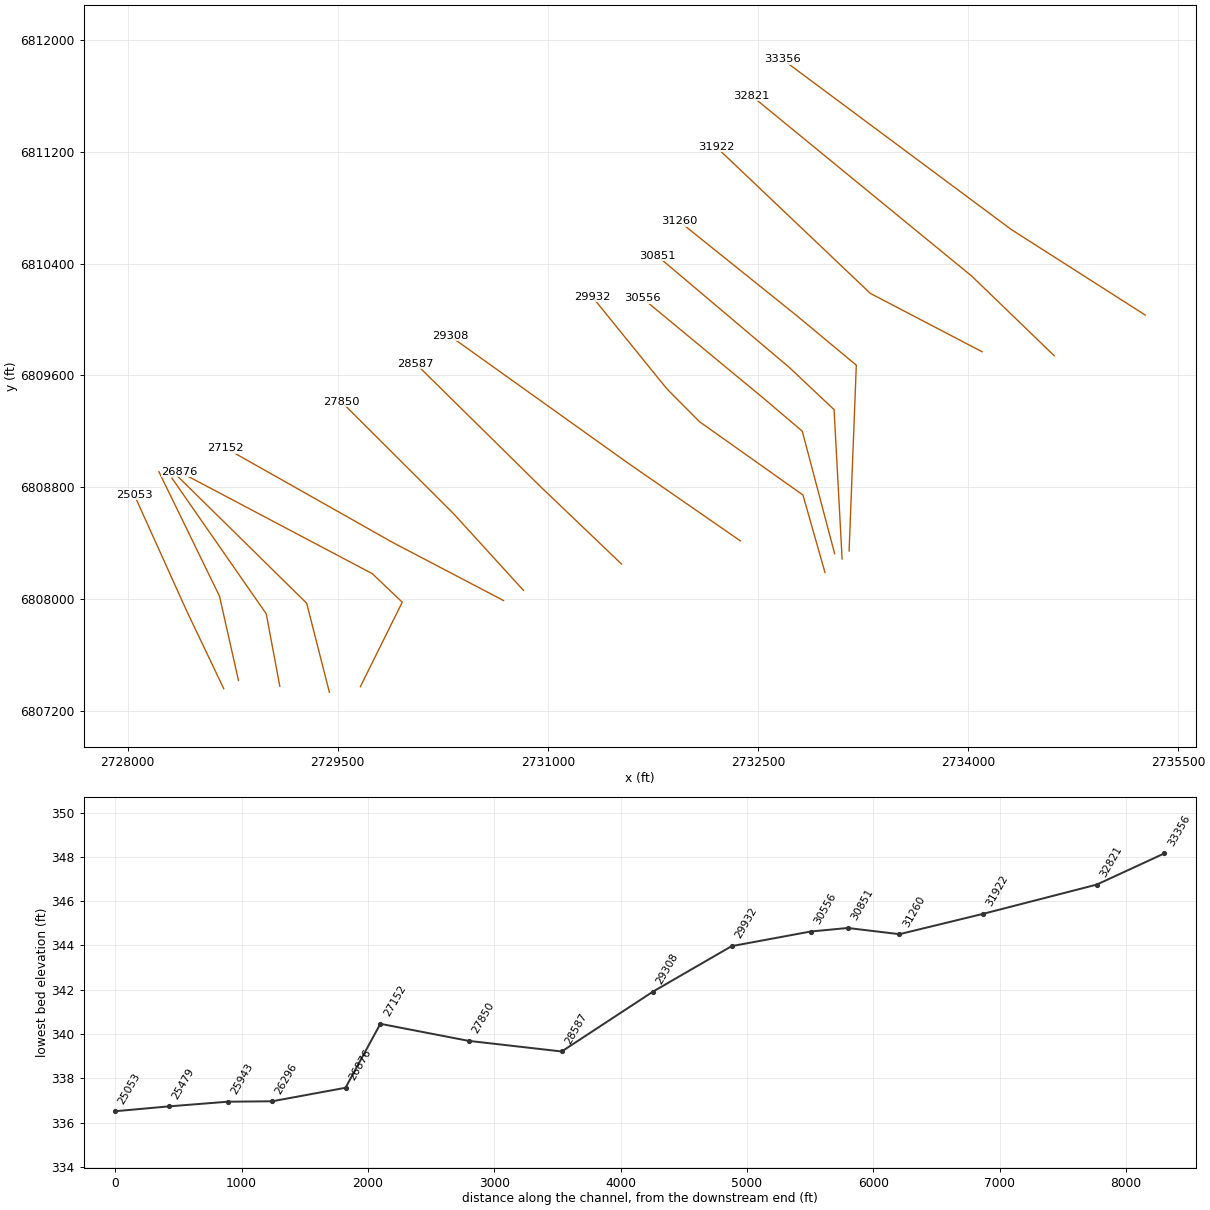
HEC-RAS study South Twin Creek.prj: South Twin Creek Base Level Engineering

--- South Twin Creek.g01 (geometry) --- (continued)

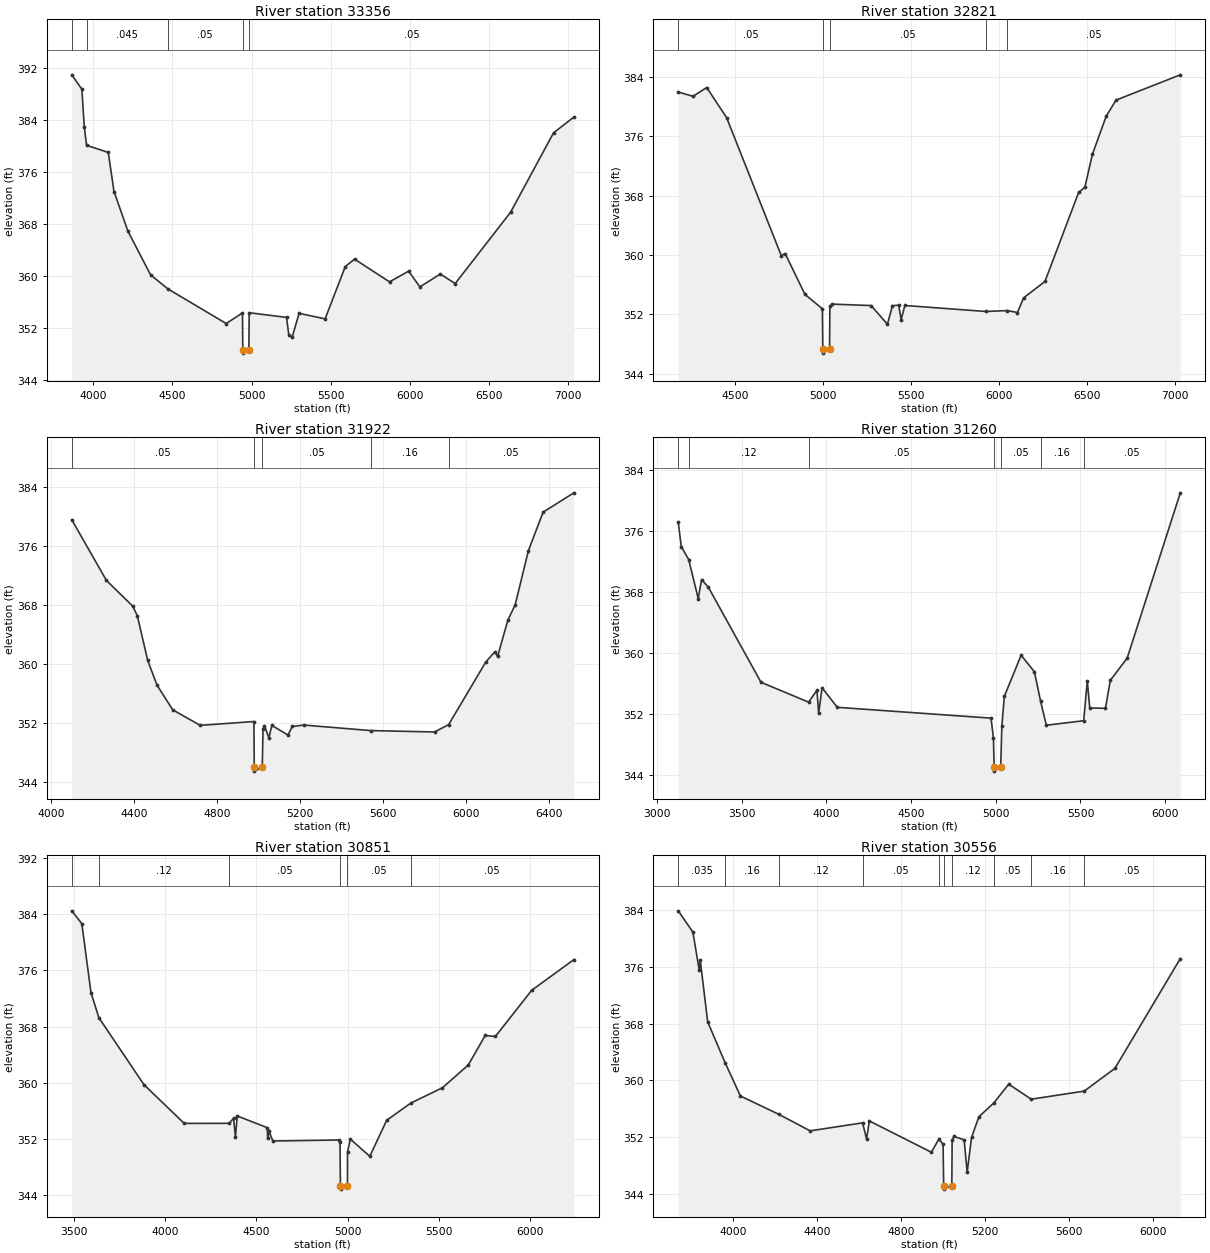
Type RM Length L Ch R = 1,33356,535,535,535
BEGIN DESCRIPTION:
South Twin Creek33356.221
END DESCRIPTION:
XS GIS Cut Line= 3
      2735265.31      6810031.84      2734308.47      6810644.36
      2732675.98      6811861.02
#Sta/Elev= 30
  3863.9  391.00  3927.8  388.79  3943.0  382.96  3957.4  380.16  4094.4  379.05
  4130.8  373.04  4218.7  366.93  4361.8  360.21  4470.5  358.06  4839.4  352.72
  4942.5  354.35  4944.5  348.66  4945.5  348.16  4982.8  348.66  4984.8  354.38
  5220.8  353.66  5235.4  350.90  5256.3  350.61  5300.1  354.28  5464.5  353.44
  5592.0  361.49  5650.4  362.63  5871.4  359.13  5992.3  360.78  6063.2  358.36
  6192.5  360.33  6286.4  358.87  6636.7  369.86  6907.7  382.07  7036.0  384.49
#Mann=5,-1,0
  3863.9    0.05       0  3957.4   0.045       0  4470.5    0.05       0
  4944.5    0.05       0  4982.8    0.05       0
Bank Sta=4944.5,4982.8
Exp/Cntr=0.3,0.1

Type RM Length L Ch R = 1,32821,899,899,899
BEGIN DESCRIPTION:
South Twin Creek32821.331
END DESCRIPTION:
XS GIS Cut Line= 3
      2734614.91      6809741.08      2734026.00      6810311.00
      2732453.62      6811602.01
#Sta/Elev= 30
  4176.0  381.98  4260.0  381.40  4337.9  382.59  4451.1  378.52  4762.1  359.88
  4783.4  360.19  4896.6  354.67  4995.5  352.73  4997.9  347.25  4998.9  346.75
  5036.2  347.25  5037.9  353.06  5052.2  353.36  5272.5  353.17  5365.1  350.64
  5393.8  353.15  5428.9  353.22  5443.3  351.28  5464.1  353.18  5924.8  352.37
  6046.1  352.49  6104.2  352.23  6139.3  354.21  6260.6  356.42  6452.2  368.44
  6487.3  369.12  6530.4  373.58  6608.6  378.71  6664.6  380.89  7030.0  384.30
#Mann=5,-1,0
  4176.0    0.05       0  4997.9    0.05       0  5036.2    0.05       0
  5924.8    0.16       0  6046.1    0.05       0
Bank Sta=4997.9,5036.2
Exp/Cntr=0.3,0.1

Type RM Length L Ch R = 1,31922,662,662,662
BEGIN DESCRIPTION:
South Twin Creek31921.521
END DESCRIPTION:
XS GIS Cut Line= 3
      2734100.50      6809769.07      2733302.73      6810186.75
      2732201.01      6811235.99
#Sta/Elev= 30
  4099.5  379.59  4266.8  371.34  4393.6  367.85  4415.6  366.55  4465.8  360.47
  4510.9  357.11  4586.5  353.76  4718.9  351.65  4978.1  352.17  4979.9  345.93
  4980.9  345.43  5018.4  345.93  5022.0  351.11  5029.0  351.62  5050.4  349.95
  5064.5  351.65  5142.2  350.34  5163.3  351.50  5219.9  351.69  5541.1  350.94
  5849.6  350.75  5917.5  351.75  6097.1  360.28  6139.6  361.63  6153.7  361.02
  6203.1  365.95  6238.3  368.02  6302.2  375.39  6373.0  380.62  6521.4  383.25
#Mann=5,-1,0
  4099.5    0.05       0  4979.9    0.05       0  5018.4    0.05       0
  5541.1    0.16       0  5917.5    0.05       0
Bank Sta=4979.9,5018.4
Exp/Cntr=0.3,0.1

Type RM Length L Ch R = 1,31260,409,409,409
BEGIN DESCRIPTION:
Mapping XS 9141b9f7
END DESCRIPTION:
XS GIS Cut Line= 4
      2733150.81      6808343.07      2733202.38      6809672.77
      2732778.07      6810026.69      2731937.20      6810703.10
#Sta/Elev= 30
  3126.6  377.23  3144.5  373.99  3188.4  372.29  3244.6  367.17  3264.6  369.67
  3304.7  368.65  3614.9  356.18  3895.8  353.57  3945.1  355.13  3955.2  352.10
  3975.2  355.46  4065.2  352.89  4972.2  351.47  4986.5  348.82  4990.5  345.01
  4991.5  344.51  5029.2  345.01  5036.2  350.50  5050.6  354.32  5149.8  359.74
  5228.2  357.55  5264.2  353.73  5298.6  350.54  5518.8  351.13  5540.2  356.35
  5554.6  352.81  5647.3  352.76  5676.1  356.44  5775.3  359.34  6089.0  381.06
#Mann=7,-1,0
  3126.6   0.035       0  3188.4    0.12       0  3895.8    0.05       0
  4990.5    0.05       0  5029.2    0.05       0  5264.2    0.16       0
  5518.8    0.05       0
Bank Sta=4990.5,5029.2
Exp/Cntr=0.3,0.1

Type RM Length L Ch R = 1,30851,295,295,295
BEGIN DESCRIPTION:
South Twin Creek30851.379
END DESCRIPTION:
XS GIS Cut Line= 4
      2733101.00      6808285.96      2733043.56      6809354.97
      2732723.06      6809657.67      2731777.97      6810457.78
#Sta/Elev= 30
  3488.6  384.51  3543.7  382.68  3593.8  372.84  3636.8  369.27  3884.2  359.69
  4104.5  354.17  4350.5  354.18  4374.9  354.91  4384.9  352.26  4395.0  355.23
  4559.2  353.56  4561.7  352.02  4568.9  353.06  4590.0  351.66  4950.8  351.80
  4957.7  351.56  4959.8  345.29  4960.8  344.79  4998.5  345.29  4998.8  350.10
  5014.4  351.92  5120.9  349.48  5213.2  354.61  5344.6  357.06  5518.7  359.26
  5660.4  362.51  5752.7  366.72  5808.6  366.58  6007.5  373.17  6238.3  377.54
#Mann=6,-1,0
  3488.6   0.035       0  3636.8    0.12       0  4350.5    0.05       0
  4959.8    0.07       0  4998.5    0.05       0  5344.6    0.05       0
Bank Sta=4959.8,4998.5
Exp/Cntr=0.3,0.1

Type RM Length L Ch R = 1,30556,624,624,624
BEGIN DESCRIPTION:
Mapping XS 0f6ca603
END DESCRIPTION:
XS GIS Cut Line= 4
      2733047.60      6808323.74      2732816.47      6809200.43
      2732546.54      6809430.47      2731676.69      6810151.44
#Sta/Elev= 30
  3738.7  383.93  3808.6  380.92  3838.6  375.58  3843.7  376.94  3878.9  368.26
  3962.1  362.47  4034.9  357.78  4218.1  355.19  4366.7  352.86  4616.7  353.99
  4635.6  351.71  4648.9  354.26  4944.2  349.84  4979.6  351.68  5000.0  350.98
  5002.9  345.13  5003.9  344.63  5041.6  345.13  5043.1  351.51  5050.9  352.08
  5100.4  351.59  5114.7  347.03  5135.6  351.93  5170.7  354.85  5241.3  356.79
  5312.7  359.45  5419.8  357.33  5671.9  358.47  5818.0  361.67  6129.8  377.19
#Mann=10,-1,0
  3738.7   0.035       0  3962.1    0.16       0  4218.1    0.12       0
  4616.7    0.05       0  4979.6    0.12       0  5002.9    0.07       0
  5041.6    0.12       0  5241.3    0.05       0  5419.8    0.16       0
  5671.9    0.05       0
Bank Sta=5002.9,5041.6
Exp/Cntr=0.3,0.1

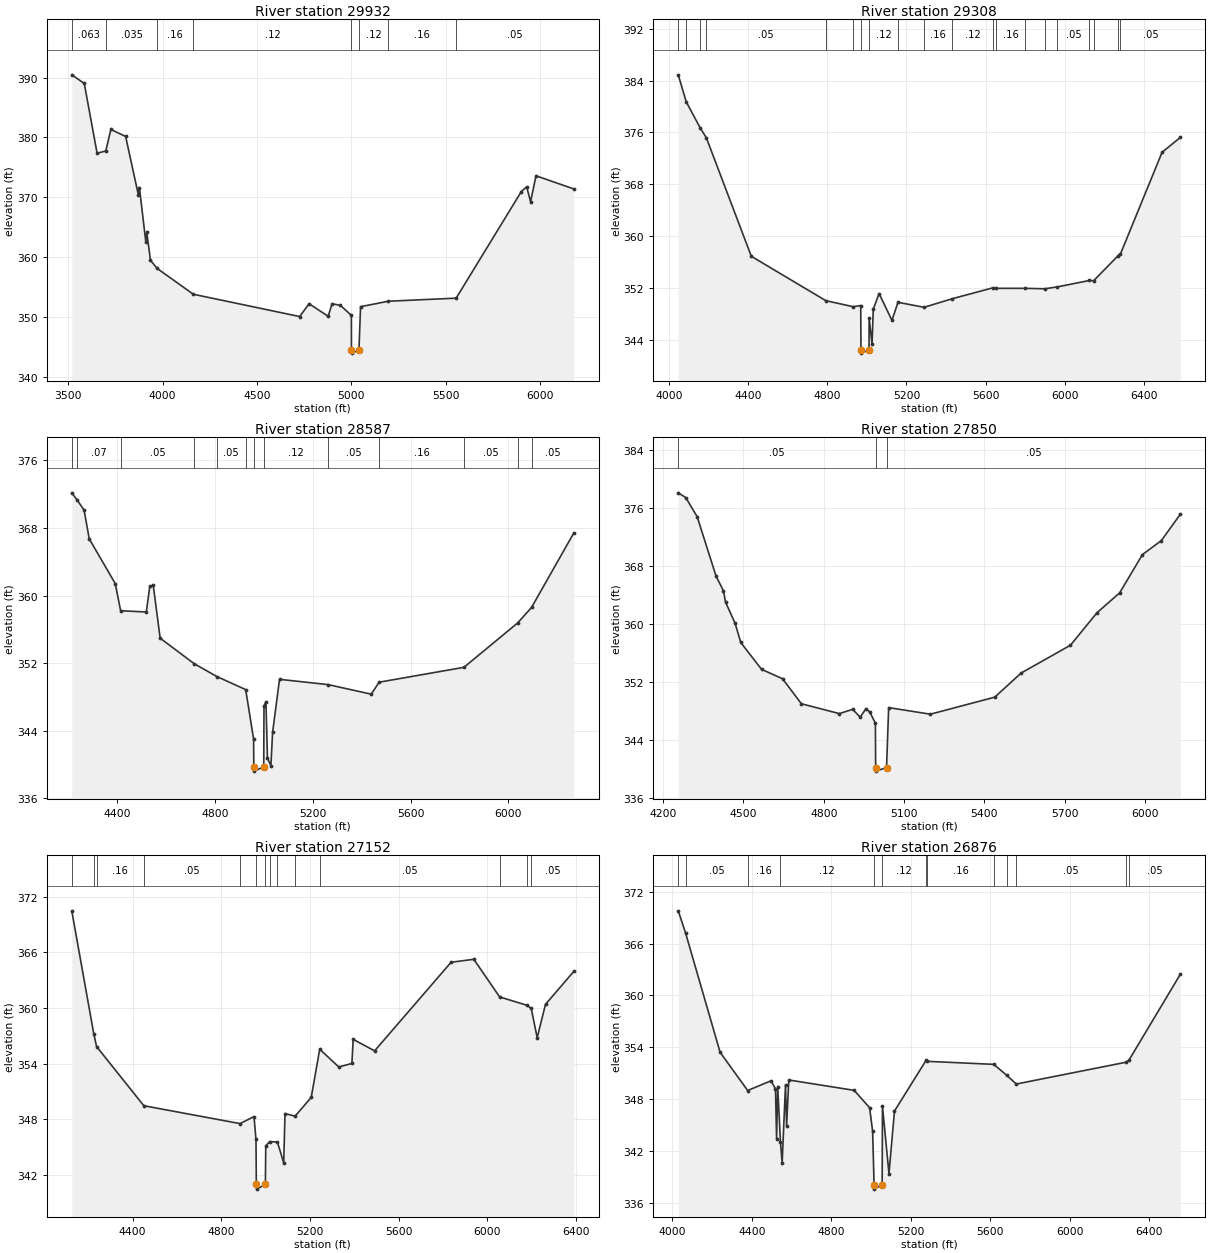
Type RM Length L Ch R = 1,29932,624,624,624
BEGIN DESCRIPTION:
South Twin Creek29932.02
END DESCRIPTION:
XS GIS Cut Line= 5
      2732978.37      6808189.69      2732821.44      6808743.65
      2732084.27      6809267.26      2731849.30      6809504.18
      2731316.18      6810163.58
#Sta/Elev= 30
  3518.3  390.45  3584.6  389.01  3652.5  377.36  3698.6  377.73  3725.6  381.33
  3803.8  380.16  3871.7  370.35  3876.9  371.63  3910.8  362.55  3916.0  364.16
  3935.4  359.48  3971.0  358.11  4162.9  353.80  4726.3  350.08  4776.5  352.22
  4877.4  350.12  4898.3  352.22  4942.6  351.94  5000.6  350.28  5001.0  344.47
  5002.0  343.97  5040.7  344.47  5049.2  351.73  5197.3  352.64  5555.9  353.15
  5901.0  370.93  5929.7  371.76  5950.6  369.26  5979.3  373.59  6179.9  371.39
#Mann=8,-1,0
  3518.3   0.063       0  3698.6   0.035       0  3971.0    0.16       0
  4162.9    0.12       0  5001.0    0.07       0  5040.7    0.12       0
  5197.3    0.16       0  5555.9    0.05       0
Bank Sta=5001,5040.7
Exp/Cntr=0.3,0.1

Type RM Length L Ch R = 1,29308,721,721,721
BEGIN DESCRIPTION:
South Twin Creek29307.9
END DESCRIPTION:
XS GIS Cut Line= 3
      2732374.89      6808415.14      2731573.62      6808971.23
      2730300.17      6809882.77
#Sta/Elev= 30
  4044.6  384.90  4084.9  380.74  4155.3  376.73  4187.1  375.16  4414.5  356.87
  4791.9  350.01  4930.6  349.08  4968.3  349.26  4969.6  342.41  4970.6  341.91
  5010.2  342.41  5010.9  347.32  5025.6  343.32  5031.8  348.71  5061.3  351.11
  5126.4  346.97  5156.8  349.76  5289.2  348.99  5431.0  350.31  5637.5  352.00
  5652.1  351.92  5800.3  351.92  5899.7  351.85  5963.2  352.14  6126.0  353.13
  6147.4  353.10  6271.2  356.96  6282.8  357.21  6493.7  372.93  6586.0  375.23
#Mann=20,-1,0
  4044.6    0.05       0  4084.9    0.07       0  4155.3   0.063       0
  4187.1    0.05       0  4791.9    0.07       0  4930.6    0.16       0
  4969.6    0.07       0  5010.2    0.12       0  5156.8    0.12       0
  5289.2    0.16       0  5431.0    0.12       0  5637.5   0.035       0
  5652.1    0.16       0  5800.3    0.05       0  5899.7    0.07       0
  5963.2    0.05       0  6126.0   0.035       0  6147.4    0.05       0
  6271.2    0.07       0  6282.8    0.05       0
Bank Sta=4969.6,5010.2
Exp/Cntr=0.3,0.1

Type RM Length L Ch R = 1,28587,737,737,737
BEGIN DESCRIPTION:
South Twin Creek28586.95
END DESCRIPTION:
XS GIS Cut Line= 3
      2731525.87      6808249.70      2730954.21      6808797.35
      2730056.96      6809683.74
#Sta/Elev= 30
  4214.5  372.16  4235.1  371.36  4264.9  370.12  4286.0  366.71  4392.2  361.42
  4414.3  358.20  4519.3  358.05  4533.5  361.09  4547.6  361.22  4575.9  354.95
  4715.6  351.92  4807.8  350.41  4925.7  348.86  4958.0  342.99  4958.8  339.71
  4959.8  339.21  4999.4  339.71  5000.5  346.92  5008.4  347.42  5014.6  340.77
  5028.7  339.85  5035.7  343.82  5064.0  350.08  5263.3  349.45  5438.9  348.32
  5471.2  349.74  5818.1  351.50  6037.5  356.75  6094.5  358.59  6267.4  367.42
#Mann=13,-1,0
  4214.5    0.16       0  4235.1    0.07       0  4414.3    0.05       0
  4715.6    0.16       0  4807.8    0.05       0  4925.7    0.12       0
  4958.8    0.07       0  4999.4    0.12       0  5263.3    0.05       0
  5471.2    0.16       0  5818.1    0.05       0  6037.5    0.16       0
  6094.5    0.05       0
Bank Sta=4958.8,4999.4
Exp/Cntr=0.3,0.1

Type RM Length L Ch R = 1,27850,698,698,698
BEGIN DESCRIPTION:
South Twin Creek27850.257
END DESCRIPTION:
XS GIS Cut Line= 3
      2730825.99      6808061.01      2730326.00      6808611.00
      2729525.98      6809411.02
#Sta/Elev= 30
  4256.7  378.11  4284.7  377.46  4327.3  374.82  4398.3  366.57  4425.6  364.58
  4433.4  363.01  4469.2  360.09  4490.2  357.45  4567.9  353.74  4646.3  352.44
  4716.5  348.99  4858.4  347.63  4907.8  348.22  4936.1  347.14  4957.8  348.32
  4972.0  347.85  4992.9  346.30  4993.8  340.19  4994.8  339.69  5034.5  340.19
  5042.4  348.46  5198.0  347.55  5438.4  349.90  5537.4  353.24  5721.2  357.07
  5820.2  361.55  5905.1  364.31  5989.9  369.58  6060.7  371.52  6131.4  375.15
#Mann=3,-1,0
  4256.7    0.05       0  4993.8    0.05       0  5034.5    0.05       0
Bank Sta=4993.8,5034.5
Exp/Cntr=0.3,0.1

Type RM Length L Ch R = 1,27152,276,276,276
BEGIN DESCRIPTION:
South Twin Creek27152.2
END DESCRIPTION:
XS GIS Cut Line= 3
      2730683.63      6807988.40      2729897.52      6808401.15
      2728700.13      6809079.16
#Sta/Elev= 30
  4126.1  370.49  4225.3  357.22  4238.1  355.84  4451.0  349.46  4885.1  347.53
  4947.9  348.29  4956.7  345.82  4958.4  340.96  4959.4  340.46  4999.1  340.96
  5000.8  345.12  5017.7  345.58  5053.3  345.55  5081.8  343.29  5087.6  348.62
  5133.0  348.33  5205.9  350.36  5244.1  355.56  5330.0  353.64  5389.2  354.02
  5395.0  356.62  5491.6  355.38  5836.5  364.94  5939.0  365.26  6055.4  361.20
  6176.9  360.31  6197.7  359.97  6224.7  356.80  6262.2  360.40  6390.0  363.96
#Mann=14,-1,0
  4126.1    0.16       0  4225.3    0.12       0  4238.1    0.16       0
  4451.0    0.05       0  4885.1    0.12       0  4958.4    0.07       0
  4999.1    0.12       0  5017.7    0.16       0  5053.3    0.05       0
  5133.0    0.12       0  5244.1    0.05       0  6055.4    0.12       0
  6176.9    0.16       0  6197.7    0.05       0
Bank Sta=4958.4,4999.1
Exp/Cntr=0.3,0.1

Type RM Length L Ch R = 1,26876,580,580,580
BEGIN DESCRIPTION:
South Twin Creek26875.54
END DESCRIPTION:
XS GIS Cut Line= 4
      2729661.36      6807372.08      2729960.42      6807976.61
      2729746.38      6808180.84      2728369.54      6808909.99
#Sta/Elev= 30
  4029.7  369.80  4066.4  367.25  4240.5  353.42  4379.3  348.99  4497.0  350.12
  4519.4  349.18  4525.0  343.43  4530.6  349.45  4544.6  343.00  4553.0  340.61
  4569.9  349.66  4575.4  344.88  4586.3  350.21  4915.6  349.01  4993.3  347.00
  5008.6  344.28  5015.9  338.07  5016.9  337.57  5056.6  338.07  5058.2  347.15
  5090.9  339.37  5118.6  346.61  5278.2  352.50  5284.2  352.37  5618.4  352.02
  5684.7  350.74  5731.9  349.74  6285.4  352.27  6299.0  352.49  6558.0  362.45
#Mann=13,-1,0
  4029.7    0.07       0  4066.4    0.05       0  4379.3    0.16       0
  4544.6    0.12       0  5015.9    0.07       0  5056.6    0.12       0
  5278.2    0.12       0  5284.2    0.16       0  5618.4    0.12       0
  5684.7    0.16       0  5731.9    0.05       0  6285.4    0.16       0
  6299.0    0.05       0
Bank Sta=5015.9,5056.6
Exp/Cntr=0.3,0.1

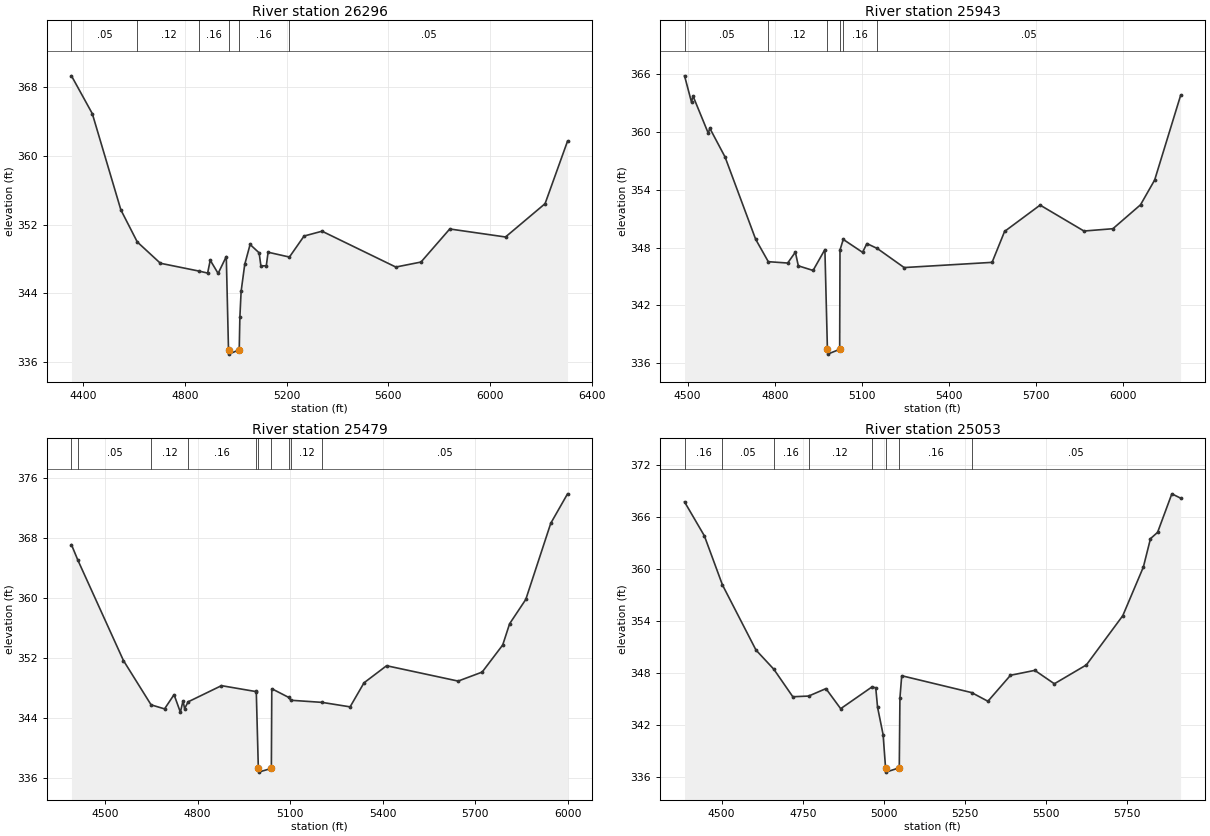
Type RM Length L Ch R = 1,26296,353,353,353
BEGIN DESCRIPTION:
South Twin Creek26296.38
END DESCRIPTION:
XS GIS Cut Line= 3
      2729440.04      6807332.23      2729278.04      6807969.23
      2728357.31      6808877.21
#Sta/Elev= 30
  4354.2  369.27  4436.1  364.88  4548.5  353.70  4613.0  349.98  4703.8  347.51
  4857.4  346.59  4889.5  346.37  4899.8  347.86  4930.8  346.33  4962.9  348.29
  4971.6  337.46  4972.6  336.96  5013.8  337.46  5016.3  341.23  5021.2  344.24
  5035.4  347.37  5056.5  349.69  5092.0  348.72  5099.0  347.20  5120.2  347.22
  5127.3  348.79  5211.1  348.23  5268.7  350.67  5339.4  351.23  5629.4  347.07
  5728.4  347.65  5841.5  351.49  6060.7  350.56  6216.3  354.43  6304.6  361.69
#Mann=6,-1,0
  4354.2    0.05       0  4613.0    0.12       0  4857.4    0.16       0
  4971.6    0.07       0  5013.8    0.16       0  5211.1    0.05       0
Bank Sta=4971.6,5013.8
Exp/Cntr=0.3,0.1

Type RM Length L Ch R = 1,25943,464,464,464
BEGIN DESCRIPTION:
South Twin Creek25942.57
END DESCRIPTION:
XS GIS Cut Line= 3
      2729086.08      6807375.89      2728989.39      6807893.19
      2728315.94      6808864.51
#Sta/Elev= 30
  4489.4  365.81  4513.4  363.08  4518.5  363.72  4571.2  359.85  4576.3  360.38
  4628.9  357.39  4734.2  348.86  4777.8  346.53  4844.6  346.39  4871.0  347.52
  4881.2  346.10  4932.0  345.62  4972.7  347.79  4981.4  337.44  4982.4  336.94
  5023.6  337.44  5024.7  347.74  5035.9  348.84  5102.4  347.50  5117.3  348.41
  5153.1  347.90  5245.6  345.92  5548.4  346.46  5591.5  349.67  5713.8  352.40
  5864.8  349.71  5964.4  349.95  6059.5  352.43  6108.2  355.00  6197.6  363.78
#Mann=6,-1,0
  4489.4    0.05       0  4777.8    0.12       0  4981.4    0.07       0
  5023.6    0.12       0  5035.9    0.16       0  5153.1    0.05       0
Bank Sta=4981.4,5023.6
Exp/Cntr=0.3,0.1

Type RM Length L Ch R = 1,25479,426,426,426
BEGIN DESCRIPTION:
South Twin Creek25478.92
END DESCRIPTION:
XS GIS Cut Line= 3
      2728791.01      6807416.61      2728655.56      6808019.58
      2728222.96      6808909.96
#Sta/Elev= 30
  4391.3  367.08  4411.9  365.03  4559.8  351.62  4649.4  345.71  4693.0  345.17
  4723.8  347.07  4744.3  344.73  4752.9  346.24  4758.0  345.21  4769.4  346.11
  4877.5  348.27  4989.4  347.48  4990.3  347.52  4997.0  337.23  4998.0  336.73
  5039.2  337.23  5040.6  347.86  5095.5  346.70  5102.6  346.32  5203.1  346.04
  5294.4  345.44  5339.5  348.65  5412.7  350.93  5644.6  348.88  5722.4  350.08
  5789.1  353.70  5811.4  356.53  5863.9  359.78  5944.8  369.94  5999.2  373.87
#Mann=10,-1,0
  4391.3    0.16       0  4411.9    0.05       0  4649.4    0.12       0
  4769.4    0.16       0  4989.4    0.12       0  4997.0    0.07       0
  5039.2    0.12       0  5095.5    0.05       0  5102.6    0.12       0
  5203.1    0.05       0
Bank Sta=4997,5039.2
Exp/Cntr=0.3,0.1

Type RM Length L Ch R = 1,25053,460,460,460
BEGIN DESCRIPTION:
South Twin Creek25053.4
END DESCRIPTION:
XS GIS Cut Line= 3
      2728685.76      6807357.90      2728418.95      6807918.79
      2728046.67      6808745.64
#Sta/Elev= 30
  4386.1  367.74  4447.1  363.82  4502.9  358.14  4606.1  350.62  4661.1  348.40
  4719.6  345.22  4768.3  345.30  4821.6  346.16  4867.0  343.84  4963.2  346.35
  4975.0  346.26  4980.6  344.01  4997.7  340.84  5005.2  337.01  5006.2  336.51
  5047.5  337.01  5049.5  345.07  5055.0  347.65  5270.5  345.70  5320.5  344.70
  5390.0  347.70  5464.9  348.27  5525.1  346.72  5623.8  348.90  5735.9  354.59
  5799.2  360.20  5821.2  363.49  5843.1  364.22  5887.0  368.67  5914.0  368.17
#Mann=8,-1,0
  4386.1    0.16       0  4502.9    0.05       0  4661.1    0.16       0
  4768.3    0.12       0  4963.2    0.16       0  5005.2    0.07       0
  5047.5    0.16       0  5270.5    0.05       0
Bank Sta=5005.2,5047.5
Exp/Cntr=0.3,0.1