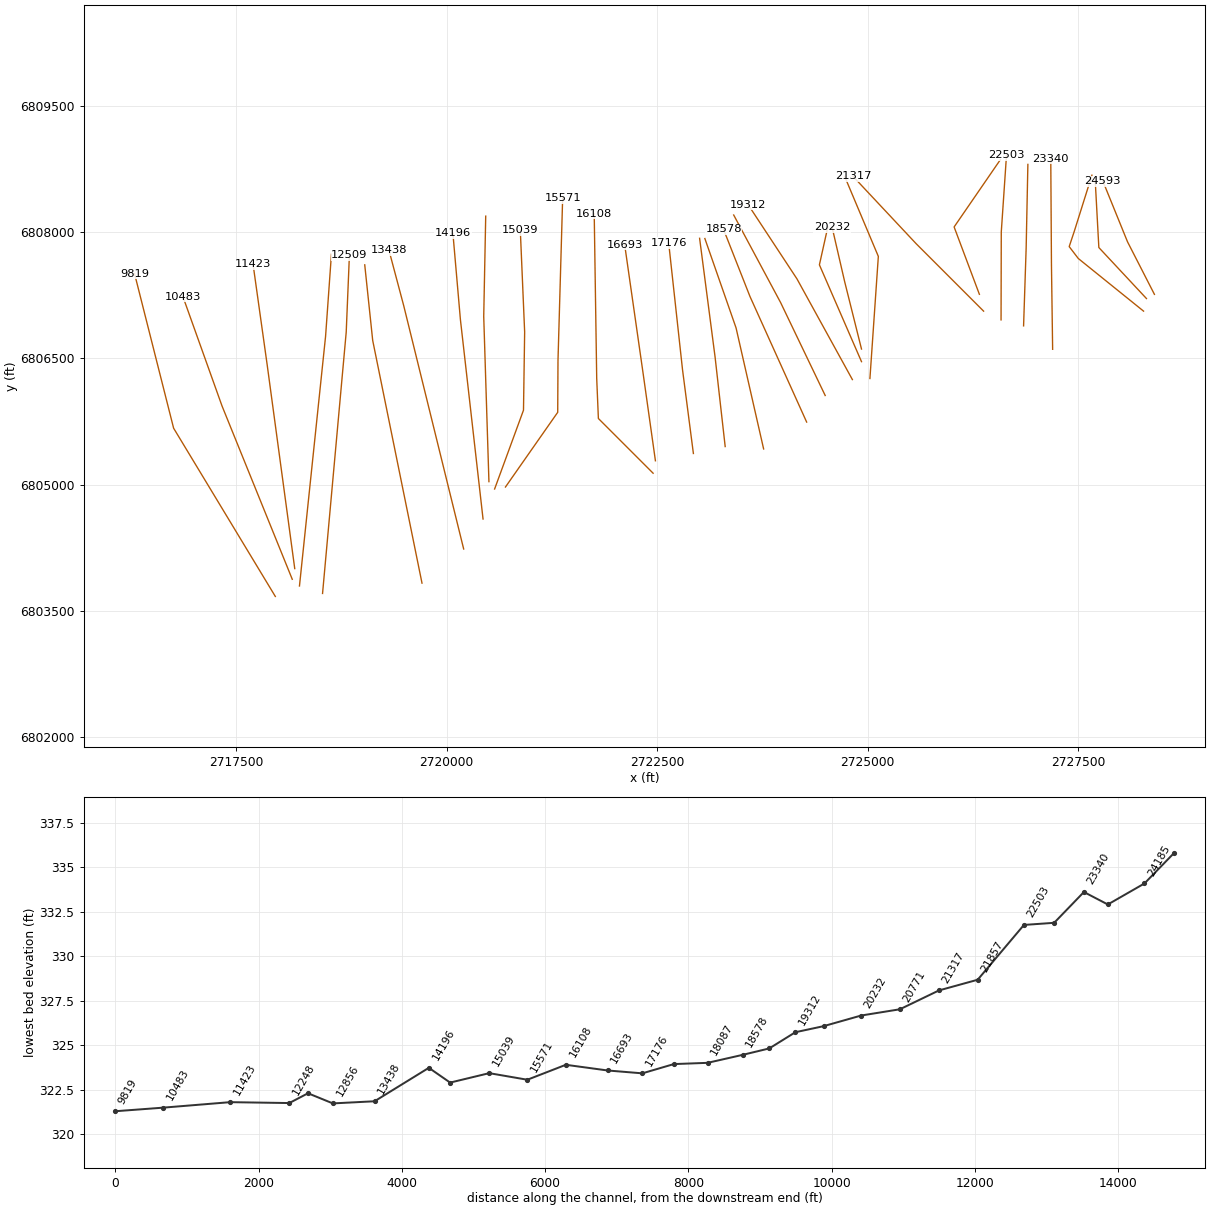
HEC-RAS study South Twin Creek.prj: South Twin Creek Base Level Engineering

--- South Twin Creek.g01 (geometry) --- (continued)

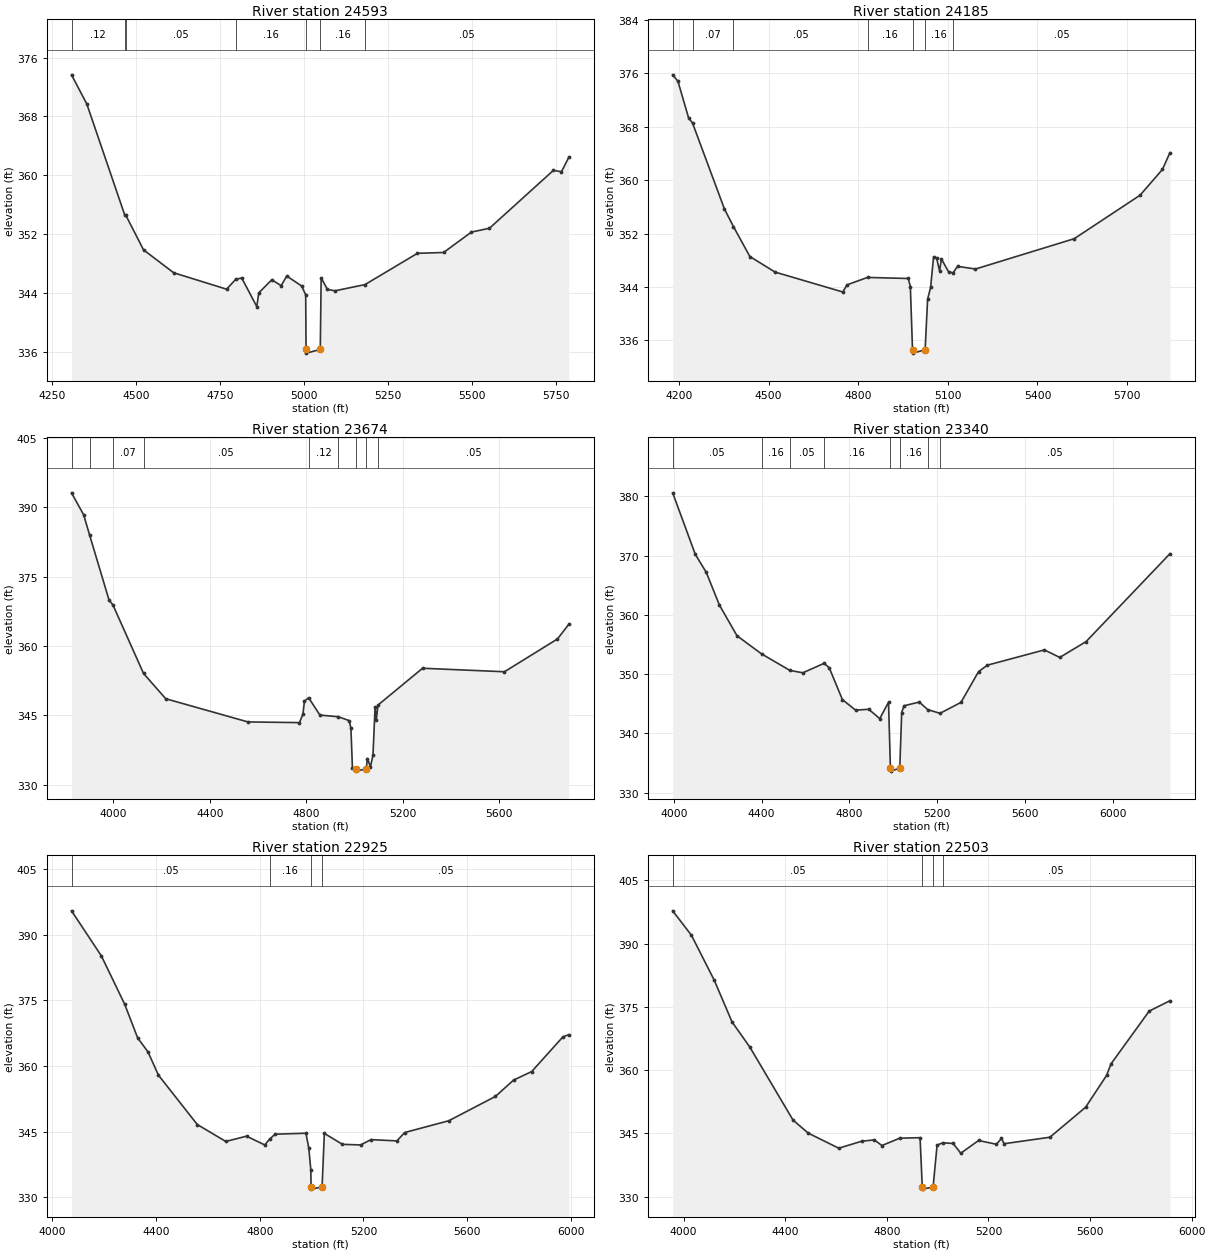
Type RM Length L Ch R = 1,24593,408,408,408
BEGIN DESCRIPTION:
South Twin Creek24593.05
END DESCRIPTION:
XS GIS Cut Line= 3
      2728404.97      6807260.37      2728085.20      6807885.00
      2727792.60      6808605.53
#Sta/Elev= 30
  4308.4  373.65  4354.0  369.67  4466.7  354.58  4469.7  354.57  4522.6  349.84
  4612.4  346.72  4769.7  344.49  4796.7  345.82  4814.7  346.02  4859.6  342.12
  4865.5  343.99  4904.3  345.77  4932.1  344.97  4948.7  346.28  4993.1  344.92
  5005.1  343.72  5006.2  336.29  5007.2  335.79  5048.5  336.29  5051.1  346.02
  5069.8  344.46  5092.2  344.27  5181.4  345.11  5337.6  349.37  5415.3  349.48
  5498.3  352.26  5551.9  352.78  5742.0  360.65  5766.1  360.47  5787.8  362.42
#Mann=7,-1,0
  4308.4    0.12       0  4466.7    0.07       0  4469.7    0.05       0
  4796.7    0.16       0  5006.2    0.07       0  5048.5    0.16       0
  5181.4    0.05       0
Bank Sta=5006.2,5048.5
Exp/Cntr=0.3,0.1

Type RM Length L Ch R = 1,24185,511,511,511
BEGIN DESCRIPTION:
South Twin Creek24184.98
END DESCRIPTION:
XS GIS Cut Line= 3
      2728310.51      6807210.58      2727744.90      6807816.42
      2727699.64      6808650.96
#Sta/Elev= 30
  4178.7  375.79  4196.2  374.84  4231.9  369.36  4245.1  368.57  4352.1  355.68
  4382.2  353.05  4437.1  348.57  4521.6  346.24  4748.2  343.26  4762.4  344.33
  4831.0  345.44  4967.6  345.28  4974.4  344.06  4981.6  334.60  4982.6  334.10
  5023.9  334.60  5032.1  342.16  5042.2  343.96  5052.2  348.54  5062.2  348.36
  5072.2  346.41  5078.4  348.21  5102.2  346.28  5117.5  346.13  5132.3  347.10
  5192.4  346.70  5522.9  351.24  5743.2  357.75  5818.2  361.61  5843.3  364.12
#Mann=7,-1,0
  4178.7    0.12       0  4245.1    0.07       0  4382.2    0.05       0
  4831.0    0.16       0  4981.6    0.07       0  5023.9    0.16       0
  5117.5    0.05       0
Bank Sta=4981.6,5023.9
Exp/Cntr=0.3,0.1

Type RM Length L Ch R = 1,23674,334,334,334
BEGIN DESCRIPTION:
South Twin Creek23673.894
END DESCRIPTION:
XS GIS Cut Line= 5
      2728275.96      6807061.03      2727501.00      6807686.00
      2727392.71      6807827.56      2727452.10      6808005.72
      2727662.88      6808675.65
#Sta/Elev= 30
  3826.2  393.16  3876.5  388.41  3901.4  383.99  3982.1  369.92  3998.0  368.90
  4125.1  354.06  4217.2  348.59  4558.4  343.57  4772.2  343.42  4786.6  345.23
  4793.0  348.08  4810.5  348.80  4857.1  345.05  4933.9  344.69  4979.1  343.84
  4985.9  342.16  4992.2  333.57  5006.9  333.42  5007.9  332.92  5049.3  333.42
  5054.5  335.64  5066.9  333.84  5077.4  336.35  5086.1  346.73  5091.3  344.03
  5098.0  347.21  5283.3  355.19  5623.1  354.43  5843.3  361.53  5890.1  364.70
#Mann=9,-1,0
  3826.2    0.05       0  3901.4    0.12       0  3998.0    0.07       0
  4125.1    0.05       0  4810.5    0.12       0  4933.9    0.16       0
  5006.9    0.07       0  5049.3    0.16       0  5098.0    0.05       0
Bank Sta=5006.9,5049.3
Exp/Cntr=0.3,0.1

Type RM Length L Ch R = 1,23340,415,415,415
BEGIN DESCRIPTION:
South Twin Creek23339.862
END DESCRIPTION:
XS GIS Cut Line= 3
      2727196.05      6806607.96      2727182.06      6807612.77
      2727173.97      6808872.64
#Sta/Elev= 30
  3995.1  380.59  4098.1  370.21  4148.2  367.16  4208.2  361.63  4288.2  356.46
  4399.9  353.41  4529.4  350.61  4588.2  350.22  4685.2  351.82  4708.2  351.06
  4768.2  345.69  4828.2  343.91  4888.2  344.06  4938.2  342.48  4978.2  345.24
  4986.9  334.12  4987.9  333.62  5029.5  334.12  5038.2  343.48  5048.2  344.64
  5118.2  345.28  5156.3  344.02  5212.4  343.37  5308.2  345.22  5388.2  350.41
  5428.2  351.50  5688.2  354.08  5758.3  352.81  5878.3  355.49  6259.9  370.31
#Mann=8,-1,0
  3995.1    0.05       0  4399.9    0.16       0  4529.4    0.05       0
  4685.2    0.16       0  4986.9    0.07       0  5029.5    0.16       0
  5156.3    0.16       0  5212.4    0.05       0
Bank Sta=4986.9,5029.5
Exp/Cntr=0.3,0.1

Type RM Length L Ch R = 1,22925,422,422,422
BEGIN DESCRIPTION:
South Twin Creek22924.677
END DESCRIPTION:
XS GIS Cut Line= 3
      2726851.00      6806886.04      2726881.58      6807811.64
      2726902.06      6808803.93
#Sta/Elev= 30
  4073.9  395.42  4188.9  385.15  4279.0  374.10  4329.0  366.42  4369.0  363.21
  4409.0  357.93  4559.1  346.64  4669.2  342.77  4749.2  343.98  4819.3  341.98
  4838.3  343.30  4859.3  344.43  4978.3  344.65  4989.4  341.27  4997.2  336.30
  4998.1  332.39  4999.1  331.89  5040.7  332.39  5049.4  344.61  5119.4  342.11
  5189.4  341.98  5229.4  343.19  5329.4  342.90  5359.4  344.81  5529.5  347.50
  5709.5  353.05  5779.5  356.78  5849.5  358.73  5969.6  366.63  5992.5  367.15
#Mann=4,-1,0
  4073.9    0.05       0  4838.3    0.16       0  4998.1    0.07       0
  5040.7    0.05       0
Bank Sta=4998.1,5040.7
Exp/Cntr=0.3,0.1

Type RM Length L Ch R = 1,22503,646,646,646
BEGIN DESCRIPTION:
South Twin Creek22502.511
END DESCRIPTION:
XS GIS Cut Line= 3
      2726583.47      6806957.35      2726586.02      6808000.05
      2726648.08      6808912.34
#Sta/Elev= 30
  3957.3  397.79  4031.0  392.01  4121.0  381.32  4191.0  371.43  4261.0  365.46
  4431.0  348.15  4491.0  345.05  4611.0  341.48  4701.0  343.13  4751.0  343.45
  4781.0  342.11  4851.0  343.86  4931.0  343.97  4939.7  332.27  4940.7  331.77
  4982.3  332.27  4998.0  342.20  5019.9  342.76  5061.1  342.61  5091.2  340.29
  5161.3  343.31  5231.5  342.41  5251.5  343.81  5261.6  342.54  5442.0  344.08
  5582.3  351.18  5665.1  358.74  5682.5  361.48  5832.9  374.01  5914.4  376.46
#Mann=4,-1,0
  3957.3    0.05       0  4939.7    0.07       0  4982.3    0.05       0
  5019.9    0.05       0
Bank Sta=4939.7,4982.3
Exp/Cntr=0.3,0.1

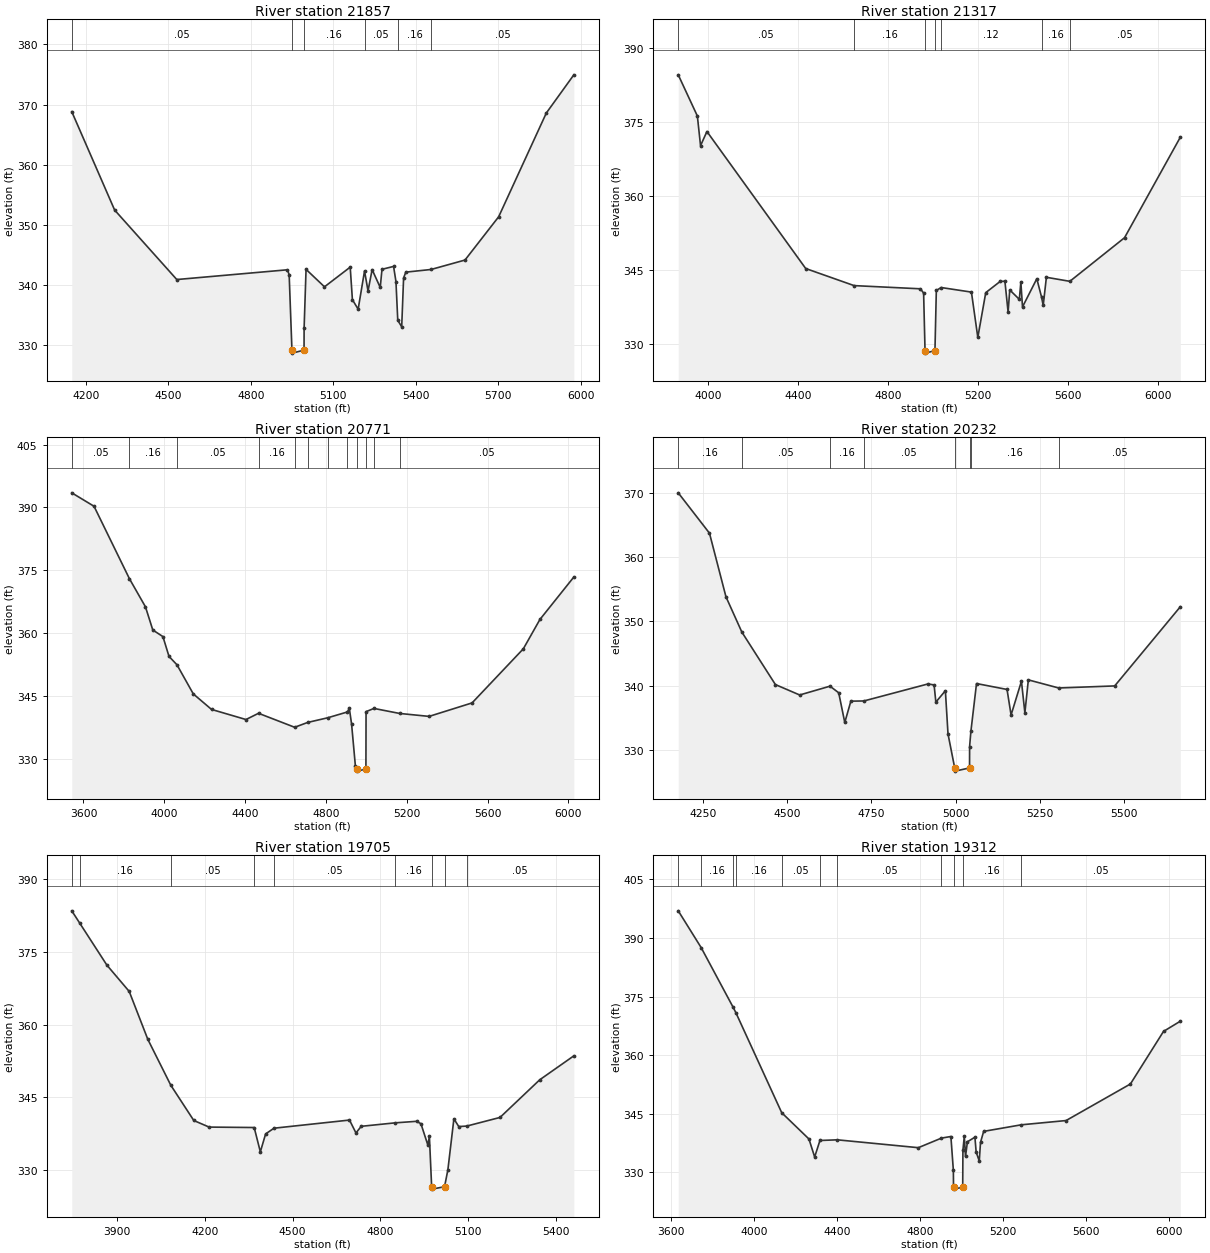
Type RM Length L Ch R = 1,21857,540,540,540
BEGIN DESCRIPTION:
South Twin Creek21857.269
END DESCRIPTION:
XS GIS Cut Line= 3
      2726326.00      6807260.99      2726026.00      6808061.00
      2726575.98      6808860.97
#Sta/Elev= 30
  4149.1  368.82  4304.9  352.47  4530.9  340.92  4933.2  342.54  4939.4  341.71
  4949.5  329.19  4950.5  328.69  4993.5  329.19  4993.7  332.79  5000.8  342.61
  5067.8  339.71  5161.3  342.98  5169.3  337.57  5190.2  335.99  5213.4  342.35
  5226.1  339.02  5241.0  342.57  5270.5  339.60  5276.8  342.62  5319.0  343.10
  5327.6  340.59  5334.2  334.15  5348.5  333.06  5355.4  341.18  5363.4  342.15
  5455.1  342.59  5578.6  344.16  5701.0  351.35  5874.2  368.59  5974.3  374.94
#Mann=6,-1,0
  4149.1    0.05       0  4949.5    0.07       0  4993.5    0.16       0
  5213.4    0.05       0  5334.2    0.16       0  5455.1    0.05       0
Bank Sta=4949.5,4993.5
Exp/Cntr=0.3,0.1

Type RM Length L Ch R = 1,21317,546,546,546
BEGIN DESCRIPTION:
South Twin Creek21316.883
END DESCRIPTION:
XS GIS Cut Line= 3
      2726376.00      6807061.00      2725576.00      6807861.00
      2724825.97      6808661.03
#Sta/Elev= 30
  3869.3  384.64  3954.2  376.27  3968.3  370.25  3996.6  373.12  4435.0  345.28
  4649.7  341.81  4944.1  341.16  4958.2  340.29  4964.5  328.59  4965.5  328.09
  5008.5  328.59  5014.6  340.82  5035.9  341.42  5170.4  340.49  5198.7  331.28
  5233.9  340.38  5297.9  342.66  5318.9  342.70  5333.1  336.44  5340.4  340.93
  5382.9  339.02  5389.7  342.51  5397.0  337.47  5460.5  343.21  5481.4  339.50
  5488.9  337.77  5503.0  343.50  5607.1  342.68  5849.8  351.54  6097.3  371.96
#Mann=7,-1,0
  3869.3    0.05       0  4649.7    0.16       0  4964.5    0.07       0
  5008.5    0.16       0  5035.9    0.12       0  5481.4    0.16       0
  5607.1    0.05       0
Bank Sta=4964.5,5008.5
Exp/Cntr=0.3,0.1

Type RM Length L Ch R = 1,20771,539,539,539
BEGIN DESCRIPTION:
South Twin Creek20770.529
END DESCRIPTION:
XS GIS Cut Line= 3
      2725026.00      6806261.05      2725126.00      6807711.00
      2724725.99      6808661.03
#Sta/Elev= 30
  3542.3  393.48  3652.5  390.27  3827.5  372.98  3906.9  366.26  3943.2  360.73
  3993.3  359.15  4023.4  354.42  4062.8  352.42  4143.7  345.46  4233.9  341.76
  4404.3  339.35  4466.3  340.84  4645.2  337.50  4709.8  338.66  4808.1  339.76
  4906.4  341.16  4915.5  342.04  4926.8  338.27  4945.6  328.25  4953.6  327.53
  4954.6  327.03  4997.7  327.53  4998.4  341.23  5037.3  342.00  5164.7  340.80
  5310.4  340.10  5523.0  343.32  5776.6  356.24  5858.6  363.24  6026.5  373.38
#Mann=12,-1,0
  3542.3    0.05       0  3827.5    0.16       0  4062.8    0.05       0
  4466.3    0.16       0  4645.2    0.05       0  4709.8    0.16       0
  4808.1    0.05       0  4906.4    0.12       0  4953.6    0.07       0
  4997.7    0.12       0  5037.3    0.16       0  5164.7    0.05       0
Bank Sta=4953.6,4997.7
Exp/Cntr=0.3,0.1

Type RM Length L Ch R = 1,20232,527,527,527
BEGIN DESCRIPTION:
South Twin Creek20231.733
END DESCRIPTION:
XS GIS Cut Line= 3
      2724926.01      6806610.96      2724726.00      6807411.00
      2724576.01      6808060.96
#Sta/Elev= 30
  4175.9  369.99  4268.7  363.71  4317.7  353.81  4364.9  348.32  4464.6  340.15
  4536.7  338.53  4626.8  339.90  4652.7  338.87  4670.7  334.25  4688.8  337.57
  4727.5  337.60  4918.1  340.25  4936.1  340.09  4941.3  337.42  4969.6  339.19
  4977.4  332.47  4997.3  327.18  4998.3  326.68  5041.4  327.18  5041.6  330.50
  5045.4  332.87  5062.1  340.31  5152.8  339.39  5164.8  335.42  5195.6  340.67
  5205.8  335.75  5216.1  340.88  5306.2  339.62  5472.7  339.94  5667.6  352.26
#Mann=8,-1,0
  4175.9    0.16       0  4364.9    0.05       0  4626.8    0.16       0
  4727.5    0.05       0  4997.3    0.05       0  5041.4    0.05       0
  5045.4    0.16       0  5306.2    0.05       0
Bank Sta=4997.3,5041.4
Exp/Cntr=0.3,0.1

Type RM Length L Ch R = 1,19705,393,393,393
BEGIN DESCRIPTION:
South Twin Creek19704.56
END DESCRIPTION:
XS GIS Cut Line= 3
      2724925.99      6806461.03      2724426.00      6807611.00
      2724525.99      6808060.96
#Sta/Elev= 30
  3745.9  383.50  3773.0  380.97  3865.8  372.30  3942.1  366.87  4005.7  356.98
  4084.1  347.52  4162.7  340.24  4215.0  338.88  4369.0  338.79  4390.0  333.77
  4408.0  337.47  4436.6  338.65  4694.5  340.33  4716.6  337.67  4734.6  339.04
  4851.3  339.76  4923.5  340.07  4938.5  339.58  4962.0  335.20  4967.4  336.95
  4975.1  326.58  4976.1  326.08  5019.2  326.58  5030.6  330.09  5051.1  340.59
  5067.7  338.99  5095.0  339.09  5208.6  340.87  5344.3  348.64  5460.8  353.58
#Mann=9,-1,0
  3745.9    0.05       0  3773.0    0.16       0  4084.1    0.05       0
  4369.0    0.16       0  4436.6    0.05       0  4851.3    0.16       0
  4975.1    0.07       0  5019.2    0.16       0  5095.0    0.05       0
Bank Sta=4975.1,5019.2
Exp/Cntr=0.3,0.1

Type RM Length L Ch R = 1,19312,364,364,364
BEGIN DESCRIPTION:
South Twin Creek19311.58
END DESCRIPTION:
XS GIS Cut Line= 3
      2724817.54      6806248.33      2724159.40      6807444.31
      2723578.58      6808326.94
#Sta/Elev= 30
  3634.9  396.92  3745.2  387.54  3899.1  372.31  3913.0  370.86  4134.1  345.28
  4265.4  338.56  4292.9  333.96  4318.4  338.18  4402.0  338.35  4792.9  336.34
  4904.5  338.79  4950.0  339.20  4962.0  330.52  4962.7  326.24  4963.7  325.74
  5007.0  326.24  5008.0  335.66  5014.6  339.21  5020.6  334.09  5029.7  337.85
  5065.9  339.02  5071.9  335.22  5086.9  332.93  5092.9  337.69  5108.0  340.51
  5289.4  342.19  5505.6  343.28  5815.9  352.63  5975.6  366.08  6056.6  368.69
#Mann=11,-1,0
  3634.9    0.05       0  3745.2    0.16       0  3899.1    0.12       0
  3913.0    0.16       0  4134.1    0.05       0  4318.4    0.16       0
  4402.0    0.05       0  4904.5    0.16       0  4962.7    0.07       0
  5007.0    0.16       0  5289.4    0.05       0
Bank Sta=4962.7,5007
Exp/Cntr=0.3,0.1

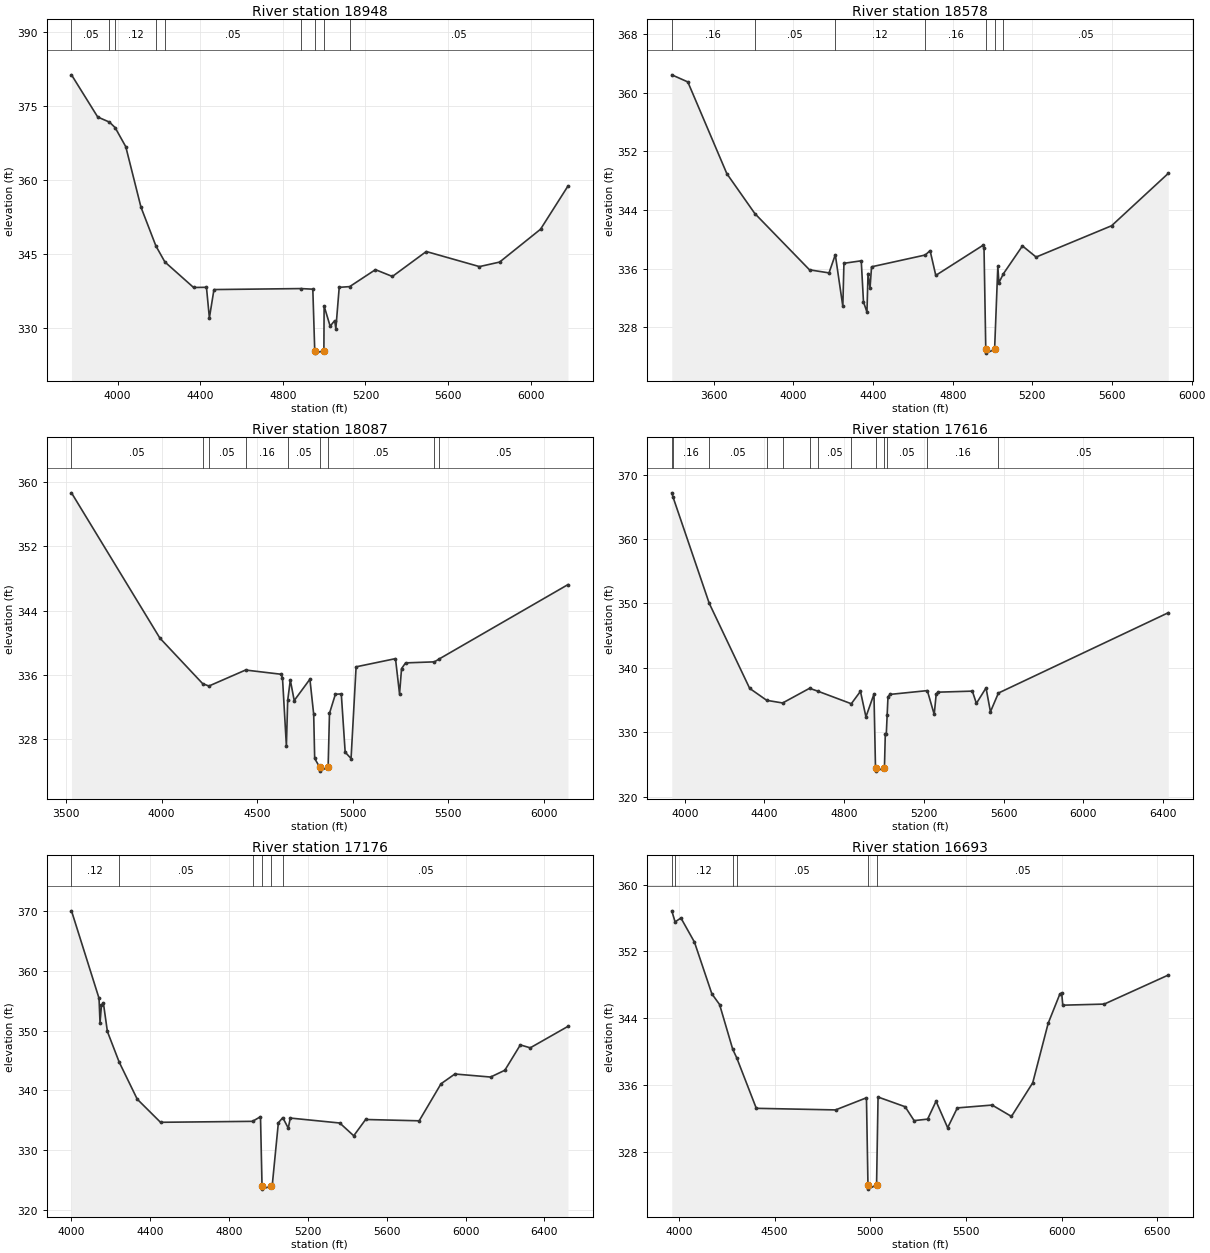
Type RM Length L Ch R = 1,18948,370,370,370
BEGIN DESCRIPTION:
South Twin Creek18948.129
END DESCRIPTION:
XS GIS Cut Line= 3
      2724494.74      6806058.97      2723965.74      6807161.98
      2723408.04      6808202.78
#Sta/Elev= 30
  3776.7  381.31  3903.7  372.75  3960.7  371.71  3988.1  370.59  4039.6  366.72
  4113.1  354.46  4185.6  346.57  4229.0  343.33  4367.9  338.15  4430.3  338.19
  4444.4  331.98  4466.6  337.73  4886.9  337.93  4945.3  337.81  4954.6  325.33
  4955.6  324.83  4998.9  325.33  5000.0  334.39  5029.2  330.30  5051.2  331.43
  5056.8  329.79  5073.1  338.18  5123.8  338.33  5248.5  341.77  5330.6  340.39
  5494.7  345.45  5752.2  342.39  5849.8  343.31  6047.9  349.97  6180.8  358.74
#Mann=9,-1,0
  3776.7    0.05       0  3960.7    0.16       0  3988.1    0.12       0
  4185.6    0.16       0  4229.0    0.05       0  4886.9    0.16       0
  4954.6    0.07       0  4998.9    0.16       0  5123.8    0.05       0
Bank Sta=4954.6,4998.9
Exp/Cntr=0.3,0.1

Type RM Length L Ch R = 1,18578,491,491,491
BEGIN DESCRIPTION:
South Twin Creek18578.042
END DESCRIPTION:
XS GIS Cut Line= 3
      2724274.50      6805743.47      2723601.00      6807236.00
      2723287.39      6808032.43
#Sta/Elev= 30
  3389.1  362.42  3469.6  361.45  3665.6  348.94  3806.3  343.50  4080.7  335.83
  4178.7  335.41  4210.3  337.89  4248.1  330.84  4253.6  336.72  4340.6  337.06
  4351.8  331.46  4369.2  330.07  4374.7  335.32  4384.7  333.35  4392.3  336.24
  4662.1  337.85  4686.3  338.45  4714.9  335.07  4951.7  339.17  4957.2  338.75
  4966.0  324.97  4967.0  324.47  5010.3  324.97  5026.5  336.31  5031.9  334.07
  5054.9  335.31  5150.1  339.09  5218.8  337.57  5597.9  341.84  5882.5  348.98
#Mann=7,-1,0
  3389.1    0.16       0  3806.3    0.05       0  4210.3    0.12       0
  4662.1    0.16       0  4966.0    0.07       0  5010.3    0.16       0
  5054.9    0.05       0
Bank Sta=4966,5010.3
Exp/Cntr=0.3,0.1

Type RM Length L Ch R = 1,18087,471,471,471
BEGIN DESCRIPTION:
South Twin Creek18086.977
END DESCRIPTION:
XS GIS Cut Line= 3
      2723763.53      6805424.18      2723435.93      6806862.62
      2723065.67      6807923.38
#Sta/Elev= 30
  3528.8  358.68  3991.4  340.59  4215.6  334.91  4248.2  334.62  4440.0  336.61
  4624.5  336.09  4633.2  335.68  4653.7  327.16  4660.5  332.82  4674.2  335.36
  4694.7  332.81  4776.8  335.47  4796.6  331.10  4801.8  325.60  4827.7  324.52
  4828.7  324.02  4872.2  324.52  4879.3  331.22  4910.1  333.59  4941.1  333.64
  4961.4  326.38  4992.2  325.59  5018.6  337.01  5224.8  338.03  5246.0  333.63
  5256.5  336.79  5277.7  337.50  5428.7  337.63  5452.1  337.97  6127.6  347.25
#Mann=9,-1,0
  3528.8    0.05       0  4215.6    0.07       0  4248.2    0.05       0
  4440.0    0.16       0  4660.5    0.05       0  4827.7    0.05       0
  4872.2    0.05       0  5428.7    0.16       0  5452.1    0.05       0
Bank Sta=4827.7,4872.2
Exp/Cntr=0.3,0.1

Type RM Length L Ch R = 1,17616,440,440,440
BEGIN DESCRIPTION:
South Twin Creek17615.53
END DESCRIPTION:
XS GIS Cut Line= 3
      2723306.96      6805452.55      2723186.57      6806519.12
      2723003.12      6807926.17
#Sta/Elev= 30
  3934.8  367.19  3941.2  366.51  4122.8  350.02  4325.7  336.81  4411.3  334.95
  4491.2  334.54  4626.5  336.82  4667.2  336.38  4835.9  334.42  4881.9  336.35
  4909.4  332.38  4949.7  335.92  4957.4  324.45  4958.4  323.95  5002.3  324.45
  5006.6  329.72  5011.6  329.72  5016.0  332.72  5020.1  335.51  5030.2  335.87
  5217.6  336.46  5252.1  332.76  5262.2  335.95  5272.2  336.22  5443.7  336.38
  5463.8  334.47  5512.3  336.88  5534.4  333.17  5574.4  336.08  6427.1  348.56
#Mann=13,-1,0
  3934.8    0.05       0  3941.2    0.16       0  4122.8    0.05       0
  4411.3    0.07       0  4491.2    0.05       0  4626.5    0.16       0
  4667.2    0.05       0  4835.9    0.16       0  4957.4    0.07       0
  5002.3    0.16       0  5016.0    0.05       0  5217.6    0.16       0
  5574.4    0.05       0
Bank Sta=4957.4,5002.3
Exp/Cntr=0.3,0.1

Type RM Length L Ch R = 1,17176,483,483,483
BEGIN DESCRIPTION:
South Twin Creek17176.14
END DESCRIPTION:
XS GIS Cut Line= 3
      2722929.35      6805370.41      2722800.35      6806364.88
      2722635.93      6807871.13
#Sta/Elev= 30
  4001.4  370.11  4141.1  355.44  4146.1  351.33  4153.3  354.26  4163.3  354.62
  4183.5  349.87  4243.4  344.73  4334.8  338.52  4452.9  334.64  4919.6  334.80
  4960.0  335.58  4967.8  323.93  4968.8  323.43  5012.7  323.93  5020.4  324.35
  5050.6  334.56  5073.0  335.42  5100.9  333.66  5111.0  335.35  5362.1  334.52
  5432.9  332.38  5493.2  335.11  5764.8  334.89  5875.5  341.10  5945.9  342.74
  6127.0  342.23  6199.3  343.37  6277.8  347.62  6328.1  347.13  6519.4  350.73
#Mann=6,-1,0
  4001.4    0.12       0  4243.4    0.05       0  4919.6    0.07       0
  4967.8    0.07       0  5012.7    0.07       0  5073.0    0.05       0
Bank Sta=4967.8,5012.7
Exp/Cntr=0.3,0.1

Type RM Length L Ch R = 1,16693,585,585,585
BEGIN DESCRIPTION:
South Twin Creek16692.79
END DESCRIPTION:
XS GIS Cut Line= 3
      2722478.41      6805283.71      2722330.49      6806333.18
      2722112.85      6807852.12
#Sta/Elev= 30
  3963.0  356.86  3980.2  355.54  4010.8  356.00  4081.4  353.12  4172.3  346.94
  4212.7  345.66  4281.7  340.29  4301.7  339.32  4404.6  333.25  4818.7  333.06
  4980.2  334.51  4988.1  324.09  4989.1  323.59  5033.0  324.09  5040.8  334.60
  5182.3  333.44  5229.3  331.78  5299.9  331.96  5343.9  334.10  5404.5  330.93
  5455.0  333.30  5636.9  333.64  5737.9  332.28  5849.0  336.30  5929.8  343.42
  5990.4  346.89  6000.5  347.03  6006.0  345.58  6222.8  345.71  6557.3  349.18
#Mann=6,-1,0
  3963.0    0.16       0  3980.2    0.12       0  4281.7    0.16       0
  4301.7    0.05       0  4988.1    0.05       0  5033.0    0.05       0
Bank Sta=4988.1,5033
Exp/Cntr=0.3,0.1

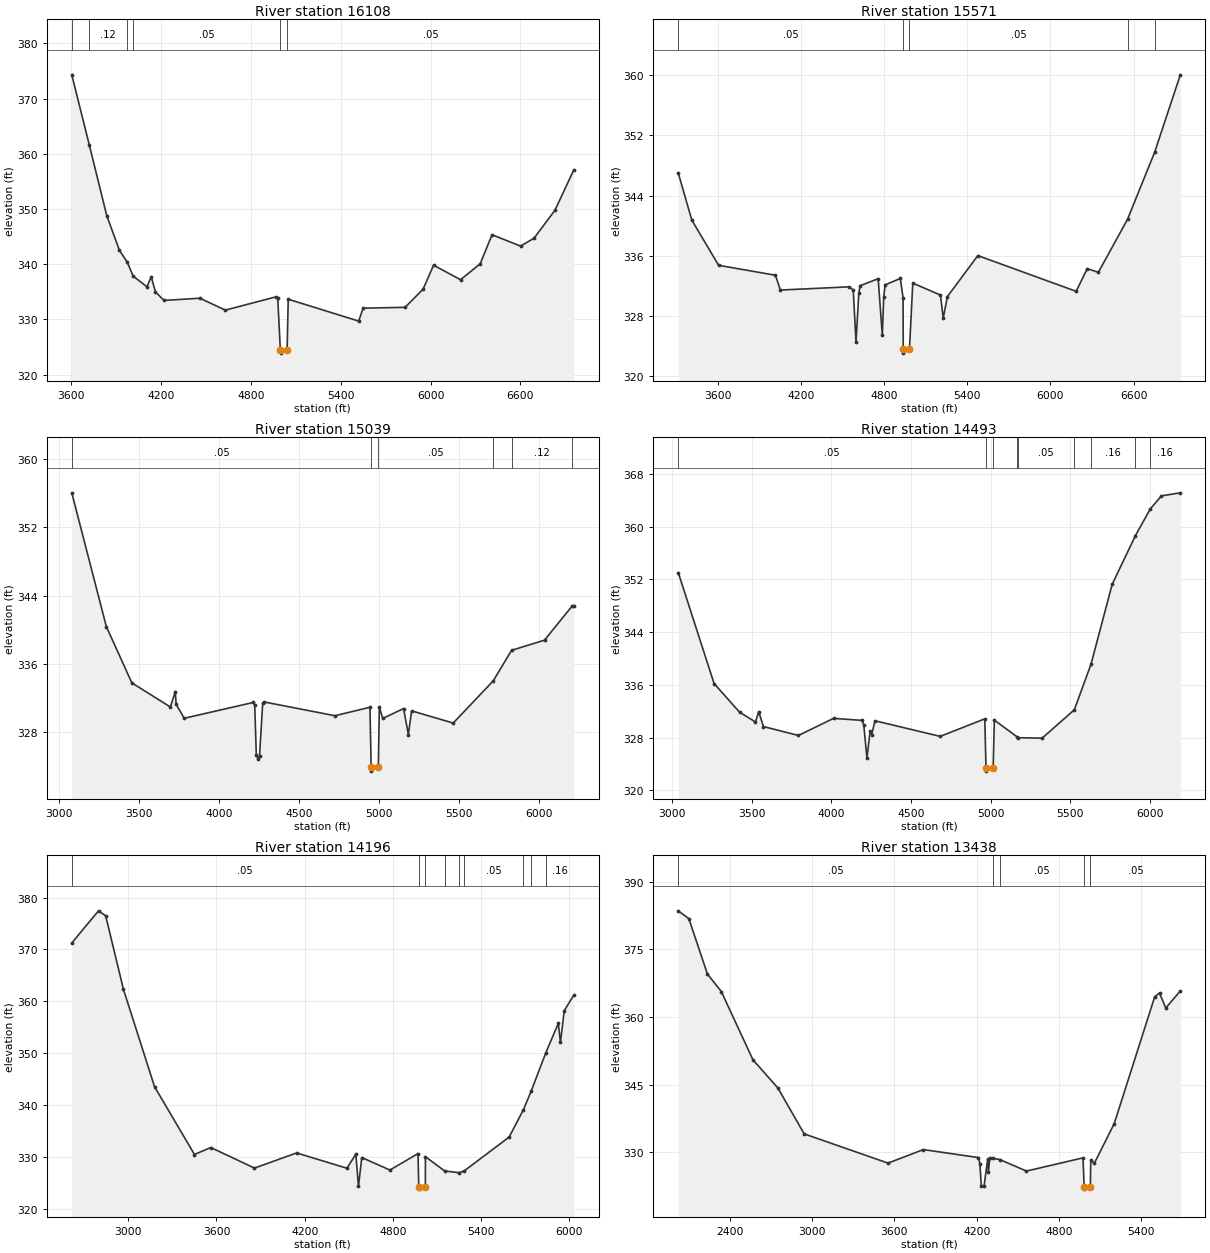
Type RM Length L Ch R = 1,16108,537,537,537
BEGIN DESCRIPTION:
South Twin Creek16108.058
END DESCRIPTION:
XS GIS Cut Line= 4
      2722450.98      6805136.02      2721801.00      6805786.00
      2721781.12      6806260.88      2721751.45      6808216.85
#Sta/Elev= 30
  3605.5  374.29  3723.3  361.50  3838.8  348.81  3923.7  342.51  3975.4  340.40
  4015.2  337.85  4107.5  335.92  4135.8  337.74  4164.1  334.98  4220.7  333.45
  4461.1  333.85  4629.8  331.69  4970.1  334.11  4980.1  333.85  4997.6  324.41
  4998.6  323.91  5042.6  324.41  5050.1  333.67  5520.2  329.71  5550.2  332.05
  5830.2  332.20  5950.2  335.50  6020.2  339.82  6200.3  337.20  6331.0  340.08
  6410.3  345.34  6600.3  343.29  6690.3  344.70  6830.3  349.78  6956.2  357.10
#Mann=6,-1,0
  3605.5    0.16       0  3723.3    0.12       0  3975.4    0.16       0
  4015.2    0.05       0  4997.6    0.05       0  5042.6    0.05       0
Bank Sta=4997.6,5042.6
Exp/Cntr=0.3,0.1

Type RM Length L Ch R = 1,15571,532,532,532
BEGIN DESCRIPTION:
South Twin Creek15570.605
END DESCRIPTION:
XS GIS Cut Line= 4
      2720697.30      6804972.18      2721317.94      6805859.41
      2721321.29      6806476.00      2721376.57      6808403.05
#Sta/Elev= 30
  3310.9  347.02  3408.9  340.75  3602.5  334.74  4013.2  333.42  4048.9  331.45
  4545.3  331.88  4575.3  331.45  4595.3  324.51  4615.3  331.04  4625.3  332.03
  4755.3  332.96  4785.3  325.42  4795.3  330.48  4805.3  332.14  4915.3  332.99
  4935.3  330.43  4936.4  323.57  4937.4  323.07  4981.4  323.57  5005.3  332.37
  5205.3  330.79  5225.3  327.73  5255.4  330.58  5475.4  336.03  6185.7  331.28
  6265.8  334.30  6345.8  333.80  6557.0  340.86  6753.0  349.78  6938.1  360.05
#Mann=5,-1,0
  3310.9    0.05       0  4936.4    0.05       0  4981.4    0.05       0
  6557.0    0.16       0  6753.0    0.12       0
Bank Sta=4936.4,4981.4
Exp/Cntr=0.3,0.1

Type RM Length L Ch R = 1,15039,546,546,546
BEGIN DESCRIPTION:
South Twin Creek15039.318
END DESCRIPTION:
XS GIS Cut Line= 4
      2720568.47      6804948.48      2720911.47      6805884.62
      2720925.23      6806813.17      2720873.62      6808024.22
#Sta/Elev= 30
  3080.7  356.04  3296.6  340.38  3456.1  333.78  3697.1  330.95  3727.6  332.75
  3733.0  331.27  3783.3  329.63  4214.1  331.48  4224.1  331.16  4234.1  325.31
  4244.1  324.90  4254.1  325.25  4274.1  331.43  4284.1  331.54  4725.0  329.93
  4944.2  330.92  4951.7  323.94  4952.7  323.44  4996.7  323.94  5002.8  330.96
  5024.2  329.61  5154.3  330.77  5184.3  327.73  5204.4  330.50  5464.6  329.07
  5715.0  334.02  5829.2  337.59  6035.1  338.78  6209.2  342.81  6218.5  342.83
#Mann=6,-1,0
  3080.7    0.05       0  4951.7    0.05       0  4996.7    0.05       0
  5715.0    0.16       0  5829.2    0.12       0  6209.2    0.16       0
Bank Sta=4951.7,4996.7
Exp/Cntr=0.3,0.1

Type RM Length L Ch R = 1,14493,297,297,297
BEGIN DESCRIPTION:
South Twin Creek14493.141
END DESCRIPTION:
XS GIS Cut Line= 3
      2720501.00      6805035.95      2720439.17      6806997.28
      2720462.83      6808189.15
#Sta/Elev= 30
  3037.7  353.03  3262.9  336.20  3422.9  331.85  3523.0  330.36  3543.0  331.92
  3573.0  329.67  3793.1  328.32  4013.2  330.91  4193.3  330.61  4203.3  329.92
  4223.3  324.88  4243.3  328.99  4253.3  328.42  4273.4  330.55  4683.6  328.18
  4963.7  330.84  4971.2  323.41  4972.2  322.91  5016.2  323.41  5023.7  330.65
  5167.8  328.09  5173.0  327.98  5323.8  327.91  5526.1  332.21  5630.7  339.10
  5763.9  351.23  5910.3  358.64  6003.3  362.67  6073.9  364.66  6192.1  365.12
#Mann=9,-1,0
  3037.7    0.05       0  4971.2    0.05       0  5016.2    0.05       0
  5167.8    0.07       0  5173.0    0.05       0  5526.1    0.07       0
  5630.7    0.16       0  5910.3    0.07       0  6003.3    0.16       0
Bank Sta=4971.2,5016.2
Exp/Cntr=0.3,0.1

Type RM Length L Ch R = 1,14196,758,758,758
BEGIN DESCRIPTION:
South Twin Creek14196.486
END DESCRIPTION:
XS GIS Cut Line= 3
      2720431.12      6804591.98      2720162.30      6806960.27
      2720073.08      6807986.30
#Sta/Elev= 30
  2616.5  371.22  2798.3  377.43  2847.0  376.47  2967.5  362.31  3179.1  343.51
  3450.8  330.42  3561.6  331.77  3858.7  327.80  4145.3  330.72  4487.5  327.77
  4547.8  330.49  4565.6  324.26  4588.1  329.84  4779.3  327.42  4970.5  330.60
  4975.4  324.24  4976.4  323.74  5020.4  324.24  5020.8  330.00  5152.0  327.24
  5250.1  326.91  5284.9  327.26  5590.1  333.79  5687.3  339.07  5740.5  342.70
  5838.6  349.99  5924.2  355.71  5938.9  352.05  5964.4  358.16  6029.9  361.18
#Mann=9,-1,0
  2616.5    0.05       0  4975.4    0.05       0  5020.4    0.05       0
  5152.0    0.05       0  5250.1    0.07       0  5284.9    0.05       0
  5687.3    0.07       0  5740.5    0.05       0  5838.6    0.16       0
Bank Sta=4975.4,5020.4
Exp/Cntr=0.3,0.1

Type RM Length L Ch R = 1,13438,582,582,582
BEGIN DESCRIPTION:
South Twin Creek13438.325
END DESCRIPTION:
XS GIS Cut Line= 3
      2720201.01      6804235.95      2719489.06      6807125.13
      2719313.14      6807786.63
#Sta/Elev= 30
  2024.4  383.51  2101.7  381.78  2237.1  369.52  2338.6  365.62  2569.0  350.51
  2750.5  344.28  2942.5  334.10  3553.9  327.62  3811.3  330.62  4213.0  328.85
  4223.3  327.49  4233.6  322.57  4254.2  322.65  4280.7  328.53  4285.8  325.71
  4295.4  328.71  4316.7  328.70  4368.1  328.41  4563.2  325.86  4975.2  328.79
  4983.4  322.36  4984.4  321.86  5028.7  322.36  5031.7  328.21  5057.8  327.59
  5202.7  336.36  5497.9  364.47  5532.9  365.31  5578.2  361.98  5684.5  365.75
#Mann=5,-1,0
  2024.4    0.05       0  4316.7    0.12       0  4368.1    0.05       0
  4983.4    0.05       0  5028.7    0.05       0
Bank Sta=4983.4,5028.7
Exp/Cntr=0.3,0.1

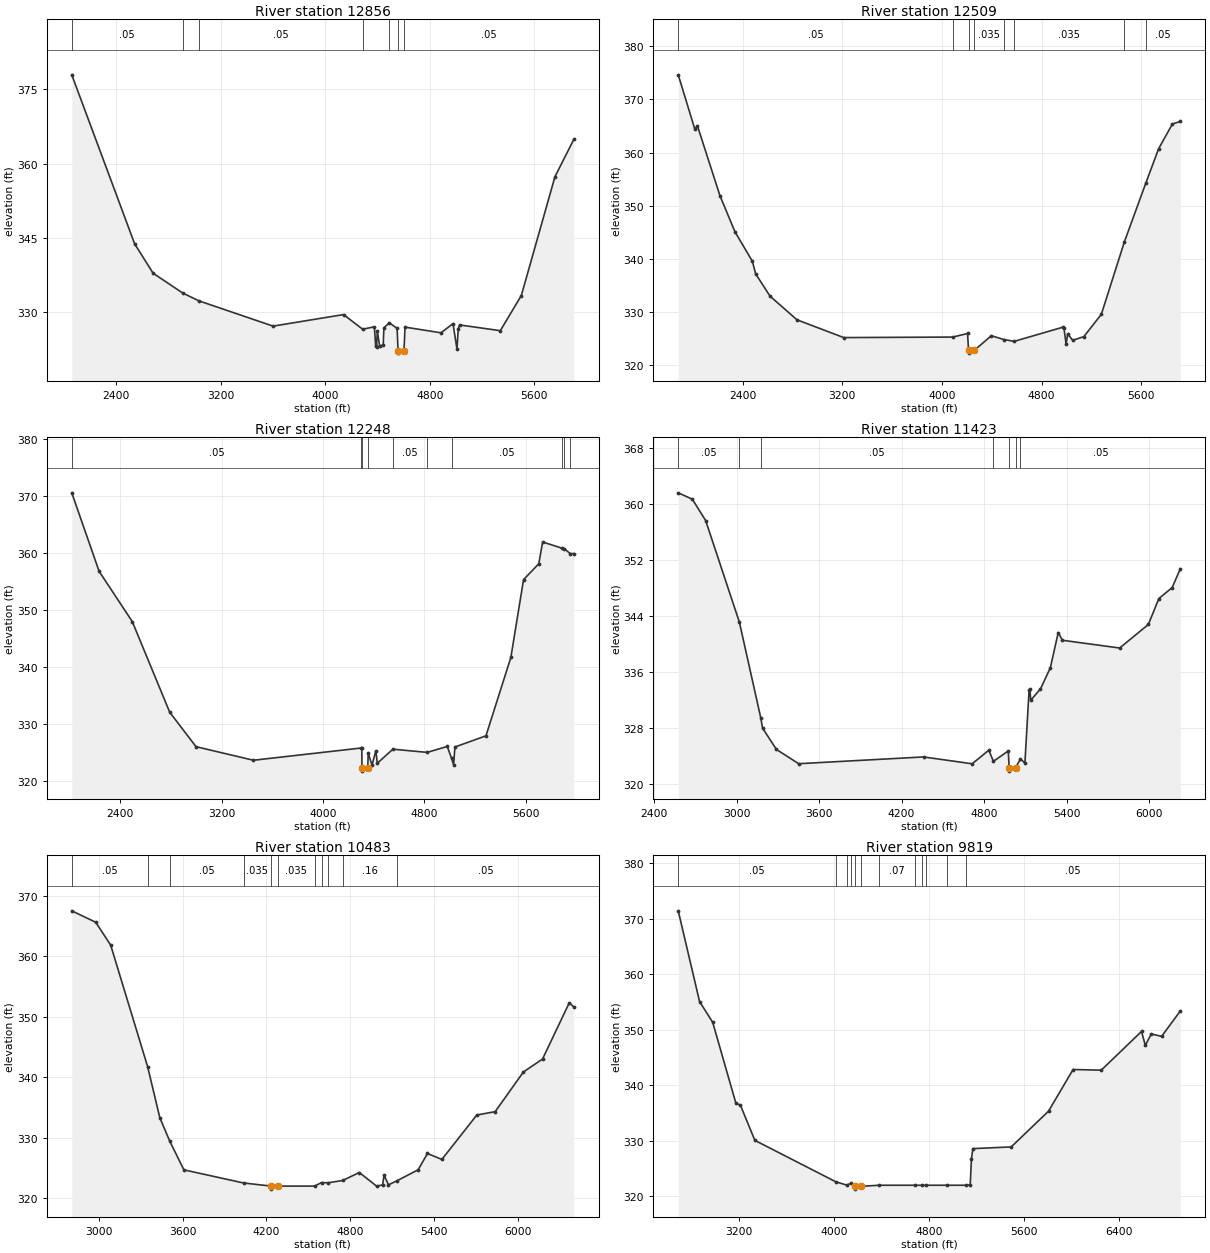
Type RM Length L Ch R = 1,12856,347,347,347
BEGIN DESCRIPTION:
South Twin Creek12855.764
END DESCRIPTION:
XS GIS Cut Line= 3
      2719706.05      6803830.52      2719120.56      6806712.65
      2719026.00      6807610.99
#Sta/Elev= 30
  2059.0  377.90  2540.3  343.80  2681.9  337.86  2908.2  333.87  3032.4  332.29
  3600.3  327.19  4139.9  329.52  4286.4  326.56  4375.9  327.06  4386.1  323.13
  4393.1  322.95  4398.2  326.24  4416.7  323.14  4443.7  323.38  4448.8  326.84
  4490.1  327.86  4550.1  326.74  4557.3  322.24  4558.3  321.74  4602.6  322.24
  4610.6  326.99  4886.1  325.84  4977.9  327.69  5008.4  322.59  5018.4  326.67
  5028.5  327.43  5340.2  326.27  5501.1  333.36  5758.8  357.35  5903.3  364.88
#Mann=7,-1,0
  2059.0    0.05       0  2908.2    0.07       0  3032.4    0.05       0
  4286.4    0.12       0  4490.1    0.05       0  4557.3    0.05       0
  4602.6    0.05       0
Bank Sta=4557.3,4602.6
Exp/Cntr=0.3,0.1

Type RM Length L Ch R = 1,12509,261,261,261
BEGIN DESCRIPTION:
South Twin Creek12508.997
END DESCRIPTION:
XS GIS Cut Line= 3
      2718524.97      6803707.99      2718805.94      6806811.20
      2718843.88      6807724.41
#Sta/Elev= 30
  1884.1  374.60  2017.6  364.36  2037.7  365.05  2218.5  351.92  2339.0  345.13
  2479.5  339.55  2505.1  337.22  2620.8  333.02  2837.1  328.57  3212.5  325.23
  4087.6  325.33  4206.6  326.00  4214.0  322.81  4215.0  322.31  4259.3  322.81
  4397.3  325.58  4497.1  324.87  4580.3  324.52  4969.7  327.17  4979.7  327.07
  4997.4  323.98  5009.8  325.96  5049.8  324.72  5139.9  325.41  5280.0  329.60
  5465.1  343.21  5637.4  354.28  5740.4  360.74  5850.5  365.36  5914.0  365.84
#Mann=8,-1,0
  1884.1    0.05       0  4087.6   0.035       0  4214.0   0.035       0
  4259.3   0.035       0  4497.1    0.05       0  4580.3   0.035       0
  5465.1   0.063       0  5637.4    0.05       0
Bank Sta=4214,4259.3
Exp/Cntr=0.3,0.1

Type RM Length L Ch R = 1,12248,825,825,825
BEGIN DESCRIPTION:
South Twin Creek12247.731
END DESCRIPTION:
XS GIS Cut Line= 3
      2718250.82      6803796.81      2718560.81      6806761.45
      2718630.34      6807736.37
#Sta/Elev= 30
  2019.2  370.61  2234.6  356.84  2496.0  348.02  2791.4  332.10  2998.7  326.05
  3451.2  323.67  4301.8  325.82  4305.8  325.89  4307.1  322.26  4308.1  321.76
  4352.5  322.26  4356.1  324.89  4386.2  322.81  4416.4  325.35  4428.2  323.15
  4550.7  325.61  4821.2  325.05  4979.4  326.09  5013.0  324.03  5029.6  322.87
  5039.7  325.99  5284.5  327.96  5480.8  341.71  5581.0  355.38  5700.9  358.15
  5731.4  361.98  5881.7  360.91  5902.5  360.81  5948.3  359.94  5977.4  359.95
#Mann=10,-1,0
  2019.2    0.05       0  4301.8    0.12       0  4307.1    0.07       0
  4352.5    0.12       0  4550.7    0.05       0  4821.2    0.12       0
  5013.0    0.05       0  5881.7   0.035       0  5902.5    0.05       0
  5948.3   0.035       0
Bank Sta=4307.1,4352.5
Exp/Cntr=0.3,0.1

Type RM Length L Ch R = 1,11423,940,940,940
BEGIN DESCRIPTION:
South Twin Creek11423.06
END DESCRIPTION:
XS GIS Cut Line= 3
      2718194.58      6804003.33      2717866.48      6806428.93
      2717699.27      6807619.97
#Sta/Elev= 30
  2576.1  361.62  2678.6  360.71  2775.6  357.65  3020.6  343.12  3176.2  329.43
  3189.3  327.96  3290.2  324.91  3451.7  322.87  4359.9  323.84  4713.1  322.86
  4834.1  324.80  4867.7  323.21  4975.4  324.69  4982.4  322.31  4983.4  321.81
  5028.9  322.31  5063.5  323.53  5096.6  322.99  5126.9  333.35  5133.5  333.57
  5138.6  331.94  5209.9  333.57  5281.2  336.58  5338.9  341.63  5369.2  340.53
  5785.4  339.42  5994.3  342.79  6070.6  346.50  6167.0  348.06  6226.5  350.76
#Mann=7,-1,0
  2576.1    0.05       0  3020.6    0.16       0  3176.2    0.05       0
  4867.7    0.16       0  4982.4    0.07       0  5028.9    0.16       0
  5063.5    0.05       0
Bank Sta=4982.4,5028.9
Exp/Cntr=0.3,0.1

Type RM Length L Ch R = 1,10483,664,664,664
BEGIN DESCRIPTION:
South Twin Creek10483.32
END DESCRIPTION:
XS GIS Cut Line= 3
      2718165.18      6803876.24      2717330.82      6805935.13
      2716867.09      6807231.88
#Sta/Elev= 30
  2805.0  367.55  2976.6  365.66  3083.8  361.88  3349.0  341.74  3436.0  333.32
  3507.1  329.45  3608.6  324.69  4036.0  322.52  4234.3  322.00  4235.3  321.50
  4280.9  322.00  4545.0  322.00  4596.1  322.59  4642.2  322.55  4746.8  322.93
  4866.0  324.25  4989.7  322.00  5032.8  322.20  5043.4  323.80  5075.2  322.21
  5137.5  322.90  5287.6  324.70  5354.7  327.40  5457.6  326.41  5708.1  333.76
  5839.9  334.32  6041.7  340.87  6179.3  343.03  6370.9  352.33  6403.7  351.65
#Mann=11,-1,0
  2805.0    0.05       0  3349.0    0.16       0  3507.1    0.05       0
  4036.0   0.035       0  4234.3    0.07       0  4280.9   0.035       0
  4545.0    0.15       0  4596.1   0.035       0  4642.2    0.15       0
  4746.8    0.16       0  5137.5    0.05       0
Bank Sta=4234.3,4280.9
Exp/Cntr=0.3,0.1

Type RM Length L Ch R = 1,9819,782,782,782
BEGIN DESCRIPTION:
South Twin Creek9819.11
END DESCRIPTION:
XS GIS Cut Line= 3
      2717963.99      6803672.44      2716756.02      6805670.77
      2716291.90      6807506.66
#Sta/Elev= 30
  2686.6  371.46  2866.2  355.11  2976.8  351.37  3172.7  336.74  3209.6  336.46
  3331.9  330.09  4013.1  322.63  4106.4  322.02  4143.5  322.39  4175.8  321.80
  4176.8  321.30  4222.4  321.80  4378.5  322.00  4679.6  322.00  4741.0  322.00
  4773.8  322.00  4949.8  322.00  5110.7  322.00  5145.7  322.05  5156.0  326.69
  5168.0  328.60  5491.1  328.91  5805.8  335.36  6012.1  342.86  6249.3  342.74
  6588.6  349.72  6620.7  347.21  6670.6  349.26  6757.8  348.84  6915.3  353.41
#Mann=12,-1,0
  2686.6    0.05       0  4013.1   0.035       0  4106.4    0.07       0
  4143.5   0.035       0  4175.8    0.07       0  4222.4   0.035       0
  4378.5    0.07       0  4679.6    0.16       0  4741.0    0.15       0
  4773.8    0.16       0  4949.8    0.15       0  5110.7    0.05       0
Bank Sta=4175.8,4222.4
Exp/Cntr=0.3,0.1