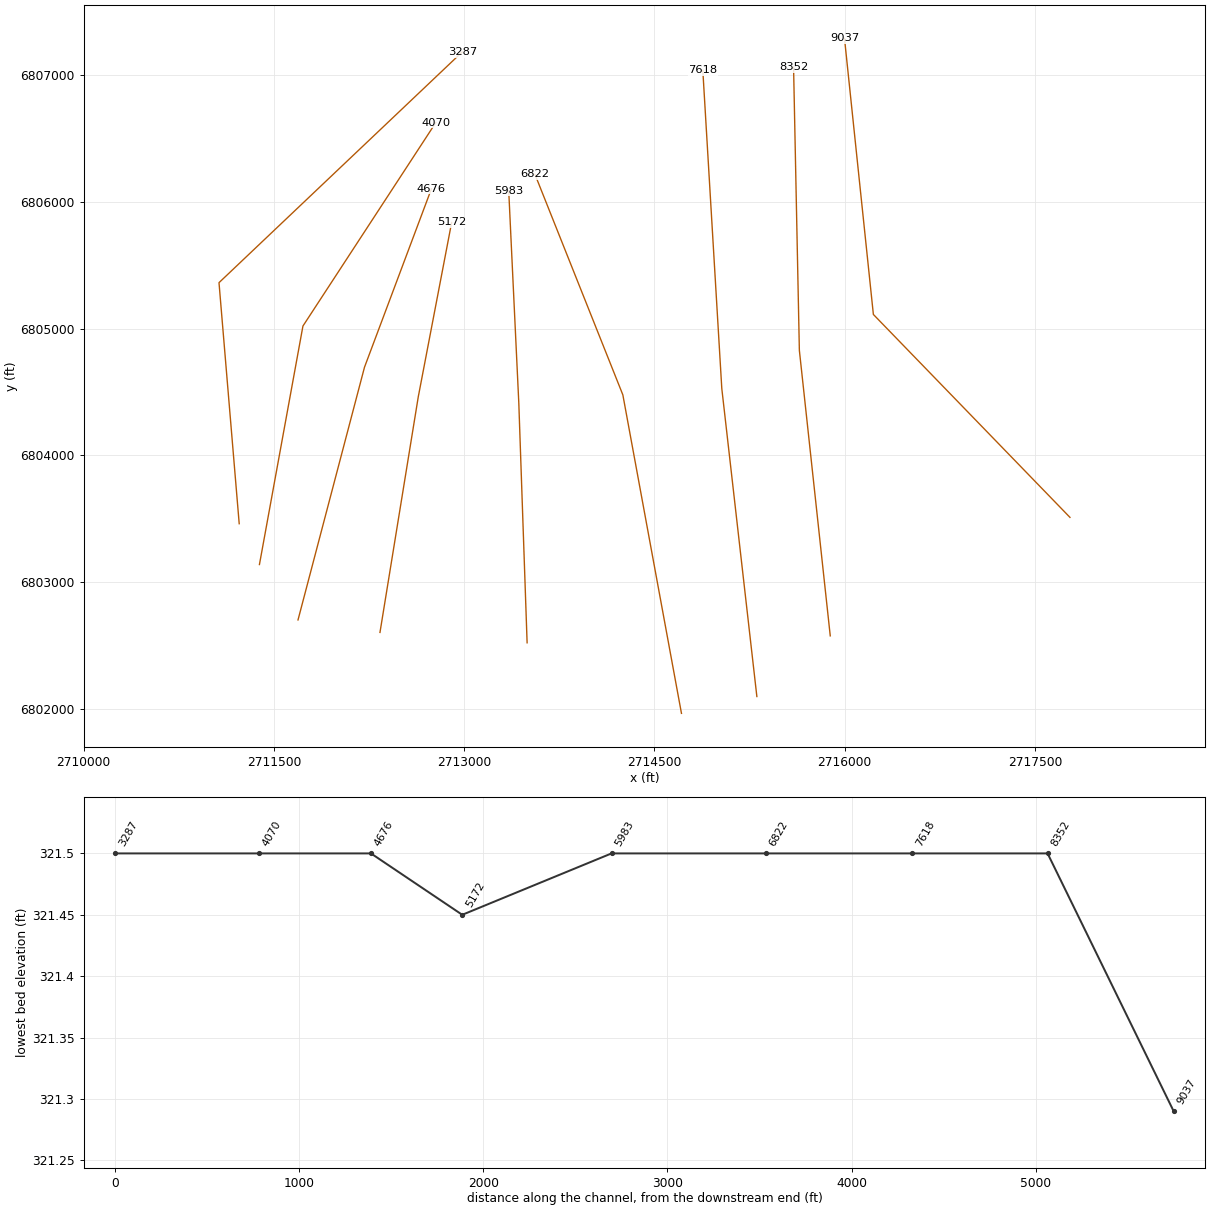
HEC-RAS study South Twin Creek.prj: South Twin Creek Base Level Engineering

--- South Twin Creek.g01 (geometry) --- (continued)

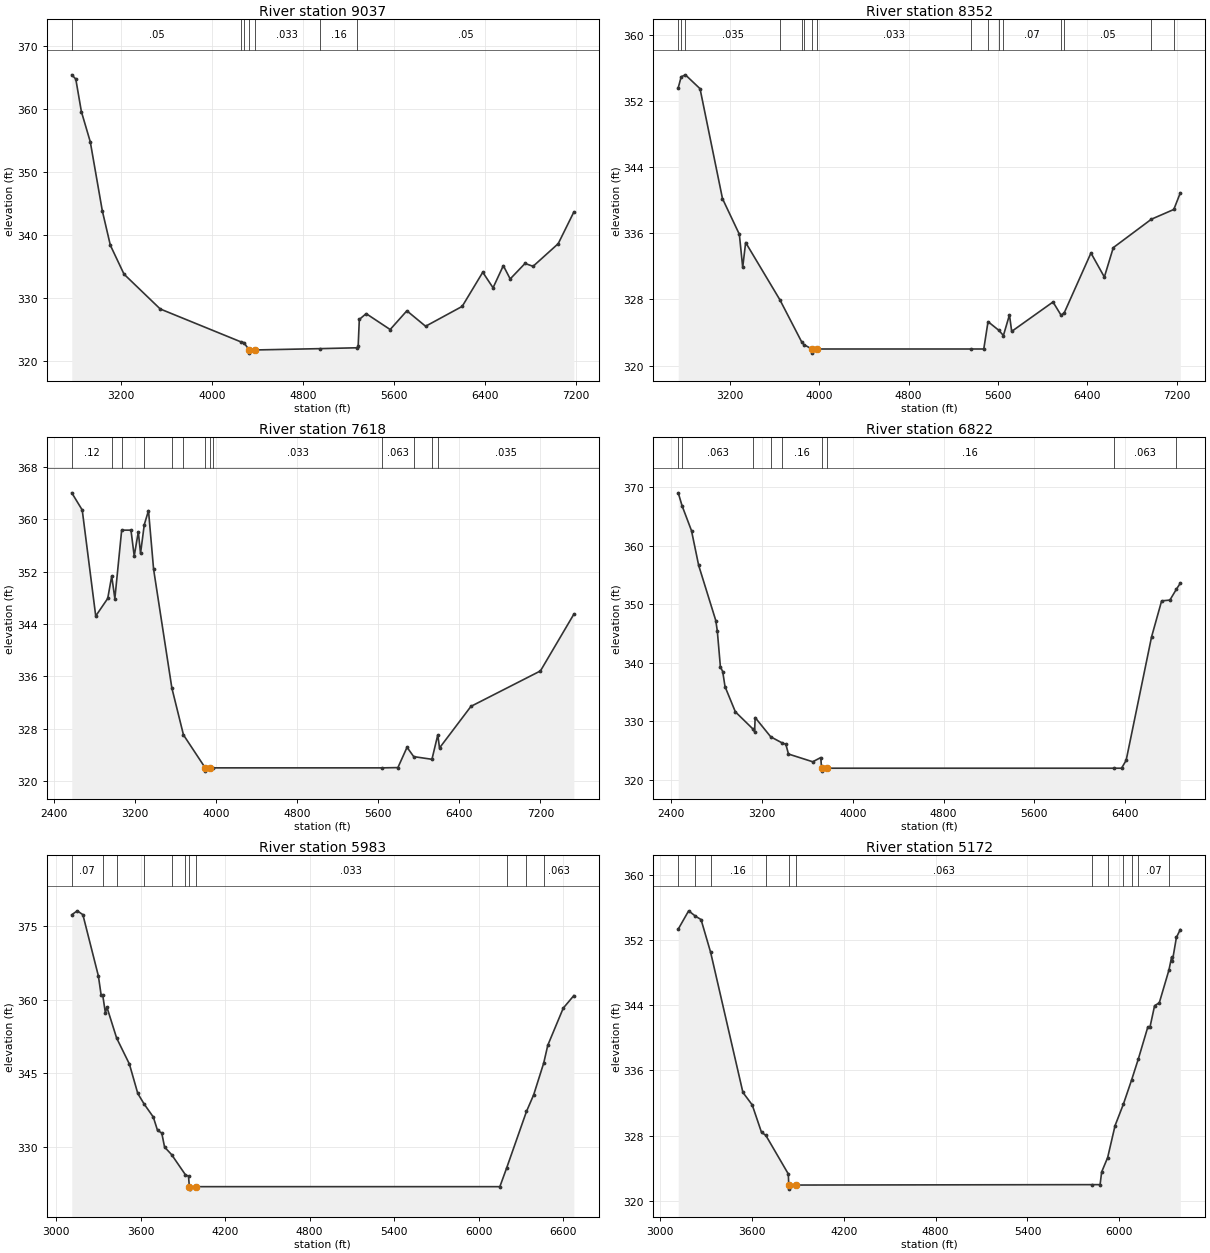
Type RM Length L Ch R = 1,9037,685,685,685
BEGIN DESCRIPTION:
South Twin Creek9036.804
END DESCRIPTION:
XS GIS Cut Line= 3
      2717775.98      6803511.02      2716226.00      6805111.00
      2715998.32      6807287.89
#Sta/Elev= 30
  2767.6  365.41  2802.9  364.74  2852.3  359.57  2930.3  354.80  3036.3  343.85
  3107.0  338.39  3227.1  333.81  3545.6  328.29  4258.7  323.05  4280.7  322.97
  4328.3  321.79  4329.3  321.29  4375.2  321.79  4949.0  322.00  5280.7  322.14
  5286.8  322.35  5296.9  326.63  5357.2  327.55  5568.3  325.03  5715.2  328.00
  5880.0  325.55  6201.8  328.70  6382.8  334.11  6473.3  331.65  6563.7  335.16
  6624.1  333.05  6754.8  335.51  6825.2  335.05  7046.4  338.64  7184.0  343.66
#Mann=7,-1,0
  2767.6    0.05       0  4258.7   0.035       0  4280.7   0.033       0
  4328.3    0.07       0  4375.2   0.033       0  4949.0    0.16       0
  5280.7    0.05       0
Bank Sta=4328.3,4375.2
Exp/Cntr=0.3,0.1

Type RM Length L Ch R = 1,8352,734,734,734
BEGIN DESCRIPTION:
South Twin Creek8351.99
END DESCRIPTION:
XS GIS Cut Line= 3
      2715886.08      6802576.80      2715642.54      6804827.96
      2715596.80      6807061.40
#Sta/Elev= 30
  2735.7  353.62  2762.0  354.95  2799.8  355.19  2931.0  353.51  3132.2  340.20
  3283.1  335.89  3313.3  331.88  3339.6  334.89  3646.2  327.96  3840.4  322.89
  3862.5  322.52  3933.3  322.00  3934.3  321.50  3980.7  322.00  5356.5  322.00
  5473.1  322.00  5511.2  325.31  5609.1  324.25  5649.0  323.63  5703.2  326.13
  5723.2  324.13  6093.3  327.69  6166.1  326.08  6194.3  326.39  6433.3  333.62
  6553.4  330.71  6633.4  334.27  6974.6  337.71  7175.5  338.89  7233.9  340.90
#Mann=16,-1,0
  2735.7    0.16       0  2762.0    0.07       0  2799.8   0.035       0
  3646.2    0.07       0  3840.4    0.12       0  3862.5   0.033       0
  3933.3   0.033       0  3980.7   0.033       0  5356.5   0.063       0
  5511.2    0.07       0  5609.1    0.16       0  5649.0    0.07       0
  6166.1    0.16       0  6194.3    0.05       0  6974.6    0.07       0
  7175.5   0.063       0
Bank Sta=3933.3,3980.7
Exp/Cntr=0.3,0.1

Type RM Length L Ch R = 1,7618,796,796,796
BEGIN DESCRIPTION:
South Twin Creek7617.75
END DESCRIPTION:
XS GIS Cut Line= 3
      2715307.44      6802098.35      2715030.93      6804527.32
      2714881.33      6807034.91
#Sta/Elev= 30
  2573.8  364.08  2677.1  361.45  2810.3  345.23  2928.7  347.92  2968.2  351.34
  2999.2  347.89  3066.5  358.37  3158.2  358.37  3190.4  354.40  3230.7  358.13
  3252.7  354.80  3289.5  359.20  3331.3  361.36  3381.6  352.39  3561.9  334.22
  3676.6  327.04  3891.3  322.00  3892.3  321.50  3938.9  322.00  3972.1  322.00
  5637.2  322.00  5793.5  322.04  5883.7  325.15  5949.5  323.72  6129.7  323.31
  6187.4  327.06  6204.2  325.04  6514.8  331.41  7200.6  336.83  7530.5  345.51
#Mann=13,-1,0
  2573.8    0.12       0  2968.2   0.063       0  3066.5    0.12       0
  3289.5    0.16       0  3561.9   0.035       0  3676.6    0.16       0
  3891.3   0.033       0  3938.9    0.16       0  3972.1   0.033       0
  5637.2   0.063       0  5949.5   0.035       0  6129.7   0.063       0
  6187.4   0.035       0
Bank Sta=3891.3,3938.9
Exp/Cntr=0.3,0.1

Type RM Length L Ch R = 1,6822,839,839,839
BEGIN DESCRIPTION:
South Twin Creek6822.49
END DESCRIPTION:
XS GIS Cut Line= 3
      2714712.99      6801965.61      2714250.80      6804476.91
      2713558.29      6806214.41
#Sta/Elev= 30
  2462.7  369.04  2496.3  366.84  2579.6  362.57  2642.8  356.64  2793.6  347.22
  2807.0  345.44  2834.2  339.32  2854.6  338.50  2874.9  335.94  2966.1  331.63
  3124.6  328.63  3135.4  328.24  3140.5  330.65  3277.9  327.36  3377.0  326.33
  3410.8  326.09  3434.1  324.42  3647.7  323.10  3718.8  323.82  3725.5  322.00
  3726.5  321.50  3773.3  322.00  6298.2  322.00  6368.8  322.00  6409.3  323.34
  6633.1  344.42  6722.0  350.58  6794.8  350.72  6852.2  352.58  6886.6  353.60
#Mann=9,-1,0
  2462.7    0.16       0  2496.3   0.063       0  3124.6    0.16       0
  3277.9   0.063       0  3377.0    0.16       0  3725.5   0.033       0
  3773.3    0.16       0  6298.2   0.063       0  6852.2   0.035       0
Bank Sta=3725.5,3773.3
Exp/Cntr=0.3,0.1

Type RM Length L Ch R = 1,5983,811,811,811
BEGIN DESCRIPTION:
South Twin Creek5983.171
END DESCRIPTION:
XS GIS Cut Line= 3
      2713496.00      6802522.13      2713430.55      6804411.00
      2713351.00      6806086.01
#Sta/Elev= 30
  3110.0  377.21  3148.9  378.01  3188.9  377.23  3299.0  364.79  3319.0  360.83
  3329.6  360.95  3349.0  357.25  3359.0  358.51  3428.8  352.17  3519.1  346.92
  3579.1  340.92  3623.4  338.81  3689.2  336.14  3719.2  333.43  3749.3  332.90
  3769.3  330.04  3819.2  328.51  3917.1  324.43  3939.4  324.12  3945.4  322.00
  3946.4  321.50  3993.4  322.00  6151.3  322.00  6198.6  325.72  6340.4  337.27
  6391.6  340.66  6463.0  347.12  6491.7  350.71  6601.8  358.26  6676.9  360.80
#Mann=11,-1,0
  3110.0    0.07       0  3329.6   0.035       0  3428.8   0.063       0
  3623.4    0.16       0  3819.2   0.035       0  3917.1   0.033       0
  3945.4   0.033       0  3993.4   0.033       0  6198.6   0.063       0
  6340.4    0.07       0  6463.0   0.063       0
Bank Sta=3945.4,3993.4
Exp/Cntr=0.3,0.1

Type RM Length L Ch R = 1,5172,496,496,496
BEGIN DESCRIPTION:
South Twin Creek5171.655
END DESCRIPTION:
XS GIS Cut Line= 3
      2712335.91      6802603.80      2712637.94      6804461.81
      2712900.99      6805835.96
#Sta/Elev= 30
  3117.6  353.31  3185.7  355.55  3229.8  354.90  3266.7  354.48  3329.4  350.46
  3540.3  333.30  3601.1  331.77  3661.8  328.41  3689.7  328.05  3837.0  323.31
  3840.0  321.95  3841.0  321.45  3888.9  321.95  5824.1  322.00  5874.8  322.00
  5885.0  323.55  5924.3  325.32  5972.6  329.23  6027.0  331.86  6081.2  334.85
  6124.6  337.39  6185.9  341.26  6200.6  341.28  6231.1  343.93  6261.7  344.28
  6325.0  348.31  6342.0  349.86  6347.1  349.38  6373.7  352.30  6399.1  353.26
#Mann=12,-1,0
  3117.6    0.16       0  3229.8   0.063       0  3329.4    0.16       0
  3689.7   0.063       0  3840.0   0.033       0  3888.9   0.063       0
  5824.1    0.07       0  5924.3   0.063       0  6027.0    0.07       0
  6081.2   0.063       0  6124.6    0.07       0  6325.0   0.063       0
Bank Sta=3840,3888.9
Exp/Cntr=0.3,0.1

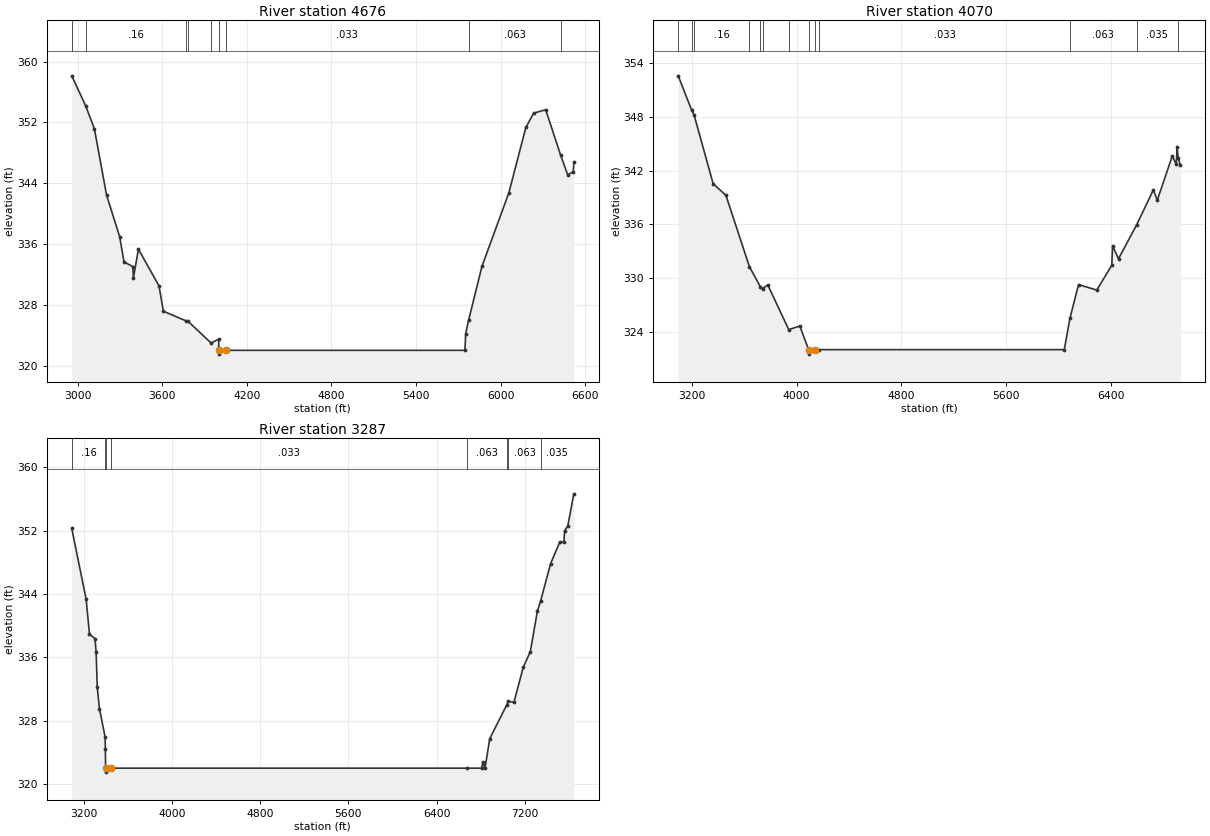
Type RM Length L Ch R = 1,4676,606,606,606
BEGIN DESCRIPTION:
South Twin Creek4675.8
END DESCRIPTION:
XS GIS Cut Line= 3
      2711689.69      6802702.38      2712213.94      6804695.14
      2712741.67      6806101.73
#Sta/Elev= 30
  2957.5  358.12  3055.5  354.20  3118.1  351.15  3204.2  342.44  3297.3  336.95
  3328.3  333.63  3390.1  333.03  3395.3  331.55  3430.4  335.31  3576.5  330.48
  3607.5  327.15  3765.4  325.90  3783.7  325.80  3945.9  322.97  4000.4  323.47
  4000.6  322.00  4001.6  321.50  4049.5  322.00  5747.6  322.00  5752.9  324.19
  5773.0  325.93  5868.6  333.07  6059.0  342.71  6180.0  351.34  6235.2  353.21
  6320.6  353.66  6427.1  347.66  6476.9  345.08  6516.4  345.51  6520.4  346.81
#Mann=9,-1,0
  2957.5   0.035       0  3055.5    0.16       0  3765.4    0.12       0
  3783.7   0.063       0  3945.9   0.033       0  4000.6   0.033       0
  4049.5   0.033       0  5773.0   0.063       0  6427.1   0.035       0
Bank Sta=4000.6,4049.5
Exp/Cntr=0.3,0.1

Type RM Length L Ch R = 1,4070,783,783,783
BEGIN DESCRIPTION:
South Twin Creek4070.03
END DESCRIPTION:
XS GIS Cut Line= 3
      2711385.55      6803139.22      2711728.55      6805019.54
      2712776.36      6806623.82
#Sta/Elev= 30
  3098.2  352.60  3200.3  348.77  3218.2  348.27  3364.3  340.55  3461.9  339.24
  3640.8  331.27  3724.5  329.02  3740.8  328.83  3781.1  329.22  3940.8  324.24
  4025.1  324.64  4092.0  322.00  4093.0  321.50  4141.0  322.00  4173.1  322.00
  6041.3  322.00  6084.2  325.50  6149.9  329.27  6288.7  328.66  6403.3  331.42
  6409.3  333.58  6454.6  332.16  6592.8  335.95  6720.0  339.85  6750.2  338.70
  6864.8  343.66  6895.0  342.71  6901.0  344.64  6909.7  343.46  6925.7  342.61
#Mann=13,-1,0
  3098.2    0.16       0  3200.3    0.12       0  3218.2    0.16       0
  3640.8    0.12       0  3724.5    0.16       0  3740.8    0.12       0
  3940.8   0.063       0  4092.0   0.033       0  4141.0   0.063       0
  4173.1   0.033       0  6084.2   0.063       0  6592.8   0.035       0
  6909.7   0.063       0
Bank Sta=4092,4141
Exp/Cntr=0.3,0.1

Type RM Length L Ch R = 1,3287,0,0,0
BEGIN DESCRIPTION:
South Twin Creek3286.592
END DESCRIPTION:
XS GIS Cut Line= 3
      2711226.00      6803460.97      2711066.74      6805361.51
      2712984.16      6807180.56
#Sta/Elev= 30
  3092.8  352.29  3223.3  343.32  3253.4  338.92  3303.6  338.37  3313.6  336.62
  3323.6  332.24  3343.7  329.51  3395.6  325.89  3397.1  324.39  3399.5  322.00
  3400.5  321.50  3448.5  322.00  6678.4  322.00  6809.9  322.00  6817.2  322.78
  6838.2  322.02  6880.7  325.73  7034.7  329.99  7048.3  330.48  7099.9  330.30
  7184.9  334.77  7248.4  336.71  7312.3  341.81  7342.4  343.15  7432.4  347.84
  7517.4  350.62  7552.6  350.53  7559.8  352.00  7588.1  352.61  7643.0  356.66
#Mann=8,-1,0
  3092.8    0.16       0  3397.1   0.033       0  3399.5   0.033       0
  3448.5   0.033       0  6678.4   0.063       0  7034.7   0.035       0
  7048.3   0.063       0  7342.4   0.035       0
Bank Sta=3399.5,3448.5
Exp/Cntr=0.3,0.1

Chan Stop Cuts=-1