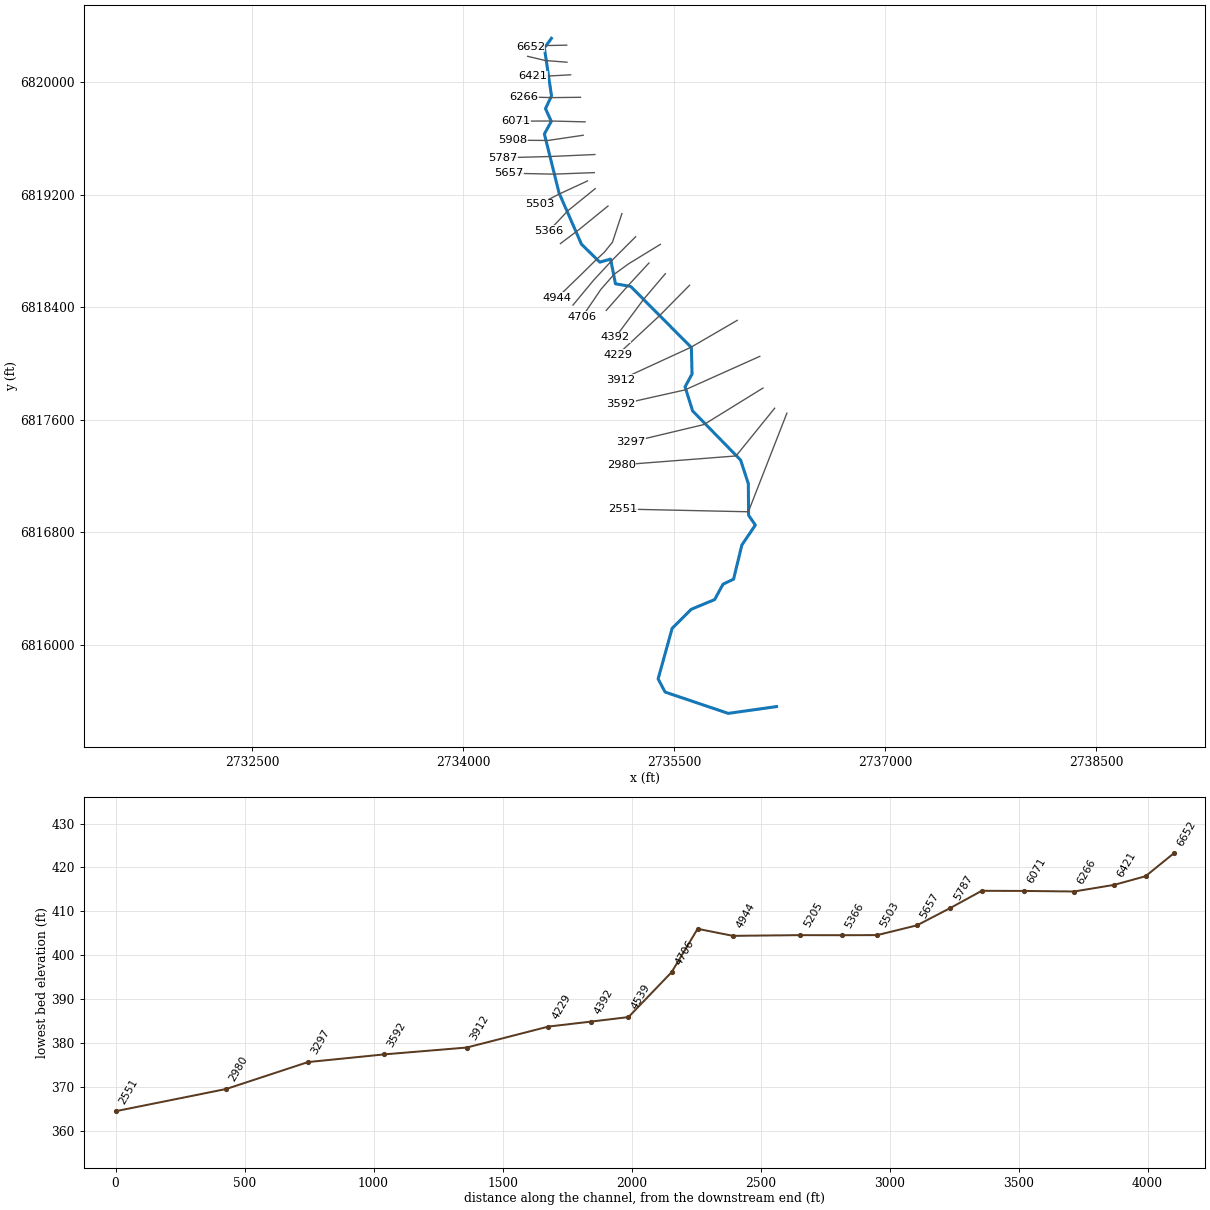
--- South Twin Creek Trib A.prj (project) ---

Proj Title=South Twin Creek Trib A Base Level Engineering
Current Plan=p01
Default Exp/Contr=0.3,0.1
English Units
Geom File=g01
Flow File=f01
Plan File=p01
BEGIN DESCRIPTION:
South Twin Creek Trib A
END DESCRIPTION:

--- South Twin Creek Trib A.p01 (plan) ---

Plan Title=Multiple Run
Short Identifier=Multiple
Geom File=g01
Flow File=f01
Subcritical Flow
K Sum by GR= 0
Std Step Tol= 0.01
Critical Tol= 0.01
Num of Std Step Trials= 20
Max Error Tol= 0.3
Flow Tol Ratio= 0.001
Split Flow NTrial= 30
Split Flow Tol= 0.02
Split Flow Ratio= 0.02
Log Output Level= 0
Friction Slope Method= 1
Unsteady Friction Slope Method= 2
Unsteady Bridges Friction Slope Method= 1
Parabolic Critical Depth
Global Vel Dist=  1 , 1 , 1
Global Log Level= 0
CheckData=True
Encroach Param= -1, 0, 0, 0
BEGIN DESCRIPTION:
Multiple Run
END DESCRIPTION:

--- South Twin Creek Trib A.f01 (steady flow) ---

Flow Title=Multiple
Number of Profiles=7
Profile Names=10-year,25-year,50-year,1pct_min,100-year,1pct_plu,500-year
River Rch & RM= South Twin Creek,Reach-1,6652
     280     357     417     242     484     965     648
Boundary for River Rch & Prof#=South Twin Creek,Reach-1,1
Up Type=0
Dn Type=3
Dn Slope=0.005
Boundary for River Rch & Prof#=South Twin Creek,Reach-1,2
Up Type=0
Dn Type=3
Dn Slope=0.005
Boundary for River Rch & Prof#=South Twin Creek,Reach-1,3
Up Type=0
Dn Type=3
Dn Slope=0.005
Boundary for River Rch & Prof#=South Twin Creek,Reach-1,4
Up Type=0
Dn Type=3
Dn Slope=0.005
Boundary for River Rch & Prof#=South Twin Creek,Reach-1,5
Up Type=0
Dn Type=3
Dn Slope=0.005
Boundary for River Rch & Prof#=South Twin Creek,Reach-1,6
Up Type=0
Dn Type=3
Dn Slope=0.005
Boundary for River Rch & Prof#=South Twin Creek,Reach-1,7
Up Type=0
Dn Type=3
Dn Slope=0.005

--- South Twin Creek Trib A.g01 (geometry) ---

Geom Title=Existing Conditions

River Reach=South Twin Creek,Reach-1
Reach XY= 30
      2734626.00      6820311.00      2734575.91      6820242.70
      2734626.40      6819901.70      2734583.59      6819810.99
      2734625.00      6819720.86      2734575.72      6819631.18
      2734679.83      6819212.58      2734839.40      6818847.69
      2734969.34      6818720.31      2735046.49      6818741.83
      2735081.04      6818566.08      2735189.27      6818547.58
      2735620.54      6818113.45      2735625.30      6817924.91
      2735575.62      6817833.81      2735629.61      6817662.50
      2735970.48      6817313.43      2736025.48      6817145.78
      2736027.24      6816921.50      2736075.12      6816851.13
      2735979.56      6816709.53      2735920.38      6816466.62
      2735845.73      6816431.42      2735786.00      6816321.63
      2735619.94      6816252.86      2735483.86      6816117.17
      2735384.21      6815757.73      2735434.00      6815664.32
      2735882.13      6815512.86      2736226.00      6815561.00

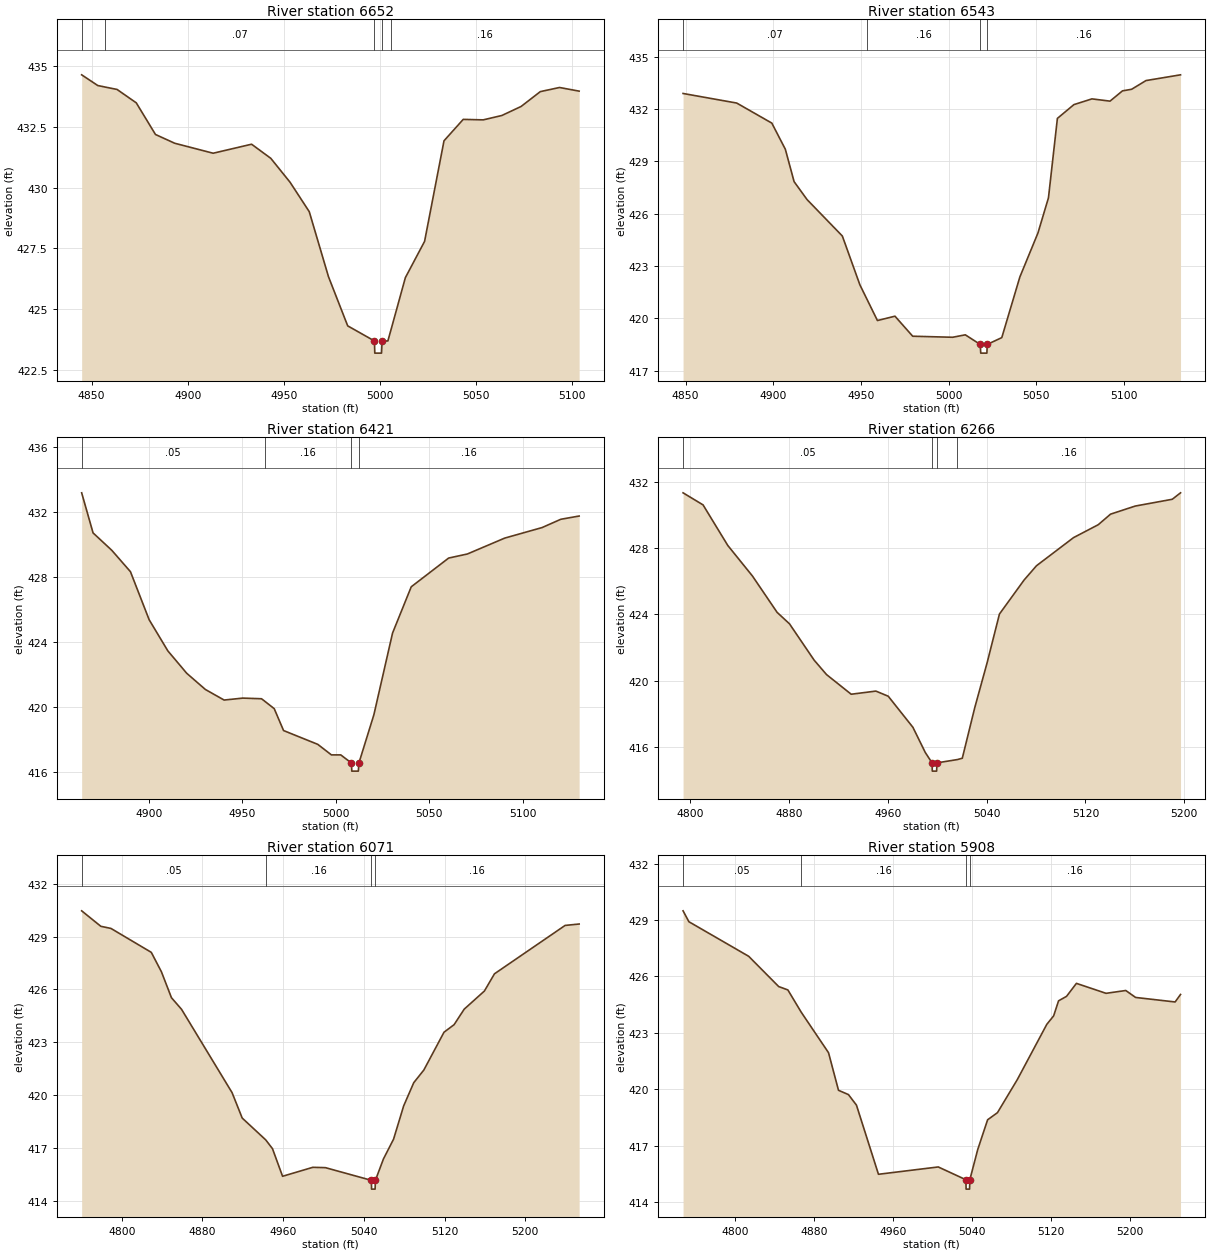
Type RM Length L Ch R = 1,6652,109,109,109
BEGIN DESCRIPTION:
South Twin Creek Trib A6652.455
END DESCRIPTION:
XS GIS Cut Line= 3
      2734734.36      6820262.43      2734579.19      6820259.60
      2734475.86      6820252.00
#Sta/Elev= 30
  4844.8  434.63  4853.2  434.19  4856.9  434.13  4863.2  434.03  4873.2  433.48
  4883.2  432.18  4893.2  431.82  4913.2  431.41  4933.2  431.78  4943.2  431.20
  4953.2  430.22  4963.2  429.01  4973.2  426.34  4983.2  424.32  4997.1  423.70
  4997.3  423.20  5000.8  423.20  5001.1  423.70  5004.1  423.70  5005.9  424.21
  5013.2  426.30  5023.2  427.79  5033.3  431.92  5043.3  432.80  5053.7  432.78
  5063.4  432.96  5073.4  433.33  5083.4  433.94  5093.4  434.11  5103.6  433.96
#Mann=5,-1,0
  4844.8    0.05       0  4856.9    0.07       0  4997.1    0.07       0
  5001.1    0.07       0  5005.9    0.16       0
Bank Sta=4997.1,5001.1
Exp/Cntr=0.3,0.1

Type RM Length L Ch R = 1,6543,122,122,122
BEGIN DESCRIPTION:
South Twin Creek Trib A6543.37
END DESCRIPTION:
XS GIS Cut Line= 3
      2734736.48      6820141.25      2734583.28      6820153.22
      2734456.84      6820183.15
#Sta/Elev= 30
  4848.6  432.90  4879.2  432.35  4899.2  431.20  4906.9  429.70  4911.9  427.84
  4919.3  426.81  4939.4  424.72  4949.4  421.92  4953.6  421.06  4959.4  419.87
  4969.4  420.12  4979.5  418.97  5002.3  418.91  5009.5  419.05  5018.0  418.50
  5018.3  418.00  5021.8  418.00  5022.0  418.50  5030.3  418.89  5040.6  422.37
  5050.9  424.89  5056.9  426.91  5062.0  431.47  5071.4  432.26  5081.7  432.59
  5092.0  432.46  5099.1  433.05  5104.3  433.14  5112.5  433.64  5132.2  433.97
#Mann=4,-1,0
  4848.6    0.07       0  4953.6    0.16       0  5018.0    0.07       0
  5022.0    0.16       0
Bank Sta=5018,5022
Exp/Cntr=0.3,0.1

Type RM Length L Ch R = 1,6421,155,155,155
BEGIN DESCRIPTION:
South Twin Creek Trib A6420.54
END DESCRIPTION:
XS GIS Cut Line= 3
      2734762.08      6820051.81      2734626.28      6820044.27
      2734496.24      6820040.33
#Sta/Elev= 30
  4864.0  433.18  4870.1  430.71  4880.1  429.64  4890.1  428.32  4900.1  425.36
  4910.1  423.44  4920.2  422.06  4930.2  421.06  4940.2  420.41  4950.2  420.53
  4960.2  420.49  4961.9  420.34  4967.0  419.88  4972.0  418.53  4990.3  417.68
  4997.6  417.03  5002.6  417.03  5008.3  416.53  5008.5  416.03  5012.0  416.03
  5012.3  416.53  5020.3  419.50  5030.3  424.54  5040.3  427.39  5060.3  429.16
  5070.3  429.41  5090.3  430.39  5110.3  431.04  5120.3  431.55  5130.1  431.75
#Mann=4,-1,0
  4864.0    0.05       0  4961.9    0.16       0  5008.3    0.07       0
  5012.3    0.16       0
Bank Sta=5008.3,5012.3
Exp/Cntr=0.3,0.1

Type RM Length L Ch R = 1,6266,195,195,195
BEGIN DESCRIPTION:
South Twin Creek Trib A6265.86
END DESCRIPTION:
XS GIS Cut Line= 3
      2734832.23      6819891.87      2734626.13      6819889.60
      2734429.32      6819895.25
#Sta/Elev= 30
  4794.0  431.35  4810.2  430.62  4830.2  428.17  4850.2  426.32  4870.2  424.12
  4880.2  423.43  4900.2  421.23  4910.2  420.36  4930.2  419.17  4950.2  419.36
  4960.2  419.05  4980.2  417.17  4990.2  415.65  4995.7  415.02  4995.9  414.52
  4999.4  414.52  4999.7  415.02  5016.3  415.22  5020.2  415.30  5030.3  418.36
  5040.3  421.07  5050.3  424.02  5070.3  426.08  5080.3  426.94  5110.3  428.64
  5130.3  429.42  5140.3  430.06  5160.3  430.55  5190.3  430.96  5197.0  431.35
#Mann=4,-1,0
  4794.0    0.05       0  4995.7    0.05       0  4999.7    0.05       0
  5016.3    0.16       0
Bank Sta=4995.7,4999.7
Exp/Cntr=0.3,0.1

Type RM Length L Ch R = 1,6071,163,163,163
BEGIN DESCRIPTION:
South Twin Creek Trib A6071.22
END DESCRIPTION:
XS GIS Cut Line= 3
      2734865.01      6819717.30      2734623.45      6819723.28
      2734372.08      6819722.54
#Sta/Elev= 30
  4760.3  430.47  4779.3  429.59  4789.3  429.47  4829.3  428.11  4839.3  427.01
  4849.3  425.53  4859.3  424.87  4909.4  420.13  4919.4  418.69  4942.7  417.45
  4949.4  416.95  4959.4  415.38  4989.4  415.89  5001.9  415.87  5047.4  415.15
  5047.6  414.65  5051.1  414.65  5051.4  415.15  5059.4  416.37  5069.4  417.49
  5079.4  419.38  5089.4  420.70  5099.4  421.42  5119.4  423.57  5129.4  424.00
  5139.4  424.88  5159.4  425.91  5169.4  426.89  5239.4  429.64  5253.3  429.72
#Mann=4,-1,0
  4760.3    0.05       0  4942.7    0.16       0  5047.4    0.07       0
  5051.4    0.16       0
Bank Sta=5047.4,5051.4
Exp/Cntr=0.3,0.1

Type RM Length L Ch R = 1,5908,121,121,121
BEGIN DESCRIPTION:
South Twin Creek Trib A5908.11
END DESCRIPTION:
XS GIS Cut Line= 3
      2734851.83      6819622.17      2734601.35      6819585.08
      2734350.47      6819586.93
#Sta/Elev= 30
  4747.2  429.49  4753.1  428.91  4813.7  427.07  4844.1  425.46  4853.4  425.28
  4867.0  424.09  4894.6  421.94  4904.7  419.94  4914.8  419.71  4922.9  419.15
  4945.2  415.47  5005.8  415.86  5033.8  415.18  5034.0  414.68  5037.5  414.68
  5037.8  415.18  5045.8  416.79  5055.8  418.37  5065.8  418.75  5085.8  420.50
  5115.8  423.45  5122.7  423.90  5127.7  424.70  5135.8  424.94  5145.8  425.63
  5175.8  425.10  5195.8  425.25  5205.8  424.88  5245.8  424.64  5251.3  425.04
#Mann=4,-1,0
  4747.2    0.05       0  4867.0    0.16       0  5033.8    0.07       0
  5037.8    0.16       0
Bank Sta=5033.8,5037.8
Exp/Cntr=0.3,0.1

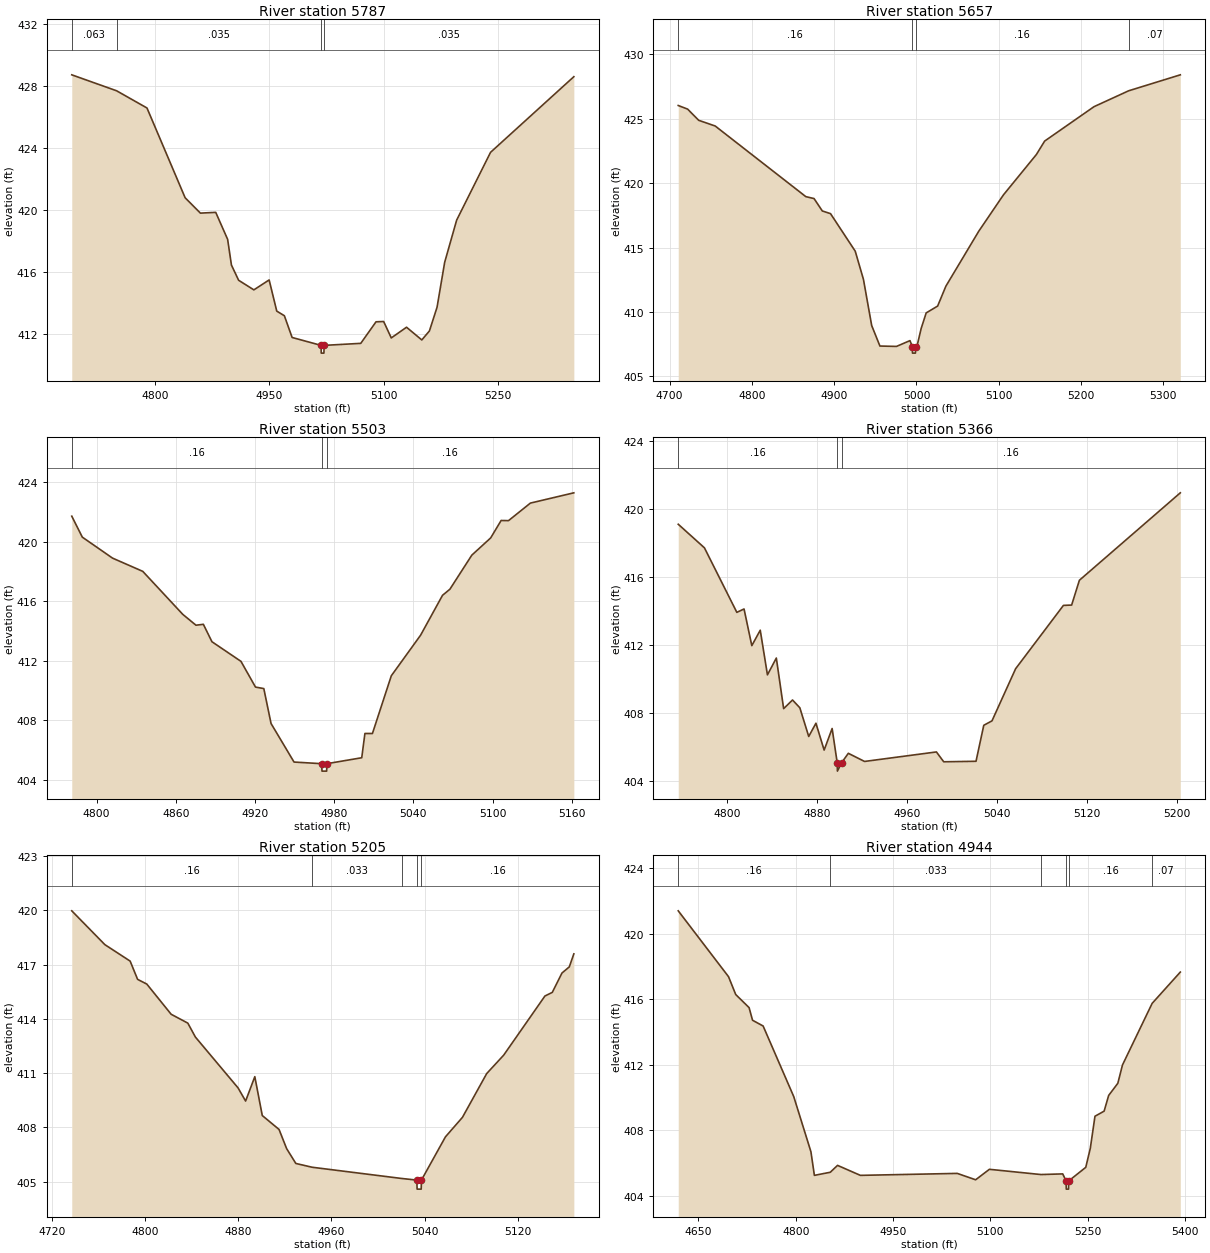
Type RM Length L Ch R = 1,5787,130,130,130
BEGIN DESCRIPTION:
South Twin Creek Trib A5786.57
END DESCRIPTION:
XS GIS Cut Line= 3
      2734934.47      6819485.15      2734626.09      6819471.37
      2734276.81      6819461.82
#Sta/Elev= 30
  4691.3  428.73  4750.1  427.70  4789.9  426.59  4839.9  420.80  4859.9  419.81
  4880.0  419.86  4895.6  418.12  4900.6  416.46  4910.0  415.48  4930.0  414.86
  4950.0  415.50  4960.0  413.49  4970.0  413.19  4980.1  411.79  5018.1  411.28
  5018.3  410.78  5021.8  410.78  5022.1  411.28  5070.1  411.41  5090.1  412.80
  5100.1  412.82  5110.1  411.76  5130.1  412.45  5150.1  411.63  5160.1  412.21
  5170.1  413.74  5180.1  416.64  5195.8  419.36  5240.2  423.73  5349.4  428.61
#Mann=4,-1,0
  4691.3   0.063       0  4750.1   0.035       0  5018.1   0.035       0
  5022.1   0.035       0
Bank Sta=5018.1,5022.1
Exp/Cntr=0.3,0.1

Type RM Length L Ch R = 1,5657,154,154,154
BEGIN DESCRIPTION:
South Twin Creek Trib A5656.62
END DESCRIPTION:
XS GIS Cut Line= 3
      2734930.88      6819356.48      2734641.19      6819345.74
      2734321.25      6819352.47
#Sta/Elev= 30
  4710.6  426.02  4722.0  425.74  4735.5  424.87  4755.5  424.43  4865.6  418.95
  4875.6  418.80  4885.6  417.84  4895.6  417.63  4925.6  414.72  4935.6  412.53
  4945.6  408.95  4955.6  407.36  4975.7  407.33  4992.1  407.78  4995.0  407.31
  4995.2  406.81  4998.7  406.81  4999.0  407.31  5000.5  407.31  5005.7  408.72
  5011.8  409.93  5025.7  410.46  5035.7  412.00  5075.7  416.27  5105.7  419.09
  5145.7  422.22  5155.7  423.26  5215.7  425.93  5257.7  427.16  5320.5  428.40
#Mann=4,-1,0
  4710.6    0.16       0  4995.0    0.07       0  4999.0    0.16       0
  5257.7    0.07       0
Bank Sta=4995,4999
Exp/Cntr=0.3,0.1

Type RM Length L Ch R = 1,5503,137,137,137
BEGIN DESCRIPTION:
South Twin Creek Trib A5503.12
END DESCRIPTION:
XS GIS Cut Line= 3
      2734882.32      6819297.49      2734680.55      6819203.97
      2734539.95      6819131.87
#Sta/Elev= 30
  4781.2  421.73  4789.2  420.32  4812.1  418.91  4835.0  418.02  4865.3  415.13
  4875.3  414.40  4880.9  414.46  4887.4  413.29  4909.4  411.97  4920.4  410.24
  4926.7  410.14  4932.2  407.79  4949.6  405.20  4970.5  405.09  4970.8  404.59
  4974.3  404.59  4974.5  405.09  5000.9  405.49  5003.3  407.12  5009.0  407.12
  5023.3  411.00  5045.5  413.73  5062.1  416.41  5067.7  416.82  5084.3  419.11
  5098.6  420.27  5106.5  421.44  5112.1  421.43  5128.7  422.61  5161.6  423.30
#Mann=3,-1,0
  4781.2    0.16       0  4970.5    0.07       0  4974.5    0.16       0
Bank Sta=4970.5,4974.5
Exp/Cntr=0.3,0.1

Type RM Length L Ch R = 1,5366,161,161,161
BEGIN DESCRIPTION:
South Twin Creek Trib A5366.28
END DESCRIPTION:
XS GIS Cut Line= 3
      2734936.86      6819242.47      2734743.97      6819086.41
      2734607.72      6818942.49
#Sta/Elev= 30
  4756.7  419.10  4780.0  417.71  4808.8  413.91  4815.2  414.11  4822.1  411.95
  4829.6  412.86  4836.0  410.23  4843.9  411.22  4850.4  408.24  4858.3  408.75
  4864.8  408.29  4872.7  406.60  4879.1  407.38  4886.4  405.80  4893.5  407.07
  4898.0  405.06  4898.2  404.56  4902.0  405.06  4907.9  405.61  4922.3  405.13
  4986.2  405.69  4992.7  405.11  5021.4  405.14  5028.3  407.26  5035.6  407.52
  5056.6  410.59  5099.1  414.32  5106.4  414.34  5113.3  415.80  5203.0  420.95
#Mann=3,-1,0
  4756.7    0.16       0  4898.0    0.07       0  4902.0    0.16       0
Bank Sta=4898,4902
Exp/Cntr=0.3,0.1

Type RM Length L Ch R = 1,5205,261,261,261
BEGIN DESCRIPTION:
South Twin Creek Trib A5205.25
END DESCRIPTION:
XS GIS Cut Line= 3
      2735028.01      6819119.09      2734822.49      6818951.88
      2734689.90      6818852.08
#Sta/Elev= 30
  4737.1  419.97  4765.5  418.10  4787.2  417.19  4793.6  416.18  4801.5  415.92
  4822.4  414.25  4836.7  413.76  4843.2  412.99  4879.8  410.18  4886.3  409.45
  4894.2  410.80  4900.6  408.65  4915.0  407.88  4921.5  406.82  4929.4  406.00
  4943.4  405.79  5020.1  405.17  5033.2  405.08  5033.5  404.58  5037.0  404.58
  5037.2  405.08  5057.8  407.47  5072.4  408.55  5093.2  410.97  5107.8  411.99
  5143.2  415.26  5149.5  415.46  5157.8  416.53  5164.1  416.87  5168.0  417.59
#Mann=5,-1,0
  4737.1    0.16       0  4943.4   0.033       0  5020.1    0.16       0
  5033.2   0.033       0  5037.2    0.16       0
Bank Sta=5033.2,5037.2
Exp/Cntr=0.3,0.1

Type RM Length L Ch R = 1,4944,137,137,137
BEGIN DESCRIPTION:
South Twin Creek Trib A4943.99
END DESCRIPTION:
XS GIS Cut Line= 6
      2735126.70      6819065.19      2735059.82      6818862.24
      2735000.90      6818789.42      2734945.14      6818738.31
      2734830.21      6818625.19      2734665.23      6818465.73
#Sta/Elev= 30
  4618.9  421.41  4696.4  417.39  4707.5  416.30  4728.1  415.50  4733.4  414.73
  4749.7  414.38  4796.9  410.07  4823.4  406.70  4828.7  405.26  4853.2  405.45
  4864.4  405.87  4899.6  405.26  5048.9  405.38  5077.2  404.99  5098.4  405.63
  5177.9  405.31  5211.4  405.35  5216.6  404.92  5216.9  404.42  5220.4  404.42
  5220.6  404.92  5246.9  405.75  5253.9  406.91  5261.1  408.87  5275.2  409.18
  5282.2  410.14  5296.3  410.88  5303.5  412.00  5349.2  415.76  5392.6  417.67
#Mann=6,-1,0
  4618.9    0.16       0  4853.2   0.033       0  5177.9    0.16       0
  5216.6   0.033       0  5220.6    0.16       0  5349.2    0.07       0
Bank Sta=5216.6,5220.6
Exp/Cntr=0.3,0.1

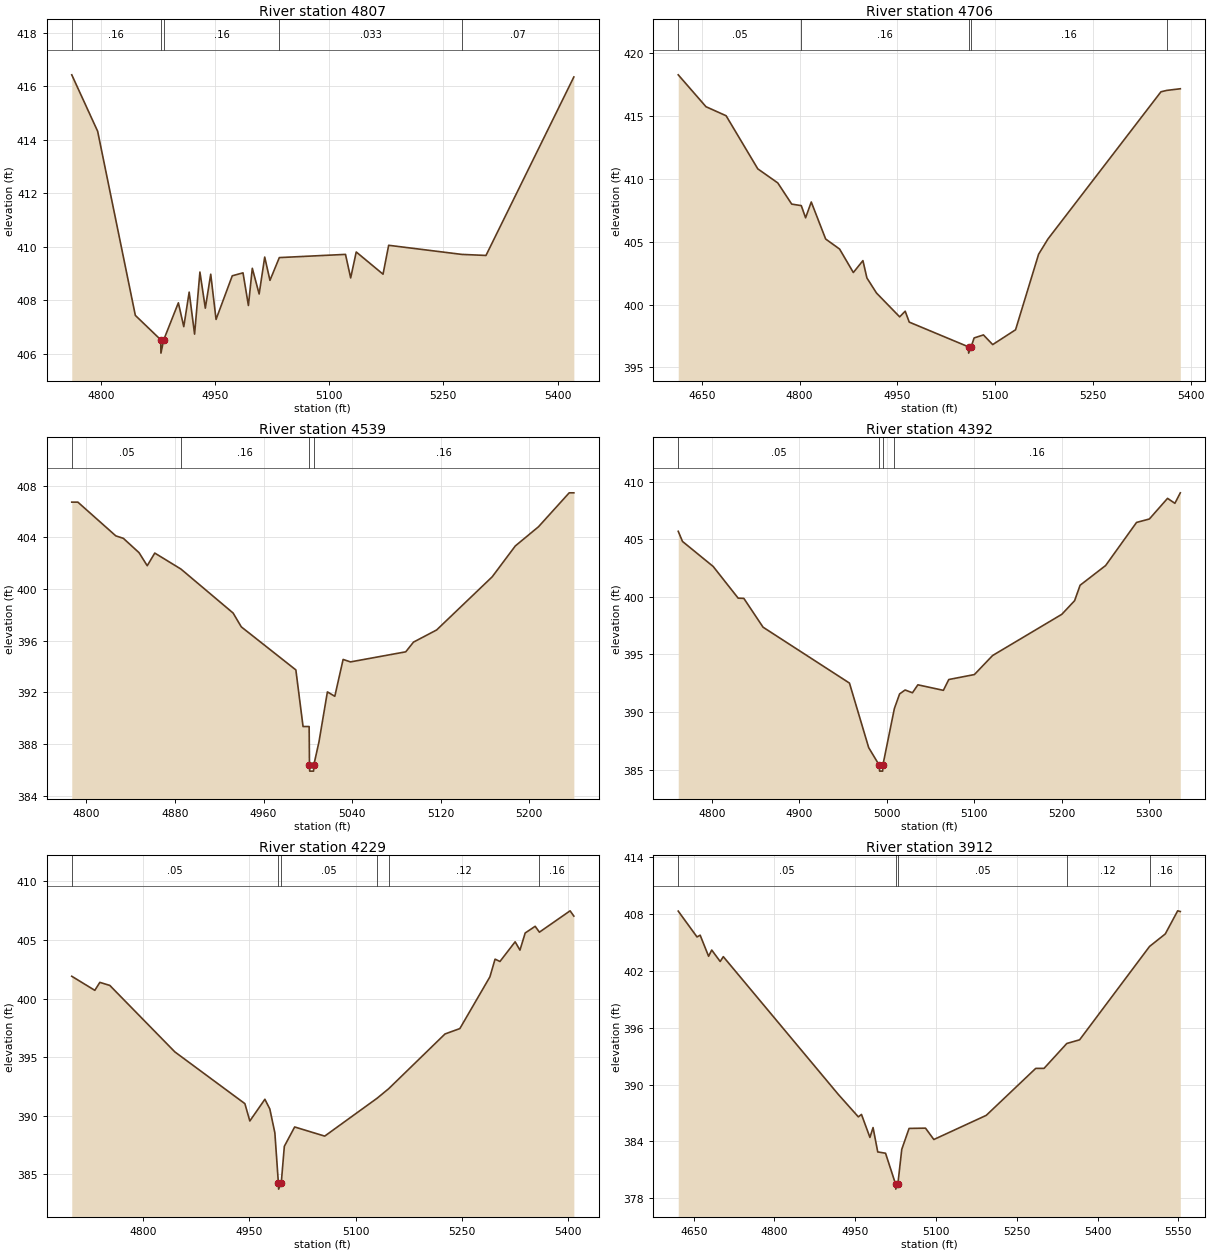
Type RM Length L Ch R = 1,4807,101,101,101
BEGIN DESCRIPTION:
South Twin Creek Trib A4807.47
END DESCRIPTION:
XS GIS Cut Line= 4
      2735224.28      6818900.76      2735053.75      6818730.05
      2734924.74      6818590.62      2734779.09      6818415.02
#Sta/Elev= 30
  4762.0  416.42  4796.0  414.31  4845.5  407.43  4878.8  406.52  4879.1  406.02
  4882.8  406.52  4902.0  407.90  4909.1  407.01  4916.2  408.30  4923.3  406.73
  4930.3  409.05  4937.4  407.70  4944.5  408.97  4951.5  407.28  4972.8  408.91
  4986.9  409.02  4994.0  407.80  4999.1  409.19  5008.1  408.23  5015.4  409.61
  5022.3  408.74  5034.6  409.59  5121.5  409.71  5128.3  408.83  5135.6  409.80
  5170.8  408.97  5178.2  410.05  5274.0  409.71  5306.0  409.67  5421.4  416.34
#Mann=5,-1,0
  4762.0    0.16       0  4878.8    0.07       0  4882.8    0.16       0
  5034.6   0.033       0  5274.0    0.07       0
Bank Sta=4878.8,4882.8
Exp/Cntr=0.3,0.1

Type RM Length L Ch R = 1,4706,167,167,167
BEGIN DESCRIPTION:
South Twin Creek Trib A4705.97
END DESCRIPTION:
XS GIS Cut Line= 5
      2735400.17      6818846.49      2735175.53      6818709.12
      2735070.74      6818633.04      2734977.70      6818526.93
      2734844.53      6818331.16
#Sta/Elev= 30
  4613.6  418.30  4656.2  415.76  4687.1  415.04  4735.7  410.81  4766.4  409.69
  4787.8  408.00  4802.5  407.88  4809.1  406.91  4817.8  408.17  4839.9  405.22
  4861.3  404.42  4882.4  402.55  4897.1  403.50  4903.2  402.12  4917.9  400.92
  4953.5  399.02  4962.0  399.47  4968.2  398.60  5059.2  396.63  5059.4  396.13
  5063.2  396.63  5067.8  397.34  5082.1  397.58  5096.3  396.81  5131.4  397.99
  5166.8  404.01  5181.1  405.22  5354.6  416.95  5363.7  417.06  5384.3  417.19
#Mann=5,-1,0
  4613.6    0.05       0  4802.5    0.16       0  5059.2    0.07       0
  5063.2    0.16       0  5363.7    0.07       0
Bank Sta=5059.2,5063.2
Exp/Cntr=0.3,0.1

Type RM Length L Ch R = 1,4539,147,147,147
BEGIN DESCRIPTION:
Mapping XS 51823a6d
END DESCRIPTION:
XS GIS Cut Line= 3
      2735319.07      6818714.08      2735173.59      6818556.52
      2735015.41      6818377.03
#Sta/Elev= 30
  4786.7  406.72  4792.2  406.72  4826.5  404.11  4833.3  403.92  4847.5  402.81
  4854.9  401.80  4861.7  402.78  4885.4  401.54  4932.5  398.14  4939.9  397.07
  4989.2  393.74  4995.7  389.36  5001.2  389.36  5001.5  386.41  5001.7  385.91
  5005.2  385.91  5005.5  386.41  5010.1  388.18  5017.7  392.04  5024.4  391.70
  5031.9  394.55  5038.6  394.36  5088.5  395.14  5095.5  395.89  5116.4  396.83
  5166.6  400.94  5187.5  403.33  5208.4  404.81  5236.2  407.44  5240.4  407.44
#Mann=4,-1,0
  4786.7    0.05       0  4885.4    0.16       0  5001.5    0.07       0
  5005.5    0.16       0
Bank Sta=5001.5,5005.5
Exp/Cntr=0.3,0.1

Type RM Length L Ch R = 1,4392,163,163,163
BEGIN DESCRIPTION:
Mapping XS c5187cd0
END DESCRIPTION:
XS GIS Cut Line= 3
      2735435.56      6818638.06      2735281.07      6818456.02
      2735080.78      6818186.31
#Sta/Elev= 30
  4761.2  405.68  4766.1  404.80  4801.2  402.63  4829.8  399.88  4836.3  399.86
  4858.3  397.36  4957.2  392.51  4979.2  386.91  4991.4  385.37  4991.7  384.87
  4995.2  384.87  4995.4  385.37  5008.6  390.30  5014.6  391.57  5020.9  391.91
  5029.3  391.67  5035.5  392.36  5064.7  391.88  5070.9  392.82  5100.2  393.25
  5121.0  394.90  5200.3  398.48  5214.9  399.66  5221.2  401.00  5250.4  402.71
  5285.8  406.45  5300.5  406.75  5321.3  408.54  5329.7  408.11  5335.9  409.02
#Mann=4,-1,0
  4761.2    0.05       0  4991.4    0.05       0  4995.4    0.05       0
  5008.6    0.16       0
Bank Sta=4991.4,4995.4
Exp/Cntr=0.3,0.1

Type RM Length L Ch R = 1,4229,317,317,317
BEGIN DESCRIPTION:
South Twin Creek Trib A4229.43
END DESCRIPTION:
XS GIS Cut Line= 3
      2735607.51      6818555.60      2735392.12      6818337.47
      2735096.50      6818062.91
#Sta/Elev= 30
  4698.7  401.90  4731.3  400.70  4738.4  401.38  4752.5  401.12  4844.5  395.45
  4943.5  391.04  4950.5  389.56  4971.8  391.41  4978.8  390.58  4985.9  388.55
  4990.9  384.25  4991.2  383.75  4994.9  384.25  4999.3  387.40  5013.9  389.05
  5056.4  388.27  5130.7  391.51  5147.0  392.32  5226.5  396.98  5247.5  397.44
  5290.0  401.85  5297.3  403.36  5304.2  403.16  5325.7  404.84  5332.5  404.13
  5339.9  405.59  5354.0  406.16  5360.0  405.66  5403.4  407.48  5408.7  407.03
#Mann=6,-1,0
  4698.7    0.05       0  4990.9    0.05       0  4994.9    0.05       0
  5130.7    0.16       0  5147.0    0.12       0  5360.0    0.16       0
Bank Sta=4990.9,4994.9
Exp/Cntr=0.3,0.1

Type RM Length L Ch R = 1,3912,320,320,320
BEGIN DESCRIPTION:
South Twin Creek Trib A3912.32
END DESCRIPTION:
XS GIS Cut Line= 3
      2735946.30      6818306.39      2735615.71      6818114.16
      2735116.14      6817884.13
#Sta/Elev= 30
  4621.3  408.33  4656.2  405.60  4662.0  405.79  4677.7  403.56  4683.5  404.22
  4699.2  403.01  4705.0  403.52  4918.6  388.97  4955.8  386.60  4961.6  386.86
  4977.3  384.43  4983.1  385.47  4991.8  382.90  5006.3  382.76  5025.1  379.47
  5025.3  378.97  5029.1  379.47  5036.4  383.17  5050.0  385.38  5080.5  385.41
  5096.0  384.21  5193.3  386.76  5285.2  391.72  5300.6  391.72  5342.9  394.35
  5366.7  394.74  5496.6  404.60  5525.8  405.92  5548.8  408.36  5553.7  408.29
#Mann=5,-1,0
  4621.3    0.05       0  5025.1    0.05       0  5029.1    0.05       0
  5342.9    0.12       0  5496.6    0.16       0
Bank Sta=5025.1,5029.1
Exp/Cntr=0.3,0.1

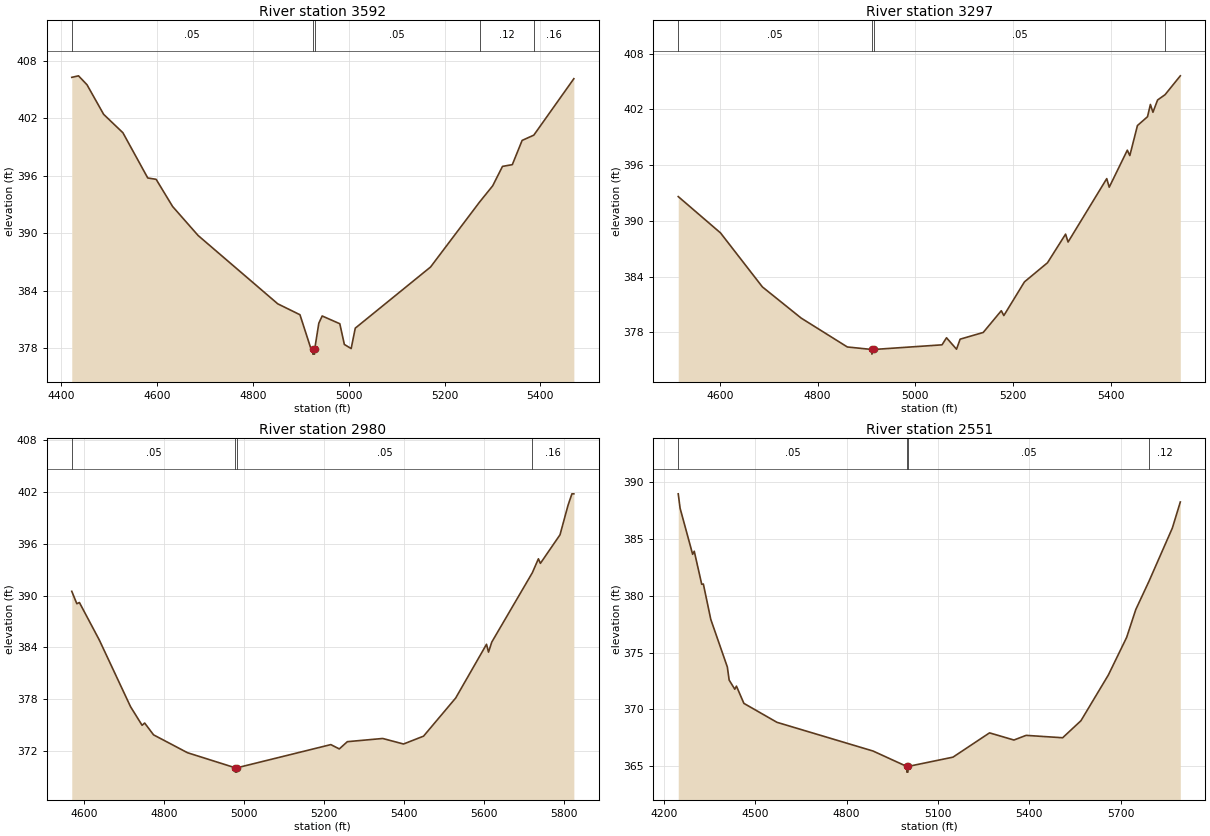
Type RM Length L Ch R = 1,3592,295,295,295
BEGIN DESCRIPTION:
South Twin Creek Trib A3592.15
END DESCRIPTION:
XS GIS Cut Line= 3
      2736106.77      6818050.45      2735574.34      6817811.85
      2735120.62      6817710.27
#Sta/Elev= 30
  4421.6  406.29  4435.7  406.45  4453.4  405.52  4488.2  402.43  4528.4  400.51
  4580.3  395.79  4597.8  395.65  4632.1  392.82  4685.4  389.79  4851.7  382.66
  4898.1  381.52  4921.3  377.93  4924.8  377.91  4925.0  377.41  4928.5  377.41
  4928.8  377.91  4937.5  380.64  4944.5  381.39  4981.3  380.58  4990.8  378.42
  5005.0  377.99  5013.6  380.12  5170.8  386.50  5273.0  393.27  5300.5  394.97
  5321.0  397.00  5341.5  397.18  5362.0  399.71  5386.4  400.26  5470.0  406.15
#Mann=5,-1,0
  4421.6    0.05       0  4924.8    0.05       0  4928.8    0.05       0
  5273.0    0.12       0  5386.4    0.16       0
Bank Sta=4924.8,4928.8
Exp/Cntr=0.3,0.1

Type RM Length L Ch R = 1,3297,317,317,317
BEGIN DESCRIPTION:
South Twin Creek Trib A3296.96
END DESCRIPTION:
XS GIS Cut Line= 3
      2736129.58      6817825.22      2735710.08      6817565.90
      2735190.74      6817441.99
#Sta/Elev= 30
  4514.8  392.61  4601.3  388.70  4687.0  382.89  4766.2  379.54  4860.7  376.43
  4910.8  376.16  4911.0  375.66  4914.8  376.16  5054.5  376.66  5063.6  377.42
  5084.1  376.19  5091.5  377.27  5138.7  377.99  5175.7  380.33  5180.9  379.81
  5223.0  383.43  5270.2  385.49  5307.2  388.57  5312.3  387.72  5391.4  394.54
  5396.5  393.62  5433.5  397.60  5438.6  397.02  5454.2  400.25  5474.8  401.20
  5480.7  402.52  5485.9  401.68  5495.4  403.00  5510.7  403.57  5541.9  405.60
#Mann=4,-1,0
  4514.8    0.05       0  4910.8    0.05       0  4914.8    0.05       0
  5510.7    0.12       0
Bank Sta=4910.8,4914.8
Exp/Cntr=0.3,0.1

Type RM Length L Ch R = 1,2980,429,429,429
BEGIN DESCRIPTION:
South Twin Creek Trib A2980.25
END DESCRIPTION:
XS GIS Cut Line= 3
      2736212.32      6817681.68      2735938.09      6817342.69
      2735121.47      6817279.22
#Sta/Elev= 30
  4568.8  390.49  4581.5  389.05  4587.9  389.19  4637.5  384.86  4715.8  377.11
  4744.6  374.96  4751.0  375.22  4773.3  373.85  4858.1  371.78  4977.6  370.03
  4977.8  369.53  4981.3  369.53  4981.6  370.03  5216.4  372.72  5237.6  372.22
  5257.7  373.06  5346.1  373.43  5398.1  372.79  5448.2  373.70  5528.5  378.12
  5605.6  384.35  5610.6  383.44  5618.8  384.61  5720.1  392.64  5735.3  394.26
  5740.3  393.73  5789.3  397.04  5809.3  400.45  5819.1  401.79  5823.9  401.79
#Mann=4,-1,0
  4568.8    0.05       0  4977.6    0.05       0  4981.6    0.05       0
  5720.1    0.16       0
Bank Sta=4977.6,4981.6
Exp/Cntr=0.3,0.1

Type RM Length L Ch R = 1,2551,0,0,0
BEGIN DESCRIPTION:
South Twin Creek Trib A2551.419
END DESCRIPTION:
XS GIS Cut Line= 3
      2736299.51      6817646.69      2736025.58      6816945.82
      2735129.79      6816965.26
#Sta/Elev= 30
  4247.5  388.99  4253.6  387.72  4294.8  383.66  4300.1  383.93  4324.6  381.02
  4330.0  381.04  4354.4  377.92  4408.8  373.72  4414.7  372.57  4433.2  371.77
  4438.6  372.04  4463.1  370.52  4571.7  368.85  4887.1  366.32  4997.9  364.96
  4998.2  364.46  5001.7  364.46  5001.9  364.96  5149.6  365.78  5269.6  367.92
  5349.7  367.29  5389.7  367.70  5509.7  367.49  5569.7  368.99  5659.7  373.02
  5719.7  376.33  5749.8  378.79  5793.1  381.28  5869.8  385.97  5896.0  388.27
#Mann=4,-1,0
  4247.5    0.05       0  4997.9    0.05       0  5001.9    0.05       0
  5793.1    0.12       0
Bank Sta=4997.9,5001.9
Exp/Cntr=0.3,0.1

Chan Stop Cuts=-1