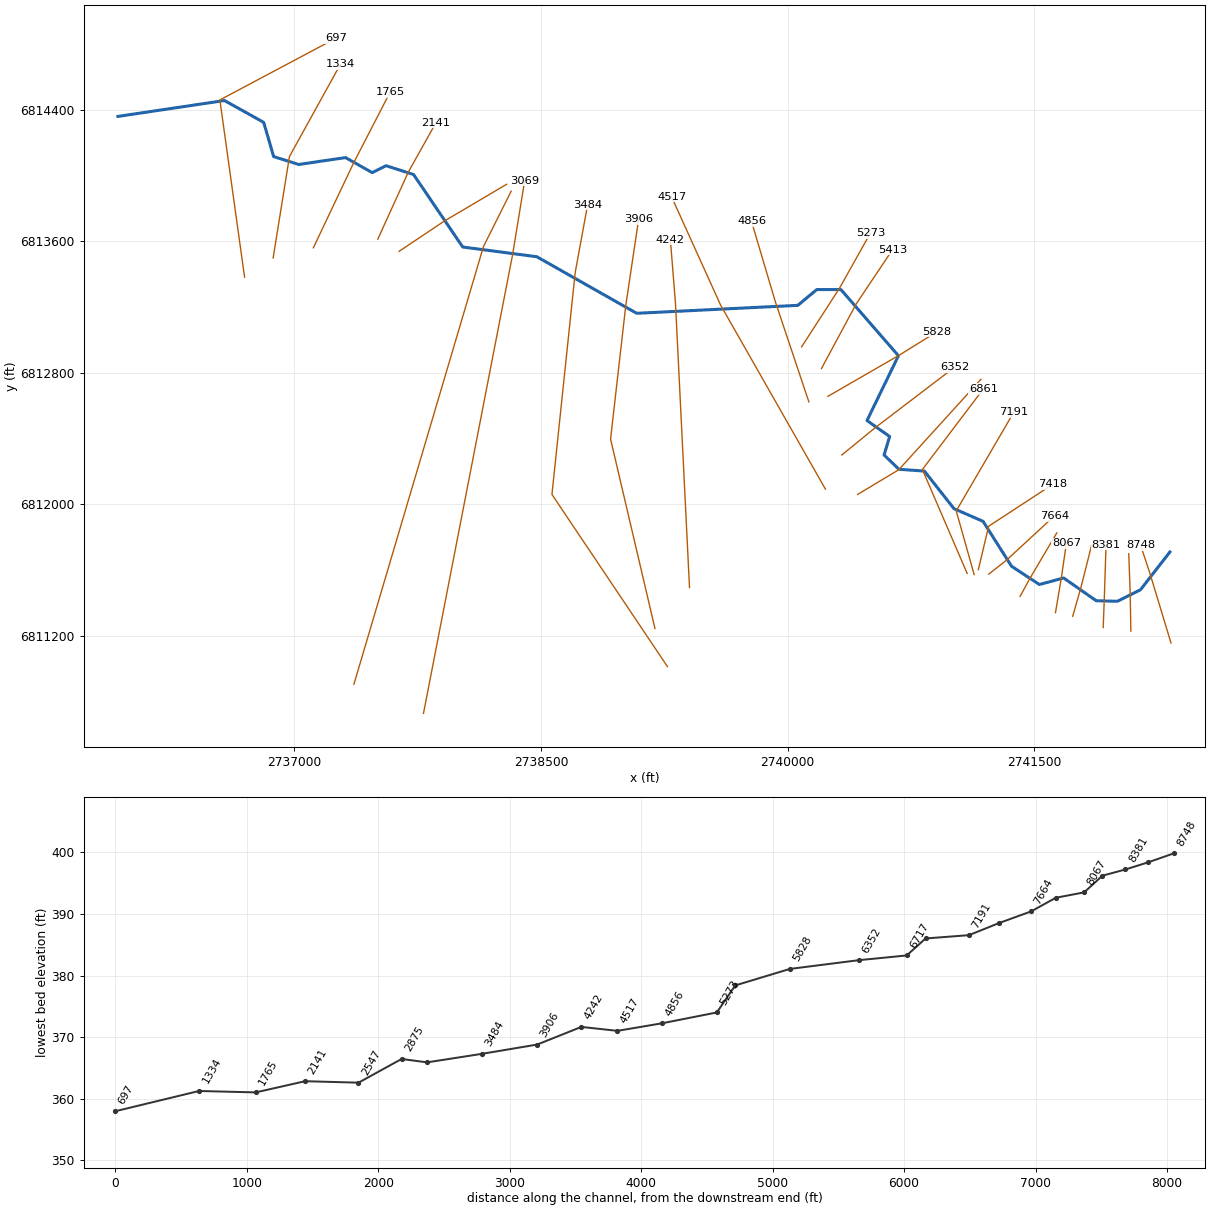
--- South Twin Creek Trib B.prj (project) ---

Proj Title=South Twin Creek Trib B Base Level Engineering
Current Plan=p01
Default Exp/Contr=0.3,0.1
English Units
Geom File=g01
Flow File=f01
Plan File=p01
BEGIN DESCRIPTION:
South Twin Creek Trib B
END DESCRIPTION:

--- South Twin Creek Trib B.p01 (plan) ---

Plan Title=Multiple Run
Short Identifier=Multiple
Geom File=g01
Flow File=f01
Subcritical Flow
K Sum by GR= 0
Std Step Tol= 0.01
Critical Tol= 0.01
Num of Std Step Trials= 20
Max Error Tol= 0.3
Flow Tol Ratio= 0.001
Split Flow NTrial= 30
Split Flow Tol= 0.02
Split Flow Ratio= 0.02
Log Output Level= 0
Friction Slope Method= 1
Unsteady Friction Slope Method= 2
Unsteady Bridges Friction Slope Method= 1
Parabolic Critical Depth
Global Vel Dist=  1 , 1 , 1
Global Log Level= 0
CheckData=True
Encroach Param= -1, 0, 0, 0
BEGIN DESCRIPTION:
Multiple Run
END DESCRIPTION:

--- South Twin Creek Trib B.f01 (steady flow) ---

Flow Title=Multiple
Number of Profiles=7
Profile Names=10-year,25-year,50-year,1pct_min,100-year,1pct_plu,500-year
River Rch & RM= South Twin Creek,Reach-1,8748
     339     442     523     308     615    1227     852
River Rch & RM= South Twin Creek,Reach-1,6717
     582     784     948     570    1137    2268    1640
River Rch & RM= South Twin Creek,Reach-1,2547
    1071    1481    1822    1110    2215    4419    3273
Boundary for River Rch & Prof#=South Twin Creek,Reach-1,1
Up Type=0
Dn Type=3
Dn Slope=0.005
Boundary for River Rch & Prof#=South Twin Creek,Reach-1,2
Up Type=0
Dn Type=3
Dn Slope=0.005
Boundary for River Rch & Prof#=South Twin Creek,Reach-1,3
Up Type=0
Dn Type=3
Dn Slope=0.005
Boundary for River Rch & Prof#=South Twin Creek,Reach-1,4
Up Type=0
Dn Type=3
Dn Slope=0.005
Boundary for River Rch & Prof#=South Twin Creek,Reach-1,5
Up Type=0
Dn Type=3
Dn Slope=0.005
Boundary for River Rch & Prof#=South Twin Creek,Reach-1,6
Up Type=0
Dn Type=3
Dn Slope=0.005
Boundary for River Rch & Prof#=South Twin Creek,Reach-1,7
Up Type=0
Dn Type=3
Dn Slope=0.005

--- South Twin Creek Trib B.g01 (geometry) ---

Geom Title=Existing Conditions

River Reach=South Twin Creek,Reach-1
Reach XY= 30
      2742326.00      6811711.00      2742146.47      6811480.62
      2742005.97      6811411.04      2741877.47      6811414.54
      2741679.32      6811552.96      2741531.90      6811512.98
      2741362.37      6811624.46      2741189.22      6811897.38
      2741012.43      6811974.47      2740832.22      6812203.26
      2740677.32      6812214.27      2740587.08      6812300.93
      2740620.98      6812413.54      2740483.20      6812510.70
      2740674.38      6812904.96      2740324.53      6813307.47
      2740177.47      6813307.46      2740062.14      6813211.54
      2739081.97      6813163.17      2738474.45      6813507.25
      2738023.52      6813566.40      2737724.51      6814007.39
      2737557.54      6814061.11      2737472.69      6814019.07
      2737310.79      6814110.49      2737026.00      6814068.56
      2736873.29      6814116.40      2736812.77      6814324.67
      2736574.26      6814457.63      2735926.00      6814361.00

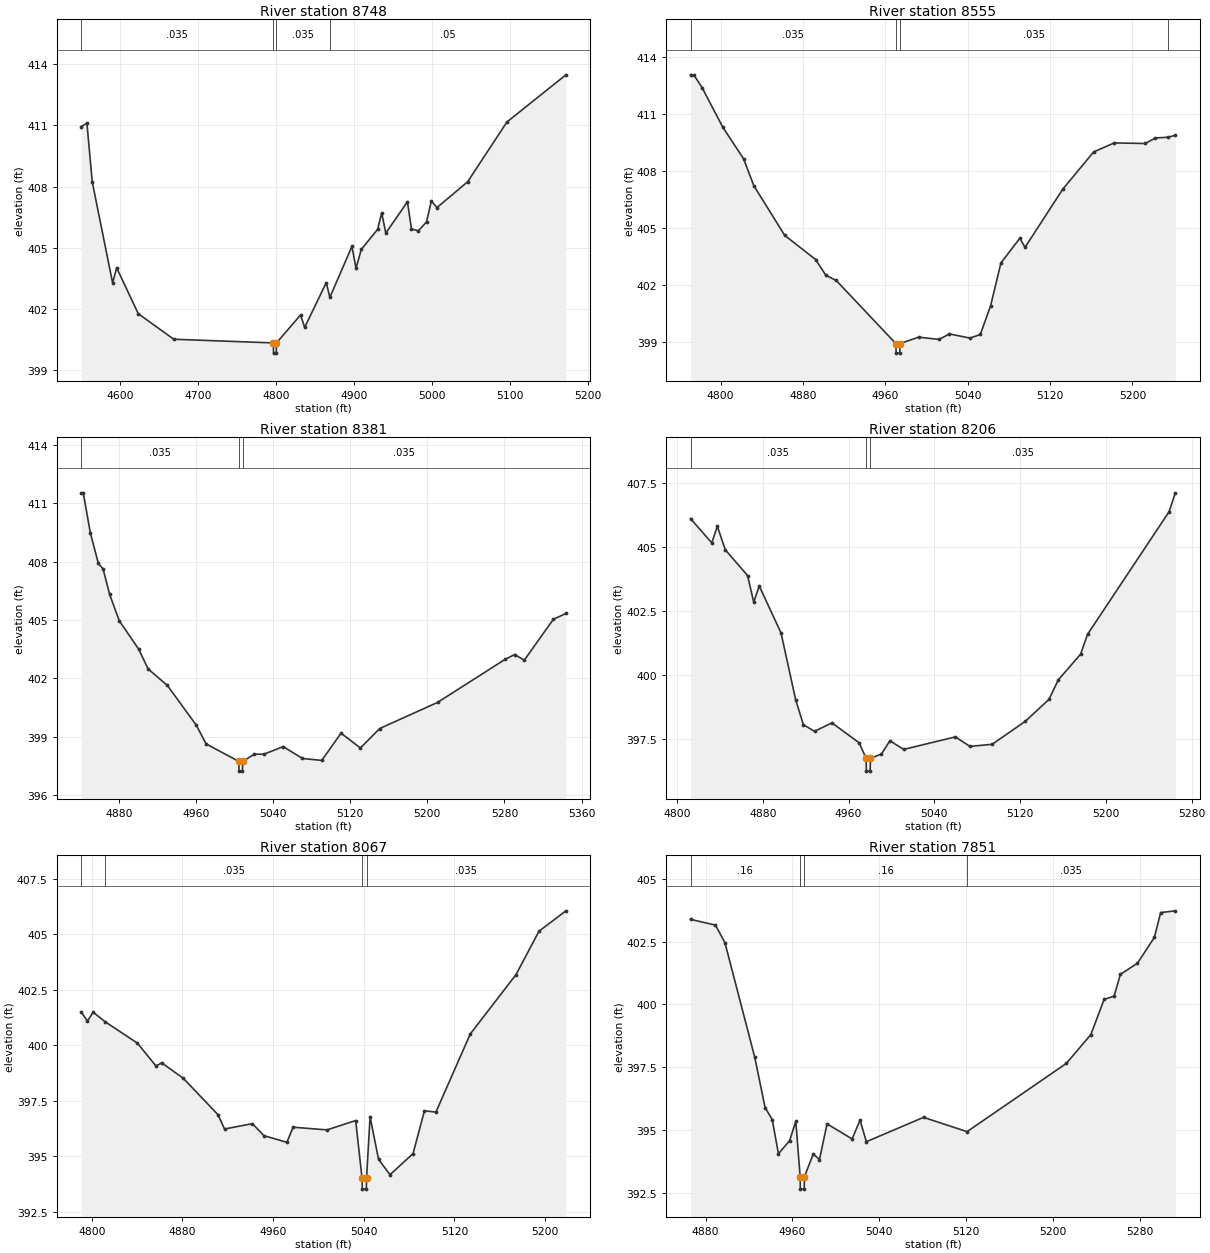
Type RM Length L Ch R = 1,8748,193,193,193
BEGIN DESCRIPTION:
South Twin Creek Trib B8747.747
END DESCRIPTION:
XS GIS Cut Line= 3
      2742332.69      6811157.44      2742202.29      6811587.82
      2742147.98      6811750.49
#Sta/Elev= 30
  4550.3  410.94  4557.7  411.11  4564.5  408.24  4590.6  403.29  4595.8  404.03
  4623.5  401.78  4669.0  400.53  4796.6  400.35  4796.8  399.85  4800.3  399.85
  4800.6  400.35  4831.5  401.72  4836.7  401.11  4864.4  403.30  4869.0  402.58
  4897.3  405.08  4902.5  404.01  4909.3  404.93  4930.2  405.91  4935.4  406.72
  4940.7  405.73  4968.4  407.26  4973.6  405.93  4982.4  405.84  4992.9  406.28
  4999.0  407.30  5006.3  406.98  5045.5  408.24  5095.9  411.17  5171.5  413.48
#Mann=4,-1,0
  4550.3   0.035       0  4796.6    0.05       0  4800.6   0.035       0
  4869.0    0.05       0
Bank Sta=4796.6,4800.6
Exp/Cntr=0.3,0.1

Type RM Length L Ch R = 1,8555,174,174,174
BEGIN DESCRIPTION:
South Twin Creek Trib B8554.56
END DESCRIPTION:
XS GIS Cut Line= 3
      2742088.35      6811229.56      2742084.25      6811463.25
      2742075.65      6811700.27
#Sta/Elev= 30
  4770.8  413.04  4774.0  413.04  4782.2  412.35  4802.2  410.28  4822.3  408.63
  4832.3  407.21  4862.3  404.60  4892.3  403.33  4902.3  402.50  4912.3  402.23
  4970.3  398.91  4970.5  398.41  4974.0  398.41  4974.3  398.91  4992.3  399.25
  5012.3  399.13  5022.3  399.42  5042.3  399.20  5052.3  399.39  5062.3  400.90
  5072.3  403.15  5090.7  404.45  5095.7  403.97  5132.4  407.03  5162.4  408.99
  5182.4  409.46  5212.4  409.43  5222.4  409.72  5234.6  409.76  5241.7  409.86
#Mann=4,-1,0
  4770.8   0.035       0  4970.3   0.035       0  4974.3   0.035       0
  5234.6    0.05       0
Bank Sta=4970.3,4974.3
Exp/Cntr=0.3,0.1

Type RM Length L Ch R = 1,8381,175,175,175
BEGIN DESCRIPTION:
South Twin Creek Trib B8380.8
END DESCRIPTION:
XS GIS Cut Line= 3
      2741920.20      6811251.53      2741926.52      6811417.93
      2741937.62      6811754.13
#Sta/Elev= 30
  4840.9  411.54  4843.1  411.54  4850.4  409.49  4858.7  407.92  4863.7  407.62
  4870.4  406.33  4880.4  404.97  4900.4  403.52  4910.4  402.49  4930.4  401.64
  4960.5  399.59  4970.5  398.64  5004.5  397.74  5004.7  397.24  5008.2  397.24
  5008.5  397.74  5020.5  398.11  5030.5  398.11  5050.5  398.50  5070.5  397.89
  5090.5  397.79  5110.5  399.19  5130.6  398.43  5150.6  399.43  5210.6  400.77
  5280.6  402.98  5290.6  403.23  5300.6  402.94  5330.7  405.04  5343.8  405.34
#Mann=3,-1,0
  4840.9   0.035       0  5004.5   0.035       0  5008.5   0.035       0
Bank Sta=5004.5,5008.5
Exp/Cntr=0.3,0.1

Type RM Length L Ch R = 1,8206,139,139,139
BEGIN DESCRIPTION:
South Twin Creek Trib B8206.03
END DESCRIPTION:
XS GIS Cut Line= 3
      2741734.76      6811319.82      2741786.32      6811501.17
      2741850.63      6811756.66
#Sta/Elev= 30
  4812.7  406.12  4832.5  405.17  4837.7  405.82  4845.1  404.90  4865.9  403.89
  4871.6  402.85  4876.8  403.48  4897.1  401.64  4910.7  399.03  4917.9  398.05
  4928.3  397.79  4944.6  398.12  4969.9  397.34  4976.4  396.73  4976.7  396.23
  4980.2  396.23  4980.4  396.73  4990.7  396.90  4998.6  397.42  5011.4  397.08
  5059.6  397.57  5073.2  397.20  5093.9  397.28  5124.8  398.18  5146.9  399.04
  5155.7  399.81  5176.4  400.81  5182.9  401.59  5258.9  406.39  5264.7  407.13
#Mann=3,-1,0
  4812.7   0.035       0  4976.4   0.035       0  4980.4   0.035       0
Bank Sta=4976.4,4980.4
Exp/Cntr=0.3,0.1

Type RM Length L Ch R = 1,8067,216,216,216
BEGIN DESCRIPTION:
South Twin Creek Trib B8067.21
END DESCRIPTION:
XS GIS Cut Line= 3
      2741629.83      6811342.05      2741665.91      6811555.97
      2741696.23      6811764.54
#Sta/Elev= 30
  4790.7  401.51  4796.2  401.09  4801.3  401.49  4811.9  401.06  4840.3  400.10
  4856.7  399.07  4861.8  399.21  4880.9  398.51  4911.3  396.88  4917.2  396.23
  4941.8  396.47  4951.9  395.93  4972.2  395.63  4977.7  396.31  5007.6  396.19
  5032.9  396.61  5038.5  394.02  5038.8  393.52  5042.3  393.52  5042.5  394.02
  5045.6  396.78  5053.1  394.86  5063.2  394.17  5083.5  395.12  5093.6  397.05
  5103.7  396.99  5134.0  400.51  5174.4  403.19  5194.6  405.14  5218.4  406.06
#Mann=4,-1,0
  4790.7    0.16       0  4811.9   0.035       0  5038.5   0.035       0
  5042.5   0.035       0
Bank Sta=5038.5,5042.5
Exp/Cntr=0.3,0.1

Type RM Length L Ch R = 1,7851,187,187,187
BEGIN DESCRIPTION:
South Twin Creek Trib B7851.18
END DESCRIPTION:
XS GIS Cut Line= 3
      2741414.25      6811440.84      2741479.11      6811558.45
      2741637.93      6811827.46
#Sta/Elev= 30
  4866.2  403.39  4889.2  403.16  4897.9  402.46  4925.4  397.89  4934.9  395.89
  4941.5  395.41  4947.2  394.05  4957.5  394.57  4963.2  395.34  4967.2  393.14
  4967.4  392.64  4970.9  392.64  4971.2  393.14  4979.3  394.04  4985.0  393.82
  4992.0  395.24  5015.1  394.64  5022.4  395.39  5028.2  394.53  5080.9  395.50
  5121.0  394.93  5212.5  397.65  5235.1  398.80  5247.3  400.20  5256.5  400.33
  5262.3  401.20  5278.0  401.64  5293.6  402.67  5299.4  403.66  5312.9  403.73
#Mann=4,-1,0
  4866.2    0.16       0  4967.2    0.07       0  4971.2    0.16       0
  5121.0   0.035       0
Bank Sta=4967.2,4971.2
Exp/Cntr=0.3,0.1

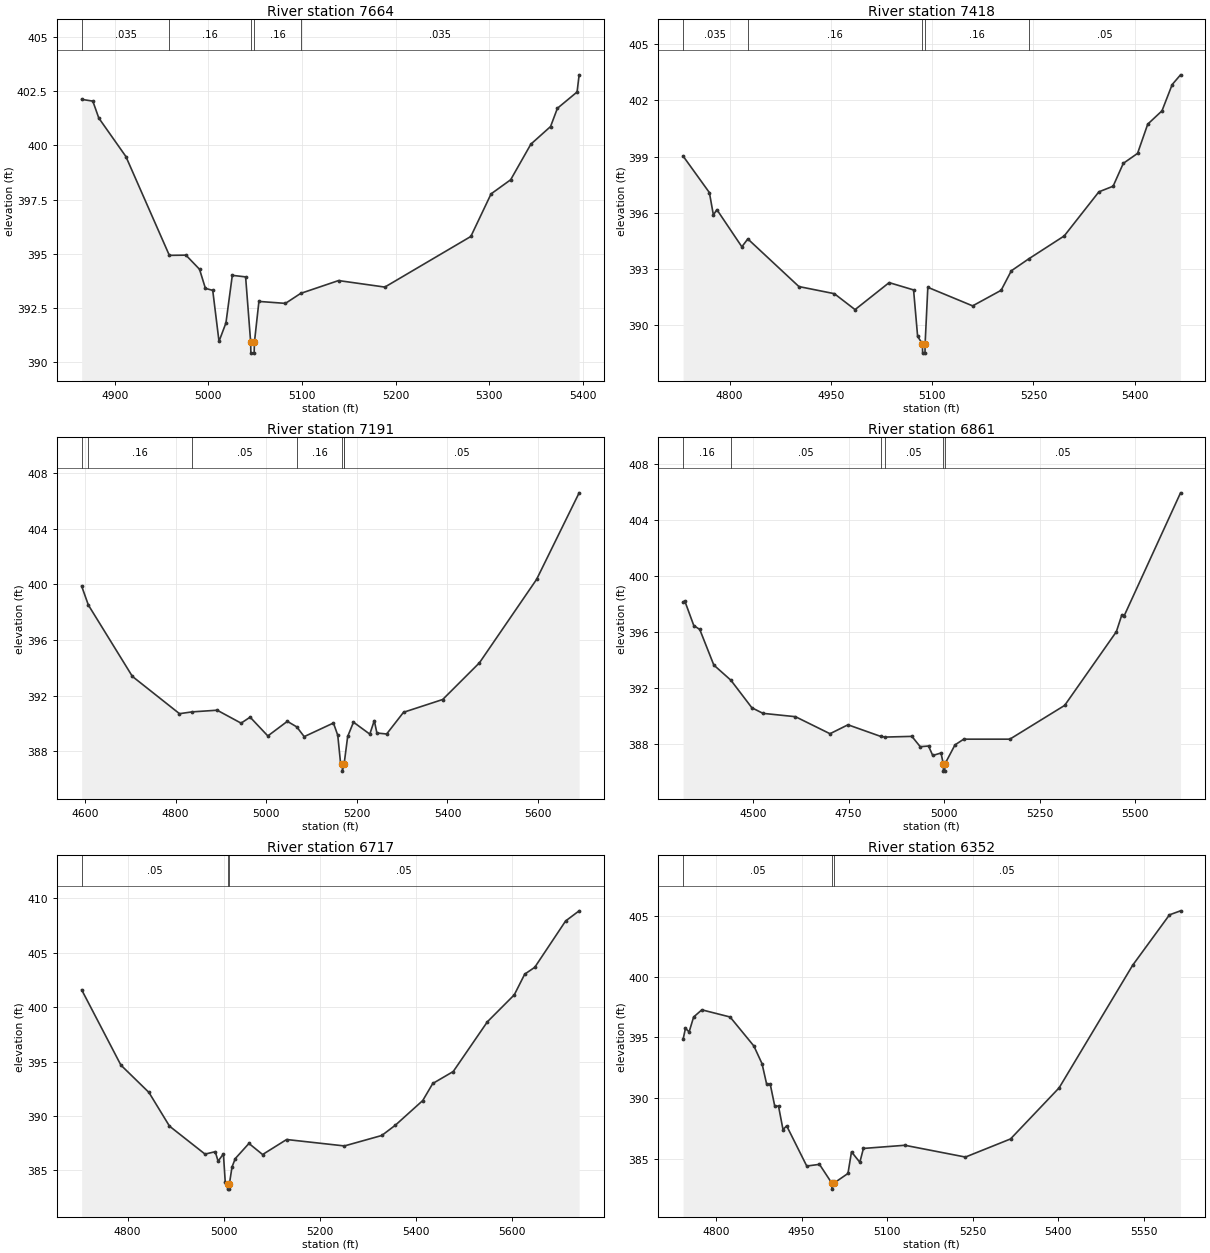
Type RM Length L Ch R = 1,7664,246,246,246
BEGIN DESCRIPTION:
South Twin Creek Trib B7663.79
END DESCRIPTION:
XS GIS Cut Line= 3
      2741224.25      6811576.59      2741331.10      6811660.56
      2741621.35      6811928.64
#Sta/Elev= 30
  4864.8  402.11  4876.7  402.03  4883.1  401.25  4912.0  399.48  4958.4  394.93
  4976.1  394.94  4990.6  394.29  4996.9  393.41  5004.7  393.32  5011.4  390.97
  5018.8  391.82  5025.6  394.01  5039.8  393.94  5045.2  390.93  5045.4  390.43
  5048.9  390.43  5049.2  390.93  5054.0  392.81  5082.3  392.72  5098.6  393.18
  5139.0  393.77  5188.4  393.47  5280.2  395.80  5301.8  397.76  5322.7  398.41
  5344.3  400.05  5365.3  400.86  5372.6  401.70  5393.6  402.45  5395.8  403.24
#Mann=5,-1,0
  4864.8   0.035       0  4958.4    0.16       0  5045.2    0.07       0
  5049.2    0.16       0  5098.6   0.035       0
Bank Sta=5045.2,5049.2
Exp/Cntr=0.3,0.1

Type RM Length L Ch R = 1,7418,227,227,227
BEGIN DESCRIPTION:
South Twin Creek Trib B7417.88
END DESCRIPTION:
XS GIS Cut Line= 3
      2741160.44      6811603.07      2741223.24      6811867.77
      2741612.56      6812121.96
#Sta/Elev= 30
  4731.0  399.03  4770.0  397.08  4775.9  395.89  4781.1  396.17  4818.1  394.19
  4826.9  394.61  4902.6  392.07  4955.1  391.69  4985.8  390.84  5036.3  392.28
  5072.5  391.89  5078.5  389.41  5085.6  389.02  5085.9  388.52  5089.4  388.52
  5089.6  389.02  5093.6  392.03  5160.0  391.04  5202.2  391.87  5217.3  392.91
  5242.8  393.54  5295.7  394.77  5347.0  397.12  5368.1  397.42  5383.2  398.64
  5404.3  399.17  5419.4  400.73  5440.5  401.44  5455.6  402.84  5468.0  403.36
#Mann=5,-1,0
  4731.0   0.035       0  4826.9    0.16       0  5085.6    0.07       0
  5089.6    0.16       0  5242.8    0.05       0
Bank Sta=5085.6,5089.6
Exp/Cntr=0.3,0.1

Type RM Length L Ch R = 1,7191,330,330,330
BEGIN DESCRIPTION:
South Twin Creek Trib B7190.889
END DESCRIPTION:
XS GIS Cut Line= 3
      2741135.08      6811573.26      2741026.00      6811961.00
      2741375.99      6812560.99
#Sta/Elev= 30
  4593.0  399.87  4607.8  398.51  4704.9  393.38  4808.8  390.70  4836.6  390.83
  4891.9  390.95  4944.7  390.02  4964.6  390.45  5003.7  389.10  5046.7  390.15
  5067.5  389.75  5083.9  389.05  5148.4  390.03  5157.9  389.15  5164.1  387.16
  5167.9  387.07  5168.1  386.57  5171.9  387.07  5172.5  387.22  5179.8  389.06
  5192.6  390.09  5228.6  389.23  5238.5  390.20  5244.3  389.31  5265.8  389.24
  5303.0  390.80  5389.4  391.72  5470.5  394.36  5596.6  400.36  5690.4  406.58
#Mann=7,-1,0
  4593.0   0.035       0  4607.8    0.16       0  4836.6    0.05       0
  5067.5    0.16       0  5167.9    0.05       0  5171.9    0.16       0
  5172.5    0.05       0
Bank Sta=5167.9,5171.9
Exp/Cntr=0.3,0.1

Type RM Length L Ch R = 1,6861,144,144,144
BEGIN DESCRIPTION:
South Twin Creek Trib B6861.36
END DESCRIPTION:
XS GIS Cut Line= 3
      2741092.37      6811580.85      2740820.00      6812212.96
      2741190.64      6812702.36
#Sta/Elev= 30
  4316.5  398.12  4321.0  398.22  4344.6  396.46  4360.2  396.18  4397.0  393.63
  4441.8  392.54  4496.6  390.57  4525.6  390.17  4610.7  389.93  4701.1  388.71
  4748.2  389.35  4833.6  388.52  4845.4  388.47  4915.5  388.52  4937.3  387.78
  4959.1  387.83  4970.0  387.15  4991.8  387.33  4997.7  386.53  4998.0  386.03
  5001.5  386.03  5001.7  386.53  5028.3  387.91  5051.2  388.32  5171.9  388.32
  5315.4  390.74  5450.7  396.02  5465.2  397.24  5471.5  397.18  5618.7  405.97
#Mann=6,-1,0
  4316.5    0.16       0  4441.8    0.05       0  4833.6    0.16       0
  4845.4    0.05       0  4997.7    0.05       0  5001.7    0.05       0
Bank Sta=4997.7,5001.7
Exp/Cntr=0.3,0.1

Type RM Length L Ch R = 1,6717,365,365,365
BEGIN DESCRIPTION:
South Twin Creek Trib B6717.409
END DESCRIPTION:
XS GIS Cut Line= 3
      2740426.00      6812061.00      2740676.00      6812211.00
      2741176.03      6812761.03
#Sta/Elev= 30
  4704.6  401.59  4786.2  394.67  4844.5  392.16  4887.3  389.06  4961.2  386.49
  4982.5  386.71  4988.4  385.84  4999.5  386.51  5003.2  383.96  5008.0  383.77
  5008.3  383.27  5011.8  383.27  5012.0  383.77  5017.4  385.31  5024.2  386.08
  5052.6  387.47  5081.0  386.45  5131.0  387.83  5251.2  387.24  5328.9  388.20
  5357.3  389.15  5414.1  391.41  5435.0  392.98  5477.6  394.08  5548.6  398.65
  5604.6  401.13  5626.3  403.03  5647.2  403.66  5711.4  407.92  5739.5  408.85
#Mann=3,-1,0
  4704.6    0.05       0  5008.0    0.05       0  5012.0    0.05       0
Bank Sta=5008,5012
Exp/Cntr=0.3,0.1

Type RM Length L Ch R = 1,6352,524,524,524
BEGIN DESCRIPTION:
South Twin Creek Trib B6351.95
END DESCRIPTION:
XS GIS Cut Line= 3
      2740330.13      6812301.43      2740533.51      6812467.33
      2741017.87      6812836.71
#Sta/Elev= 30
  4742.5  394.82  4746.7  395.74  4753.1  395.44  4761.0  396.67  4775.4  397.26
  4824.9  396.67  4866.6  394.28  4880.9  392.82  4888.8  391.17  4895.3  391.12
  4903.2  389.32  4909.7  389.34  4917.6  387.40  4924.0  387.71  4959.2  384.40
  4981.5  384.54  5003.0  383.00  5003.2  382.50  5007.0  383.00  5031.4  383.79
  5037.6  385.57  5052.2  384.71  5058.5  385.85  5131.1  386.11  5237.2  385.14
  5316.2  386.63  5401.4  390.84  5530.2  400.93  5594.7  405.08  5614.1  405.41
#Mann=3,-1,0
  4742.5    0.05       0  5003.0    0.05       0  5007.0    0.05       0
Bank Sta=5003,5007
Exp/Cntr=0.3,0.1

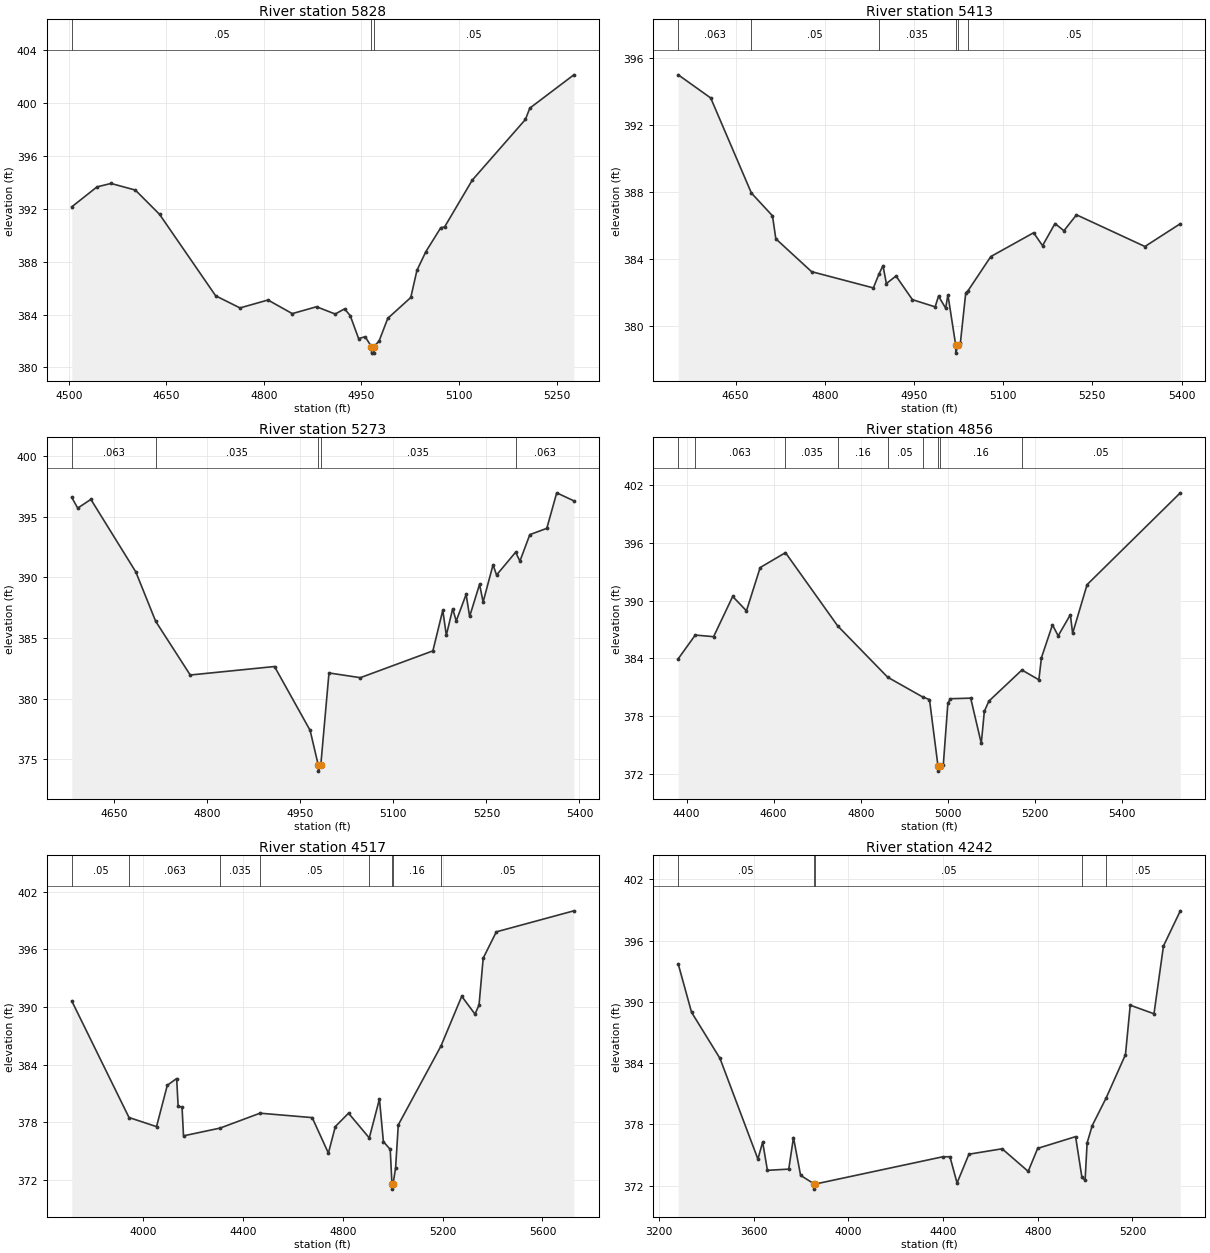
Type RM Length L Ch R = 1,5828,415,415,415
BEGIN DESCRIPTION:
South Twin Creek Trib B5828.17
END DESCRIPTION:
XS GIS Cut Line= 3
      2740245.19      6812657.89      2740677.42      6812907.17
      2740909.24      6813051.23
#Sta/Elev= 30
  4504.7  392.15  4543.5  393.66  4565.0  393.92  4602.4  393.42  4639.7  391.58
  4725.9  385.42  4763.3  384.50  4806.4  385.10  4843.7  384.07  4881.0  384.59
  4909.7  384.04  4924.1  384.43  4932.8  383.92  4945.7  382.18  4955.7  382.32
  4965.4  381.58  4965.6  381.08  4969.1  381.08  4969.4  381.58  4977.2  382.00
  4990.5  383.71  5025.9  385.29  5035.4  387.35  5049.1  388.76  5072.0  390.57
  5077.9  390.63  5120.4  394.17  5202.1  398.76  5208.9  399.62  5276.6  402.14
#Mann=3,-1,0
  4504.7    0.05       0  4965.4    0.05       0  4969.4    0.05       0
Bank Sta=4965.4,4969.4
Exp/Cntr=0.3,0.1

Type RM Length L Ch R = 1,5413,140,140,140
BEGIN DESCRIPTION:
South Twin Creek Trib B5413.38
END DESCRIPTION:
XS GIS Cut Line= 3
      2740205.87      6812826.64      2740417.09      6813219.62
      2740638.59      6813550.48
#Sta/Elev= 30
  4553.6  395.00  4608.2  393.62  4676.6  387.95  4712.1  386.59  4717.7  385.22
  4777.8  383.26  4881.7  382.29  4891.2  383.12  4897.9  383.62  4903.6  382.55
  4919.8  383.00  4947.4  381.59  4985.6  381.16  4991.3  381.80  5003.3  381.08
  5007.1  381.88  5020.1  378.90  5020.4  378.40  5024.1  378.90  5028.1  379.02
  5037.1  382.00  5040.7  382.11  5079.2  384.16  5151.2  385.58  5166.2  384.81
  5187.2  386.13  5202.2  385.70  5223.3  386.65  5338.4  384.76  5397.9  386.12
#Mann=6,-1,0
  4553.6   0.063       0  4676.6    0.05       0  4891.2   0.035       0
  5020.1   0.035       0  5024.1   0.035       0  5040.7    0.05       0
Bank Sta=5020.1,5024.1
Exp/Cntr=0.3,0.1

Type RM Length L Ch R = 1,5273,417,417,417
BEGIN DESCRIPTION:
South Twin Creek Trib B5272.94
END DESCRIPTION:
XS GIS Cut Line= 3
      2740085.12      6812958.90      2740314.86      6813314.17
      2740503.88      6813651.21
#Sta/Elev= 30
  4581.4  396.59  4591.0  395.71  4612.2  396.43  4684.7  390.44  4716.7  386.37
  4772.4  381.94  4908.3  382.64  4965.7  377.37  4978.8  374.51  4979.1  374.01
  4982.9  374.51  4996.1  382.11  5046.7  381.72  5163.6  383.93  5179.6  387.28
  5185.3  385.22  5195.5  387.40  5201.3  386.40  5217.2  388.59  5222.9  386.77
  5238.9  389.43  5244.6  387.96  5260.6  391.03  5266.3  390.19  5297.0  392.07
  5304.0  391.34  5319.9  393.52  5347.3  394.04  5363.3  396.97  5390.9  396.31
#Mann=5,-1,0
  4581.4   0.063       0  4716.7   0.035       0  4978.8   0.035       0
  4982.9   0.035       0  5297.0   0.063       0
Bank Sta=4978.8,4982.9
Exp/Cntr=0.3,0.1

Type RM Length L Ch R = 1,4856,339,339,339
BEGIN DESCRIPTION:
South Twin Creek Trib B4856.16
END DESCRIPTION:
XS GIS Cut Line= 3
      2740129.56      6812624.04      2739926.96      6813228.86
      2739780.45      6813722.32
#Sta/Elev= 30
  4381.0  383.95  4420.1  386.42  4462.2  386.25  4506.0  390.44  4537.6  388.94
  4569.1  393.45  4627.2  395.00  4747.1  387.37  4861.8  382.03  4942.3  379.97
  4957.8  379.70  4977.4  372.75  4977.6  372.25  4981.5  372.75  4989.5  372.90
  5000.0  379.32  5005.7  379.79  5052.4  379.85  5076.7  375.14  5083.7  378.47
  5094.1  379.54  5170.0  382.78  5208.9  381.76  5214.8  384.06  5240.1  387.48
  5253.2  386.34  5281.2  388.54  5286.4  386.60  5319.6  391.67  5533.6  401.23
#Mann=9,-1,0
  4381.0    0.05       0  4420.1   0.063       0  4627.2   0.035       0
  4747.1    0.16       0  4861.8    0.05       0  4942.3    0.16       0
  4977.4    0.07       0  4981.5    0.16       0  5170.0    0.05       0
Bank Sta=4977.4,4981.5
Exp/Cntr=0.3,0.1

Type RM Length L Ch R = 1,4517,275,275,275
BEGIN DESCRIPTION:
South Twin Creek Trib B4516.98
END DESCRIPTION:
XS GIS Cut Line= 3
      2740230.41      6812093.07      2739592.07      6813213.97
      2739294.12      6813871.94
#Sta/Elev= 30
  3713.5  390.62  3942.9  378.48  4053.2  377.53  4096.4  381.84  4133.9  382.54
  4139.7  379.69  4155.5  379.53  4161.3  376.57  4308.1  377.38  4468.0  378.93
  4677.1  378.47  4742.0  374.77  4769.8  377.54  4822.7  378.93  4905.9  376.35
  4946.6  380.41  4962.4  375.97  4989.8  375.16  4996.8  371.52  4997.0  371.02
  5000.9  371.52  5011.3  373.23  5022.1  377.71  5193.2  385.93  5276.4  391.11
  5329.5  389.25  5345.7  390.20  5362.4  395.08  5415.0  397.82  5725.7  400.01
#Mann=8,-1,0
  3713.5    0.05       0  3942.9   0.063       0  4308.1   0.035       0
  4468.0    0.05       0  4905.9    0.16       0  4996.8    0.07       0
  5000.9    0.16       0  5193.2    0.05       0
Bank Sta=4996.8,5000.9
Exp/Cntr=0.3,0.1

Type RM Length L Ch R = 1,4242,336,336,336
BEGIN DESCRIPTION:
Mapping XS 747f2768
END DESCRIPTION:
XS GIS Cut Line= 3
      2739403.25      6811494.89      2739318.07      6813222.97
      2739286.78      6813611.84
#Sta/Elev= 30
  3281.7  393.70  3337.9  388.98  3458.0  384.46  3618.2  374.60  3638.2  376.27
  3658.3  373.50  3748.4  373.62  3768.4  376.71  3798.4  373.01  3856.5  372.16
  3856.7  371.66  3860.6  372.16  4399.2  374.83  4429.2  374.83  4459.2  372.26
  4509.3  375.08  4649.5  375.61  4759.6  373.40  4799.6  375.65  4959.8  376.80
  4986.4  372.82  4999.9  372.52  5008.4  376.18  5030.0  377.88  5088.6  380.58
  5170.4  384.83  5190.5  389.67  5290.8  388.83  5330.9  395.47  5402.0  398.91
#Mann=5,-1,0
  3281.7    0.05       0  3856.5    0.07       0  3860.6    0.05       0
  4986.4    0.16       0  5088.6    0.05       0
Bank Sta=3856.5,3860.6
Exp/Cntr=0.3,0.1

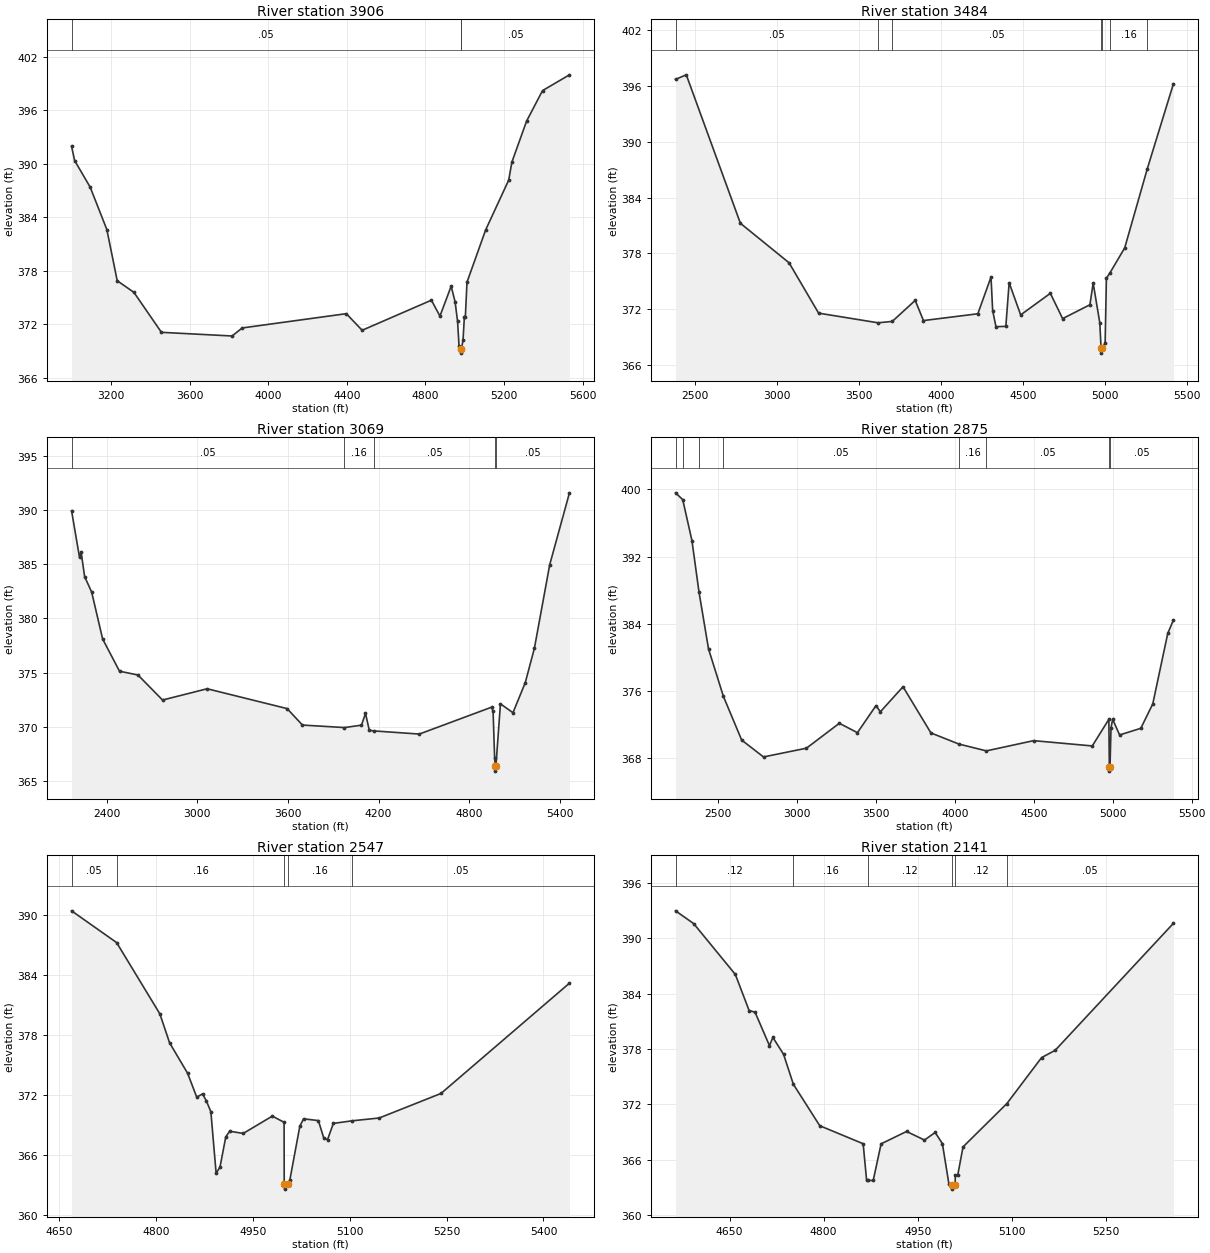
Type RM Length L Ch R = 1,3906,422,422,422
BEGIN DESCRIPTION:
Mapping XS ca7ffc95
END DESCRIPTION:
XS GIS Cut Line= 4
      2739193.03      6811245.71      2738923.03      6812397.91
      2739015.44      6813209.66      2739094.05      6813736.63
#Sta/Elev= 30
  2999.6  391.96  3015.3  390.36  3094.2  387.39  3179.2  382.63  3231.9  376.90
  3316.8  375.60  3456.9  371.12  3816.4  370.71  3867.8  371.61  4397.5  373.21
  4478.0  371.35  4830.3  374.72  4873.9  372.94  4930.9  376.29  4951.0  374.54
  4963.4  372.37  4971.2  369.54  4979.2  369.29  4979.4  368.79  4983.3  369.29
  4991.3  370.24  4998.2  372.88  5003.2  372.88  5011.5  376.74  5106.5  382.60
  5223.8  388.18  5240.0  390.20  5314.8  394.79  5395.7  398.20  5532.8  399.97
#Mann=3,-1,0
  2999.6    0.05       0  4979.2    0.05       0  4983.3    0.05       0
Bank Sta=4979.2,4983.3
Exp/Cntr=0.3,0.1

Type RM Length L Ch R = 1,3484,415,415,415
BEGIN DESCRIPTION:
Mapping XS d1db547e
END DESCRIPTION:
XS GIS Cut Line= 4
      2739269.09      6811013.80      2738566.35      6812061.09
      2738707.82      6813410.79      2738783.32      6813823.33
#Sta/Elev= 30
  2381.7  396.71  2447.3  397.20  2777.4  381.24  3074.5  376.99  3254.5  371.58
  3617.5  370.54  3704.0  370.69  3843.9  372.95  3894.2  370.78  4226.0  371.51
  4306.4  375.46  4316.5  371.86  4336.6  370.12  4396.9  370.16  4417.0  374.85
  4487.4  371.39  4668.4  373.71  4743.3  370.99  4909.7  372.48  4929.7  374.81
  4970.1  370.54  4978.0  367.78  4978.3  367.28  4982.2  367.78  5002.7  368.35
  5010.4  375.33  5032.1  375.91  5122.2  378.60  5260.1  387.11  5419.4  396.24
#Mann=7,-1,0
  2381.7    0.05       0  3617.5    0.07       0  3704.0    0.05       0
  4978.0    0.05       0  4982.2    0.05       0  5032.1    0.16       0
  5260.1    0.05       0
Bank Sta=4978,4982.2
Exp/Cntr=0.3,0.1

Type RM Length L Ch R = 1,3069,194,194,194
BEGIN DESCRIPTION:
Mapping XS 6c0c00e8
END DESCRIPTION:
XS GIS Cut Line= 3
      2737784.84      6810729.12      2738327.34      6813521.56
      2738400.50      6813970.08
#Sta/Elev= 30
  2166.2  389.93  2219.0  385.62  2229.2  386.14  2252.8  383.85  2299.4  382.42
  2371.9  378.10  2483.9  375.12  2606.2  374.77  2769.1  372.46  3064.6  373.50
  3594.3  371.67  3696.2  370.15  3974.7  369.92  4087.3  370.14  4113.8  371.23
  4139.0  369.67  4170.0  369.61  4470.4  369.32  4949.2  371.80  4959.3  371.41
  4969.5  367.09  4974.0  366.40  4974.3  365.90  4978.2  366.40  5008.0  372.11
  5091.0  371.29  5172.4  374.06  5233.2  377.25  5334.5  384.95  5465.3  391.58
#Mann=5,-1,0
  2166.2    0.05       0  3974.7    0.16       0  4170.0    0.05       0
  4974.0    0.05       0  4978.2    0.05       0
Bank Sta=4974,4978.2
Exp/Cntr=0.3,0.1

Type RM Length L Ch R = 1,2875,328,328,328
BEGIN DESCRIPTION:
Mapping XS 9aee0a53
END DESCRIPTION:
XS GIS Cut Line= 3
      2737361.56      6810906.13      2738149.77      6813569.30
      2738318.23      6813905.82
#Sta/Elev= 30
  2231.0  399.60  2276.5  398.79  2334.9  393.91  2379.4  387.81  2439.9  381.01
  2533.8  375.37  2649.9  370.15  2788.2  368.14  3060.0  369.18  3268.5  372.15
  3383.2  371.03  3500.4  374.25  3528.4  373.52  3671.9  376.50  3848.6  371.00
  4025.0  369.68  4199.8  368.86  4499.1  370.08  4870.6  369.45  4975.6  372.62
  4978.7  366.95  4979.0  366.45  4982.9  366.95  4989.3  371.62  4999.7  372.62
  5043.8  370.76  5178.0  371.55  5253.8  374.46  5348.8  382.86  5384.7  384.45
#Mann=8,-1,0
  2231.0    0.16       0  2276.5   0.035       0  2379.4    0.16       0
  2533.8    0.05       0  4025.0    0.16       0  4199.8    0.05       0
  4978.7    0.05       0  4982.9    0.05       0
Bank Sta=4978.7,4982.9
Exp/Cntr=0.3,0.1

Type RM Length L Ch R = 1,2547,406,406,406
BEGIN DESCRIPTION:
South Twin Creek Trib B2547.31
END DESCRIPTION:
XS GIS Cut Line= 3
      2737636.71      6813540.26      2737910.26      6813723.40
      2738290.92      6813948.05
#Sta/Elev= 30
  4669.1  390.38  4738.9  387.21  4805.9  380.09  4820.9  377.21  4848.8  374.17
  4863.0  371.78  4872.0  372.11  4878.0  371.39  4884.9  370.32  4893.0  364.19
  4899.0  364.80  4908.0  367.82  4914.0  368.38  4935.0  368.16  4980.1  369.89
  4998.3  369.27  4998.5  363.10  4999.0  362.60  5004.0  363.10  5007.1  363.48
  5022.7  368.89  5028.5  369.62  5051.4  369.44  5059.8  367.69  5065.6  367.54
  5074.6  369.16  5103.7  369.42  5145.6  369.70  5241.3  372.15  5440.3  383.16
#Mann=5,-1,0
  4669.1    0.05       0  4738.9    0.16       0  4998.5    0.07       0
  5004.0    0.16       0  5103.7    0.05       0
Bank Sta=4998.5,5004
Exp/Cntr=0.3,0.1

Type RM Length L Ch R = 1,2141,376,376,376
BEGIN DESCRIPTION:
South Twin Creek Trib B2141.46
END DESCRIPTION:
XS GIS Cut Line= 3
      2737506.94      6813614.22      2737692.11      6814021.29
      2737861.20      6814323.73
#Sta/Elev= 30
  4563.9  392.95  4592.8  391.57  4659.2  386.07  4681.2  382.16  4690.6  381.99
  4713.6  378.37  4719.1  379.25  4736.1  377.43  4751.7  374.19  4793.8  369.70
  4863.0  367.75  4868.5  363.78  4871.0  363.78  4879.0  363.78  4891.6  367.74
  4932.2  369.08  4960.7  368.15  4977.8  368.97  4989.3  367.76  4999.8  363.35
  5004.1  363.34  5004.5  362.84  5009.7  363.34  5009.8  364.37  5013.8  364.37
  5022.2  367.41  5092.1  372.10  5147.4  377.07  5169.1  377.86  5357.6  391.60
#Mann=6,-1,0
  4563.9    0.12       0  4751.7    0.16       0  4871.0    0.12       0
  5004.1    0.07       0  5009.7    0.12       0  5092.1    0.05       0
Bank Sta=5004.1,5009.7
Exp/Cntr=0.3,0.1

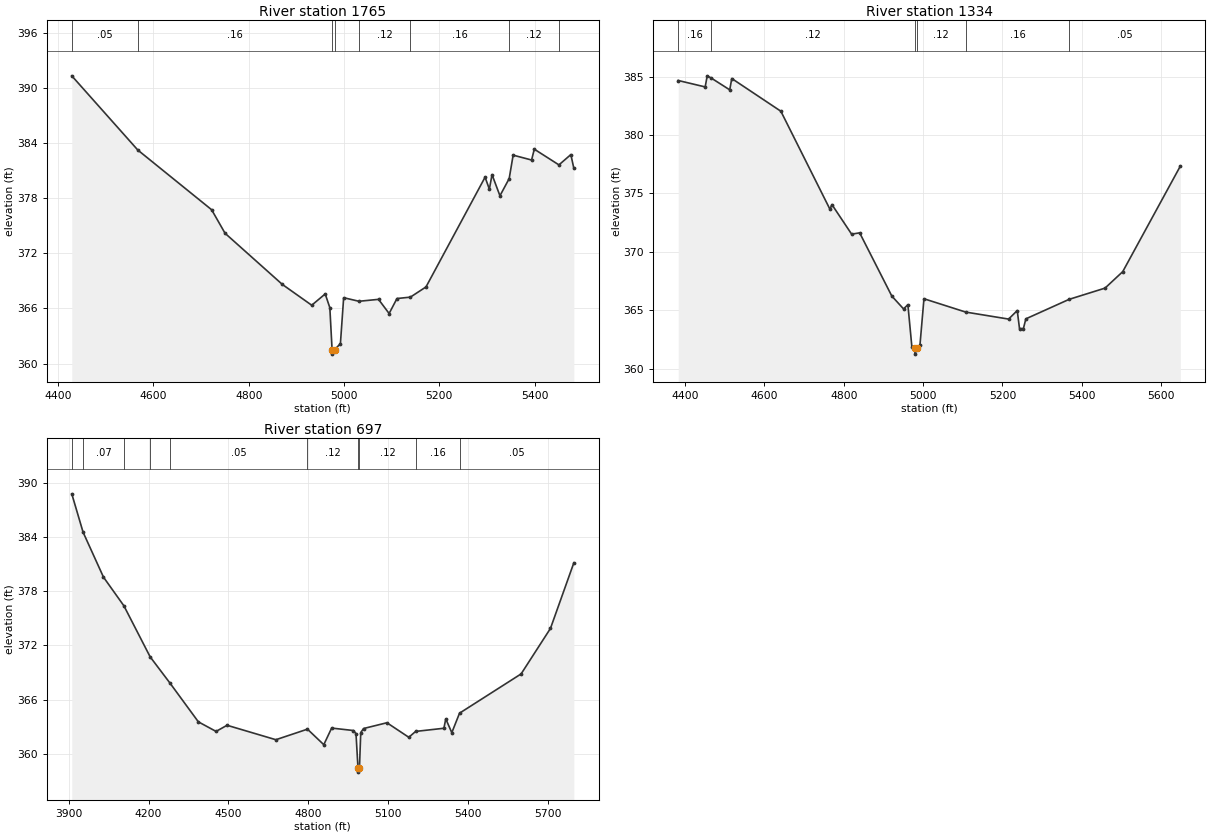
Type RM Length L Ch R = 1,1765,431,431,431
BEGIN DESCRIPTION:
South Twin Creek Trib B1764.82
END DESCRIPTION:
XS GIS Cut Line= 3
      2737114.87      6813561.63      2737359.95      6814078.36
      2737580.68      6814506.62
#Sta/Elev= 30
  4428.6  391.30  4567.3  383.22  4722.1  376.73  4750.3  374.17  4870.6  368.60
  4932.2  366.34  4960.5  367.57  4970.2  366.07  4974.9  361.52  4975.3  361.02
  4980.5  361.52  4992.4  362.16  4999.2  367.16  5031.3  366.77  5072.4  366.98
  5094.6  365.44  5111.1  367.07  5139.2  367.22  5172.0  368.33  5296.0  380.27
  5305.0  378.97  5310.6  380.55  5327.2  378.25  5346.6  380.12  5354.9  382.67
  5393.6  382.14  5399.3  383.32  5451.0  381.61  5476.0  382.73  5482.3  381.24
#Mann=8,-1,0
  4428.6    0.05       0  4567.3    0.16       0  4974.9    0.07       0
  4980.5    0.16       0  5031.3    0.12       0  5139.2    0.16       0
  5346.6    0.12       0  5451.0    0.16       0
Bank Sta=4974.9,4980.5
Exp/Cntr=0.3,0.1

Type RM Length L Ch R = 1,1334,637,637,637
BEGIN DESCRIPTION:
South Twin Creek Trib B1334.13
END DESCRIPTION:
XS GIS Cut Line= 3
      2736870.09      6813499.63      2736969.41      6814116.73
      2737278.93      6814677.09
#Sta/Elev= 30
  4382.9  384.67  4450.8  384.12  4455.9  385.07  4466.5  384.87  4512.7  383.87
  4517.8  384.84  4641.5  382.04  4765.2  373.65  4770.2  374.05  4819.8  371.52
  4840.1  371.63  4921.1  366.22  4950.7  365.12  4961.6  365.48  4971.8  361.82
  4979.1  361.75  4979.5  361.25  4984.7  361.75  4992.0  362.01  5002.1  365.99
  5107.2  364.85  5215.4  364.25  5237.2  364.98  5242.9  363.43  5252.7  363.44
  5258.9  364.27  5368.0  365.94  5458.4  366.90  5503.0  368.31  5648.1  377.34
#Mann=6,-1,0
  4382.9    0.16       0  4466.5    0.12       0  4979.1    0.07       0
  4984.7    0.12       0  5107.2    0.16       0  5368.0    0.05       0
Bank Sta=4979.1,4984.7
Exp/Cntr=0.3,0.1

Type RM Length L Ch R = 1,697,0,0,0
BEGIN DESCRIPTION:
South Twin Creek Trib B696.988
END DESCRIPTION:
XS GIS Cut Line= 3
      2736696.41      6813382.90      2736546.13      6814461.18
      2737250.98      6814835.99
#Sta/Elev= 30
  3911.3  388.79  3953.8  384.54  4030.5  379.56  4107.3  376.38  4205.9  370.73
  4280.5  367.82  4387.1  363.53  4453.6  362.47  4495.0  363.15  4678.4  361.55
  4797.1  362.72  4858.5  361.00  4888.0  362.84  4969.7  362.57  4979.6  362.22
  4986.9  358.46  4987.3  357.96  4992.6  358.46  4997.4  362.34  5007.9  362.79
  5095.8  363.43  5178.0  361.82  5203.8  362.47  5309.9  362.82  5317.0  363.86
  5339.6  362.33  5368.7  364.49  5600.1  368.84  5710.4  373.88  5798.3  381.15
#Mann=10,-1,0
  3911.3    0.16       0  3953.8    0.07       0  4107.3    0.05       0
  4205.9    0.07       0  4280.5    0.05       0  4797.1    0.12       0
  4986.9    0.07       0  4992.6    0.12       0  5203.8    0.16       0
  5368.7    0.05       0
Bank Sta=4986.9,4992.6
Exp/Cntr=0.3,0.1

Chan Stop Cuts=-1