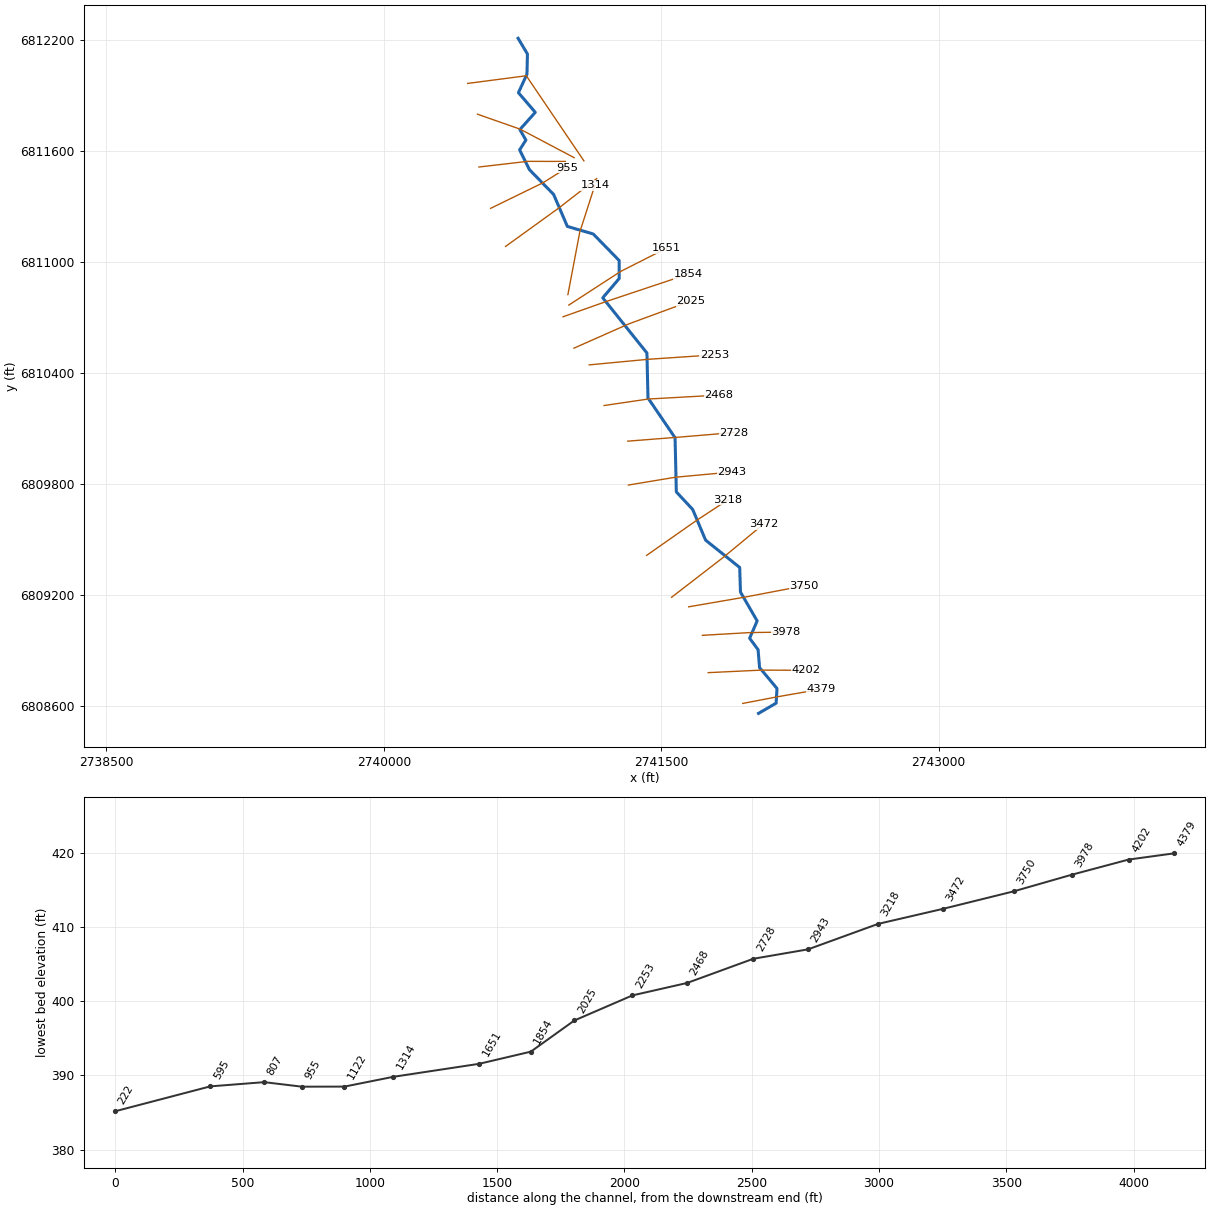
--- South Twin Creek Trib B1.prj (project) ---

Proj Title=South Twin Creek Trib B1 Base Level Engineering
Current Plan=p01
Default Exp/Contr=0.3,0.1
English Units
Geom File=g01
Flow File=f01
Plan File=p01
BEGIN DESCRIPTION:
South Twin Creek Trib B1
END DESCRIPTION:

--- South Twin Creek Trib B1.p01 (plan) ---

Plan Title=Multiple Run
Short Identifier=Multiple
Geom File=g01
Flow File=f01
Subcritical Flow
K Sum by GR= 0
Std Step Tol= 0.01
Critical Tol= 0.01
Num of Std Step Trials= 20
Max Error Tol= 0.3
Flow Tol Ratio= 0.001
Split Flow NTrial= 30
Split Flow Tol= 0.02
Split Flow Ratio= 0.02
Log Output Level= 0
Friction Slope Method= 1
Unsteady Friction Slope Method= 2
Unsteady Bridges Friction Slope Method= 1
Parabolic Critical Depth
Global Vel Dist=  1 , 1 , 1
Global Log Level= 0
CheckData=True
Encroach Param= -1, 0, 0, 0
BEGIN DESCRIPTION:
Multiple Run
END DESCRIPTION:

--- South Twin Creek Trib B1.f01 (steady flow) ---

Flow Title=Multiple
Number of Profiles=7
Profile Names=10-year,25-year,50-year,1pct_min,100-year,1pct_plu,500-year
River Rch & RM= South Twin Creek,Reach-1,4379
     257     328     384     224     446     891     604
Boundary for River Rch & Prof#=South Twin Creek,Reach-1,1
Up Type=0
Dn Type=3
Dn Slope=0.005
Boundary for River Rch & Prof#=South Twin Creek,Reach-1,2
Up Type=0
Dn Type=3
Dn Slope=0.005
Boundary for River Rch & Prof#=South Twin Creek,Reach-1,3
Up Type=0
Dn Type=3
Dn Slope=0.005
Boundary for River Rch & Prof#=South Twin Creek,Reach-1,4
Up Type=0
Dn Type=3
Dn Slope=0.005
Boundary for River Rch & Prof#=South Twin Creek,Reach-1,5
Up Type=0
Dn Type=3
Dn Slope=0.005
Boundary for River Rch & Prof#=South Twin Creek,Reach-1,6
Up Type=0
Dn Type=3
Dn Slope=0.005
Boundary for River Rch & Prof#=South Twin Creek,Reach-1,7
Up Type=0
Dn Type=3
Dn Slope=0.005

--- South Twin Creek Trib B1.g01 (geometry) ---

Geom Title=Existing Conditions

River Reach=South Twin Creek,Reach-1
Reach XY= 30
      2742026.00      6808561.00      2742121.07      6808616.27
      2742125.81      6808695.65      2742031.54      6808808.58
      2742023.50      6808905.44      2741977.86      6808967.13
      2742018.44      6809061.00      2741928.25      6809216.94
      2741924.14      6809349.85      2741739.62      6809497.78
      2741670.15      6809663.29      2741581.47      6809758.55
      2741574.64      6810051.35      2741428.18      6810266.45
      2741422.45      6810509.53      2741183.60      6810807.66
      2741272.52      6810912.50      2741272.54      6811009.50
      2741132.17      6811153.14      2740992.45      6811193.87
      2740917.86      6811367.06      2740786.75      6811501.32
      2740734.23      6811607.77      2740767.96      6811661.00
      2740735.33      6811717.67      2740818.89      6811811.00
      2740727.64      6811917.03      2740773.72      6812016.93
      2740776.45      6812126.15      2740726.00      6812211.00

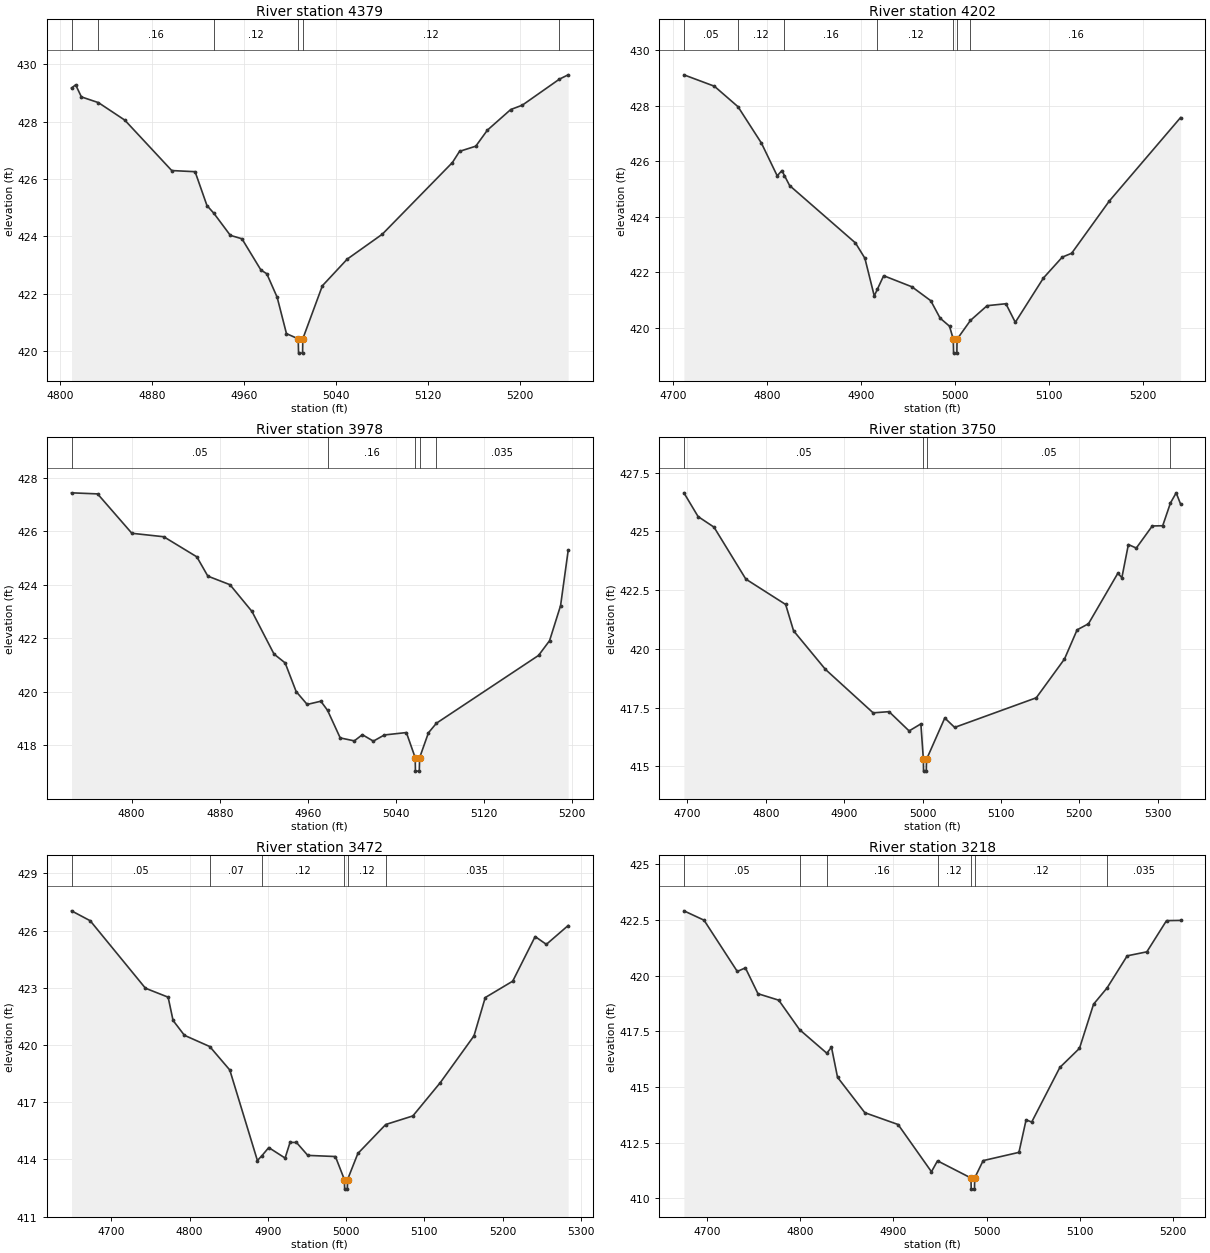
Type RM Length L Ch R = 1,4379,177,177,177
BEGIN DESCRIPTION:
South Twin Creek Trib B14378.911
END DESCRIPTION:
XS GIS Cut Line= 3
      2741940.51      6808614.75      2742127.01      6808650.55
      2742365.13      6808691.99
#Sta/Elev= 30
  4810.1  429.17  4813.7  429.28  4818.7  428.86  4833.5  428.66  4856.4  428.05
  4897.2  426.29  4917.5  426.25  4927.8  425.07  4933.8  424.80  4948.1  424.03
  4958.2  423.91  4974.7  422.82  4979.8  422.69  4988.8  421.87  4996.9  420.60
  5007.1  420.42  5007.4  419.92  5010.9  419.92  5011.1  420.42  5028.1  422.27
  5049.7  423.20  5080.2  424.07  5141.1  426.57  5147.3  426.96  5161.4  427.14
  5171.5  427.70  5191.8  428.42  5201.8  428.57  5234.1  429.48  5241.7  429.63
#Mann=6,-1,0
  4810.1    0.05       0  4833.5    0.16       0  4933.8    0.12       0
  5007.1    0.07       0  5011.1    0.12       0  5234.1    0.07       0
Bank Sta=5007.1,5011.1
Exp/Cntr=0.3,0.1

Type RM Length L Ch R = 1,4202,224,224,224
BEGIN DESCRIPTION:
South Twin Creek Trib B14201.63
END DESCRIPTION:
XS GIS Cut Line= 3
      2741753.61      6808781.18      2742042.99      6808795.01
      2742281.87      6808793.80
#Sta/Elev= 30
  4711.4  429.12  4743.8  428.71  4769.0  427.97  4793.9  426.66  4810.7  425.48
  4815.7  425.67  4818.4  425.49  4823.9  425.13  4894.0  423.06  4904.0  422.51
  4914.0  421.15  4917.4  421.40  4924.0  421.88  4954.1  421.48  4974.1  420.98
  4984.1  420.35  4994.1  420.06  4998.1  419.59  4998.4  419.09  5001.9  419.09
  5002.1  419.59  5016.4  420.27  5034.1  420.80  5054.1  420.87  5064.1  420.20
  5094.1  421.80  5114.1  422.55  5124.1  422.69  5164.1  424.57  5240.0  427.58
#Mann=7,-1,0
  4711.4    0.05       0  4769.0    0.12       0  4818.4    0.16       0
  4917.4    0.12       0  4998.1    0.07       0  5002.1    0.12       0
  5016.4    0.16       0
Bank Sta=4998.1,5002.1
Exp/Cntr=0.3,0.1

Type RM Length L Ch R = 1,3978,228,228,228
BEGIN DESCRIPTION:
South Twin Creek Trib B13978.16
END DESCRIPTION:
XS GIS Cut Line= 3
      2741722.37      6808983.06      2741976.39      6808997.77
      2742172.92      6809000.74
#Sta/Elev= 30
  4745.4  427.43  4769.1  427.39  4800.2  425.92  4829.2  425.79  4859.2  425.04
  4869.2  424.32  4889.3  424.00  4909.3  423.00  4929.3  421.41  4939.4  421.08
  4949.4  420.01  4959.4  419.53  4971.8  419.65  4977.9  419.31  4989.4  418.28
  5002.2  418.17  5009.5  418.40  5019.5  418.16  5029.5  418.39  5049.5  418.48
  5057.5  417.54  5057.7  417.04  5061.2  417.04  5061.5  417.54  5069.5  418.47
  5076.8  418.83  5169.5  421.36  5179.5  421.91  5189.5  423.22  5196.4  425.28
#Mann=5,-1,0
  4745.4    0.05       0  4977.9    0.16       0  5057.5    0.07       0
  5061.5    0.16       0  5076.8   0.035       0
Bank Sta=5057.5,5061.5
Exp/Cntr=0.3,0.1

Type RM Length L Ch R = 1,3750,278,278,278
BEGIN DESCRIPTION:
South Twin Creek Trib B13750.12
END DESCRIPTION:
XS GIS Cut Line= 3
      2741648.13      6809137.16      2741951.23      6809189.40
      2742271.45      6809250.66
#Sta/Elev= 30
  4695.6  426.64  4713.7  425.63  4734.0  425.18  4774.6  422.97  4825.4  421.89
  4835.5  420.77  4876.1  419.13  4937.0  417.28  4957.3  417.33  4982.9  416.51
  4997.9  416.81  5001.1  415.30  5001.3  414.80  5004.8  414.80  5005.1  415.30
  5028.4  417.06  5041.0  416.66  5145.1  417.92  5181.1  419.57  5197.2  420.81
  5211.7  421.07  5249.2  423.22  5254.3  423.03  5262.6  424.44  5272.7  424.29
  5293.1  425.23  5306.4  425.24  5316.3  426.21  5323.6  426.64  5329.2  426.16
#Mann=4,-1,0
  4695.6    0.05       0  5001.1    0.05       0  5005.1    0.05       0
  5316.3    0.07       0
Bank Sta=5001.1,5005.1
Exp/Cntr=0.3,0.1

Type RM Length L Ch R = 1,3472,254,254,254
BEGIN DESCRIPTION:
South Twin Creek Trib B13472.29
END DESCRIPTION:
XS GIS Cut Line= 3
      2741555.69      6809188.63      2741835.81      6809404.86
      2742052.29      6809583.91
#Sta/Elev= 30
  4649.0  427.04  4672.9  426.52  4743.5  422.98  4772.5  422.51  4778.8  421.29
  4793.3  420.51  4825.7  419.92  4851.3  418.69  4886.6  413.94  4892.5  414.20
  4901.1  414.62  4922.0  414.07  4928.3  414.89  4936.5  414.89  4951.0  414.21
  4986.3  414.15  4997.8  412.94  4998.1  412.44  5001.6  412.44  5001.8  412.94
  5015.0  414.31  5050.6  415.83  5085.3  416.28  5120.4  418.03  5163.4  420.48
  5177.8  422.49  5212.9  423.35  5241.6  425.69  5255.9  425.28  5283.8  426.27
#Mann=6,-1,0
  4649.0    0.05       0  4825.7    0.07       0  4892.5    0.12       0
  4997.8    0.07       0  5001.8    0.12       0  5050.6   0.035       0
Bank Sta=4997.8,5001.8
Exp/Cntr=0.3,0.1

Type RM Length L Ch R = 1,3218,275,275,275
BEGIN DESCRIPTION:
South Twin Creek Trib B13218.48
END DESCRIPTION:
XS GIS Cut Line= 3
      2741420.92      6809415.32      2741687.01      6809601.74
      2741861.06      6809716.00
#Sta/Elev= 30
  4675.2  422.91  4696.8  422.49  4732.5  420.19  4741.2  420.35  4754.7  419.19
  4777.0  418.90  4799.3  417.58  4828.6  416.52  4833.6  416.79  4840.1  415.44
  4869.4  413.85  4905.1  413.32  4940.9  411.20  4947.4  411.69  4983.3  410.92
  4983.6  410.42  4987.1  410.42  4987.3  410.92  4996.4  411.70  5034.8  412.07
  5042.5  413.53  5048.5  413.43  5078.7  415.88  5099.8  416.74  5114.9  418.72
  5129.4  419.45  5151.0  420.89  5172.1  421.07  5193.2  422.47  5208.3  422.48
#Mann=7,-1,0
  4675.2    0.05       0  4799.3    0.07       0  4828.6    0.16       0
  4947.4    0.12       0  4983.3    0.07       0  4987.3    0.12       0
  5129.4   0.035       0
Bank Sta=4983.3,4987.3
Exp/Cntr=0.3,0.1

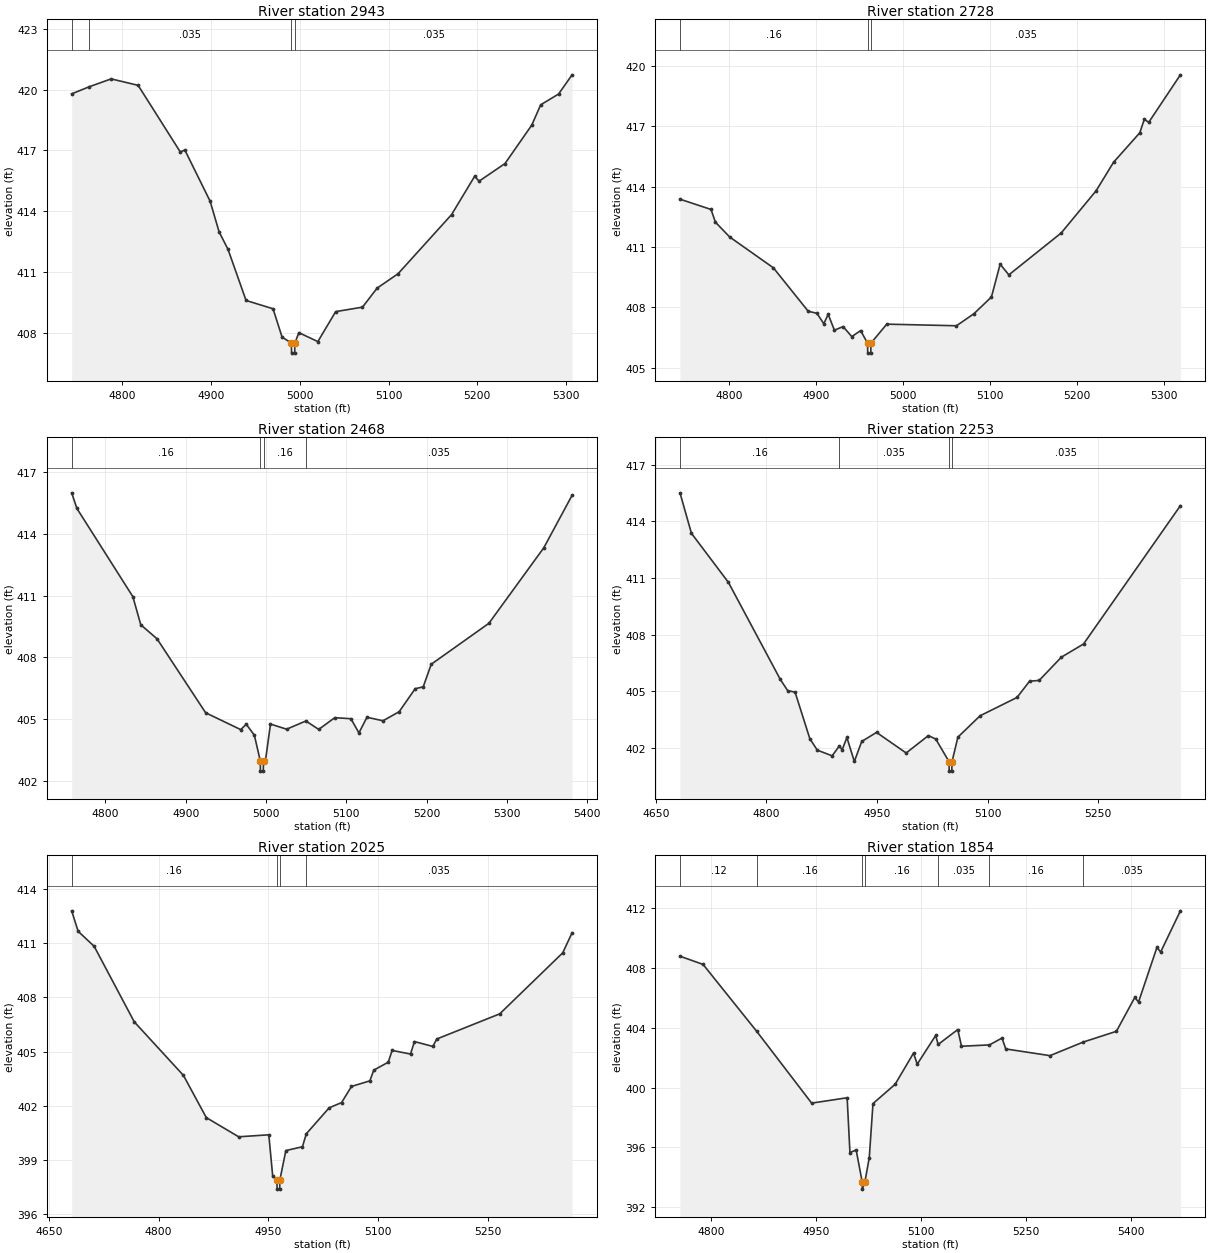
Type RM Length L Ch R = 1,2943,215,215,215
BEGIN DESCRIPTION:
South Twin Creek Trib B12943.13
END DESCRIPTION:
XS GIS Cut Line= 3
      2741322.13      6809795.66      2741578.44      6809838.14
      2741881.26      6809865.97
#Sta/Elev= 30
  4742.9  419.79  4762.6  420.14  4787.4  420.53  4817.8  420.21  4865.3  416.92
  4870.4  417.02  4898.9  414.49  4909.0  412.98  4919.1  412.11  4939.4  409.59
  4969.8  409.18  4980.0  407.78  4990.4  407.49  4990.7  406.99  4994.2  406.99
  4994.4  407.49  4998.9  408.00  5020.3  407.56  5040.4  409.04  5070.6  409.26
  5087.1  410.20  5110.7  410.91  5171.0  413.83  5197.0  415.72  5202.0  415.48
  5231.2  416.35  5261.4  418.25  5271.4  419.25  5291.5  419.78  5306.8  420.73
#Mann=4,-1,0
  4742.9    0.05       0  4762.6   0.035       0  4990.4   0.035       0
  4994.4   0.035       0
Bank Sta=4990.4,4994.4
Exp/Cntr=0.3,0.1

Type RM Length L Ch R = 1,2728,260,260,260
BEGIN DESCRIPTION:
South Twin Creek Trib B12727.87
END DESCRIPTION:
XS GIS Cut Line= 3
      2741318.96      6810032.96      2741575.77      6810052.93
      2741892.58      6810079.43
#Sta/Elev= 30
  4743.9  413.37  4779.6  412.86  4784.6  412.23  4801.1  411.49  4851.3  409.96
  4891.4  407.80  4901.4  407.70  4909.3  407.18  4914.3  407.65  4921.5  406.86
  4931.5  407.04  4941.5  406.54  4951.6  406.84  4959.6  406.22  4959.8  405.72
  4963.3  405.72  4963.6  406.22  4981.7  407.16  5061.9  407.08  5082.0  407.68
  5102.1  408.51  5112.1  410.14  5122.1  409.61  5182.3  411.69  5222.5  413.79
  5242.6  415.21  5272.7  416.67  5277.9  417.34  5283.0  417.19  5319.4  419.55
#Mann=3,-1,0
  4743.9    0.16       0  4959.6   0.035       0  4963.6   0.035       0
Bank Sta=4959.6,4963.6
Exp/Cntr=0.3,0.1

Type RM Length L Ch R = 1,2468,215,215,215
BEGIN DESCRIPTION:
South Twin Creek Trib B12467.88
END DESCRIPTION:
XS GIS Cut Line= 3
      2741190.85      6810225.61      2741429.65      6810260.73
      2741811.19      6810281.94
#Sta/Elev= 30
  4757.9  416.00  4764.4  415.24  4834.1  410.95  4844.0  409.58  4864.2  408.90
  4924.8  405.30  4968.5  404.48  4975.4  404.74  4985.5  404.21  4992.9  402.96
  4993.1  402.46  4996.6  402.46  4996.9  402.96  4999.3  402.96  5005.6  404.75
  5025.7  404.50  5049.7  404.90  5065.7  404.49  5085.7  405.06  5105.8  405.01
  5115.8  404.32  5125.8  405.08  5145.8  404.91  5165.9  405.35  5185.9  406.47
  5195.9  406.56  5205.9  407.66  5277.7  409.65  5346.2  413.33  5381.4  415.88
#Mann=4,-1,0
  4757.9    0.16       0  4992.9    0.07       0  4996.9    0.16       0
  5049.7   0.035       0
Bank Sta=4992.9,4996.9
Exp/Cntr=0.3,0.1

Type RM Length L Ch R = 1,2253,228,228,228
BEGIN DESCRIPTION:
South Twin Creek Trib B12252.7
END DESCRIPTION:
XS GIS Cut Line= 3
      2741110.57      6810445.36      2741427.48      6810475.42
      2741787.13      6810499.58
#Sta/Elev= 30
  4682.7  415.51  4698.2  413.37  4748.4  410.77  4818.7  405.64  4828.8  405.04
  4838.8  404.96  4858.9  402.49  4869.0  401.89  4889.1  401.59  4898.8  402.11
  4902.7  401.91  4909.1  402.56  4919.2  401.29  4929.2  402.35  4949.3  402.83
  4989.5  401.74  5019.6  402.66  5029.6  402.48  5047.7  401.28  5047.9  400.78
  5051.4  400.78  5051.7  401.28  5059.7  402.58  5089.8  403.71  5139.9  404.68
  5156.9  405.54  5169.9  405.58  5200.0  406.81  5230.1  407.51  5361.5  414.83
#Mann=4,-1,0
  4682.7    0.16       0  4898.8   0.035       0  5047.7   0.035       0
  5051.7   0.035       0
Bank Sta=5047.7,5051.7
Exp/Cntr=0.3,0.1

Type RM Length L Ch R = 1,2025,171,171,171
BEGIN DESCRIPTION:
South Twin Creek Trib B12025.28
END DESCRIPTION:
XS GIS Cut Line= 3
      2741027.92      6810535.78      2741322.58      6810666.19
      2741661.26      6810791.08
#Sta/Elev= 30
  4681.4  412.77  4690.2  411.64  4712.1  410.81  4766.8  406.64  4834.0  403.68
  4865.2  401.35  4909.4  400.29  4950.5  400.40  4955.9  398.10  4961.6  397.90
  4961.9  397.40  4965.4  397.40  4965.6  397.90  4973.8  399.53  4996.4  399.74
  5001.8  400.46  5032.9  401.89  5049.9  402.18  5063.4  403.07  5088.5  403.38
  5093.8  403.97  5113.6  404.41  5118.9  405.06  5144.0  404.86  5149.4  405.55
  5174.5  405.28  5179.8  405.69  5265.8  407.08  5351.8  410.45  5364.6  411.56
#Mann=4,-1,0
  4681.4    0.16       0  4961.6    0.07       0  4965.6    0.16       0
  5001.8   0.035       0
Bank Sta=4961.6,4965.6
Exp/Cntr=0.3,0.1

Type RM Length L Ch R = 1,1854,203,203,203
BEGIN DESCRIPTION:
South Twin Creek Trib B11853.8
END DESCRIPTION:
XS GIS Cut Line= 3
      2740968.75      6810705.39      2741198.40      6810786.62
      2741645.16      6810935.81
#Sta/Elev= 30
  4755.6  408.80  4788.6  408.25  4865.3  403.76  4943.6  398.96  4994.3  399.32
  4998.3  395.65  5007.2  395.82  5015.7  393.70  5016.0  393.20  5019.7  393.70
  5025.9  395.31  5031.2  398.93  5062.8  400.22  5089.1  402.31  5094.4  401.57
  5120.7  403.49  5124.3  402.89  5152.3  403.89  5157.6  402.77  5197.5  402.86
  5215.5  403.32  5220.8  402.59  5284.0  402.14  5331.4  403.05  5378.8  403.77
  5405.1  406.04  5410.4  405.73  5436.7  409.39  5442.0  409.08  5470.2  411.84
#Mann=7,-1,0
  4755.6    0.12       0  4865.3    0.16       0  5015.7    0.07       0
  5019.7    0.16       0  5124.3   0.035       0  5197.5    0.16       0
  5331.4   0.035       0
Bank Sta=5015.7,5019.7
Exp/Cntr=0.3,0.1

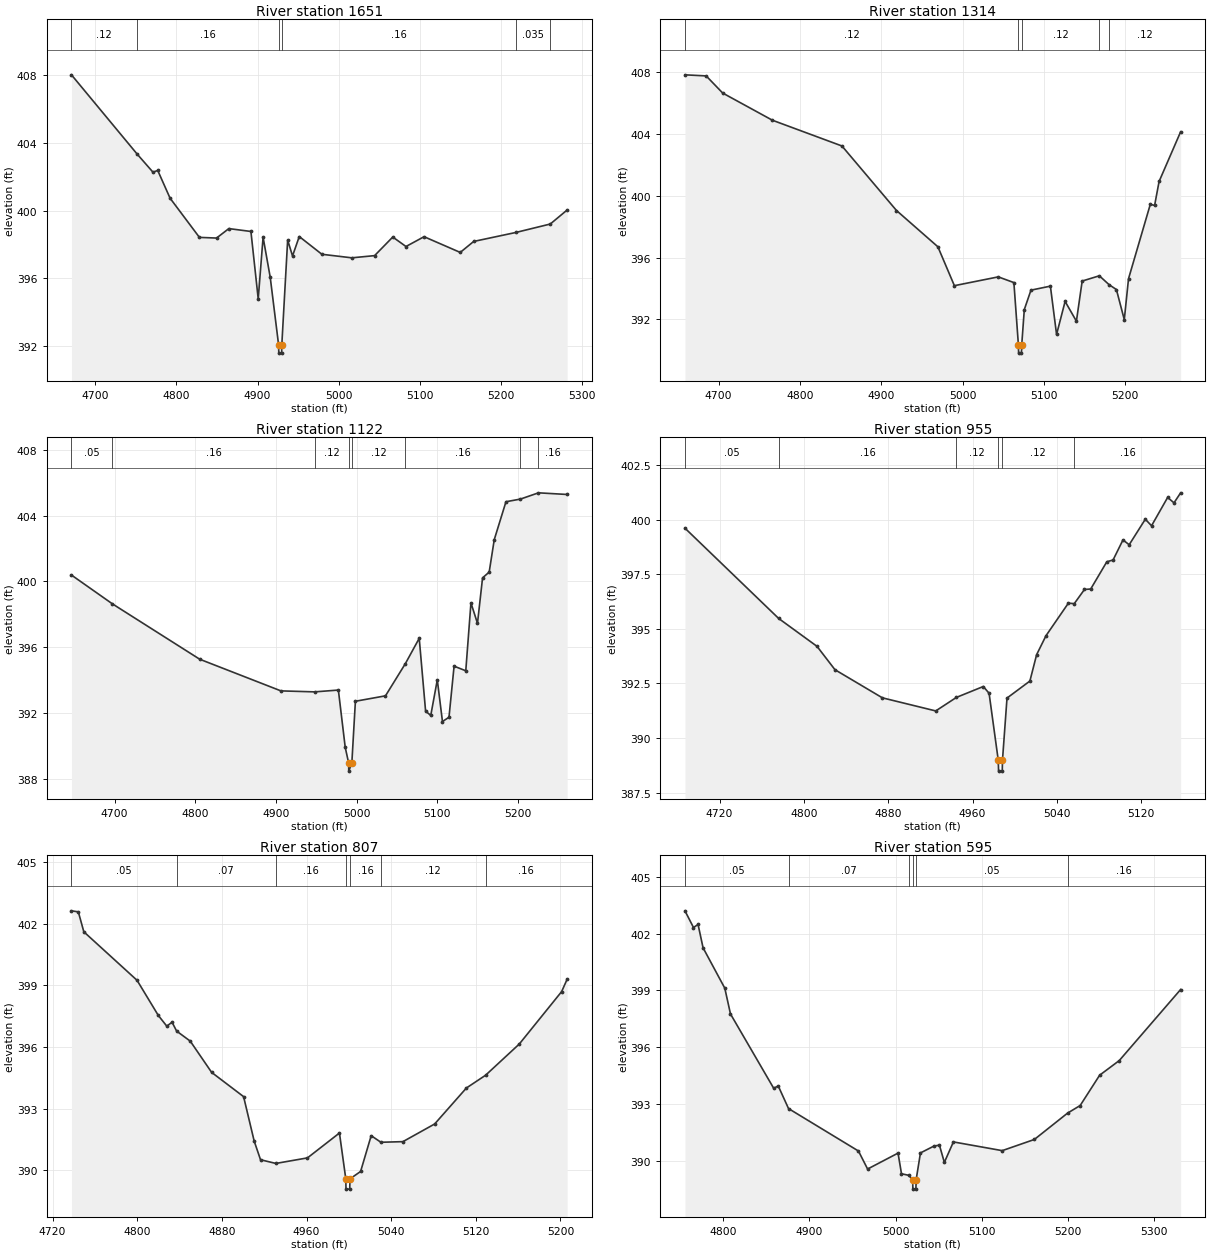
Type RM Length L Ch R = 1,1651,337,337,337
BEGIN DESCRIPTION:
South Twin Creek Trib B11651.47
END DESCRIPTION:
XS GIS Cut Line= 3
      2741000.35      6810768.94      2741280.87      6810950.94
      2741527.88      6811075.89
#Sta/Elev= 30
  4670.5  408.03  4751.5  403.34  4771.0  402.27  4776.9  402.37  4792.1  400.73
  4828.3  398.41  4849.4  398.37  4864.6  398.93  4891.8  398.76  4900.8  394.77
  4906.8  398.42  4915.6  396.05  4925.9  392.06  4926.2  391.56  4929.7  391.56
  4929.9  392.06  4937.1  398.25  4943.1  397.31  4951.4  398.46  4979.3  397.41
  5016.2  397.20  5044.3  397.33  5066.7  398.43  5083.0  397.87  5105.3  398.45
  5149.9  397.52  5166.5  398.17  5218.4  398.70  5260.9  399.20  5281.7  400.03
#Mann=6,-1,0
  4670.5    0.12       0  4751.5    0.16       0  4925.9    0.07       0
  4929.9    0.16       0  5218.4   0.035       0  5260.9    0.16       0
Bank Sta=4925.9,4929.9
Exp/Cntr=0.3,0.1

Type RM Length L Ch R = 1,1314,192,192,192
BEGIN DESCRIPTION:
South Twin Creek Trib B11313.6
END DESCRIPTION:
XS GIS Cut Line= 3
      2740995.20      6810825.38      2741059.21      6811162.83
      2741140.91      6811416.22
#Sta/Elev= 30
  4658.6  407.84  4684.7  407.77  4705.0  406.66  4766.1  404.90  4851.7  403.23
  4918.8  399.05  4969.7  396.70  4990.0  394.18  5044.0  394.75  5063.2  394.38
  5068.8  390.31  5069.0  389.81  5072.5  389.81  5072.8  390.31  5076.0  392.63
  5084.2  393.89  5108.1  394.15  5115.7  391.02  5126.2  393.16  5140.1  391.88
  5147.2  394.48  5168.3  394.82  5180.4  394.24  5189.3  393.93  5199.0  391.98
  5204.2  394.63  5231.0  399.45  5236.3  399.38  5241.8  400.93  5268.3  404.15
#Mann=5,-1,0
  4658.6    0.12       0  5068.8    0.07       0  5072.8    0.12       0
  5168.3    0.16       0  5180.4    0.12       0
Bank Sta=5068.8,5072.8
Exp/Cntr=0.3,0.1

Type RM Length L Ch R = 1,1122,167,167,167
BEGIN DESCRIPTION:
South Twin Creek Trib B11122.35
END DESCRIPTION:
XS GIS Cut Line= 3
      2740658.13      6811085.73      2740945.81      6811293.48
      2741150.82      6811452.49
#Sta/Elev= 30
  4646.5  400.39  4697.3  398.64  4805.5  395.28  4906.1  393.36  4947.9  393.30
  4977.3  393.41  4985.8  389.93  4990.0  388.99  4990.2  388.49  4994.0  388.99
  4998.4  392.73  5035.7  393.06  5060.4  395.02  5077.5  396.55  5085.4  392.13
  5091.8  391.87  5099.9  394.03  5106.3  391.50  5114.4  391.76  5120.7  394.86
  5135.2  394.58  5141.6  398.70  5149.7  397.46  5156.0  400.22  5164.2  400.57
  5170.5  402.54  5185.0  404.84  5202.9  405.00  5225.3  405.38  5260.8  405.28
#Mann=8,-1,0
  4646.5    0.05       0  4697.3    0.16       0  4947.9    0.12       0
  4990.0    0.07       0  4994.0    0.12       0  5060.4    0.16       0
  5202.9    0.12       0  5225.3    0.16       0
Bank Sta=4990,4994
Exp/Cntr=0.3,0.1

Type RM Length L Ch R = 1,955,148,148,148
BEGIN DESCRIPTION:
South Twin Creek Trib B1955.2
END DESCRIPTION:
XS GIS Cut Line= 3
      2740577.12      6811291.65      2740860.51      6811429.99
      2740991.64      6811512.35
#Sta/Elev= 30
  4687.2  399.62  4776.1  395.48  4812.5  394.20  4829.5  393.13  4874.5  391.84
  4925.1  391.24  4944.7  391.86  4970.2  392.36  4975.7  392.05  4984.4  388.98
  4984.7  388.48  4988.2  388.48  4988.4  388.98  4992.7  391.83  5014.4  392.61
  5020.8  393.82  5029.7  394.69  5050.9  396.18  5056.5  396.16  5066.2  396.81
  5072.1  396.83  5087.4  398.08  5093.3  398.16  5102.7  399.08  5108.6  398.86
  5123.9  400.03  5129.8  399.73  5145.1  401.03  5151.1  400.78  5157.4  401.24
#Mann=6,-1,0
  4687.2    0.05       0  4776.1    0.16       0  4944.7    0.12       0
  4984.4    0.07       0  4988.4    0.12       0  5056.5    0.16       0
Bank Sta=4984.4,4988.4
Exp/Cntr=0.3,0.1

Type RM Length L Ch R = 1,807,212,212,212
BEGIN DESCRIPTION:
South Twin Creek Trib B1806.76
END DESCRIPTION:
XS GIS Cut Line= 3
      2740514.42      6811515.27      2740776.88      6811545.77
      2740981.15      6811545.44
#Sta/Elev= 30
  4737.8  402.63  4744.3  402.58  4749.5  401.61  4799.8  399.25  4819.9  397.54
  4827.9  397.02  4832.9  397.21  4837.2  396.78  4850.1  396.29  4870.3  394.77
  4900.5  393.59  4910.5  391.43  4916.5  390.52  4931.0  390.34  4960.9  390.61
  4991.1  391.82  4997.1  389.59  4997.3  389.09  5000.8  389.09  5001.1  389.59
  5011.1  389.95  5021.1  391.69  5030.3  391.37  5051.1  391.40  5081.1  392.26
  5111.1  394.01  5129.2  394.63  5161.1  396.15  5201.1  398.70  5206.3  399.30
#Mann=7,-1,0
  4737.8    0.05       0  4837.2    0.07       0  4931.0    0.16       0
  4997.1    0.07       0  5001.1    0.16       0  5030.3    0.12       0
  5129.2    0.16       0
Bank Sta=4997.1,5001.1
Exp/Cntr=0.3,0.1

Type RM Length L Ch R = 1,595,373,373,373
BEGIN DESCRIPTION:
South Twin Creek Trib B1594.56
END DESCRIPTION:
XS GIS Cut Line= 3
      2740506.15      6811800.82      2740737.45      6811719.74
      2741029.00      6811565.80
#Sta/Elev= 30
  4755.7  403.20  4765.6  402.32  4770.9  402.48  4776.7  401.25  4801.9  399.12
  4808.5  397.76  4858.6  393.84  4863.9  393.96  4875.8  392.77  4956.9  390.53
  4967.5  389.58  5002.8  390.42  5006.8  389.33  5015.1  389.25  5019.8  389.02
  5020.0  388.52  5023.5  388.52  5023.8  389.02  5028.8  390.43  5044.4  390.79
  5050.8  390.84  5056.5  389.93  5067.0  391.01  5123.6  390.55  5160.9  391.14
  5199.4  392.53  5214.0  392.93  5236.6  394.53  5259.3  395.30  5330.5  399.05
#Mann=6,-1,0
  4755.7    0.05       0  4875.8    0.07       0  5015.1    0.05       0
  5019.8    0.07       0  5023.8    0.05       0  5199.4    0.16       0
Bank Sta=5019.8,5023.8
Exp/Cntr=0.3,0.1

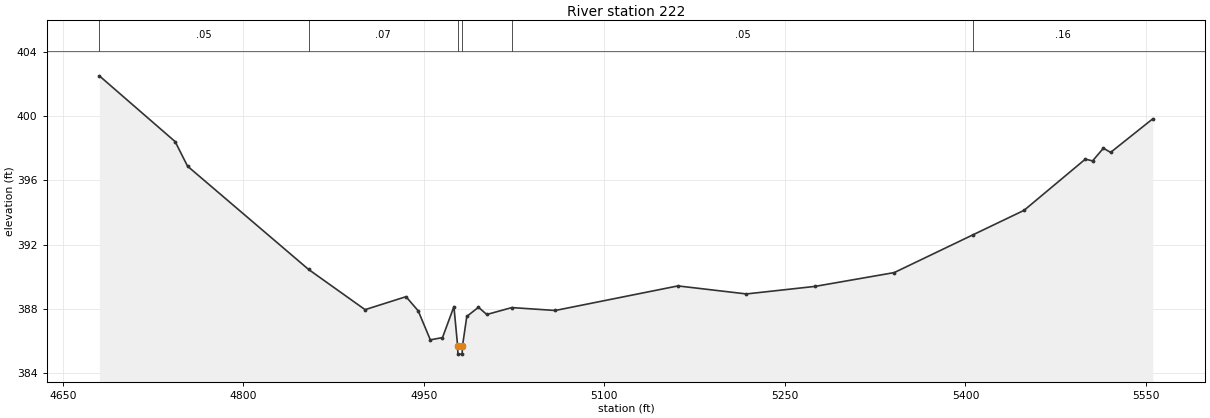
Type RM Length L Ch R = 1,222,0,0,0
BEGIN DESCRIPTION:
South Twin Creek Trib B1222.136
END DESCRIPTION:
XS GIS Cut Line= 3
      2740453.32      6811967.20      2740770.22      6812008.65
      2741081.65      6811548.54
#Sta/Elev= 30
  4680.4  402.51  4743.4  398.41  4753.7  396.88  4854.2  390.45  4901.2  387.94
  4935.2  388.75  4945.3  387.87  4955.4  386.06  4965.5  386.20  4975.0  388.13
  4978.1  385.67  4978.3  385.17  4981.8  385.17  4982.1  385.67  4985.7  387.52
  4995.4  388.09  5002.3  387.64  5023.1  388.07  5059.2  387.89  5161.1  389.42
  5218.0  388.92  5275.0  389.39  5340.8  390.25  5406.4  392.61  5448.7  394.13
  5499.6  397.32  5505.6  397.21  5514.6  398.00  5520.6  397.74  5555.6  399.83
#Mann=6,-1,0
  4680.4    0.05       0  4854.2    0.07       0  4978.1    0.07       0
  4982.1    0.07       0  5023.1    0.05       0  5406.4    0.16       0
Bank Sta=4978.1,4982.1
Exp/Cntr=0.3,0.1

Chan Stop Cuts=-1