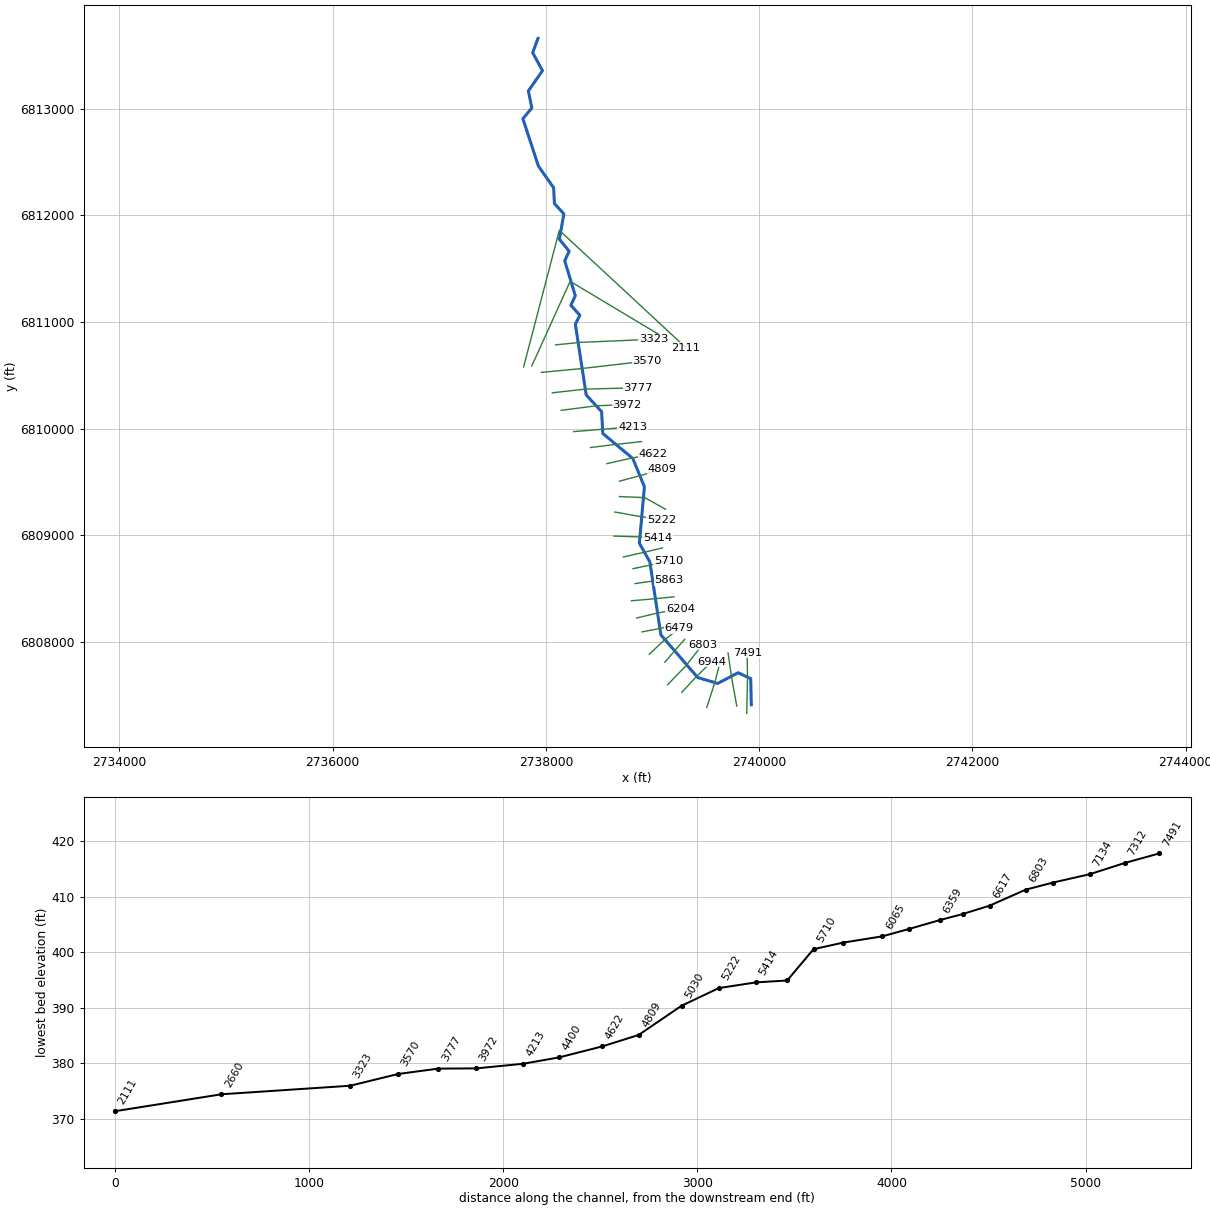
--- South Twin Creek Trib B2.prj (project) ---

Proj Title=South Twin Creek Trib B2 Base Level Engineering
Current Plan=p01
Default Exp/Contr=0.3,0.1
English Units
Geom File=g01
Flow File=f01
Plan File=p01
BEGIN DESCRIPTION:
South Twin Creek Trib B2
END DESCRIPTION:

--- South Twin Creek Trib B2.p01 (plan) ---

Plan Title=Multiple Run
Short Identifier=Multiple
Geom File=g01
Flow File=f01
Subcritical Flow
K Sum by GR= 0
Std Step Tol= 0.01
Critical Tol= 0.01
Num of Std Step Trials= 20
Max Error Tol= 0.3
Flow Tol Ratio= 0.001
Split Flow NTrial= 30
Split Flow Tol= 0.02
Split Flow Ratio= 0.02
Log Output Level= 0
Friction Slope Method= 1
Unsteady Friction Slope Method= 2
Unsteady Bridges Friction Slope Method= 1
Parabolic Critical Depth
Global Vel Dist=  1 , 1 , 1
Global Log Level= 0
CheckData=True
Encroach Param= -1, 0, 0, 0
BEGIN DESCRIPTION:
Multiple Run
END DESCRIPTION:

--- South Twin Creek Trib B2.f01 (steady flow) ---

Flow Title=Multiple
Number of Profiles=7
Profile Names=10-year,25-year,50-year,1pct_min,100-year,1pct_plu,500-year
River Rch & RM= South Twin Creek,Reach-1,7491
     498     660     789     469     935    1866    1313
Boundary for River Rch & Prof#=South Twin Creek,Reach-1,1
Up Type=0
Dn Type=3
Dn Slope=0.005
Boundary for River Rch & Prof#=South Twin Creek,Reach-1,2
Up Type=0
Dn Type=3
Dn Slope=0.005
Boundary for River Rch & Prof#=South Twin Creek,Reach-1,3
Up Type=0
Dn Type=3
Dn Slope=0.005
Boundary for River Rch & Prof#=South Twin Creek,Reach-1,4
Up Type=0
Dn Type=3
Dn Slope=0.005
Boundary for River Rch & Prof#=South Twin Creek,Reach-1,5
Up Type=0
Dn Type=3
Dn Slope=0.005
Boundary for River Rch & Prof#=South Twin Creek,Reach-1,6
Up Type=0
Dn Type=3
Dn Slope=0.005
Boundary for River Rch & Prof#=South Twin Creek,Reach-1,7
Up Type=0
Dn Type=3
Dn Slope=0.005

--- South Twin Creek Trib B2.g01 (geometry) ---

Geom Title=Existing Conditions

River Reach=South Twin Creek,Reach-1
Reach XY= 30
      2739926.00      6807411.00      2739920.83      6807655.60
      2739803.21      6807711.40      2739610.61      6807611.08
      2739423.57      6807666.52      2739078.18      6808066.45
      2738974.64      6808751.35      2738876.51      6808926.21
      2738923.74      6809455.06      2738815.25      6809720.71
      2738533.81      6809954.81      2738522.46      6810159.54
      2738378.18      6810316.45      2738275.89      6810979.46
      2738318.15      6811064.41      2738233.85      6811157.59
      2738275.70      6811246.87      2738176.30      6811575.13
      2738218.17      6811664.40      2738126.39      6811776.16
      2738168.19      6812014.41      2738079.57      6812112.47
      2738072.45      6812259.53      2737929.76      6812462.56
      2737783.89      6812907.78      2737867.99      6813007.67
      2737835.31      6813167.66      2737967.98      6813357.69
      2737876.03      6813526.38      2737926.00      6813661.00

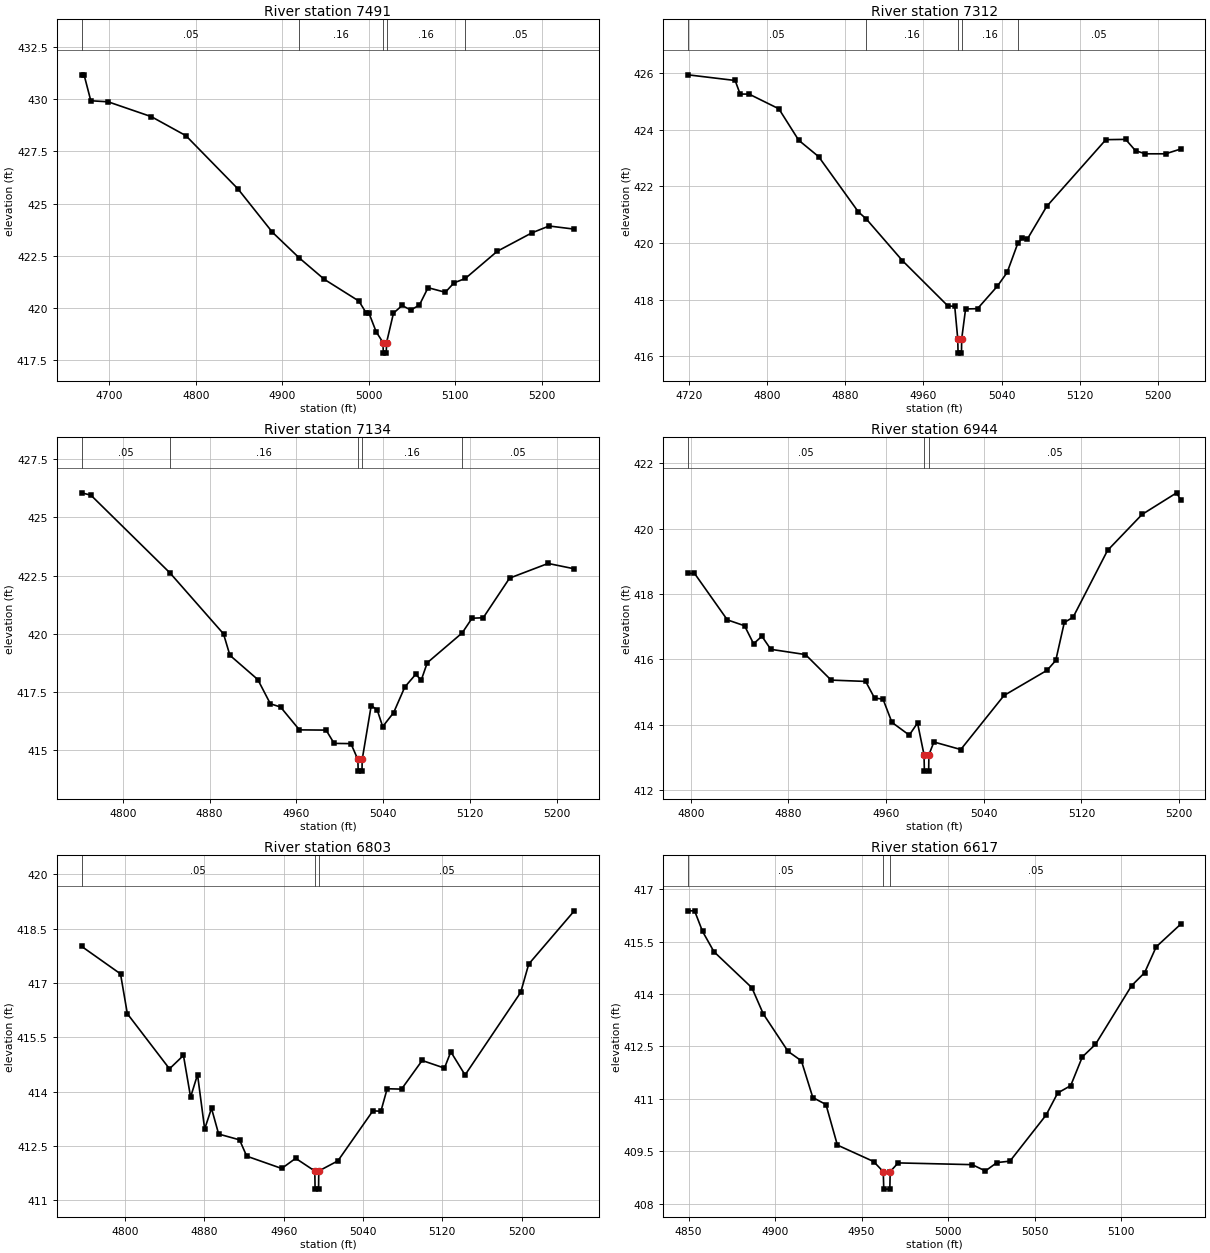
Type RM Length L Ch R = 1,7491,179,179,179
BEGIN DESCRIPTION:
South Twin Creek Trib B27490.691
END DESCRIPTION:
XS GIS Cut Line= 3
      2739883.27      6807330.29      2739890.62      6807662.40
      2739887.32      6807900.18
#Sta/Elev= 30
  4667.8  431.16  4670.7  431.16  4678.5  429.92  4698.5  429.87  4748.5  429.16
  4788.5  428.25  4848.6  425.71  4888.6  423.63  4919.7  422.40  4948.6  421.38
  4988.6  420.34  4996.8  419.79  5000.0  419.79  5008.6  418.87  5016.6  418.35
  5016.8  417.85  5020.3  417.85  5020.6  418.35  5028.6  419.76  5038.6  420.13
  5048.6  419.91  5058.6  420.15  5068.6  420.98  5088.6  420.76  5098.6  421.21
  5111.7  421.42  5148.6  422.72  5188.6  423.60  5208.6  423.93  5237.8  423.78
#Mann=5,-1,0
  4667.8    0.05       0  4919.7    0.16       0  5016.6    0.07       0
  5020.6    0.16       0  5111.7    0.05       0
Bank Sta=5016.6,5020.6
Exp/Cntr=0.3,0.1

Type RM Length L Ch R = 1,7312,178,178,178
BEGIN DESCRIPTION:
South Twin Creek Trib B27312.03
END DESCRIPTION:
XS GIS Cut Line= 3
      2739789.71      6807399.55      2739738.89      6807681.90
      2739708.14      6807896.82
#Sta/Elev= 30
  4719.2  425.94  4767.4  425.74  4772.5  425.26  4781.6  425.26  4812.1  424.74
  4832.4  423.63  4852.8  423.05  4893.4  421.10  4901.5  420.85  4938.4  419.38
  4984.9  417.78  4992.0  417.76  4995.1  416.61  4995.4  416.11  4998.9  416.11
  4999.1  416.61  5003.1  417.67  5015.3  417.68  5035.5  418.47  5045.6  418.96
  5056.5  419.99  5061.3  420.18  5066.3  420.14  5086.0  421.29  5146.6  423.65
  5166.8  423.66  5176.9  423.26  5187.0  423.15  5207.6  423.15  5223.2  423.32
#Mann=5,-1,0
  4719.2    0.05       0  4901.5    0.16       0  4995.1    0.07       0
  4999.1    0.16       0  5056.5    0.05       0
Bank Sta=4995.1,4999.1
Exp/Cntr=0.3,0.1

Type RM Length L Ch R = 1,7134,190,190,190
BEGIN DESCRIPTION:
South Twin Creek Trib B27133.84
END DESCRIPTION:
XS GIS Cut Line= 3
      2739508.79      6807386.40      2739584.11      6807619.77
      2739636.28      6807822.34
#Sta/Elev= 30
  4762.0  426.05  4770.6  425.95  4843.6  422.61  4892.9  420.00  4898.8  419.08
  4924.5  418.04  4936.1  417.00  4945.5  416.86  4962.9  415.88  4987.5  415.87
  4994.9  415.30  5010.4  415.29  5016.8  414.61  5017.1  414.11  5020.6  414.11
  5020.8  414.61  5029.1  416.92  5034.6  416.74  5039.7  416.02  5049.8  416.62
  5060.1  417.72  5070.1  418.26  5075.3  418.02  5080.8  418.76  5113.0  420.04
  5122.1  420.67  5132.4  420.69  5156.7  422.39  5192.2  423.02  5216.4  422.79
#Mann=5,-1,0
  4762.0    0.05       0  4843.6    0.16       0  5016.8    0.07       0
  5020.8    0.16       0  5113.0    0.05       0
Bank Sta=5016.8,5020.8
Exp/Cntr=0.3,0.1

Type RM Length L Ch R = 1,6944,141,141,141
BEGIN DESCRIPTION:
South Twin Creek Trib B26943.9
END DESCRIPTION:
XS GIS Cut Line= 3
      2739273.74      6807527.46      2739411.42      6807674.91
      2739555.15      6807816.65
#Sta/Elev= 30
  4797.8  418.63  4803.1  418.63  4830.0  417.21  4844.1  417.03  4851.5  416.48
  4858.3  416.71  4865.6  416.31  4894.0  416.15  4915.0  415.37  4943.3  415.33
  4950.6  414.82  4957.5  414.79  4964.8  414.08  4979.0  413.69  4985.8  414.06
  4991.1  413.09  4991.4  412.59  4994.9  412.59  4995.1  413.09  4999.2  413.48
  5021.2  413.25  5056.6  414.90  5091.9  415.67  5099.0  415.97  5106.0  417.13
  5113.2  417.29  5141.4  419.33  5169.7  420.43  5198.0  421.09  5201.4  420.87
#Mann=3,-1,0
  4797.8    0.05       0  4991.1    0.05       0  4995.1    0.05       0
Bank Sta=4991.1,4995.1
Exp/Cntr=0.3,0.1

Type RM Length L Ch R = 1,6803,186,186,186
BEGIN DESCRIPTION:
South Twin Creek Trib B26802.69
END DESCRIPTION:
XS GIS Cut Line= 3
      2739141.87      6807599.65      2739311.98      6807775.15
      2739468.28      6807973.69
#Sta/Elev= 30
  4756.0  418.01  4795.3  417.25  4802.2  416.15  4844.7  414.63  4858.8  415.00
  4866.0  413.85  4873.0  414.47  4880.2  412.97  4887.1  413.54  4894.3  412.83
  4915.4  412.67  4922.6  412.22  4957.9  411.88  4972.0  412.16  4991.3  411.81
  4991.6  411.31  4995.1  411.31  4995.3  411.81  5014.6  412.09  5049.9  413.47
  5058.0  413.46  5064.3  414.08  5078.8  414.07  5099.6  414.86  5122.1  414.65
  5128.5  415.10  5142.9  414.46  5199.0  416.74  5207.1  417.52  5253.1  418.99
#Mann=3,-1,0
  4756.0    0.05       0  4991.3    0.05       0  4995.3    0.05       0
Bank Sta=4991.3,4995.3
Exp/Cntr=0.3,0.1

Type RM Length L Ch R = 1,6617,138,138,138
BEGIN DESCRIPTION:
South Twin Creek Trib B26617.49
END DESCRIPTION:
XS GIS Cut Line= 3
      2739115.00      6807810.22      2739212.30      6807923.37
      2739301.76      6808025.10
#Sta/Elev= 30
  4849.7  416.38  4853.5  416.38  4858.1  415.79  4864.7  415.21  4886.6  414.18
  4893.2  413.43  4907.5  412.36  4915.2  412.09  4921.8  411.04  4929.4  410.84
  4936.0  409.68  4956.9  409.21  4962.5  408.92  4962.8  408.42  4966.3  408.42
  4966.5  408.92  4971.1  409.17  5013.9  409.12  5021.5  408.94  5028.2  409.18
  5035.7  409.22  5056.6  410.54  5063.3  411.17  5070.8  411.38  5077.5  412.20
  5085.1  412.56  5106.0  414.24  5113.5  414.61  5120.2  415.35  5134.4  416.00
#Mann=3,-1,0
  4849.7    0.05       0  4962.5    0.05       0  4966.5    0.05       0
Bank Sta=4962.5,4966.5
Exp/Cntr=0.3,0.1

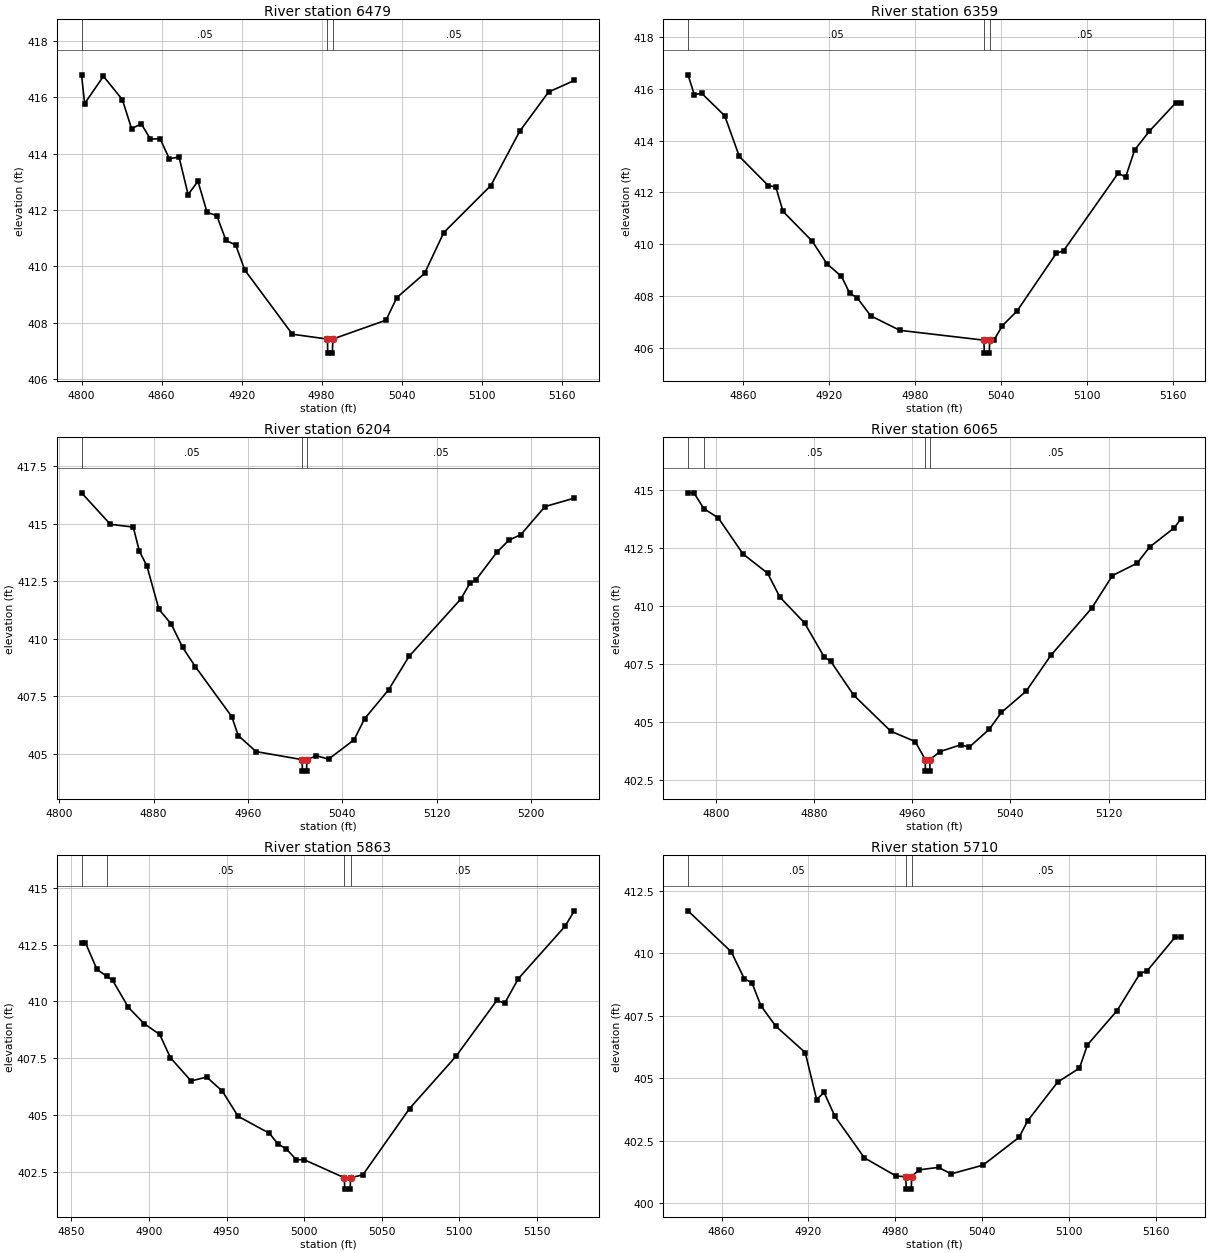
Type RM Length L Ch R = 1,6479,120,120,120
BEGIN DESCRIPTION:
South Twin Creek Trib B26479.49
END DESCRIPTION:
XS GIS Cut Line= 3
      2738969.10      6807884.67      2739112.96      6808019.72
      2739248.10      6808126.42
#Sta/Elev= 30
  4800.0  416.80  4802.3  415.78  4816.4  416.75  4830.6  415.92  4837.5  414.89
  4844.8  415.06  4851.6  414.52  4858.9  414.53  4865.8  413.82  4873.1  413.88
  4879.9  412.55  4887.3  413.02  4894.1  411.92  4901.4  411.80  4908.3  410.92
  4915.6  410.76  4922.4  409.87  4958.1  407.59  4984.4  407.42  4984.6  406.92
  4988.1  406.92  4988.4  407.42  5028.3  408.09  5036.4  408.89  5057.2  409.75
  5071.6  411.20  5106.9  412.87  5128.6  414.80  5150.2  416.19  5169.5  416.60
#Mann=3,-1,0
  4800.0    0.05       0  4984.4    0.05       0  4988.4    0.05       0
Bank Sta=4984.4,4988.4
Exp/Cntr=0.3,0.1

Type RM Length L Ch R = 1,6359,155,155,155
BEGIN DESCRIPTION:
South Twin Creek Trib B26358.54
END DESCRIPTION:
XS GIS Cut Line= 3
      2738900.87      6808094.34      2739073.62      6808127.89
      2739237.46      6808164.68
#Sta/Elev= 30
  4821.7  416.54  4826.1  415.77  4831.2  415.83  4847.3  414.96  4857.5  413.39
  4877.8  412.26  4882.9  412.22  4888.0  411.27  4908.4  410.12  4918.6  409.25
  4928.8  408.76  4934.6  408.11  4939.7  407.94  4949.2  407.24  4969.5  406.68
  5028.2  406.30  5028.5  405.80  5032.0  405.80  5032.2  406.30  5035.3  406.31
  5041.1  406.86  5051.4  407.43  5078.7  409.65  5083.8  409.75  5122.0  412.75
  5127.1  412.59  5133.4  413.64  5143.6  414.36  5162.3  415.47  5165.6  415.47
#Mann=3,-1,0
  4821.7    0.05       0  5028.2    0.05       0  5032.2    0.05       0
Bank Sta=5028.2,5032.2
Exp/Cntr=0.3,0.1

Type RM Length L Ch R = 1,6204,139,139,139
BEGIN DESCRIPTION:
South Twin Creek Trib B26203.82
END DESCRIPTION:
XS GIS Cut Line= 3
      2738852.25      6808224.81      2739027.67      6808267.07
      2739260.45      6808312.44
#Sta/Elev= 30
  4819.0  416.35  4843.4  414.98  4862.8  414.86  4868.0  413.81  4874.3  413.18
  4884.6  411.28  4894.9  410.65  4904.7  409.62  4915.4  408.79  4946.3  406.61
  4951.8  405.79  4966.9  405.09  5005.9  404.74  5006.2  404.24  5009.7  404.24
  5009.9  404.74  5018.1  404.91  5028.3  404.76  5049.9  405.60  5058.9  406.52
  5079.2  407.78  5096.5  409.23  5140.4  411.73  5148.1  412.41  5153.2  412.56
  5170.9  413.76  5181.1  414.29  5191.3  414.53  5211.7  415.75  5236.6  416.12
#Mann=3,-1,0
  4819.0    0.05       0  5005.9    0.05       0  5009.9    0.05       0
Bank Sta=5005.9,5009.9
Exp/Cntr=0.3,0.1

Type RM Length L Ch R = 1,6065,202,202,202
BEGIN DESCRIPTION:
South Twin Creek Trib B26065.12
END DESCRIPTION:
XS GIS Cut Line= 3
      2738801.35      6808386.39      2739024.38      6808405.54
      2739201.41      6808423.56
#Sta/Elev= 30
  4777.1  414.87  4781.9  414.87  4790.0  414.19  4801.8  413.79  4821.9  412.24
  4842.0  411.41  4852.0  410.38  4872.1  409.27  4888.3  407.79  4893.3  407.63
  4912.2  406.16  4942.4  404.61  4962.4  404.16  4970.5  403.39  4970.7  402.89
  4974.2  402.89  4974.5  403.39  4982.5  403.73  4999.3  404.02  5006.6  403.93
  5022.7  404.69  5032.7  405.42  5052.8  406.33  5072.9  407.87  5106.2  409.90
  5123.2  411.31  5143.3  411.84  5153.4  412.53  5173.5  413.36  5178.9  413.74
#Mann=4,-1,0
  4777.1    0.16       0  4790.0    0.05       0  4970.5    0.05       0
  4974.5    0.05       0
Bank Sta=4970.5,4974.5
Exp/Cntr=0.3,0.1

Type RM Length L Ch R = 1,5863,153,153,153
BEGIN DESCRIPTION:
South Twin Creek Trib B25863.22
END DESCRIPTION:
XS GIS Cut Line= 3
      2738836.17      6808547.34      2738975.43      6808567.97
      2739152.01      6808579.05
#Sta/Elev= 30
  4856.5  412.58  4859.0  412.58  4866.4  411.41  4872.7  411.11  4876.5  410.93
  4886.7  409.74  4896.8  409.03  4906.9  408.55  4913.8  407.53  4927.1  406.51
  4937.2  406.68  4947.3  406.06  4957.4  404.96  4977.6  404.21  4983.3  403.73
  4988.3  403.54  4995.0  403.05  5000.1  403.05  5025.9  402.26  5026.2  401.76
  5029.7  401.76  5029.9  402.26  5037.9  402.39  5068.0  405.30  5098.0  407.60
  5124.3  410.05  5129.3  409.92  5138.1  411.00  5168.2  413.30  5174.2  413.98
#Mann=4,-1,0
  4856.5    0.16       0  4872.7    0.05       0  5025.9    0.05       0
  5029.9    0.05       0
Bank Sta=5025.9,5029.9
Exp/Cntr=0.3,0.1

Type RM Length L Ch R = 1,5710,136,136,136
BEGIN DESCRIPTION:
South Twin Creek Trib B25710.43
END DESCRIPTION:
XS GIS Cut Line= 3
      2738816.72      6808687.16      2738974.75      6808720.35
      2739148.72      6808762.58
#Sta/Elev= 30
  4836.8  411.70  4866.7  410.06  4875.8  408.97  4880.9  408.83  4887.2  407.90
  4897.4  407.09  4917.8  406.03  4925.7  404.15  4930.8  404.44  4938.3  403.48
  4958.7  401.82  4980.7  401.09  4987.3  401.07  4987.6  400.57  4991.1  400.57
  4991.3  401.07  4996.4  401.34  5009.9  401.44  5018.6  401.18  5040.7  401.53
  5065.5  402.64  5071.6  403.31  5092.2  404.85  5107.3  405.41  5112.8  406.34
  5133.3  407.71  5149.1  409.19  5154.2  409.31  5173.3  410.64  5177.3  410.64
#Mann=3,-1,0
  4836.8    0.05       0  4987.3    0.05       0  4991.3    0.05       0
Bank Sta=4987.3,4991.3
Exp/Cntr=0.3,0.1

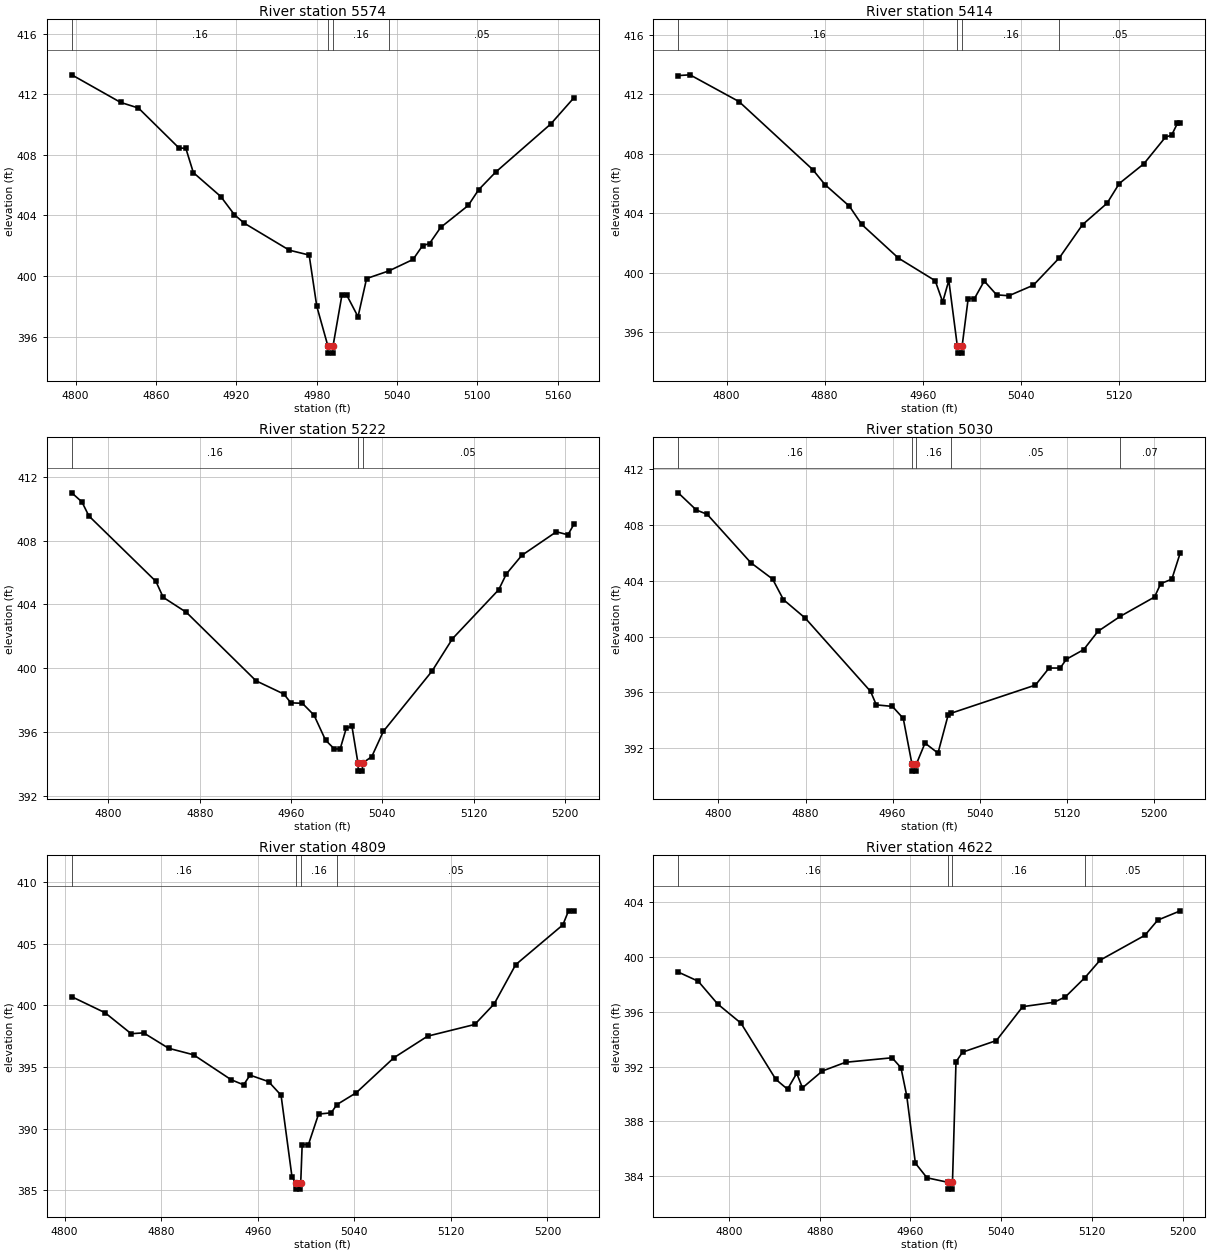
Type RM Length L Ch R = 1,5574,160,160,160
BEGIN DESCRIPTION:
South Twin Creek Trib B25573.6
END DESCRIPTION:
XS GIS Cut Line= 3
      2738727.38      6808797.61      2738927.74      6808842.19
      2739092.72      6808882.11
#Sta/Elev= 30
  4797.1  413.28  4833.6  411.46  4846.9  411.09  4877.1  408.46  4882.3  408.43
  4887.9  406.83  4908.4  405.25  4918.6  404.05  4925.8  403.50  4959.6  401.71
  4974.4  401.39  4980.1  398.01  4988.3  395.42  4988.6  394.92  4992.1  394.92
  4992.3  395.42  4998.9  398.76  5002.4  398.76  5010.9  397.32  5017.3  399.84
  5034.1  400.35  5052.0  401.10  5059.1  402.01  5064.3  402.15  5072.6  403.21
  5093.2  404.66  5101.0  405.70  5113.7  406.86  5154.9  410.04  5172.1  411.76
#Mann=4,-1,0
  4797.1    0.16       0  4988.3    0.07       0  4992.3    0.16       0
  5034.1    0.05       0
Bank Sta=4988.3,4992.3
Exp/Cntr=0.3,0.1

Type RM Length L Ch R = 1,5414,192,192,192
BEGIN DESCRIPTION:
South Twin Creek Trib B25414.24
END DESCRIPTION:
XS GIS Cut Line= 3
      2738636.41      6808993.45      2738874.84      6808985.25
      2739045.69      6808975.45
#Sta/Elev= 30
  4760.5  413.25  4770.1  413.30  4810.1  411.50  4870.2  406.93  4880.2  405.92
  4900.2  404.46  4910.2  403.24  4940.2  400.97  4970.2  399.45  4976.3  398.02
  4981.3  399.47  4988.2  395.08  4988.5  394.58  4992.0  394.58  4992.2  395.08
  4997.1  398.25  5002.2  398.25  5010.2  399.43  5020.3  398.50  5030.3  398.44
  5050.3  399.15  5071.5  400.99  5090.4  403.22  5110.4  404.66  5120.4  405.99
  5140.5  407.32  5158.1  409.11  5163.1  409.24  5167.8  410.03  5170.2  410.03
#Mann=4,-1,0
  4760.5    0.16       0  4988.2    0.07       0  4992.2    0.16       0
  5071.5    0.05       0
Bank Sta=4988.2,4992.2
Exp/Cntr=0.3,0.1

Type RM Length L Ch R = 1,5222,192,192,192
BEGIN DESCRIPTION:
South Twin Creek Trib B25221.83
END DESCRIPTION:
XS GIS Cut Line= 3
      2738647.20      6809218.85      2738876.16      6809177.52
      2739081.15      6809147.77
#Sta/Elev= 30
  4767.9  410.99  4776.8  410.42  4782.9  409.54  4841.6  405.44  4848.0  404.44
  4868.3  403.50  4929.3  399.21  4953.7  398.38  4959.8  397.83  4969.9  397.80
  4980.1  397.06  4990.2  395.49  4997.9  394.94  5003.0  394.94  5008.3  396.23
  5013.3  396.37  5018.6  394.05  5018.9  393.55  5022.4  393.55  5022.6  394.05
  5030.7  394.46  5040.8  396.04  5083.5  399.82  5101.4  401.85  5141.9  404.92
  5148.6  405.91  5162.1  407.07  5192.4  408.55  5202.5  408.36  5207.7  409.01
#Mann=3,-1,0
  4767.9    0.16       0  5018.6    0.07       0  5022.6    0.05       0
Bank Sta=5018.6,5022.6
Exp/Cntr=0.3,0.1

Type RM Length L Ch R = 1,5030,221,221,221
BEGIN DESCRIPTION:
South Twin Creek Trib B25029.58
END DESCRIPTION:
XS GIS Cut Line= 3
      2738689.38      6809363.58      2738927.85      6809353.65
      2739122.04      6809244.59
#Sta/Elev= 30
  4763.0  410.31  4779.6  409.08  4789.6  408.77  4829.7  405.30  4849.7  404.13
  4859.7  402.65  4879.7  401.33  4939.8  396.07  4945.0  395.11  4959.8  395.00
  4969.8  394.14  4977.8  390.86  4978.1  390.36  4981.6  390.36  4981.8  390.86
  4989.8  392.37  5001.7  391.65  5011.0  394.37  5013.7  394.51  5091.3  396.53
  5103.8  397.75  5114.0  397.75  5119.7  398.38  5135.6  399.07  5148.7  400.38
  5169.1  401.45  5200.7  402.84  5206.4  403.80  5216.6  404.12  5224.4  406.02
#Mann=5,-1,0
  4763.0    0.16       0  4977.8    0.07       0  4981.8    0.16       0
  5013.7    0.05       0  5169.1    0.07       0
Bank Sta=4977.8,4981.8
Exp/Cntr=0.3,0.1

Type RM Length L Ch R = 1,4809,187,187,187
BEGIN DESCRIPTION:
South Twin Creek Trib B24809.24
END DESCRIPTION:
XS GIS Cut Line= 3
      2738688.49      6809507.78      2738874.78      6809557.66
      2739089.44      6809618.59
#Sta/Elev= 30
  4805.9  400.70  4833.5  399.40  4855.1  397.70  4865.4  397.77  4886.1  396.52
  4906.8  395.99  4937.9  393.97  4948.3  393.55  4953.6  394.34  4969.0  393.81
  4979.3  392.71  4988.4  386.06  4991.6  385.59  4991.8  385.09  4995.3  385.09
  4995.6  385.59  4996.8  388.71  5002.0  388.71  5010.4  391.18  5020.8  391.28
  5025.6  391.95  5041.6  392.91  5072.8  395.75  5100.7  397.50  5139.8  398.45
  5155.9  400.12  5173.7  403.30  5212.8  406.53  5217.5  407.67  5221.9  407.67
#Mann=4,-1,0
  4805.9    0.16       0  4991.6    0.07       0  4995.6    0.16       0
  5025.6    0.05       0
Bank Sta=4991.6,4995.6
Exp/Cntr=0.3,0.1

Type RM Length L Ch R = 1,4622,222,222,222
BEGIN DESCRIPTION:
South Twin Creek Trib B24621.53
END DESCRIPTION:
XS GIS Cut Line= 3
      2738572.07      6809672.56      2738812.32      6809726.32
      2739005.58      6809760.78
#Sta/Elev= 30
  4755.3  398.91  4772.9  398.24  4790.1  396.57  4810.6  395.17  4841.3  391.06
  4851.6  390.34  4859.7  391.50  4864.8  390.44  4882.3  391.67  4902.8  392.31
  4943.8  392.64  4951.6  391.91  4956.7  389.85  4964.3  384.93  4974.5  383.86
  4993.0  383.53  4993.2  383.03  4996.7  383.03  4997.0  383.53  5000.1  392.34
  5005.9  393.05  5035.7  393.90  5058.9  396.38  5086.5  396.70  5096.6  397.10
  5113.8  398.51  5127.1  399.78  5166.6  401.60  5177.9  402.71  5197.8  403.39
#Mann=4,-1,0
  4755.3    0.16       0  4993.0    0.07       0  4997.0    0.16       0
  5113.8    0.05       0
Bank Sta=4993,4997
Exp/Cntr=0.3,0.1

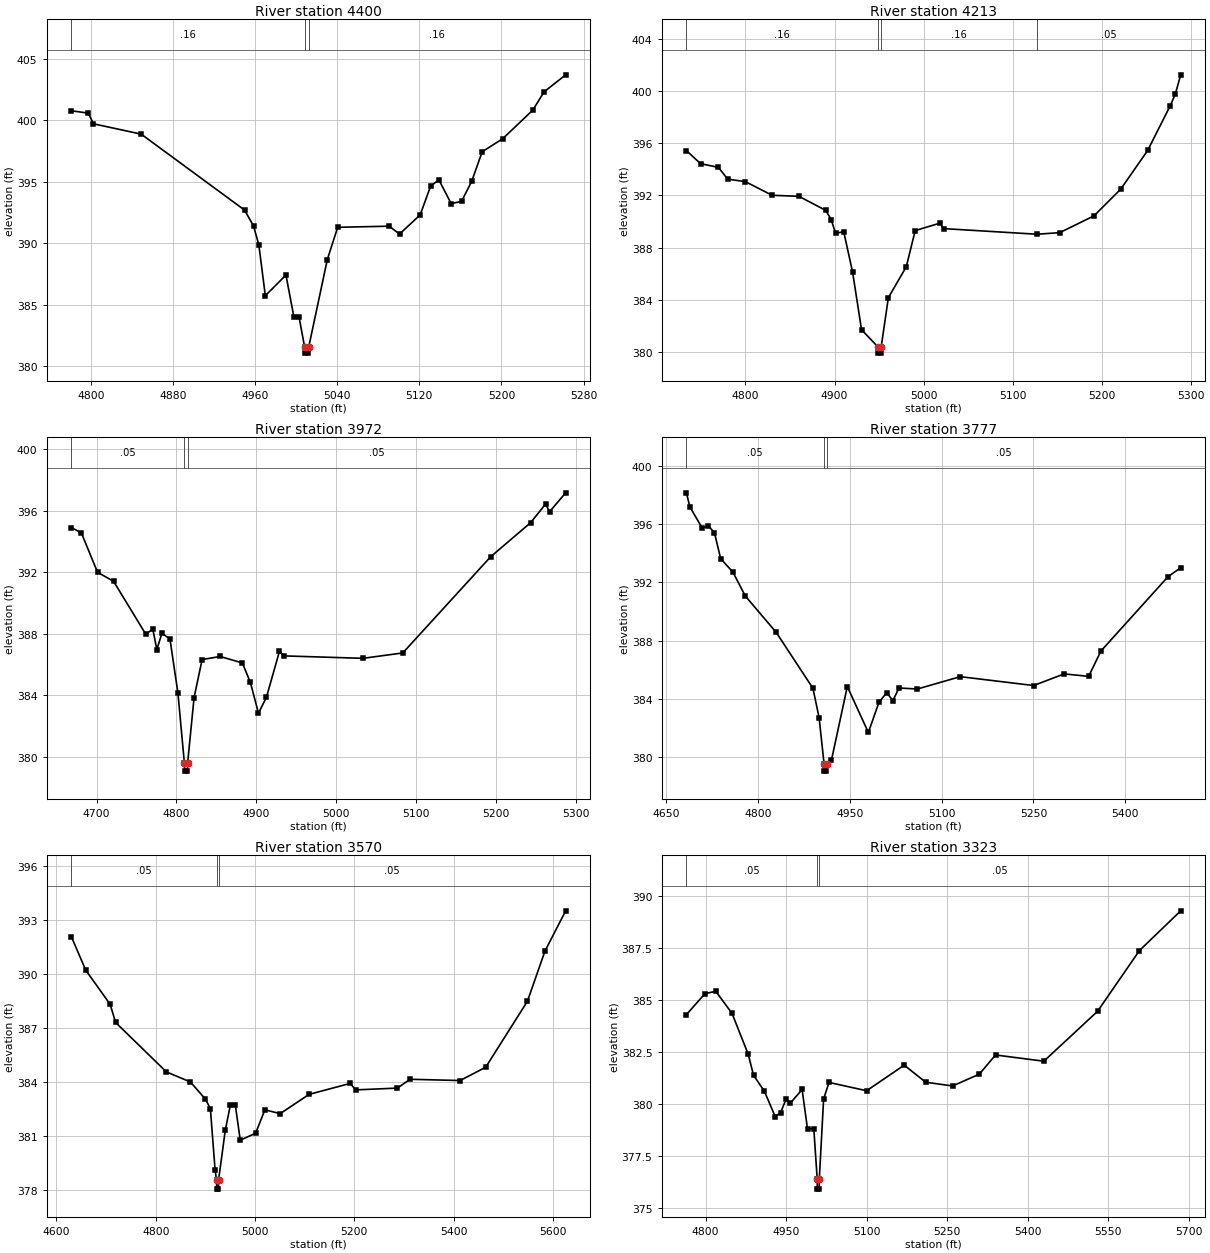
Type RM Length L Ch R = 1,4400,187,187,187
BEGIN DESCRIPTION:
South Twin Creek Trib B24399.77
END DESCRIPTION:
XS GIS Cut Line= 3
      2738418.48      6809823.48      2738636.22      6809850.73
      2738896.95      6809879.00
#Sta/Elev= 30
  4780.9  400.79  4797.4  400.60  4802.4  399.73  4848.9  398.89  4949.7  392.70
  4958.5  391.39  4963.6  389.85  4969.9  385.73  4990.0  387.41  4997.7  384.02
  5002.7  384.02  5008.2  381.55  5008.4  381.05  5011.9  381.05  5012.2  381.55
  5030.3  388.67  5040.4  391.30  5090.6  391.39  5100.7  390.75  5120.8  392.31
  5130.9  394.64  5139.0  395.17  5151.0  393.23  5161.1  393.41  5171.1  395.06
  5181.2  397.45  5201.3  398.52  5230.6  400.85  5241.5  402.33  5262.6  403.72
#Mann=3,-1,0
  4780.9    0.16       0  5008.2    0.07       0  5012.2    0.16       0
Bank Sta=5008.2,5012.2
Exp/Cntr=0.3,0.1

Type RM Length L Ch R = 1,4213,241,241,241
BEGIN DESCRIPTION:
South Twin Creek Trib B24212.68
END DESCRIPTION:
XS GIS Cut Line= 3
      2738260.13      6809972.59      2738525.73      6809994.48
      2738812.97      6810016.78
#Sta/Elev= 30
  4733.7  395.44  4749.6  394.44  4769.7  394.15  4780.0  393.25  4799.8  393.06
  4829.9  392.01  4860.0  391.93  4890.1  390.85  4896.1  390.15  4901.1  389.08
  4910.2  389.22  4920.2  386.10  4930.2  381.69  4948.3  380.39  4948.5  379.89
  4952.0  379.89  4952.3  380.39  4960.3  384.15  4980.4  386.52  4990.4  389.30
  5017.7  389.86  5022.7  389.45  5127.0  389.02  5152.5  389.14  5191.0  390.43
  5221.1  392.49  5251.2  395.45  5276.3  398.85  5282.3  399.79  5288.3  401.26
#Mann=4,-1,0
  4733.7    0.16       0  4948.3    0.07       0  4952.3    0.16       0
  5127.0    0.05       0
Bank Sta=4948.3,4952.3
Exp/Cntr=0.3,0.1

Type RM Length L Ch R = 1,3972,195,195,195
BEGIN DESCRIPTION:
South Twin Creek Trib B23972.23
END DESCRIPTION:
XS GIS Cut Line= 3
      2738143.57      6810172.44      2738471.98      6810214.87
      2738759.89      6810226.90
#Sta/Elev= 30
  4668.4  394.91  4680.9  394.56  4701.2  392.00  4721.3  391.41  4761.6  387.97
  4770.4  388.30  4775.5  386.97  4781.8  388.03  4791.9  387.66  4801.9  384.14
  4810.0  379.56  4810.3  379.06  4813.8  379.06  4814.0  379.56  4822.1  383.84
  4832.2  386.32  4854.8  386.52  4882.6  386.10  4892.7  384.83  4902.8  382.83
  4912.8  383.87  4929.1  386.86  4934.2  386.56  5033.6  386.40  5083.6  386.75
  5193.7  393.01  5243.8  395.23  5262.5  396.44  5267.5  395.94  5287.7  397.17
#Mann=3,-1,0
  4668.4    0.05       0  4810.0    0.05       0  4814.0    0.05       0
Bank Sta=4810,4814
Exp/Cntr=0.3,0.1

Type RM Length L Ch R = 1,3777,207,207,207
BEGIN DESCRIPTION:
South Twin Creek Trib B23777.24
END DESCRIPTION:
XS GIS Cut Line= 3
      2738060.34      6810336.72      2738375.61      6810371.91
      2738866.45      6810383.56
#Sta/Elev= 30
  4682.6  398.17  4688.3  397.20  4708.4  395.75  4718.5  395.90  4728.5  395.42
  4738.6  393.64  4758.7  392.71  4778.9  391.07  4829.2  388.58  4889.5  384.72
  4899.6  382.69  4907.7  379.52  4907.9  379.02  4911.4  379.02  4911.7  379.52
  4919.7  379.76  4945.7  384.84  4980.1  381.68  4997.5  383.76  5010.2  384.42
  5020.2  383.87  5030.2  384.74  5060.2  384.67  5130.3  385.52  5250.3  384.91
  5300.3  385.71  5340.3  385.54  5360.3  387.28  5470.3  392.41  5490.8  393.01
#Mann=3,-1,0
  4682.6    0.05       0  4907.7    0.05       0  4911.7    0.05       0
Bank Sta=4907.7,4911.7
Exp/Cntr=0.3,0.1

Type RM Length L Ch R = 1,3570,247,247,247
BEGIN DESCRIPTION:
South Twin Creek Trib B23569.79
END DESCRIPTION:
XS GIS Cut Line= 3
      2737957.28      6810528.24      2738322.56      6810562.88
      2738947.31      6810634.86
#Sta/Elev= 30
  4630.0  392.09  4658.9  390.23  4708.1  388.33  4719.1  387.32  4821.4  384.57
  4869.8  384.01  4899.9  383.06  4910.0  382.53  4919.5  379.12  4922.5  378.55
  4922.8  378.05  4926.3  378.05  4926.5  378.55  4940.1  381.34  4950.2  382.71
  4960.2  382.74  4970.2  380.77  5001.2  381.16  5019.8  382.46  5050.7  382.25
  5108.8  383.32  5191.6  383.93  5202.8  383.57  5286.8  383.67  5312.4  384.16
  5413.1  384.09  5464.7  384.83  5548.7  388.50  5584.2  391.30  5625.8  393.53
#Mann=3,-1,0
  4630.0    0.05       0  4922.5    0.05       0  4926.5    0.05       0
Bank Sta=4922.5,4926.5
Exp/Cntr=0.3,0.1

Type RM Length L Ch R = 1,3323,663,663,663
BEGIN DESCRIPTION:
South Twin Creek Trib B23323.22
END DESCRIPTION:
XS GIS Cut Line= 3
      2738091.44      6810786.55      2738327.72      6810809.96
      2739010.75      6810839.16
#Sta/Elev= 30
  4764.2  384.32  4798.9  385.33  4819.0  385.44  4849.2  384.38  4879.3  382.42
  4889.4  381.40  4909.5  380.64  4929.6  379.42  4939.6  379.60  4949.7  380.24
  4958.1  380.07  4979.8  380.72  4989.9  378.82  5001.6  378.84  5007.9  376.43
  5008.2  375.93  5011.7  375.93  5011.9  376.43  5019.9  380.26  5029.9  381.06
  5100.0  380.66  5170.1  381.89  5210.1  381.07  5260.2  380.89  5310.2  381.46
  5340.2  382.38  5430.3  382.08  5530.4  384.48  5608.4  387.40  5685.3  389.31
#Mann=3,-1,0
  4764.2    0.05       0  5007.9    0.05       0  5011.9    0.05       0
Bank Sta=5007.9,5011.9
Exp/Cntr=0.3,0.1

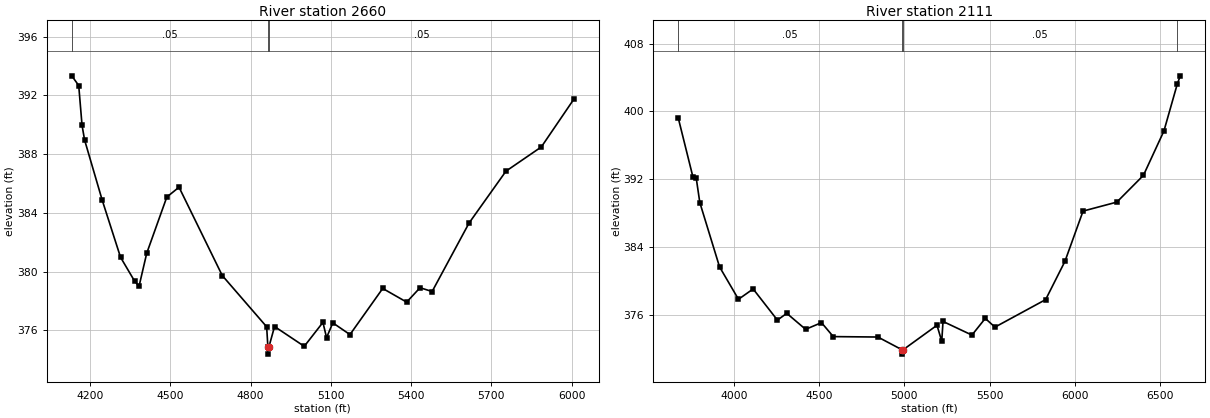
Type RM Length L Ch R = 1,2660,549,549,549
BEGIN DESCRIPTION:
Mapping XS d21de7db
END DESCRIPTION:
XS GIS Cut Line= 3
      2737866.85      6810587.32      2738227.39      6811382.15
      2739089.33      6810865.90
#Sta/Elev= 30
  4131.2  393.33  4157.2  392.67  4169.6  389.96  4179.2  388.96  4245.0  384.87
  4313.6  380.98  4365.8  379.37  4382.8  379.01  4411.4  381.25  4486.6  385.08
  4532.3  385.75  4693.9  379.74  4860.0  376.25  4864.5  374.89  4864.7  374.39
  4868.5  374.89  4889.5  376.27  5000.6  374.92  5070.4  376.55  5084.0  375.51
  5107.3  376.52  5171.5  375.72  5294.0  378.86  5383.5  377.93  5433.6  378.91
  5478.7  378.65  5616.8  383.31  5754.8  386.84  5887.1  388.49  6008.7  391.74
#Mann=3,-1,0
  4131.2    0.05       0  4864.5    0.05       0  4868.5    0.05       0
Bank Sta=4864.5,4868.5
Exp/Cntr=0.3,0.1

Type RM Length L Ch R = 1,2111,0,0,0
BEGIN DESCRIPTION:
South Twin Creek Trib B23033.04
END DESCRIPTION:
XS GIS Cut Line= 3
      2737790.61      6810578.59      2738125.85      6811861.00
      2739311.83      6810760.97
#Sta/Elev= 30
  3674.5  399.24  3760.0  392.31  3780.3  392.08  3801.0  389.24  3916.6  381.64
  4027.6  377.81  4113.6  379.03  4255.8  375.35  4310.7  376.15  4421.2  374.26
  4514.2  375.05  4583.4  373.40  4845.0  373.35  4987.7  371.83  4987.9  371.33
  4991.7  371.83  5191.2  374.74  5219.2  372.85  5226.6  375.19  5396.1  373.58
  5474.3  375.55  5531.0  374.52  5828.1  377.77  5941.3  382.29  6047.5  388.23
  6245.4  389.29  6401.3  392.45  6521.5  397.69  6600.4  403.28  6617.6  404.21
#Mann=4,-1,0
  3674.5    0.05       0  4987.7    0.05       0  4991.7    0.05       0
  6600.4    0.07       0
Bank Sta=4987.7,4991.7
Exp/Cntr=0.3,0.1

Chan Stop Cuts=-1