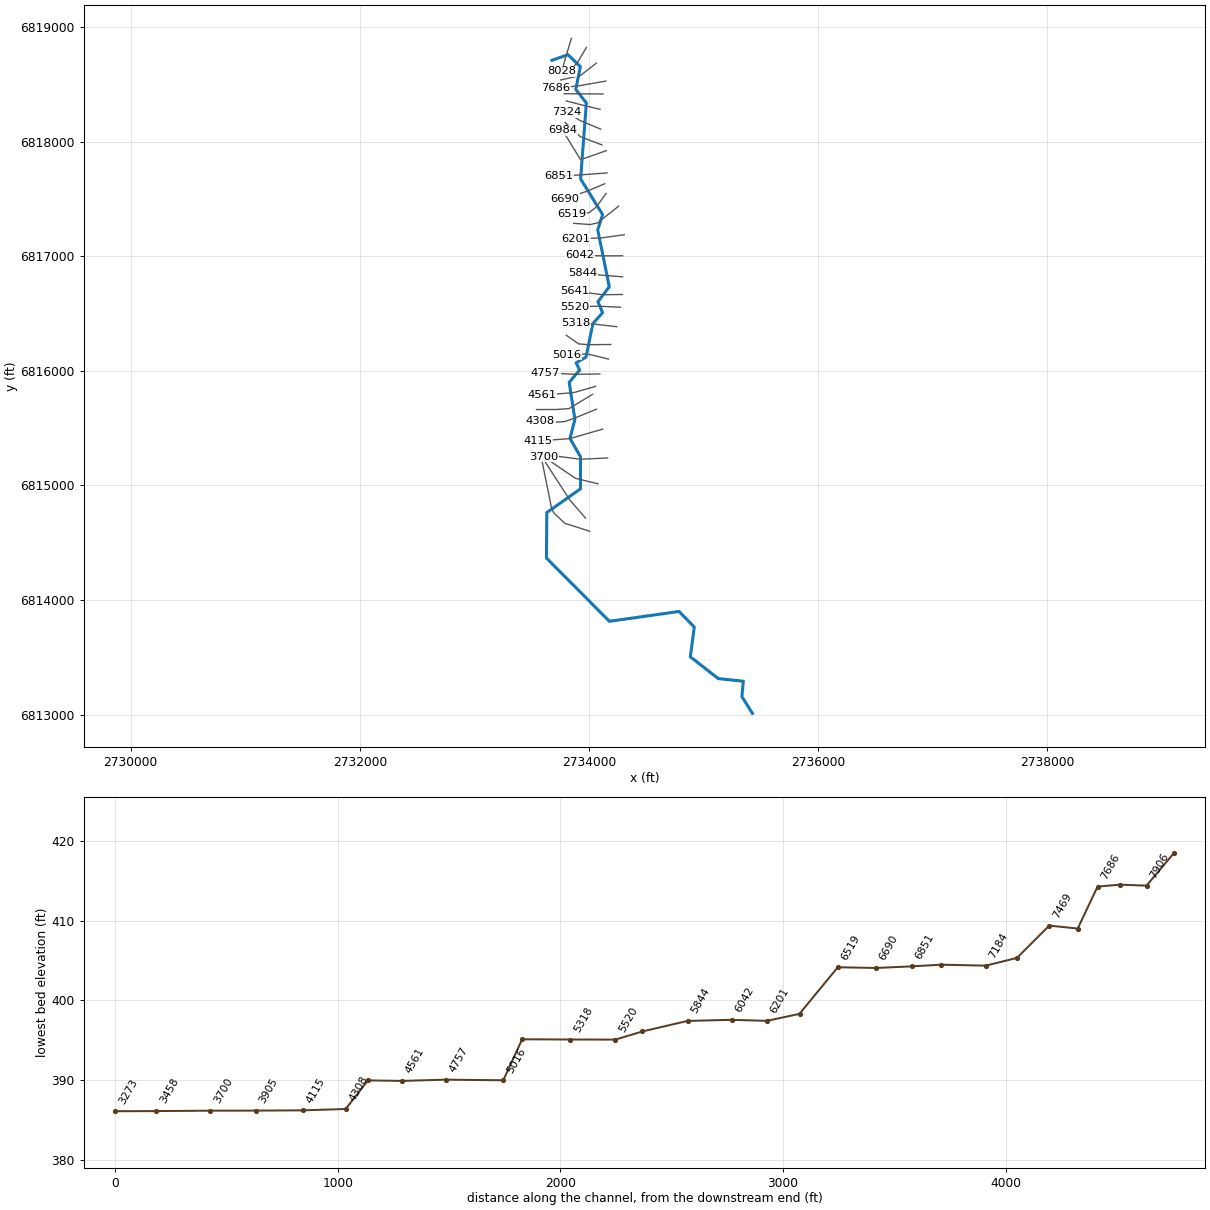
--- South Twin Creek Trib C.prj (project) ---

Proj Title=South Twin Creek Trib C Base Level Engineering
Current Plan=p01
Default Exp/Contr=0.3,0.1
English Units
Geom File=g01
Flow File=f01
Plan File=p01
BEGIN DESCRIPTION:
South Twin Creek Trib C
END DESCRIPTION:

--- South Twin Creek Trib C.p01 (plan) ---

Plan Title=Multiple Run
Short Identifier=Multiple
Geom File=g01
Flow File=f01
Subcritical Flow
K Sum by GR= 0
Std Step Tol= 0.01
Critical Tol= 0.01
Num of Std Step Trials= 20
Max Error Tol= 0.3
Flow Tol Ratio= 0.001
Split Flow NTrial= 30
Split Flow Tol= 0.02
Split Flow Ratio= 0.02
Log Output Level= 0
Friction Slope Method= 1
Unsteady Friction Slope Method= 2
Unsteady Bridges Friction Slope Method= 1
Parabolic Critical Depth
Global Vel Dist=  1 , 1 , 1
Global Log Level= 0
CheckData=True
Encroach Param= -1, 0, 0, 0
BEGIN DESCRIPTION:
Multiple Run
END DESCRIPTION:

--- South Twin Creek Trib C.f01 (steady flow) ---

Flow Title=Multiple
Number of Profiles=7
Profile Names=10-year,25-year,50-year,1pct_min,100-year,1pct_plu,500-year
River Rch & RM= South Twin Creek,Reach-1,8028
      62      70      76      41      82     164      95
River Rch & RM= South Twin Creek,Reach-1,6851
     308     394     461     268     535    1067     718
Boundary for River Rch & Prof#=South Twin Creek,Reach-1,1
Up Type=0
Dn Type=3
Dn Slope=0.005
Boundary for River Rch & Prof#=South Twin Creek,Reach-1,2
Up Type=0
Dn Type=3
Dn Slope=0.005
Boundary for River Rch & Prof#=South Twin Creek,Reach-1,3
Up Type=0
Dn Type=3
Dn Slope=0.005
Boundary for River Rch & Prof#=South Twin Creek,Reach-1,4
Up Type=0
Dn Type=3
Dn Slope=0.005
Boundary for River Rch & Prof#=South Twin Creek,Reach-1,5
Up Type=0
Dn Type=3
Dn Slope=0.005
Boundary for River Rch & Prof#=South Twin Creek,Reach-1,6
Up Type=0
Dn Type=3
Dn Slope=0.005
Boundary for River Rch & Prof#=South Twin Creek,Reach-1,7
Up Type=0
Dn Type=3
Dn Slope=0.005

--- South Twin Creek Trib C.g01 (geometry) ---

Geom Title=Existing Conditions

River Reach=South Twin Creek,Reach-1
Reach XY= 30
      2733676.00      6818711.00      2733816.41      6818759.82
      2733923.96      6818655.15      2733883.81      6818457.59
      2733976.47      6818338.24      2733926.29      6817676.12
      2734118.20      6817364.42      2734075.91      6817231.10
      2734176.47      6816733.77      2734077.67      6816604.95
      2734118.15      6816507.59      2734034.02      6816414.34
      2733972.79      6816119.34      2733887.17      6816071.29
      2733917.98      6816007.68      2733826.66      6815900.36
      2733876.47      6815576.16      2733833.53      6815410.99
      2733925.05      6815251.14      2733925.20      6814970.80
      2733631.34      6814763.74      2733628.06      6814366.85
      2734177.47      6813814.55      2734785.80      6813900.53
      2734918.21      6813764.42      2734883.80      6813504.79
      2735127.50      6813314.62      2735346.59      6813291.79
      2735333.81      6813157.60      2735426.00      6813011.00

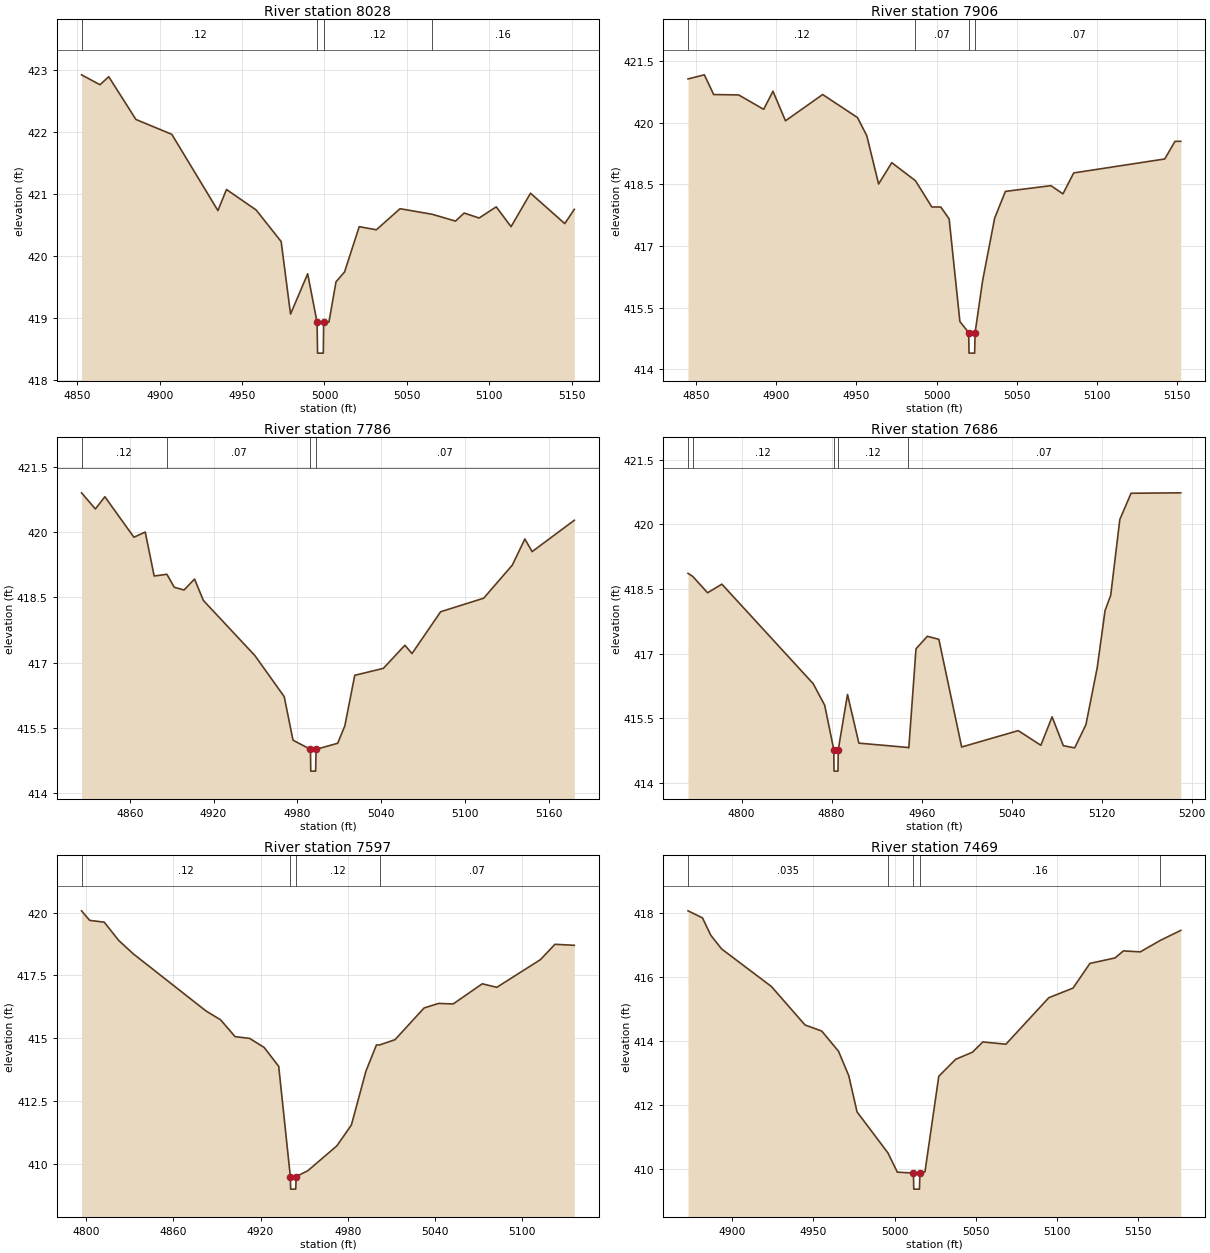
Type RM Length L Ch R = 1,8028,122,122,122
BEGIN DESCRIPTION:
South Twin Creek Trib C8027.662
END DESCRIPTION:
XS GIS Cut Line= 3
      2733845.46      6818902.60      2733803.34      6818761.24
      2733761.45      6818615.43
#Sta/Elev= 30
  4852.5  422.92  4863.7  422.76  4869.0  422.89  4885.5  422.20  4907.3  421.96
  4935.3  420.73  4940.5  421.07  4958.5  420.74  4973.7  420.23  4979.4  419.06
  4989.8  419.71  4995.5  418.93  4995.8  418.43  4999.3  418.43  4999.5  418.93
  5002.7  418.93  5007.0  419.58  5012.2  419.74  5021.1  420.47  5031.5  420.42
  5045.9  420.76  5065.4  420.67  5079.6  420.56  5084.8  420.69  5093.9  420.61
  5104.3  420.79  5113.3  420.47  5125.1  421.01  5145.9  420.52  5151.7  420.75
#Mann=4,-1,0
  4852.5    0.12       0  4995.5    0.07       0  4999.5    0.12       0
  5065.4    0.16       0
Bank Sta=4995.5,4999.5
Exp/Cntr=0.3,0.1

Type RM Length L Ch R = 1,7906,120,120,120
BEGIN DESCRIPTION:
South Twin Creek Trib C7905.92
END DESCRIPTION:
XS GIS Cut Line= 3
      2733977.04      6818823.28      2733897.89      6818689.84
      2733796.16      6818576.57
#Sta/Elev= 30
  4844.9  421.07  4855.1  421.17  4860.9  420.69  4876.5  420.68  4892.1  420.33
  4897.9  420.77  4905.7  420.05  4928.9  420.69  4950.6  420.13  4956.4  419.69
  4963.8  418.51  4972.0  419.03  4986.8  418.59  4997.0  417.95  5002.6  417.95
  5007.8  417.66  5014.5  415.16  5020.0  414.89  5020.2  414.39  5023.7  414.39
  5024.0  414.89  5028.7  416.16  5036.2  417.68  5042.9  418.33  5071.3  418.47
  5078.8  418.27  5085.5  418.78  5142.3  419.12  5148.7  419.55  5152.3  419.55
#Mann=4,-1,0
  4844.9    0.12       0  4986.8    0.07       0  5020.0    0.07       0
  5024.0    0.07       0
Bank Sta=5020,5024
Exp/Cntr=0.3,0.1

Type RM Length L Ch R = 1,7786,100,100,100
BEGIN DESCRIPTION:
South Twin Creek Trib C7785.65
END DESCRIPTION:
XS GIS Cut Line= 3
      2734063.76      6818686.59      2733925.94      6818578.58
      2733752.71      6818538.99
#Sta/Elev= 30
  4825.5  420.90  4835.4  420.53  4842.2  420.81  4863.0  419.88  4871.1  420.00
  4877.5  418.99  4886.6  419.03  4891.9  418.73  4898.9  418.67  4906.4  418.92
  4912.7  418.43  4949.7  417.16  4970.6  416.22  4976.9  415.22  4989.4  415.01
  4989.6  414.51  4993.1  414.51  4993.4  415.01  5008.9  415.15  5014.0  415.55
  5021.1  416.71  5041.6  416.87  5057.0  417.40  5062.1  417.21  5082.6  418.17
  5113.4  418.48  5133.9  419.24  5142.9  419.84  5148.1  419.55  5178.3  420.27
#Mann=4,-1,0
  4825.5    0.12       0  4886.6    0.07       0  4989.4    0.07       0
  4993.4    0.07       0
Bank Sta=4989.4,4993.4
Exp/Cntr=0.3,0.1

Type RM Length L Ch R = 1,7686,89,89,89
BEGIN DESCRIPTION:
South Twin Creek Trib C7685.89
END DESCRIPTION:
XS GIS Cut Line= 3
      2734145.67      6818529.43      2733892.43      6818485.36
      2733711.97      6818470.71
#Sta/Elev= 30
  4752.3  418.86  4756.5  418.79  4769.7  418.41  4782.4  418.61  4863.6  416.30
  4873.8  415.80  4881.9  414.77  4882.1  414.27  4885.6  414.27  4885.9  414.77
  4894.1  416.05  4904.2  414.92  4947.5  414.82  4948.6  414.81  4955.0  417.11
  4965.1  417.40  4975.3  417.33  4995.6  414.83  5045.9  415.21  5066.0  414.87
  5076.0  415.53  5086.0  414.86  5096.1  414.81  5106.1  415.35  5116.1  416.67
  5123.1  418.00  5128.1  418.35  5136.2  420.11  5146.2  420.72  5190.4  420.73
#Mann=5,-1,0
  4752.3   0.035       0  4756.5    0.12       0  4881.9    0.07       0
  4885.9    0.12       0  4947.5    0.07       0
Bank Sta=4881.9,4885.9
Exp/Cntr=0.3,0.1

Type RM Length L Ch R = 1,7597,128,128,128
BEGIN DESCRIPTION:
South Twin Creek Trib C7597.25
END DESCRIPTION:
XS GIS Cut Line= 3
      2734121.56      6818416.94      2733916.49      6818418.16
      2733782.67      6818419.33
#Sta/Elev= 30
  4796.9  420.07  4802.5  419.69  4812.5  419.62  4822.5  418.89  4832.5  418.36
  4882.5  416.09  4892.5  415.74  4902.5  415.07  4912.5  415.00  4922.5  414.64
  4932.5  413.89  4940.5  409.51  4940.7  409.01  4944.2  409.01  4944.5  409.51
  4952.5  409.74  4972.5  410.73  4982.5  411.56  4992.5  413.70  4999.7  414.74
  5001.9  414.74  5012.5  414.95  5032.5  416.21  5042.5  416.39  5052.5  416.37
  5072.5  417.17  5082.5  417.03  5112.5  418.13  5122.5  418.74  5135.8  418.70
#Mann=4,-1,0
  4796.9    0.12       0  4940.5    0.07       0  4944.5    0.12       0
  5001.9    0.07       0
Bank Sta=4940.5,4944.5
Exp/Cntr=0.3,0.1

Type RM Length L Ch R = 1,7469,145,145,145
BEGIN DESCRIPTION:
South Twin Creek Trib C7468.68
END DESCRIPTION:
XS GIS Cut Line= 3
      2734096.10      6818283.13      2733970.50      6818312.63
      2733801.84      6818356.13
#Sta/Elev= 30
  4872.9  418.06  4881.8  417.84  4886.9  417.30  4893.6  416.87  4924.2  415.70
  4944.9  414.50  4955.2  414.31  4965.5  413.68  4971.8  412.92  4976.9  411.79
  4995.9  410.51  5001.7  409.91  5011.6  409.88  5011.8  409.38  5015.3  409.38
  5015.6  409.88  5018.7  409.92  5027.2  412.90  5037.6  413.43  5047.9  413.65
  5054.3  413.97  5068.5  413.90  5094.9  415.35  5109.8  415.65  5120.2  416.42
  5135.6  416.59  5140.8  416.81  5151.2  416.78  5163.6  417.14  5176.1  417.45
#Mann=5,-1,0
  4872.9   0.035       0  4995.9    0.16       0  5011.6    0.07       0
  5015.6    0.16       0  5163.6    0.07       0
Bank Sta=5011.6,5015.6
Exp/Cntr=0.3,0.1

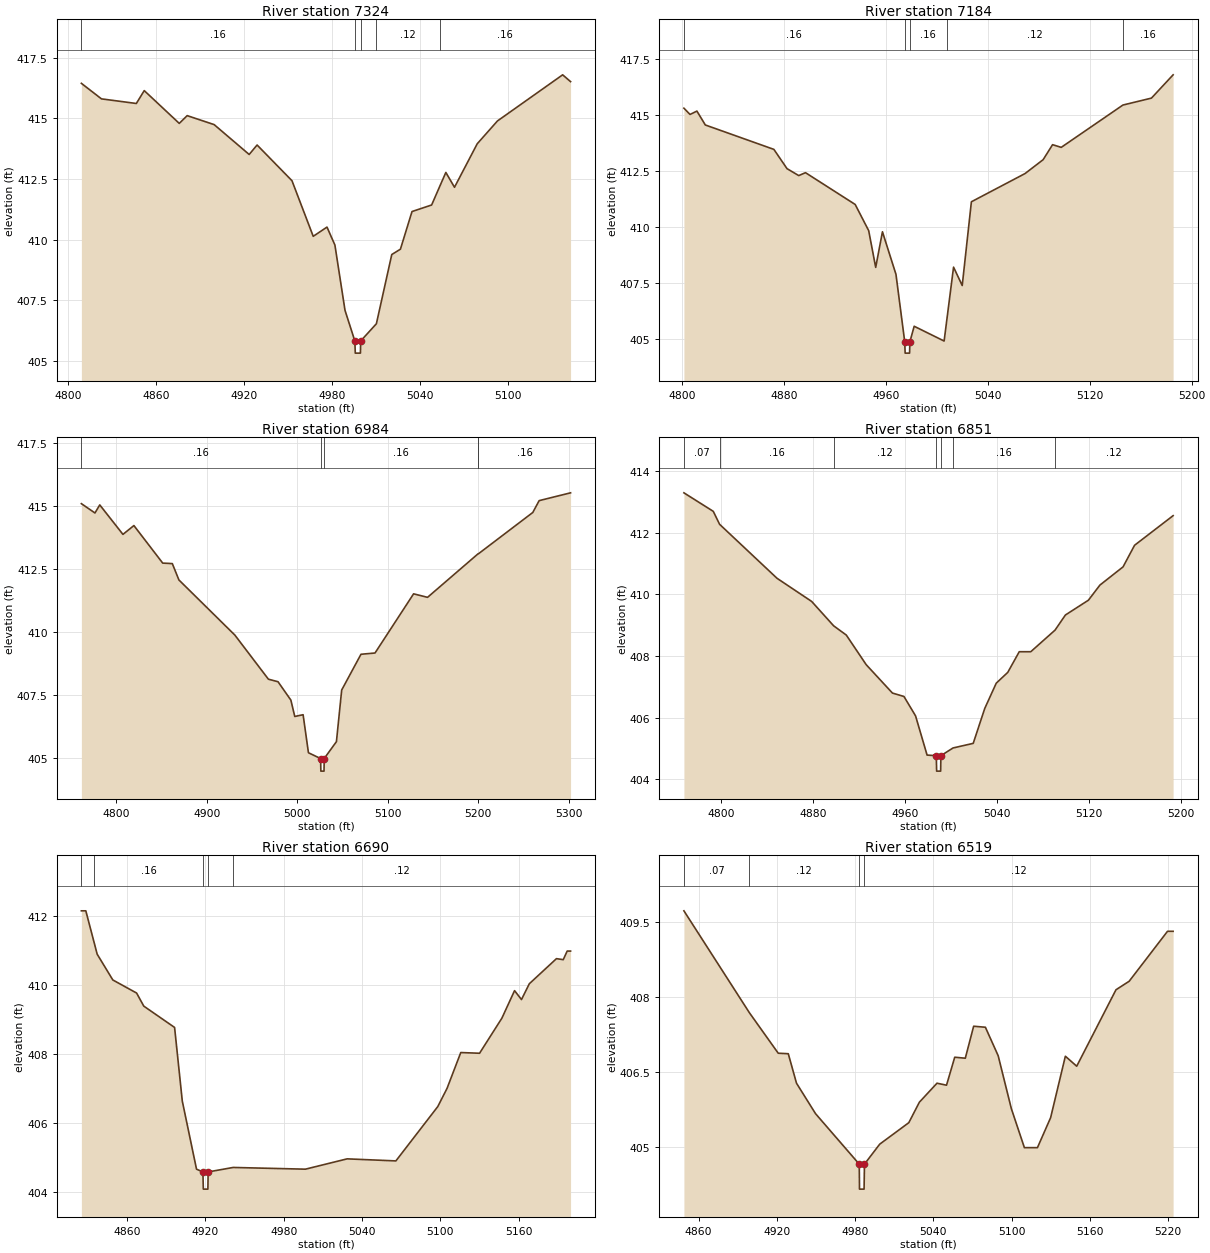
Type RM Length L Ch R = 1,7324,140,140,140
BEGIN DESCRIPTION:
South Twin Creek Trib C7324.09
END DESCRIPTION:
XS GIS Cut Line= 3
      2734102.05      6818110.09      2733924.84      6818183.83
      2733803.25      6818256.91
#Sta/Elev= 30
  4809.1  416.44  4822.8  415.80  4846.6  415.61  4852.0  416.14  4875.9  414.79
  4881.3  415.11  4899.7  414.74  4923.6  413.51  4929.0  413.90  4952.8  412.43
  4967.3  410.14  4976.7  410.52  4982.1  409.78  4989.0  407.09  4995.7  405.83
  4996.0  405.33  4999.5  405.33  4999.7  405.83  5010.4  406.54  5020.9  409.39
  5026.8  409.61  5034.7  411.16  5048.1  411.43  5053.8  412.22  5057.8  412.77
  5063.7  412.16  5079.2  413.95  5093.0  414.89  5137.5  416.79  5142.9  416.51
#Mann=5,-1,0
  4809.1    0.16       0  4995.7    0.07       0  4999.7    0.16       0
  5010.4    0.12       0  5053.8    0.16       0
Bank Sta=4995.7,4999.7
Exp/Cntr=0.3,0.1

Type RM Length L Ch R = 1,7184,200,200,200
BEGIN DESCRIPTION:
South Twin Creek Trib C7183.58
END DESCRIPTION:
XS GIS Cut Line= 3
      2734111.71      6817972.86      2733925.40      6818043.14
      2733790.09      6818168.97
#Sta/Elev= 30
  4801.5  415.30  4806.3  415.02  4811.7  415.17  4818.3  414.55  4872.1  413.46
  4882.4  412.60  4891.6  412.29  4896.9  412.42  4935.9  411.00  4946.5  409.83
  4952.0  408.19  4957.3  409.78  4967.9  407.88  4974.8  404.86  4975.1  404.36
  4978.6  404.36  4978.8  404.86  4982.2  405.56  5005.7  404.90  5007.8  405.84
  5013.1  408.20  5019.9  407.38  5027.1  411.12  5069.2  412.38  5083.4  413.00
  5090.8  413.67  5097.6  413.55  5146.0  415.44  5168.4  415.75  5185.4  416.79
#Mann=5,-1,0
  4801.5    0.16       0  4974.8    0.07       0  4978.8    0.16       0
  5007.8    0.12       0  5146.0    0.16       0
Bank Sta=4974.8,4978.8
Exp/Cntr=0.3,0.1

Type RM Length L Ch R = 1,6984,133,133,133
BEGIN DESCRIPTION:
South Twin Creek Trib C6983.747
END DESCRIPTION:
XS GIS Cut Line= 3
      2734150.64      6817922.60      2733926.00      6817843.09
      2733768.65      6818100.62
#Sta/Elev= 30
  4761.7  415.10  4776.7  414.73  4782.0  415.05  4807.6  413.88  4819.7  414.23
  4851.5  412.74  4862.1  412.72  4869.4  412.07  4931.2  409.88  4968.2  408.13
  4978.8  408.03  4993.0  407.30  4997.3  406.65  5006.5  406.72  5012.4  405.21
  5025.8  404.98  5026.1  404.48  5029.6  404.48  5029.8  404.98  5043.3  405.65
  5049.1  407.70  5070.4  409.12  5085.9  409.17  5128.5  411.52  5143.9  411.38
  5199.7  413.11  5200.1  413.11  5260.1  414.75  5267.1  415.22  5301.8  415.53
#Mann=5,-1,0
  4761.7    0.16       0  5025.8    0.07       0  5029.8    0.16       0
  5199.7    0.12       0  5200.1    0.16       0
Bank Sta=5025.8,5029.8
Exp/Cntr=0.3,0.1

Type RM Length L Ch R = 1,6851,161,161,161
BEGIN DESCRIPTION:
South Twin Creek Trib C6851.391
END DESCRIPTION:
XS GIS Cut Line= 3
      2734156.72      6817727.86      2733925.35      6817710.73
      2733732.52      6817700.53
#Sta/Elev= 30
  4768.0  413.29  4793.5  412.69  4799.0  412.27  4848.9  410.52  4879.0  409.77
  4898.1  408.98  4909.1  408.68  4926.4  407.72  4949.2  406.80  4959.2  406.69
  4969.3  406.06  4979.3  404.79  4987.3  404.77  4987.6  404.27  4991.1  404.27
  4991.3  404.77  5001.8  405.02  5019.4  405.17  5029.4  406.30  5039.4  407.12
  5049.4  407.47  5059.4  408.14  5069.4  408.14  5090.5  408.84  5099.5  409.33
  5119.5  409.81  5129.5  410.30  5149.6  410.89  5159.6  411.59  5193.1  412.55
#Mann=7,-1,0
  4768.0    0.07       0  4799.0    0.16       0  4898.1    0.12       0
  4987.3    0.07       0  4991.3    0.12       0  5001.8    0.16       0
  5090.5    0.12       0
Bank Sta=4987.3,4991.3
Exp/Cntr=0.3,0.1

Type RM Length L Ch R = 1,6690,171,171,171
BEGIN DESCRIPTION:
South Twin Creek Trib C6689.98
END DESCRIPTION:
XS GIS Cut Line= 3
      2734137.17      6817633.71      2733977.06      6817565.85
      2733785.96      6817504.20
#Sta/Elev= 30
  4825.0  412.16  4828.4  412.16  4834.9  411.22  4837.1  410.90  4849.1  410.15
  4867.3  409.77  4872.8  409.39  4896.4  408.77  4902.3  406.63  4913.2  404.65
  4918.1  404.57  4918.4  404.07  4921.9  404.07  4922.1  404.57  4941.3  404.70
  4996.6  404.65  5028.6  404.95  5065.9  404.89  5098.0  406.47  5105.1  407.00
  5115.6  408.04  5130.0  408.02  5147.1  409.04  5156.8  409.84  5162.1  409.58
  5168.1  410.04  5188.9  410.77  5194.1  410.74  5197.1  410.99  5199.7  410.99
#Mann=5,-1,0
  4825.0    0.07       0  4834.9    0.16       0  4918.1    0.07       0
  4922.1    0.16       0  4941.3    0.12       0
Bank Sta=4918.1,4922.1
Exp/Cntr=0.3,0.1

Type RM Length L Ch R = 1,6519,172,172,172
BEGIN DESCRIPTION:
South Twin Creek Trib C6519.4
END DESCRIPTION:
XS GIS Cut Line= 4
      2734149.46      6817549.13      2734059.72      6817427.53
      2734000.54      6817381.10      2733852.39      6817368.95
#Sta/Elev= 30
  4848.8  409.73  4899.0  407.69  4921.1  406.88  4928.8  406.87  4935.1  406.28
  4949.7  405.67  4983.2  404.66  4983.4  404.16  4986.9  404.16  4987.2  404.66
  4998.9  405.06  5021.2  405.49  5029.3  405.90  5042.8  406.28  5050.1  406.24
  5056.4  406.80  5064.5  406.78  5070.9  407.42  5079.9  407.40  5089.7  406.83
  5099.8  405.77  5109.8  404.99  5119.8  404.99  5129.9  405.59  5141.2  406.82
  5149.9  406.62  5180.0  408.15  5190.1  408.32  5219.5  409.32  5223.8  409.32
#Mann=4,-1,0
  4848.8    0.07       0  4899.0    0.12       0  4983.2    0.07       0
  4987.2    0.12       0
Bank Sta=4983.2,4987.2
Exp/Cntr=0.3,0.1

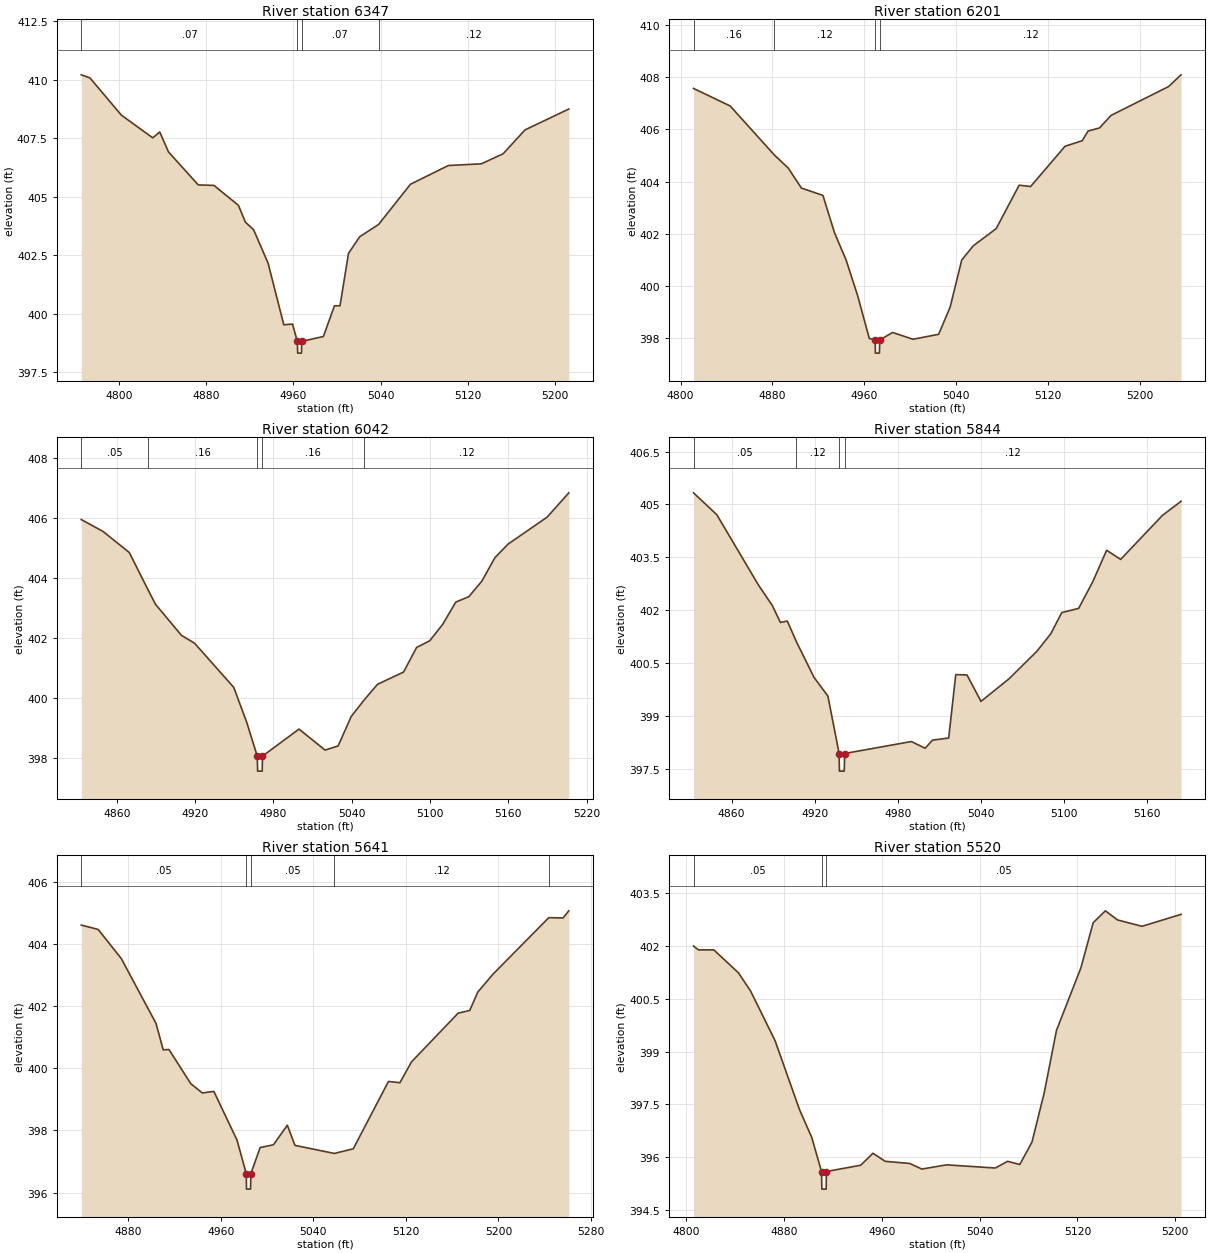
Type RM Length L Ch R = 1,6347,146,146,146
BEGIN DESCRIPTION:
South Twin Creek Trib C6347.2
END DESCRIPTION:
XS GIS Cut Line= 4
      2734259.37      6817439.16      2734076.13      6817292.83
      2734010.33      6817277.43      2733865.98      6817287.88
#Sta/Elev= 30
  4765.6  410.20  4773.5  410.07  4802.3  408.48  4831.1  407.51  4837.5  407.76
  4845.5  406.91  4872.8  405.50  4887.2  405.48  4909.6  404.63  4916.0  403.91
  4923.5  403.59  4936.8  402.16  4951.2  399.53  4959.2  399.56  4963.6  398.82
  4963.9  398.32  4967.4  398.32  4967.6  398.82  4987.5  399.03  4997.6  400.34
  5002.7  400.34  5010.5  402.58  5020.8  403.29  5038.0  403.81  5067.3  405.53
  5102.1  406.33  5132.2  406.40  5152.2  406.83  5172.3  407.85  5212.4  408.74
#Mann=4,-1,0
  4765.6    0.07       0  4963.6    0.07       0  4967.6    0.07       0
  5038.0    0.12       0
Bank Sta=4963.6,4967.6
Exp/Cntr=0.3,0.1

Type RM Length L Ch R = 1,6201,159,159,159
BEGIN DESCRIPTION:
South Twin Creek Trib C6201.18
END DESCRIPTION:
XS GIS Cut Line= 3
      2734307.63      6817188.62      2734115.68      6817161.58
      2733885.10      6817152.67
#Sta/Elev= 30
  4811.3  407.56  4843.2  406.89  4881.8  405.01  4893.7  404.52  4905.3  403.75
  4924.0  403.47  4934.1  402.04  4944.2  401.00  4954.3  399.63  4964.4  398.00
  4969.5  397.94  4969.7  397.44  4973.2  397.44  4973.5  397.94  4984.6  398.23
  5002.5  397.97  5024.8  398.16  5034.8  399.20  5044.9  401.00  5054.9  401.54
  5074.9  402.20  5094.9  403.86  5104.9  403.81  5134.9  405.35  5149.8  405.56
  5154.9  405.93  5164.9  406.05  5175.0  406.53  5225.0  407.63  5235.9  408.08
#Mann=4,-1,0
  4811.3    0.16       0  4881.8    0.12       0  4969.5    0.07       0
  4973.5    0.12       0
Bank Sta=4969.5,4973.5
Exp/Cntr=0.3,0.1

Type RM Length L Ch R = 1,6042,198,198,198
BEGIN DESCRIPTION:
South Twin Creek Trib C6042.21
END DESCRIPTION:
XS GIS Cut Line= 3
      2734292.83      6817004.70      2734120.87      6817004.10
      2733919.41      6817009.66
#Sta/Elev= 30
  4832.8  405.95  4849.6  405.55  4869.6  404.85  4883.7  403.63  4889.6  403.13
  4909.6  402.09  4919.6  401.83  4949.6  400.36  4959.6  399.19  4967.6  398.07
  4967.9  397.57  4971.4  397.57  4971.6  398.07  4999.6  398.97  5019.6  398.27
  5029.6  398.41  5039.6  399.39  5049.5  399.94  5059.7  400.46  5079.7  400.87
  5089.7  401.69  5099.7  401.91  5109.7  402.46  5119.7  403.20  5129.7  403.38
  5139.7  403.90  5149.7  404.68  5159.7  405.13  5189.7  406.03  5206.3  406.84
#Mann=5,-1,0
  4832.8    0.05       0  4883.7    0.16       0  4967.6    0.07       0
  4971.6    0.16       0  5049.5    0.12       0
Bank Sta=4967.6,4971.6
Exp/Cntr=0.3,0.1

Type RM Length L Ch R = 1,5844,203,203,203
BEGIN DESCRIPTION:
South Twin Creek Trib C5843.83
END DESCRIPTION:
XS GIS Cut Line= 3
      2734292.75      6816821.13      2734120.47      6816834.38
      2733942.68      6816856.07
#Sta/Elev= 30
  4832.5  405.33  4849.3  404.71  4879.4  402.71  4889.4  402.13  4895.2  401.65
  4900.2  401.69  4906.8  401.10  4919.5  400.09  4929.5  399.56  4937.6  397.93
  4937.8  397.43  4941.3  397.43  4941.6  397.93  4989.7  398.27  4999.7  398.08
  5005.0  398.31  5016.7  398.37  5021.8  400.17  5029.9  400.16  5040.0  399.41
  5060.2  400.05  5080.3  400.83  5090.4  401.33  5098.3  401.93  5110.5  402.05
  5120.6  402.80  5130.7  403.70  5140.8  403.44  5171.0  404.69  5184.4  405.09
#Mann=4,-1,0
  4832.5    0.05       0  4906.8    0.12       0  4937.6    0.07       0
  4941.6    0.12       0
Bank Sta=4937.6,4941.6
Exp/Cntr=0.3,0.1

Type RM Length L Ch R = 1,5641,121,121,121
BEGIN DESCRIPTION:
South Twin Creek Trib C5641.01
END DESCRIPTION:
XS GIS Cut Line= 3
      2734290.56      6816666.95      2734124.47      6816664.76
      2733870.99      6816695.13
#Sta/Elev= 30
  4839.4  404.62  4854.0  404.48  4874.0  403.54  4904.0  401.45  4910.2  400.60
  4915.2  400.61  4934.0  399.51  4944.0  399.21  4954.0  399.26  4974.0  397.69
  4982.0  396.61  4982.2  396.11  4985.7  396.11  4986.0  396.61  4994.0  397.45
  5005.5  397.54  5017.5  398.17  5024.1  397.52  5058.2  397.26  5074.5  397.41
  5104.9  399.58  5114.8  399.54  5124.8  400.21  5165.1  401.78  5175.2  401.87
  5182.1  402.46  5195.3  403.04  5243.5  404.86  5255.8  404.85  5260.8  405.08
#Mann=5,-1,0
  4839.4    0.05       0  4982.0    0.05       0  4986.0    0.05       0
  5058.2    0.12       0  5243.5    0.05       0
Bank Sta=4982,4986
Exp/Cntr=0.3,0.1

Type RM Length L Ch R = 1,5520,202,202,202
BEGIN DESCRIPTION:
South Twin Creek Trib C5520.3
END DESCRIPTION:
XS GIS Cut Line= 3
      2734272.62      6816555.69      2734079.78      6816564.99
      2733874.15      6816558.41
#Sta/Elev= 30
  4805.9  402.00  4809.9  401.89  4822.5  401.89  4842.6  401.24  4852.6  400.72
  4872.6  399.31  4892.6  397.35  4902.6  396.56  4910.6  395.59  4910.9  395.09
  4914.4  395.09  4914.6  395.59  4942.7  395.77  4952.7  396.11  4962.7  395.88
  4982.7  395.82  4992.7  395.66  5012.8  395.78  5052.8  395.69  5062.8  395.88
  5072.8  395.79  5082.8  396.43  5092.8  397.83  5102.8  399.60  5122.8  401.38
  5132.8  402.66  5142.8  403.00  5152.8  402.74  5172.8  402.56  5204.7  402.90
#Mann=3,-1,0
  4805.9    0.05       0  4910.6    0.05       0  4914.6    0.05       0
Bank Sta=4910.6,4914.6
Exp/Cntr=0.3,0.1

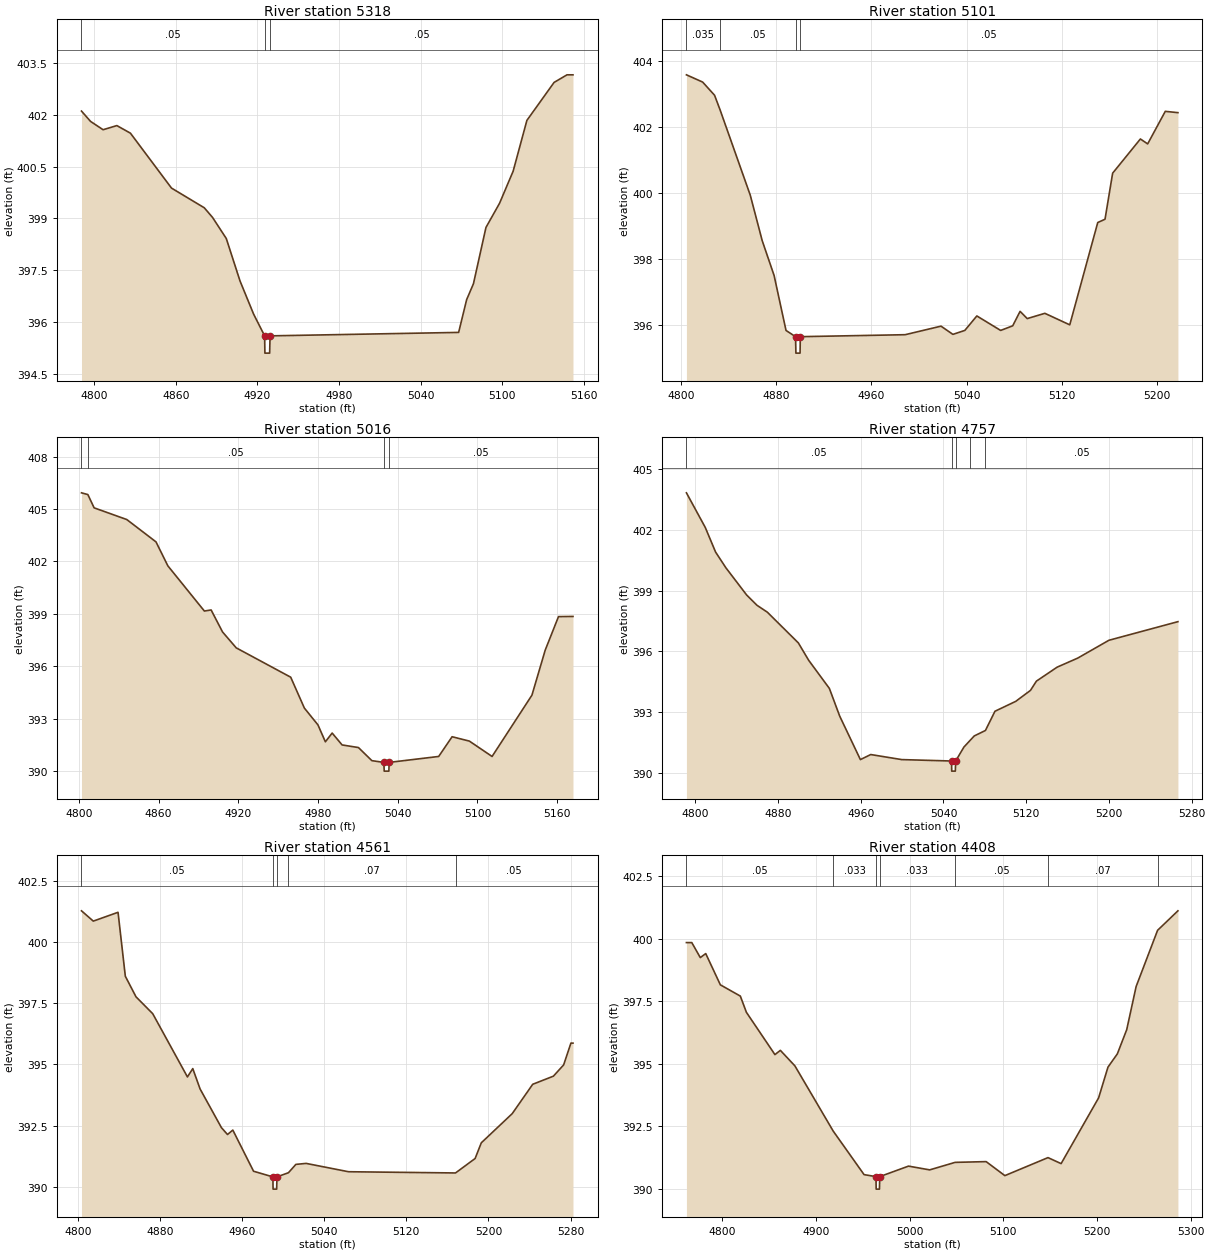
Type RM Length L Ch R = 1,5318,217,217,217
BEGIN DESCRIPTION:
South Twin Creek Trib C5317.95
END DESCRIPTION:
XS GIS Cut Line= 3
      2734241.78      6816385.71      2734031.00      6816410.17
      2733882.19      6816422.25
#Sta/Elev= 25
  4790.6  402.11  4797.3  401.81  4806.5  401.57  4816.6  401.69  4826.6  401.47
  4856.8  399.88  4880.9  399.31  4887.0  399.03  4897.1  398.42  4907.2  397.19
  4917.2  396.23  4925.3  395.60  4925.5  395.10  4929.0  395.10  4929.3  395.60
  5068.0  395.70  5073.9  396.65  5078.9  397.11  5088.1  398.74  5098.1  399.44
  5108.1  400.37  5118.2  401.84  5138.2  402.94  5147.7  403.16  5152.1  403.16
#Mann=3,-1,0
  4790.6    0.05       0  4925.3    0.05       0  4929.3    0.05       0
Bank Sta=4925.3,4929.3
Exp/Cntr=0.3,0.1

Type RM Length L Ch R = 1,5101,85,85,85
BEGIN DESCRIPTION:
South Twin Creek Trib C5101.15
END DESCRIPTION:
XS GIS Cut Line= 4
      2734189.62      6816230.35      2733989.70      6816229.09
      2733908.68      6816235.84      2733801.08      6816311.21
#Sta/Elev= 30
  4804.7  403.59  4818.3  403.37  4828.3  402.97  4832.9  402.53  4858.3  399.93
  4868.3  398.55  4878.3  397.49  4888.3  395.82  4896.3  395.63  4896.6  395.13
  4900.1  395.13  4900.3  395.63  4988.3  395.69  5018.4  395.95  5028.4  395.70
  5038.4  395.82  5048.5  396.26  5068.5  395.82  5078.6  395.96  5084.8  396.40
  5090.8  396.18  5105.6  396.34  5126.5  395.99  5150.0  399.10  5156.1  399.20
  5162.5  400.60  5185.8  401.64  5191.9  401.49  5206.7  402.48  5217.3  402.44
#Mann=4,-1,0
  4804.7   0.035       0  4832.9    0.05       0  4896.3    0.05       0
  4900.3    0.05       0
Bank Sta=4896.3,4900.3
Exp/Cntr=0.3,0.1

Type RM Length L Ch R = 1,5016,259,259,259
BEGIN DESCRIPTION:
South Twin Creek Trib C5015.66
END DESCRIPTION:
XS GIS Cut Line= 5
      2734169.10      6816103.44      2734034.51      6816136.63
      2733975.41      6816149.09      2733883.05      6816138.26
      2733805.08      6816139.88
#Sta/Elev= 30
  4801.9  405.93  4806.7  405.83  4811.4  405.07  4836.0  404.40  4858.0  403.12
  4866.9  401.75  4894.4  399.16  4899.5  399.22  4908.1  397.96  4918.4  397.05
  4959.4  395.37  4969.7  393.60  4979.9  392.64  4985.5  391.67  4990.6  392.17
  4998.1  391.49  5010.4  391.34  5020.5  390.59  5029.5  390.49  5029.8  389.99
  5033.3  389.99  5033.5  390.49  5070.8  390.83  5080.9  391.96  5093.9  391.71
  5111.0  390.83  5141.0  394.34  5151.0  396.92  5161.0  398.84  5171.9  398.85
#Mann=4,-1,0
  4801.9   0.035       0  4806.7    0.05       0  5029.5    0.05       0
  5033.5    0.05       0
Bank Sta=5029.5,5033.5
Exp/Cntr=0.3,0.1

Type RM Length L Ch R = 1,4757,196,196,196
BEGIN DESCRIPTION:
South Twin Creek Trib C4756.92
END DESCRIPTION:
XS GIS Cut Line= 3
      2734094.20      6815973.52      2733881.13      6815970.23
      2733619.34      6815982.98
#Sta/Elev= 30
  4791.5  403.83  4809.7  402.12  4819.7  400.90  4829.7  400.12  4849.7  398.78
  4859.7  398.27  4869.7  397.93  4899.7  396.41  4909.7  395.55  4929.7  394.16
  4939.7  392.79  4959.7  390.64  4969.7  390.89  4999.7  390.64  5047.8  390.57
  5048.0  390.07  5051.5  390.07  5051.8  390.57  5059.8  391.26  5065.6  391.58
  5069.8  391.81  5080.6  392.08  5089.8  393.03  5109.9  393.52  5124.1  394.06
  5129.9  394.52  5149.9  395.21  5169.9  395.66  5200.0  396.54  5266.7  397.46
#Mann=5,-1,0
  4791.5    0.05       0  5047.8    0.05       0  5051.8    0.05       0
  5065.6    0.07       0  5080.6    0.05       0
Bank Sta=5047.8,5051.8
Exp/Cntr=0.3,0.1

Type RM Length L Ch R = 1,4561,153,153,153
BEGIN DESCRIPTION:
South Twin Creek Trib C4560.69
END DESCRIPTION:
XS GIS Cut Line= 3
      2734057.09      6815865.28      2733865.79      6815810.54
      2733586.94      6815788.37
#Sta/Elev= 30
  4803.7  401.27  4815.2  400.85  4839.3  401.21  4846.4  398.60  4856.8  397.76
  4873.1  397.07  4906.9  394.49  4912.1  394.83  4919.2  394.00  4940.0  392.42
  4945.9  392.14  4951.1  392.32  4971.3  390.64  4990.1  390.41  4990.3  389.91
  4993.8  389.91  4994.1  390.41  5005.3  390.58  5012.5  390.92  5022.5  390.96
  5063.8  390.62  5168.0  390.57  5187.1  391.16  5193.1  391.80  5223.2  392.99
  5243.2  394.19  5263.3  394.52  5273.3  394.98  5280.4  395.87  5282.4  395.87
#Mann=5,-1,0
  4803.7    0.05       0  4990.1    0.05       0  4994.1    0.05       0
  5005.3    0.07       0  5168.0    0.05       0
Bank Sta=4990.1,4994.1
Exp/Cntr=0.3,0.1

Type RM Length L Ch R = 1,4408,100,100,100
BEGIN DESCRIPTION:
South Twin Creek Trib C4407.52
END DESCRIPTION:
XS GIS Cut Line= 5
      2734030.80      6815795.38      2733881.50      6815705.27
      2733824.97      6815671.03      2733719.30      6815663.35
      2733541.43      6815662.61
#Sta/Elev= 30
  4761.9  399.84  4767.6  399.84  4776.7  399.24  4782.5  399.40  4798.1  398.15
  4819.4  397.70  4825.9  397.05  4856.3  395.36  4862.1  395.53  4877.6  394.91
  4918.5  392.30  4951.4  390.56  4964.1  390.48  4964.3  389.98  4967.8  389.98
  4968.1  390.48  4998.8  390.90  5021.4  390.75  5048.5  391.05  5081.6  391.08
  5101.6  390.52  5147.6  391.24  5161.6  391.00  5201.6  393.63  5211.6  394.86
  5221.6  395.39  5231.6  396.36  5241.6  398.08  5264.5  400.33  5286.2  401.11
#Mann=7,-1,0
  4761.9    0.05       0  4918.5   0.033       0  4964.1   0.033       0
  4968.1   0.033       0  5048.5    0.05       0  5147.6    0.07       0
  5264.5    0.05       0
Bank Sta=4964.1,4968.1
Exp/Cntr=0.3,0.1

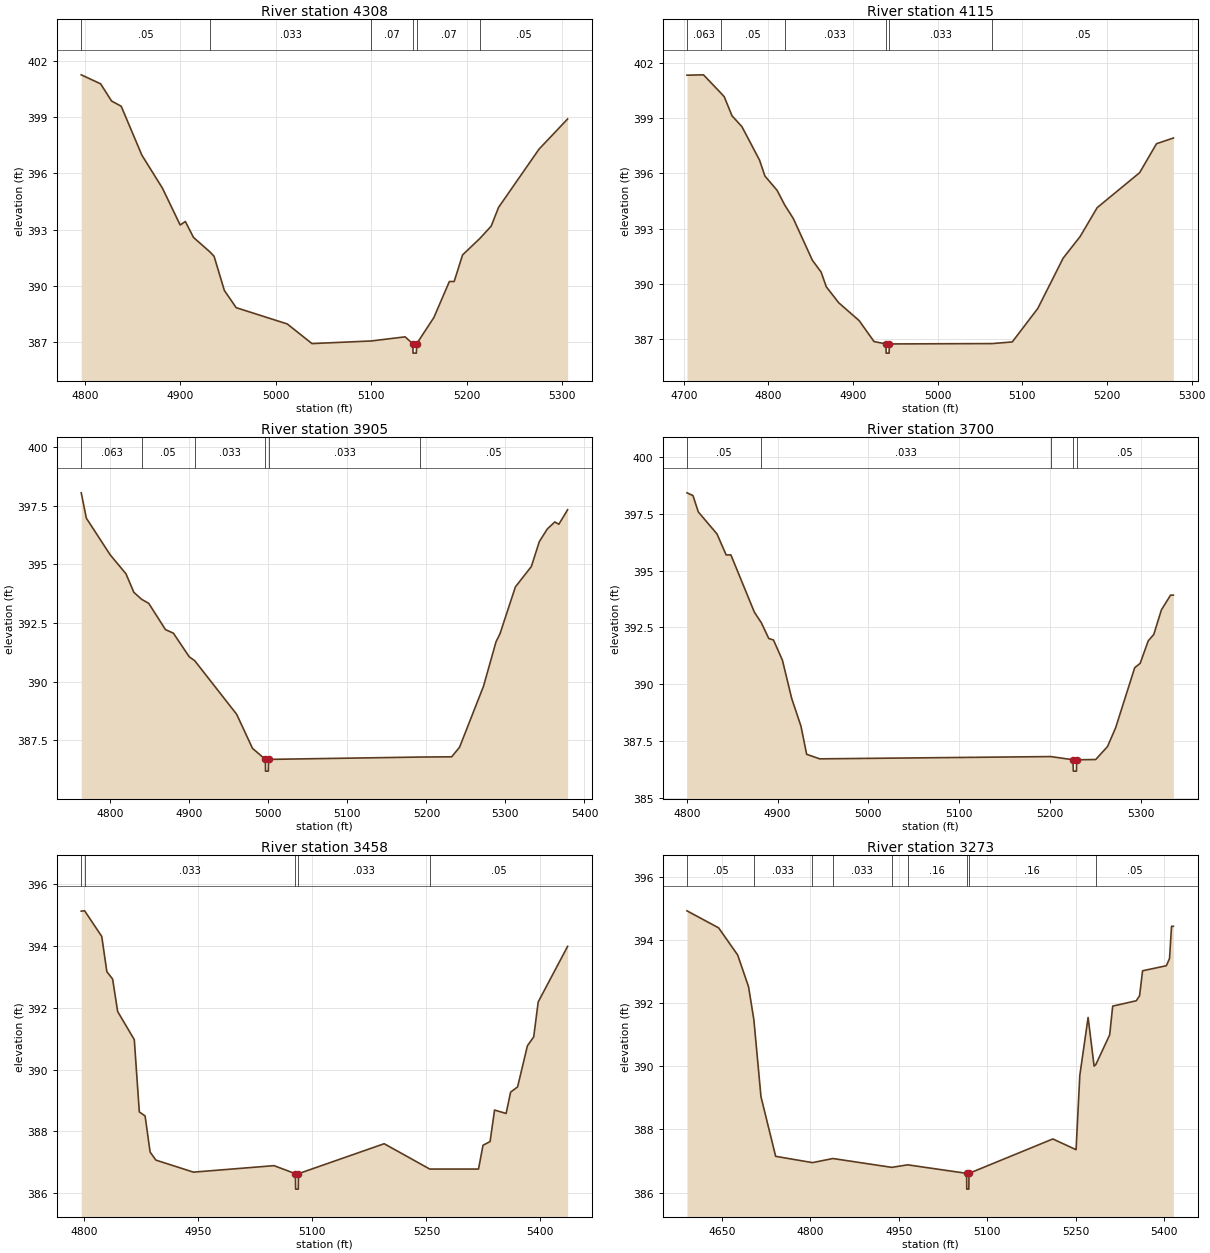
Type RM Length L Ch R = 1,4308,193,193,193
BEGIN DESCRIPTION:
South Twin Creek Trib C4307.91
END DESCRIPTION:
XS GIS Cut Line= 5
      2734064.75      6815666.31      2733872.52      6815587.30
      2733786.48      6815557.56      2733698.40      6815552.02
      2733576.18      6815561.26
#Sta/Elev= 30
  4796.0  401.27  4816.3  400.79  4827.8  399.87  4837.9  399.59  4859.5  396.98
  4881.1  395.21  4899.7  393.24  4905.1  393.43  4913.6  392.58  4930.9  391.80
  4935.2  391.57  4946.0  389.74  4958.4  388.82  5011.9  387.95  5037.8  386.90
  5099.8  387.04  5135.4  387.26  5143.5  386.89  5143.7  386.39  5147.2  386.39
  5147.5  386.89  5165.5  388.29  5181.8  390.22  5186.8  390.22  5195.6  391.64
  5213.9  392.53  5225.6  393.18  5233.3  394.18  5275.8  397.30  5305.7  398.91
#Mann=6,-1,0
  4796.0    0.05       0  4930.9   0.033       0  5099.8    0.07       0
  5143.5   0.033       0  5147.5    0.07       0  5213.9    0.05       0
Bank Sta=5143.5,5147.5
Exp/Cntr=0.3,0.1

Type RM Length L Ch R = 1,4115,210,210,210
BEGIN DESCRIPTION:
South Twin Creek Trib C4114.82
END DESCRIPTION:
XS GIS Cut Line= 3
      2734118.32      6815491.84      2733830.67      6815408.86
      2733556.20      6815388.53
#Sta/Elev= 30
  4703.8  401.35  4723.3  401.37  4743.4  400.40  4747.8  400.18  4757.0  399.14
  4768.7  398.55  4789.5  396.73  4795.9  395.86  4810.3  395.08  4819.2  394.29
  4829.5  393.54  4851.9  391.28  4862.3  390.63  4868.4  389.83  4883.1  388.96
  4907.2  387.99  4924.8  386.85  4938.9  386.72  4939.1  386.22  4942.6  386.22
  4942.9  386.72  5064.5  386.74  5088.1  386.83  5118.2  388.65  5148.2  391.39
  5168.3  392.57  5188.4  394.14  5238.5  396.04  5258.5  397.62  5278.4  397.93
#Mann=6,-1,0
  4703.8   0.063       0  4743.4    0.05       0  4819.2   0.033       0
  4938.9   0.033       0  4942.9   0.033       0  5064.5    0.05       0
Bank Sta=4938.9,4942.9
Exp/Cntr=0.3,0.1

Type RM Length L Ch R = 1,3905,205,205,205
BEGIN DESCRIPTION:
South Twin Creek Trib C3904.55
END DESCRIPTION:
XS GIS Cut Line= 3
      2734162.52      6815240.05      2733924.59      6815229.24
      2733550.46      6815277.49
#Sta/Elev= 30
  4763.3  398.05  4769.8  396.97  4799.9  395.41  4819.9  394.60  4829.9  393.81
  4839.8  393.51  4848.7  393.34  4869.9  392.22  4879.9  392.07  4900.0  391.06
  4906.8  390.90  4960.0  388.61  4980.0  387.16  4996.3  386.69  4996.5  386.19
  5000.0  386.19  5000.3  386.69  5192.4  386.79  5232.0  386.80  5242.0  387.21
  5272.3  389.81  5288.1  391.70  5293.2  392.05  5312.6  394.04  5332.8  394.91
  5342.9  395.97  5353.0  396.51  5362.5  396.81  5367.6  396.71  5378.7  397.33
#Mann=6,-1,0
  4763.3   0.063       0  4839.8    0.05       0  4906.8   0.033       0
  4996.3   0.033       0  5000.3   0.033       0  5192.4    0.05       0
Bank Sta=4996.3,5000.3
Exp/Cntr=0.3,0.1

Type RM Length L Ch R = 1,3700,242,242,242
BEGIN DESCRIPTION:
South Twin Creek Trib C3699.56
END DESCRIPTION:
XS GIS Cut Line= 3
      2734078.19      6815014.65      2733882.96      6815062.00
      2733605.05      6815249.43
#Sta/Elev= 30
  4800.1  398.42  4806.7  398.30  4812.6  397.58  4833.2  396.61  4843.3  395.69
  4848.5  395.69  4874.4  393.17  4882.0  392.71  4890.3  392.01  4895.4  391.95
  4905.3  391.06  4915.5  389.38  4925.8  388.15  4932.0  386.92  4946.4  386.72
  5201.1  386.82  5225.6  386.68  5225.9  386.18  5229.4  386.18  5229.6  386.68
  5250.6  386.69  5263.6  387.26  5272.6  388.09  5293.6  390.73  5299.6  390.92
  5308.5  391.91  5314.6  392.19  5323.0  393.27  5333.1  393.92  5336.2  393.92
#Mann=5,-1,0
  4800.1    0.05       0  4882.0   0.033       0  5201.1    0.05       0
  5225.6   0.033       0  5229.6    0.05       0
Bank Sta=5225.6,5229.6
Exp/Cntr=0.3,0.1

Type RM Length L Ch R = 1,3458,185,185,185
BEGIN DESCRIPTION:
South Twin Creek Trib C3457.7
END DESCRIPTION:
XS GIS Cut Line= 3
      2733969.04      6814715.95      2733831.53      6814873.76
      2733598.03      6815235.42
#Sta/Elev= 30
  4796.0  395.13  4800.5  395.14  4823.0  394.31  4829.7  393.17  4837.3  392.93
  4843.9  391.88  4865.8  390.97  4872.4  388.63  4880.0  388.50  4886.6  387.33
  4894.2  387.07  4943.6  386.68  5049.6  386.89  5077.7  386.63  5078.0  386.13
  5081.5  386.13  5081.7  386.63  5194.5  387.60  5254.4  386.78  5318.6  386.78
  5324.5  387.55  5333.8  387.67  5339.7  388.69  5354.9  388.58  5360.8  389.27
  5370.0  389.44  5382.9  390.77  5391.2  391.06  5397.1  392.19  5435.8  393.99
#Mann=5,-1,0
  4796.0    0.05       0  4800.5   0.033       0  5077.7   0.033       0
  5081.7   0.033       0  5254.4    0.05       0
Bank Sta=5077.7,5081.7
Exp/Cntr=0.3,0.1

Type RM Length L Ch R = 1,3273,38,38,38
BEGIN DESCRIPTION:
South Twin Creek Trib C3272.62
END DESCRIPTION:
XS GIS Cut Line= 5
      2734005.60      6814600.77      2733787.82      6814670.11
      2733690.06      6814763.05      2733671.32      6814809.37
      2733589.76      6815212.70
#Sta/Elev= 30
  4590.9  394.93  4644.6  394.39  4676.9  393.53  4695.4  392.52  4704.4  391.47
  4716.4  389.04  4741.3  387.15  4803.7  386.95  4838.4  387.08  4938.2  386.80
  4965.2  386.88  5065.2  386.61  5065.4  386.11  5068.9  386.11  5069.2  386.61
  5211.4  387.70  5250.8  387.36  5257.1  389.71  5271.2  391.55  5281.4  390.01
  5284.1  390.05  5307.8  391.00  5312.9  391.91  5352.9  392.08  5358.5  392.24
  5363.6  393.03  5403.9  393.19  5409.3  393.42  5412.7  394.44  5415.8  394.44
#Mann=9,-1,0
  4590.9    0.05       0  4704.4   0.033       0  4803.7    0.05       0
  4838.4   0.033       0  4938.2    0.05       0  4965.2    0.16       0
  5065.2    0.07       0  5069.2    0.16       0  5284.1    0.05       0
Bank Sta=5065.2,5069.2
Exp/Cntr=0.3,0.1