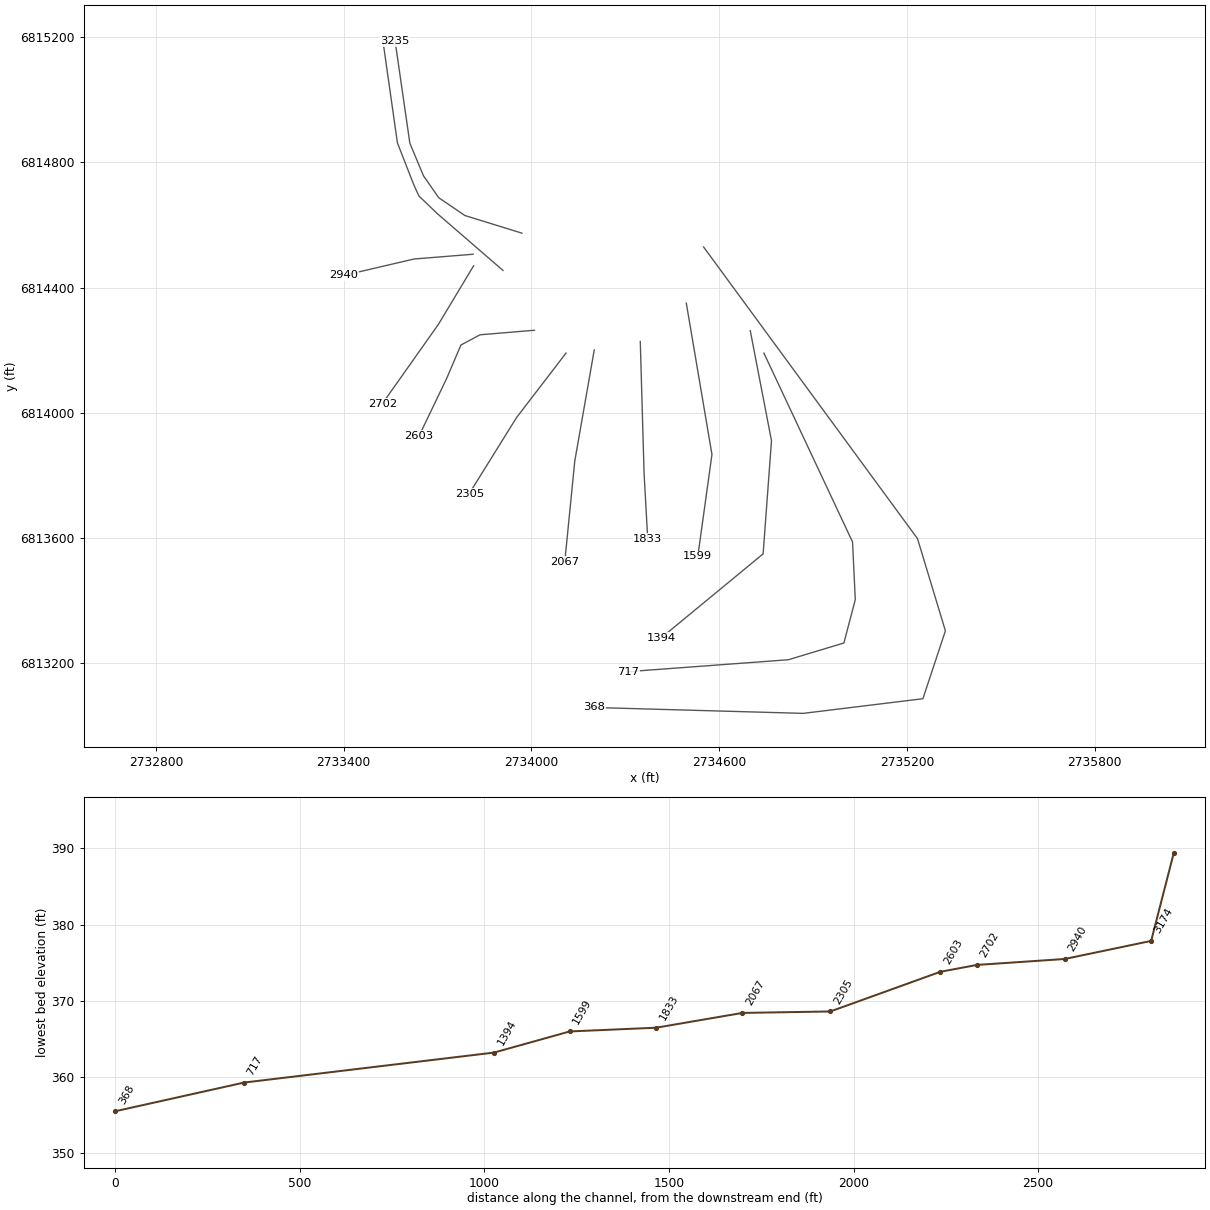
HEC-RAS study South Twin Creek Trib C.prj: South Twin Creek Trib C Base Level Engineering

--- South Twin Creek Trib C.g01 (geometry) --- (continued)

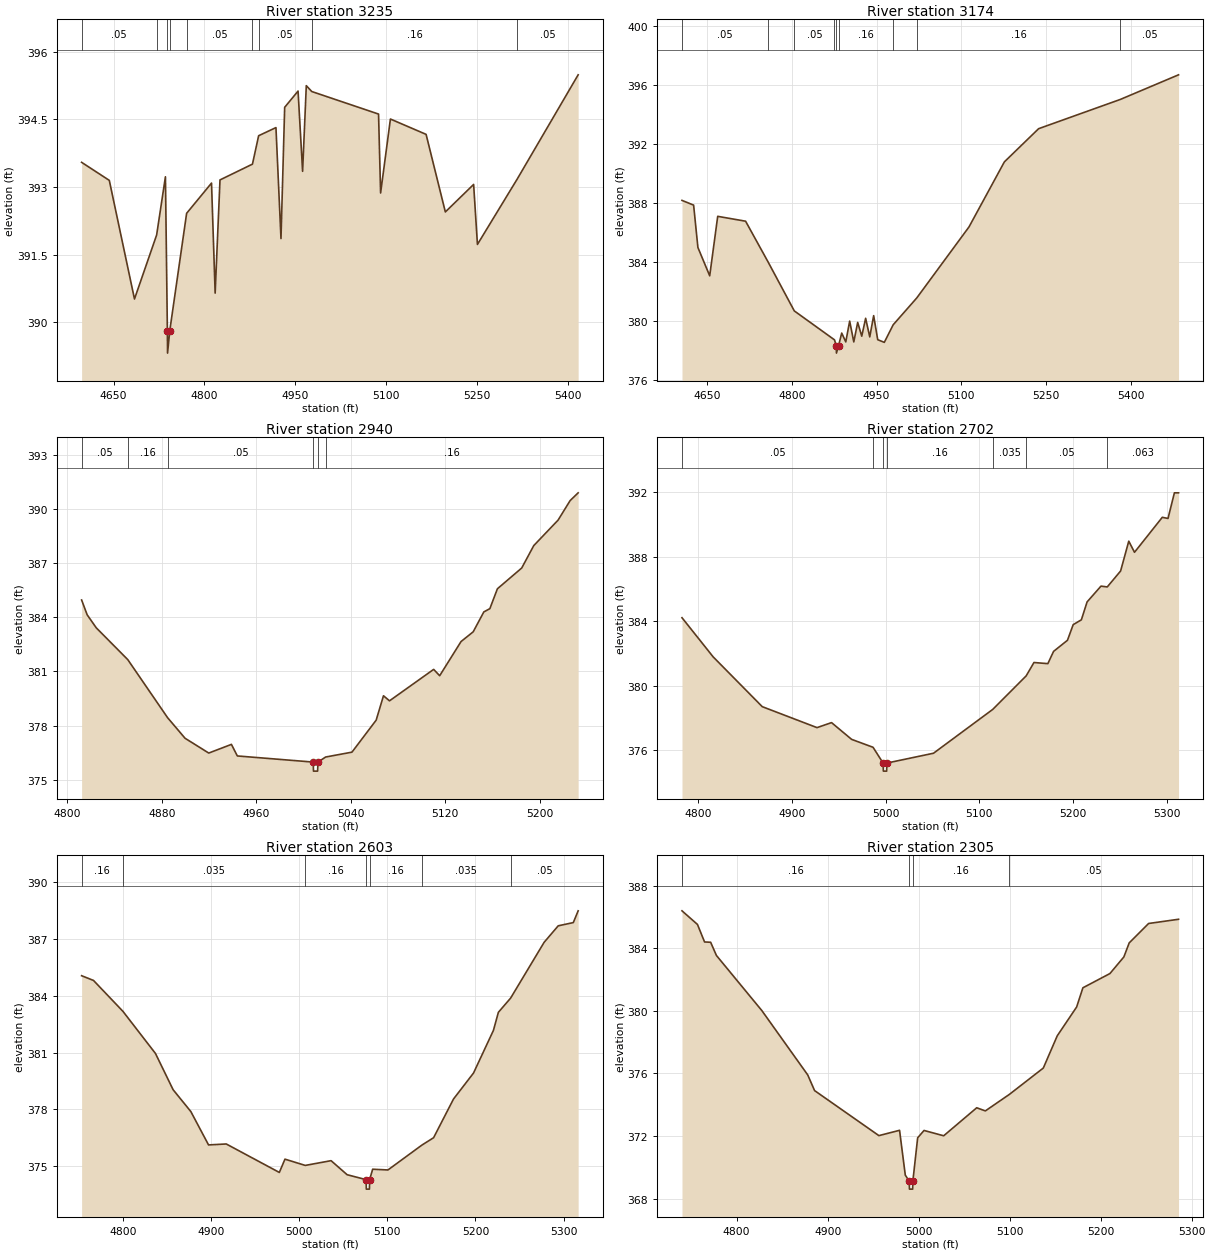
Type RM Length L Ch R = 1,3235,61,61,61
BEGIN DESCRIPTION:
South Twin Creek Trib C3234.54
END DESCRIPTION:
XS GIS Cut Line= 6
      2733969.42      6814573.96      2733787.29      6814630.26
      2733703.61      6814687.17      2733654.91      6814757.02
      2733611.28      6814861.63      2733564.14      6815187.75
#Sta/Elev= 30
  4597.3  393.55  4643.0  393.15  4684.6  390.52  4721.2  391.94  4735.7  393.23
  4738.9  389.82  4739.2  389.32  4742.9  389.82  4770.7  392.42  4811.8  393.09
  4817.8  390.65  4825.8  393.16  4879.4  393.51  4889.6  394.14  4918.2  394.32
  4926.5  391.86  4932.6  394.77  4954.7  395.13  4962.2  393.35  4968.3  395.25
  4977.3  395.12  5087.6  394.62  5091.0  392.87  5107.2  394.51  5166.1  394.17
  5197.9  392.45  5244.6  393.06  5250.9  391.73  5316.6  393.18  5417.2  395.49
#Mann=9,-1,0
  4597.3    0.05       0  4721.2   0.033       0  4738.9    0.07       0
  4742.9   0.033       0  4770.7    0.05       0  4879.4   0.033       0
  4889.6    0.05       0  4977.3    0.16       0  5316.6    0.05       0
Bank Sta=4738.9,4742.9
Exp/Cntr=0.3,0.1

Type RM Length L Ch R = 1,3174,234,234,234
BEGIN DESCRIPTION:
South Twin Creek Trib C3173.94
END DESCRIPTION:
XS GIS Cut Line= 6
      2733909.08      6814454.74      2733700.43      6814635.14
      2733640.26      6814692.60      2733623.20      6814730.30
      2733571.56      6814862.43      2733524.06      6815196.59
#Sta/Elev= 30
  4605.2  388.20  4625.8  387.88  4633.4  385.01  4654.3  383.09  4668.5  387.12
  4717.9  386.79  4758.3  383.99  4804.2  380.71  4875.4  378.75  4878.6  378.35
  4878.9  377.85  4882.6  378.35  4888.2  379.21  4895.4  378.61  4902.3  380.02
  4909.6  378.61  4916.5  379.93  4923.7  379.00  4930.6  380.21  4937.9  378.95
  4944.8  380.39  4952.0  378.76  4963.7  378.58  4979.4  379.77  5021.2  381.59
  5113.7  386.40  5176.4  390.81  5237.1  393.06  5381.7  395.04  5485.0  396.71
#Mann=9,-1,0
  4605.2    0.05       0  4758.3    0.16       0  4804.2    0.05       0
  4875.4    0.16       0  4878.6    0.05       0  4882.6    0.16       0
  4979.4    0.05       0  5021.2    0.16       0  5381.7    0.05       0
Bank Sta=4878.6,4882.6
Exp/Cntr=0.3,0.1

Type RM Length L Ch R = 1,2940,238,238,238
BEGIN DESCRIPTION:
Mapping XS ebaf7101
END DESCRIPTION:
XS GIS Cut Line= 3
      2733813.34      6814506.57      2733624.45      6814491.29
      2733399.42      6814438.70
#Sta/Elev= 30
  4812.0  384.95  4816.7  384.13  4824.4  383.41  4851.1  381.65  4884.8  378.44
  4899.6  377.30  4919.7  376.48  4938.9  376.96  4943.9  376.32  5008.2  375.98
  5008.4  375.48  5011.9  375.48  5012.2  375.98  5018.7  376.26  5041.0  376.53
  5061.5  378.30  5067.7  379.65  5072.8  379.37  5110.2  381.11  5115.3  380.76
  5133.4  382.65  5143.7  383.19  5152.7  384.29  5157.8  384.47  5164.2  385.57
  5184.8  386.72  5195.0  387.96  5215.6  389.37  5225.8  390.45  5232.6  390.88
#Mann=6,-1,0
  4812.0    0.05       0  4851.1    0.16       0  4884.8    0.05       0
  5008.2    0.05       0  5012.2    0.05       0  5018.7    0.16       0
Bank Sta=5008.2,5012.2
Exp/Cntr=0.3,0.1

Type RM Length L Ch R = 1,2702,99,99,99
BEGIN DESCRIPTION:
South Twin Creek Trib C2702.49
END DESCRIPTION:
XS GIS Cut Line= 3
      2733814.97      6814469.46      2733702.48      6814282.34
      2733523.21      6814028.74
#Sta/Elev= 30
  4783.2  384.22  4816.4  381.79  4868.7  378.70  4927.0  377.40  4942.5  377.71
  4963.9  376.67  4986.7  376.18  4997.4  375.20  4997.7  374.70  5001.2  374.70
  5001.4  375.20  5051.1  375.81  5114.2  378.53  5149.8  380.61  5158.1  381.44
  5172.9  381.37  5179.0  382.13  5193.8  382.82  5199.9  383.79  5208.6  384.09
  5214.7  385.20  5229.5  386.18  5236.2  386.13  5250.4  387.12  5259.1  388.97
  5265.2  388.28  5294.8  390.45  5300.9  390.38  5307.7  391.97  5312.1  391.97
#Mann=7,-1,0
  4783.2    0.05       0  4986.7    0.16       0  4997.4    0.07       0
  5001.4    0.16       0  5114.2   0.035       0  5149.8    0.05       0
  5236.2   0.063       0
Bank Sta=4997.4,5001.4
Exp/Cntr=0.3,0.1

Type RM Length L Ch R = 1,2603,298,298,298
BEGIN DESCRIPTION:
South Twin Creek Trib C2603.4
END DESCRIPTION:
XS GIS Cut Line= 5
      2734009.49      6814263.61      2733835.58      6814249.11
      2733774.60      6814216.50      2733728.62      6814108.91
      2733640.93      6813926.23
#Sta/Elev= 30
  4753.2  385.05  4766.7  384.80  4800.1  383.17  4837.0  380.95  4857.0  379.04
  4877.1  377.89  4897.2  376.13  4917.3  376.18  4977.5  374.68  4983.9  375.38
  5006.9  375.05  5036.2  375.30  5054.4  374.56  5075.9  374.30  5076.2  373.80
  5079.7  373.80  5079.9  374.30  5083.4  374.85  5100.7  374.81  5139.2  376.12
  5152.5  376.51  5175.1  378.55  5197.8  379.92  5220.4  382.17  5226.0  383.12
  5239.9  383.87  5277.9  386.81  5293.9  387.68  5311.0  387.85  5316.5  388.47
#Mann=7,-1,0
  4753.2    0.16       0  4800.1   0.035       0  5006.9    0.16       0
  5075.9   0.035       0  5079.9    0.16       0  5139.2   0.035       0
  5239.9    0.05       0
Bank Sta=5075.9,5079.9
Exp/Cntr=0.3,0.1

Type RM Length L Ch R = 1,2305,238,238,238
BEGIN DESCRIPTION:
South Twin Creek Trib C2305.01
END DESCRIPTION:
XS GIS Cut Line= 3
      2734110.44      6814190.67      2733952.10      6813984.30
      2733801.27      6813741.79
#Sta/Elev= 30
  4739.9  386.39  4756.9  385.52  4764.7  384.40  4771.4  384.38  4777.7  383.54
  4827.7  380.01  4878.1  375.90  4885.6  374.90  4956.3  372.02  4979.0  372.36
  4985.3  369.50  4989.6  369.10  4989.9  368.60  4993.4  368.60  4993.6  369.10
  4998.9  371.88  5005.9  372.35  5027.5  372.01  5063.8  373.80  5073.3  373.60
  5099.8  374.66  5137.0  376.34  5152.3  378.40  5173.6  380.24  5180.5  381.47
  5210.2  382.38  5225.5  383.44  5231.4  384.34  5252.7  385.58  5285.6  385.85
#Mann=4,-1,0
  4739.9    0.16       0  4989.6    0.07       0  4993.6    0.16       0
  5099.8    0.05       0
Bank Sta=4989.6,4993.6
Exp/Cntr=0.3,0.1

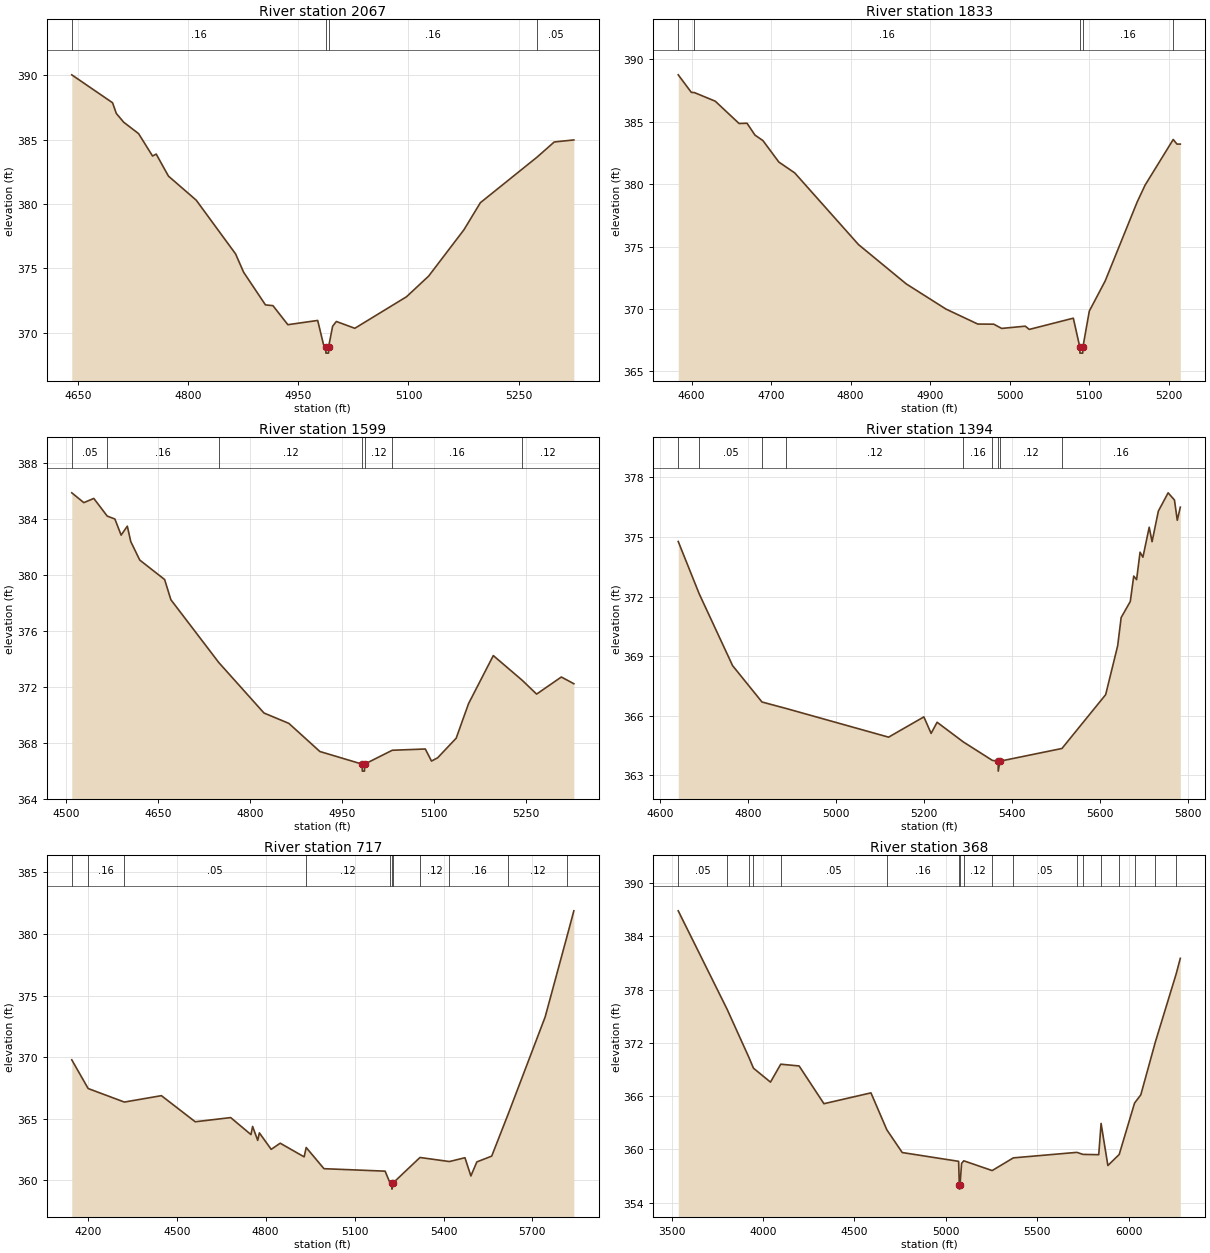
Type RM Length L Ch R = 1,2067,234,234,234
BEGIN DESCRIPTION:
South Twin Creek Trib C2066.67
END DESCRIPTION:
XS GIS Cut Line= 3
      2734200.62      6814200.55      2734138.42      6813845.82
      2734106.49      6813524.44
#Sta/Elev= 30
  4641.9  390.04  4697.4  387.87  4702.5  387.04  4712.5  386.36  4732.8  385.47
  4751.8  383.73  4756.8  383.88  4773.4  382.17  4811.2  380.30  4864.8  376.12
  4875.7  374.70  4905.4  372.16  4915.6  372.10  4935.9  370.62  4976.5  370.95
  4984.3  369.10  4987.4  368.91  4987.7  368.41  4991.2  368.41  4991.4  368.91
  4996.8  370.50  5001.9  370.87  5027.0  370.34  5097.3  372.79  5127.5  374.40
  5175.5  378.00  5197.8  380.10  5275.1  383.65  5298.3  384.82  5325.0  384.98
#Mann=4,-1,0
  4641.9    0.16       0  4987.4    0.07       0  4991.4    0.16       0
  5275.1    0.05       0
Bank Sta=4987.4,4991.4
Exp/Cntr=0.3,0.1

Type RM Length L Ch R = 1,1833,234,234,234
BEGIN DESCRIPTION:
South Twin Creek Trib C1832.62
END DESCRIPTION:
XS GIS Cut Line= 3
      2734347.75      6814227.46      2734359.88      6813806.89
      2734371.46      6813596.75
#Sta/Elev= 30
  4583.3  388.77  4599.8  387.36  4603.5  387.35  4629.8  386.66  4659.8  384.87
  4669.8  384.89  4679.8  383.94  4689.8  383.50  4709.8  381.78  4729.8  380.91
  4809.9  375.17  4869.9  372.02  4919.9  370.00  4959.9  368.80  4979.9  368.79
  4989.9  368.45  5019.6  368.63  5024.6  368.37  5080.0  369.27  5088.1  366.97
  5088.3  366.47  5091.8  366.47  5092.1  366.97  5100.1  369.84  5120.1  372.26
  5160.2  378.57  5170.2  379.93  5205.6  383.59  5210.3  383.22  5214.5  383.22
#Mann=5,-1,0
  4583.3    0.05       0  4603.5    0.16       0  5088.1    0.07       0
  5092.1    0.16       0  5205.6    0.05       0
Bank Sta=5088.1,5092.1
Exp/Cntr=0.3,0.1

Type RM Length L Ch R = 1,1599,205,205,205
BEGIN DESCRIPTION:
South Twin Creek Trib C1598.97
END DESCRIPTION:
XS GIS Cut Line= 3
      2734494.81      6814350.43      2734576.81      6813866.56
      2734531.57      6813540.76
#Sta/Elev= 30
  4509.1  385.85  4528.8  385.15  4545.1  385.45  4567.0  384.19  4579.5  383.98
  4589.7  382.83  4599.8  383.47  4605.4  382.37  4620.1  381.05  4660.7  379.66
  4670.9  378.22  4749.2  373.73  4822.9  370.13  4863.5  369.39  4914.2  367.38
  4983.2  366.48  4983.5  365.98  4987.0  365.98  4987.2  366.48  5032.4  367.47
  5086.3  367.56  5096.4  366.70  5106.4  366.93  5136.7  368.33  5156.9  370.80
  5197.3  374.23  5244.4  372.47  5268.0  371.48  5308.4  372.70  5328.8  372.22
#Mann=7,-1,0
  4509.1    0.05       0  4567.0    0.16       0  4749.2    0.12       0
  4983.2    0.07       0  4987.2    0.12       0  5032.4    0.16       0
  5244.4    0.12       0
Bank Sta=4983.2,4987.2
Exp/Cntr=0.3,0.1

Type RM Length L Ch R = 1,1394,677,677,677
BEGIN DESCRIPTION:
South Twin Creek Trib C1393.52
END DESCRIPTION:
XS GIS Cut Line= 4
      2734699.24      6814262.38      2734767.09      6813910.67
      2734740.35      6813548.96      2734415.84      6813281.53
#Sta/Elev= 30
  4640.8  374.77  4688.2  372.15  4764.4  368.52  4831.2  366.69  4886.8  366.36
  5119.0  364.92  5199.2  365.94  5215.7  365.11  5229.3  365.67  5288.9  364.68
  5355.0  363.75  5368.1  363.71  5368.3  363.21  5372.1  363.71  5513.1  364.35
  5612.5  367.06  5639.8  369.52  5647.7  370.94  5668.5  371.75  5676.3  373.03
  5682.8  372.85  5690.7  374.23  5697.2  373.98  5711.5  375.49  5718.0  374.76
  5732.3  376.30  5754.5  377.22  5768.9  376.86  5775.3  375.84  5782.2  376.50
#Mann=9,-1,0
  4640.8    0.16       0  4688.2    0.05       0  4831.2    0.16       0
  4886.8    0.12       0  5288.9    0.16       0  5355.0    0.12       0
  5368.1    0.07       0  5372.1    0.12       0  5513.1    0.16       0
Bank Sta=5368.1,5372.1
Exp/Cntr=0.3,0.1

Type RM Length L Ch R = 1,717,349,349,349
BEGIN DESCRIPTION:
South Twin Creek Trib C716.88
END DESCRIPTION:
XS GIS Cut Line= 6
      2734742.85      6814190.61      2735026.16      6813586.89
      2735034.93      6813402.66      2734998.50      6813264.12
      2734821.12      6813210.57      2734309.59      6813172.59
#Sta/Elev= 30
  4145.7  369.78  4201.0  367.45  4323.1  366.35  4448.2  366.87  4562.3  364.75
  4681.9  365.09  4750.3  363.71  4755.9  364.37  4773.1  363.24  4778.7  363.85
  4818.6  362.51  4849.0  363.01  4929.8  361.90  4936.7  362.66  4996.7  360.94
  5203.0  360.74  5219.2  359.80  5225.8  359.78  5226.0  359.28  5229.8  359.78
  5320.6  361.85  5419.8  361.52  5472.4  361.83  5492.4  360.35  5512.5  361.49
  5562.6  361.96  5618.0  365.36  5743.1  373.27  5816.1  379.75  5839.8  381.88
#Mann=11,-1,0
  4145.7    0.05       0  4201.0    0.16       0  4323.1    0.05       0
  4936.7    0.12       0  5219.2    0.16       0  5225.8    0.07       0
  5229.8    0.16       0  5320.6    0.12       0  5419.8    0.16       0
  5618.0    0.12       0  5816.1    0.16       0
Bank Sta=5225.8,5229.8
Exp/Cntr=0.3,0.1

Type RM Length L Ch R = 1,368,0,0,0
BEGIN DESCRIPTION:
South Twin Creek Trib C368.004
END DESCRIPTION:
XS GIS Cut Line= 6
      2734550.15      6814529.60      2735233.77      6813597.64
      2735322.90      6813302.93      2735251.00      6813086.00
      2734868.36      6813039.16      2734199.96      6813057.96
#Sta/Elev= 30
  3536.3  386.86  3804.0  375.76  3923.4  370.33  3947.8  369.14  4040.9  367.57
  4097.0  369.59  4197.6  369.39  4333.4  365.14  4590.5  366.36  4677.4  362.20
  4761.7  359.64  5070.1  358.65  5073.8  356.02  5074.0  355.52  5077.8  356.02
  5086.3  358.42  5098.2  358.71  5253.6  357.61  5369.3  359.04  5716.9  359.66
  5750.2  359.43  5836.5  359.40  5849.3  362.92  5886.5  358.18  5948.4  359.42
  6032.4  365.21  6066.6  366.14  6146.5  372.11  6259.8  379.74  6282.7  381.51
#Mann=18,-1,0
  3536.3    0.05       0  3804.0    0.16       0  3923.4    0.05       0
  3947.8    0.16       0  4097.0    0.05       0  4677.4    0.16       0
  5073.8    0.07       0  5077.8    0.16       0  5098.2    0.12       0
  5253.6    0.16       0  5369.3    0.05       0  5716.9    0.12       0
  5750.2    0.16       0  5849.3    0.12       0  5948.4    0.16       0
  6032.4    0.05       0  6146.5    0.16       0  6259.8    0.05       0
Bank Sta=5073.8,5077.8
Exp/Cntr=0.3,0.1

Chan Stop Cuts=-1