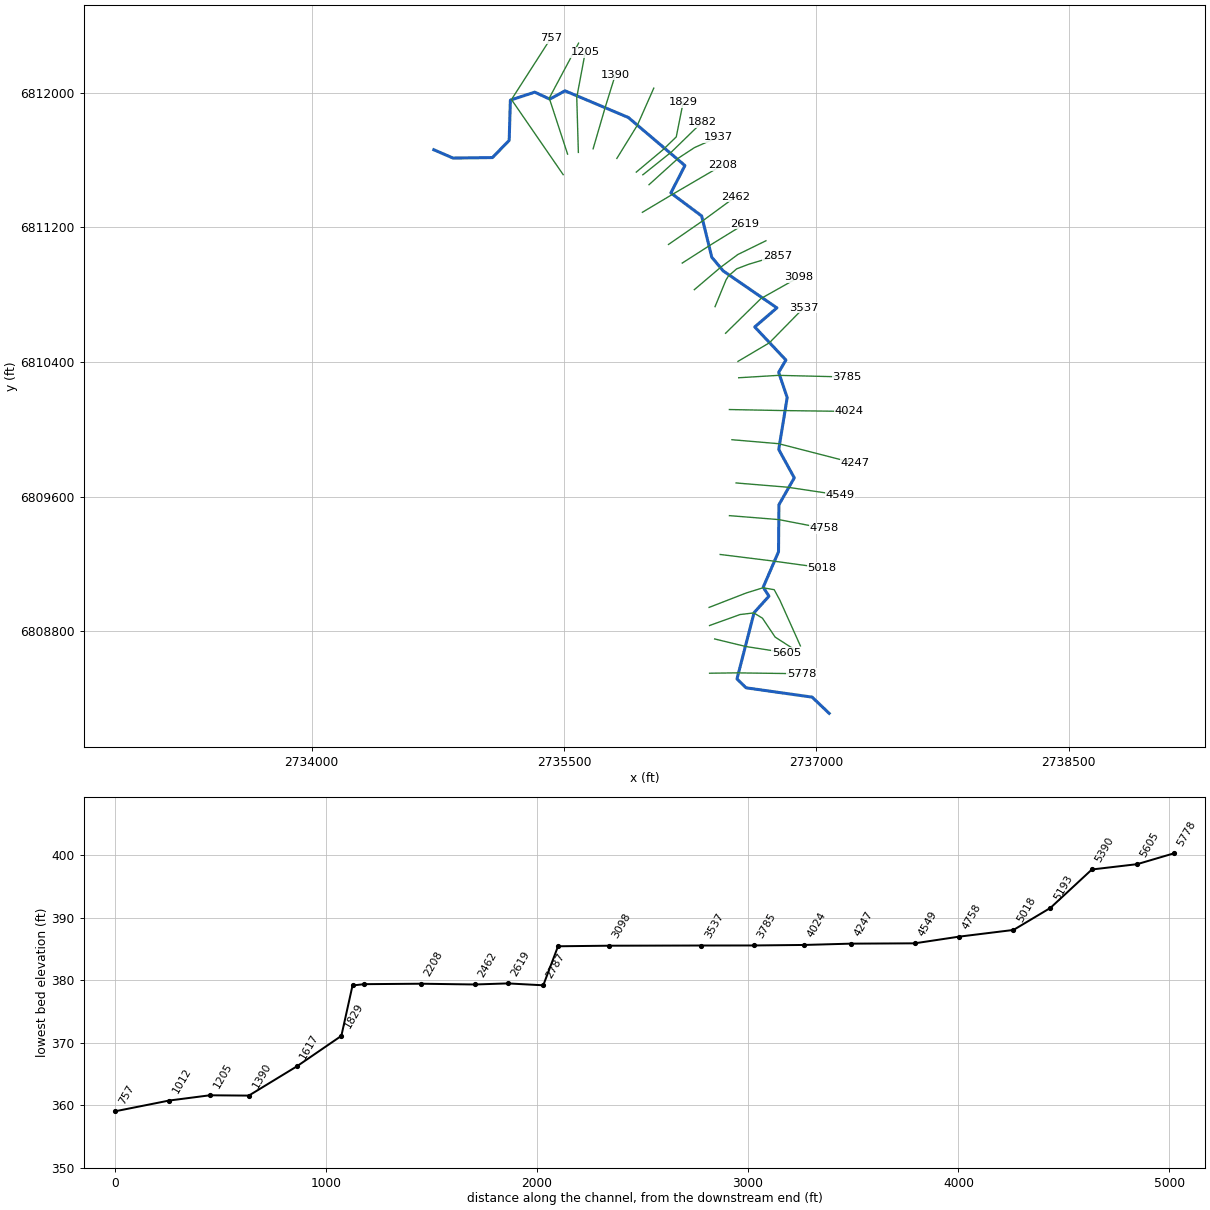
--- South Twin Creek Trib D.prj (project) ---

Proj Title=South Twin Creek Trib D Base Level Engineering
Current Plan=p01
Default Exp/Contr=0.3,0.1
English Units
Geom File=g01
Flow File=f01
Plan File=p01
BEGIN DESCRIPTION:
South Twin Creek Trib D
END DESCRIPTION:

--- South Twin Creek Trib D.p01 (plan) ---

Plan Title=Multiple Run
Short Identifier=Multiple
Geom File=g01
Flow File=f01
Subcritical Flow
K Sum by GR= 0
Std Step Tol= 0.01
Critical Tol= 0.01
Num of Std Step Trials= 20
Max Error Tol= 0.3
Flow Tol Ratio= 0.001
Split Flow NTrial= 30
Split Flow Tol= 0.02
Split Flow Ratio= 0.02
Log Output Level= 0
Friction Slope Method= 1
Unsteady Friction Slope Method= 2
Unsteady Bridges Friction Slope Method= 1
Parabolic Critical Depth
Global Vel Dist=  1 , 1 , 1
Global Log Level= 0
CheckData=True
Encroach Param= -1, 0, 0, 0
BEGIN DESCRIPTION:
Multiple Run
END DESCRIPTION:

--- South Twin Creek Trib D.f01 (steady flow) ---

Flow Title=Multiple
Number of Profiles=7
Profile Names=10-year,25-year,50-year,1pct_min,100-year,1pct_plu,500-year
River Rch & RM= South Twin Creek,Reach-1,5778
     250     316     366     211     422     841     557
Boundary for River Rch & Prof#=South Twin Creek,Reach-1,1
Up Type=0
Dn Type=3
Dn Slope=0.005
Boundary for River Rch & Prof#=South Twin Creek,Reach-1,2
Up Type=0
Dn Type=3
Dn Slope=0.005
Boundary for River Rch & Prof#=South Twin Creek,Reach-1,3
Up Type=0
Dn Type=3
Dn Slope=0.005
Boundary for River Rch & Prof#=South Twin Creek,Reach-1,4
Up Type=0
Dn Type=3
Dn Slope=0.005
Boundary for River Rch & Prof#=South Twin Creek,Reach-1,5
Up Type=0
Dn Type=3
Dn Slope=0.005
Boundary for River Rch & Prof#=South Twin Creek,Reach-1,6
Up Type=0
Dn Type=3
Dn Slope=0.005
Boundary for River Rch & Prof#=South Twin Creek,Reach-1,7
Up Type=0
Dn Type=3
Dn Slope=0.005

--- South Twin Creek Trib D.g01 (geometry) ---

Geom Title=Existing Conditions

River Reach=South Twin Creek,Reach-1
Reach XY= 30
      2737076.00      6808311.00      2736974.55      6808407.51
      2736581.64      6808462.97      2736527.99      6808516.27
      2736629.57      6808909.53      2736717.99      6809007.67
      2736683.80      6809060.90      2736774.78      6809271.50
      2736777.36      6809551.35      2736868.50      6809711.00
      2736776.18      6809879.27      2736826.30      6810188.16
      2736775.82      6810338.28      2736818.68      6810411.10
      2736633.51      6810607.85      2736765.23      6810721.19
      2736445.84      6810941.07      2736378.16      6811022.27
      2736317.98      6811267.34      2736134.96      6811404.31
      2736218.55      6811567.07      2735882.06      6811852.86
      2735505.82      6812011.29      2735415.30      6811961.84
      2735326.01      6812003.41      2735181.03      6811955.93
      2735173.95      6811716.84      2735074.55      6811614.53
      2734839.89      6811611.60      2734726.00      6811661.00

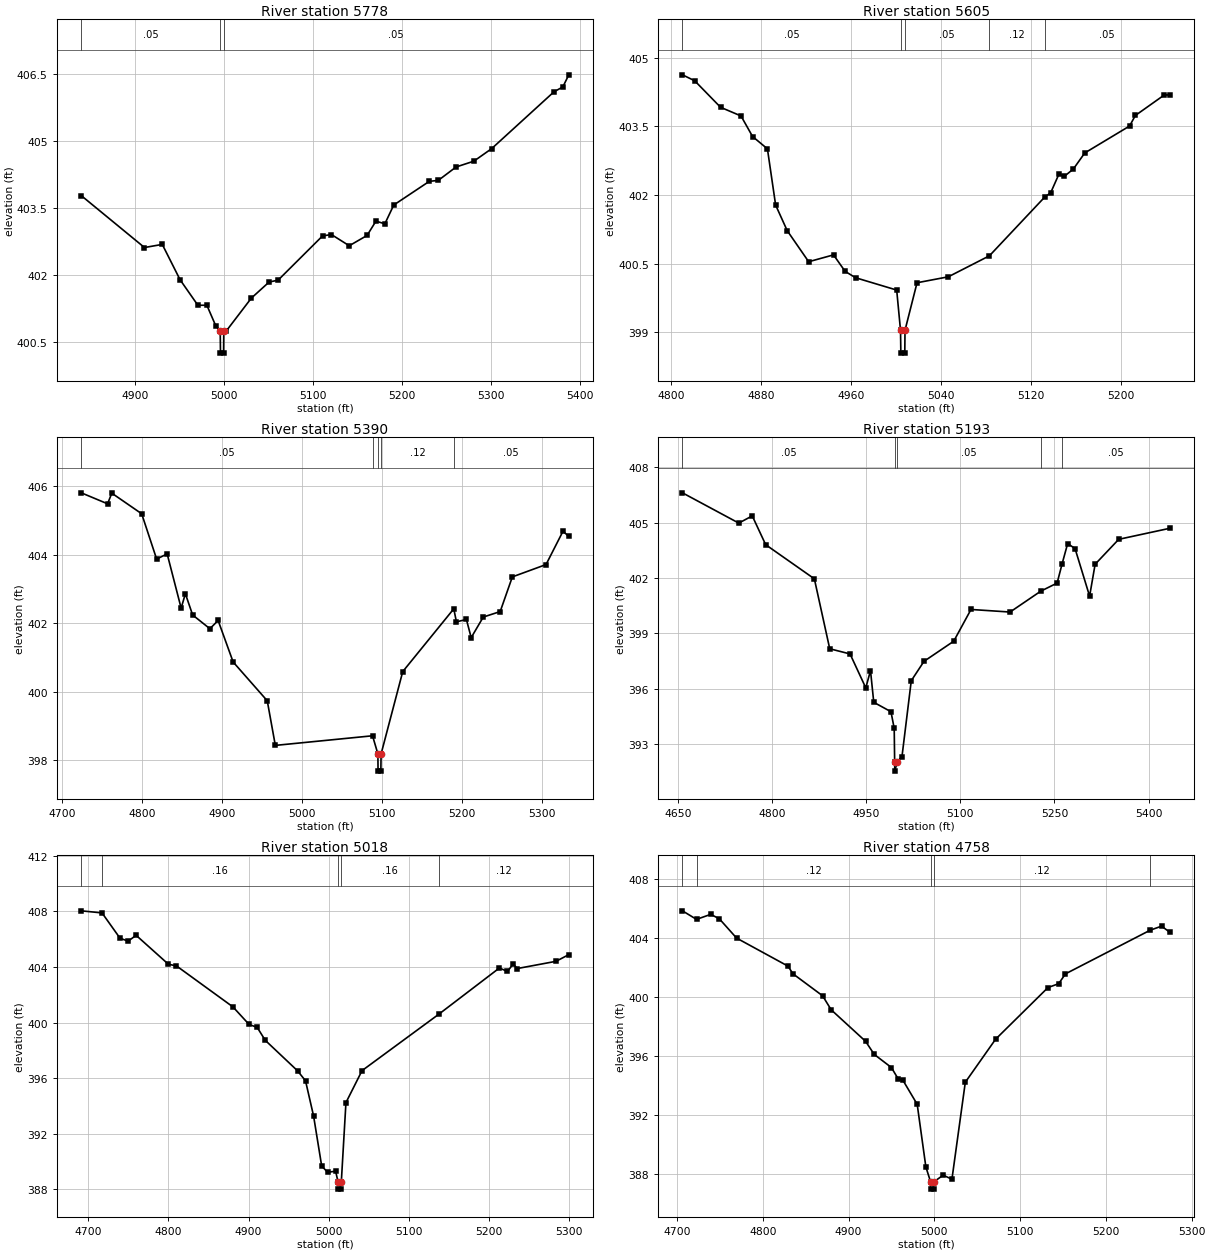
Type RM Length L Ch R = 1,5778,173,173,173
BEGIN DESCRIPTION:
South Twin Creek Trib D5777.667
END DESCRIPTION:
XS GIS Cut Line= 3
      2736364.96      6808549.64      2736525.15      6808551.79
      2736912.71      6808546.55
#Sta/Elev= 30
  4839.8  403.78  4910.8  402.62  4930.8  402.69  4950.8  401.90  4970.8  401.33
  4980.9  401.33  4990.9  400.87  4995.9  400.76  4996.2  400.26  4999.7  400.26
  4999.9  400.76  5002.9  400.76  5030.9  401.49  5050.9  401.85  5060.9  401.89
  5110.9  402.88  5120.9  402.91  5140.9  402.66  5160.9  402.89  5170.9  403.21
  5180.9  403.15  5190.9  403.57  5230.9  404.10  5240.9  404.12  5260.9  404.42
  5280.9  404.55  5300.9  404.83  5370.9  406.10  5380.9  406.21  5387.6  406.48
#Mann=3,-1,0
  4839.8    0.05       0  4995.9    0.05       0  4999.9    0.05       0
Bank Sta=4995.9,4999.9
Exp/Cntr=0.3,0.1

Type RM Length L Ch R = 1,5605,215,215,215
BEGIN DESCRIPTION:
South Twin Creek Trib D5604.57
END DESCRIPTION:
XS GIS Cut Line= 3
      2736395.40      6808753.33      2736580.64      6808708.37
      2736820.86      6808671.19
#Sta/Elev= 30
  4810.1  404.63  4821.0  404.50  4844.0  403.92  4862.2  403.73  4872.5  403.28
  4885.7  403.01  4893.0  401.78  4903.3  401.22  4922.4  400.54  4944.5  400.69
  4954.8  400.33  4964.1  400.19  5000.7  399.92  5004.1  399.04  5004.4  398.54
  5007.9  398.54  5008.1  399.04  5018.8  400.08  5046.6  400.21  5083.2  400.67
  5132.2  401.95  5137.7  402.05  5144.9  402.45  5149.9  402.41  5157.9  402.57
  5168.0  402.92  5207.9  403.51  5213.0  403.74  5238.8  404.19  5243.8  404.19
#Mann=5,-1,0
  4810.1    0.05       0  5004.1    0.05       0  5008.1    0.05       0
  5083.2    0.12       0  5132.2    0.05       0
Bank Sta=5004.1,5008.1
Exp/Cntr=0.3,0.1

Type RM Length L Ch R = 1,5390,197,197,197
BEGIN DESCRIPTION:
South Twin Creek Trib D5389.84
END DESCRIPTION:
XS GIS Cut Line= 6
      2736364.86      6808833.15      2736546.36      6808898.48
      2736627.74      6808908.20      2736679.21      6808876.95
      2736754.67      6808764.44      2736872.18      6808688.80
#Sta/Elev= 30
  4723.8  405.80  4756.7  405.48  4762.0  405.79  4799.4  405.19  4818.1  403.87
  4831.3  404.02  4848.8  402.44  4854.1  402.86  4863.2  402.24  4884.8  401.84
  4895.1  402.08  4913.9  400.87  4956.6  399.74  4966.7  398.44  5088.4  398.72
  5095.1  398.19  5095.3  397.69  5098.8  397.69  5099.1  398.19  5126.2  400.59
  5190.1  402.42  5193.4  402.04  5205.9  402.11  5211.9  401.58  5227.0  402.18
  5248.2  402.34  5263.4  403.35  5305.6  403.71  5326.8  404.68  5334.1  404.53
#Mann=5,-1,0
  4723.8    0.05       0  5088.4    0.12       0  5095.1    0.05       0
  5099.1    0.12       0  5190.1    0.05       0
Bank Sta=5095.1,5099.1
Exp/Cntr=0.3,0.1

Type RM Length L Ch R = 1,5193,175,175,175
BEGIN DESCRIPTION:
South Twin Creek Trib D5193.38
END DESCRIPTION:
XS GIS Cut Line= 6
      2736362.29      6808940.89      2736583.03      6809026.64
      2736682.66      6809057.57      2736749.10      6809046.16
      2736782.54      6808984.60      2736904.79      6808712.17
#Sta/Elev= 30
  4657.0  406.62  4746.8  404.98  4768.3  405.37  4789.7  403.81  4867.3  401.96
  4891.8  398.17  4924.2  397.89  4949.3  396.05  4956.8  396.99  4962.0  395.27
  4989.4  394.76  4994.6  393.86  4995.3  392.04  4995.5  391.54  4999.3  392.04
  5007.0  392.33  5021.8  396.44  5042.1  397.49  5089.5  398.58  5117.0  400.30
  5179.3  400.16  5228.2  401.29  5254.3  401.73  5262.4  402.79  5271.1  403.87
  5282.9  403.60  5306.1  401.02  5314.9  402.75  5352.5  404.10  5434.2  404.70
#Mann=5,-1,0
  4657.0    0.05       0  4995.3    0.05       0  4999.3    0.05       0
  5228.2    0.12       0  5262.4    0.05       0
Bank Sta=4995.3,4999.3
Exp/Cntr=0.3,0.1

Type RM Length L Ch R = 1,5018,260,260,260
BEGIN DESCRIPTION:
South Twin Creek Trib D5017.52
END DESCRIPTION:
XS GIS Cut Line= 3
      2736427.99      6809255.51      2736735.86      6809217.33
      2737031.88      6809176.86
#Sta/Elev= 30
  4691.1  408.03  4717.0  407.88  4739.5  406.06  4749.6  405.85  4759.6  406.27
  4799.9  404.19  4810.0  404.07  4880.6  401.12  4900.7  399.86  4910.8  399.65
  4920.9  398.72  4961.2  396.53  4971.2  395.81  4981.3  393.27  4991.4  389.68
  4998.9  389.23  5008.8  389.31  5011.9  388.52  5012.1  388.02  5015.6  388.02
  5015.9  388.52  5021.7  394.24  5041.8  396.54  5137.8  400.60  5213.4  403.92
  5223.5  403.67  5230.6  404.21  5235.7  403.88  5284.1  404.40  5300.1  404.88
#Mann=5,-1,0
  4691.1    0.07       0  4717.0    0.16       0  5011.9    0.07       0
  5015.9    0.16       0  5137.8    0.12       0
Bank Sta=5011.9,5015.9
Exp/Cntr=0.3,0.1

Type RM Length L Ch R = 1,4758,209,209,209
BEGIN DESCRIPTION:
South Twin Creek Trib D4757.76
END DESCRIPTION:
XS GIS Cut Line= 3
      2736483.14      6809486.28      2736775.99      6809462.90
      2737045.63      6809410.83
#Sta/Elev= 30
  4706.3  405.84  4722.7  405.26  4739.3  405.60  4749.3  405.30  4769.4  403.99
  4829.5  402.08  4835.0  401.57  4869.7  400.07  4879.7  399.12  4919.8  396.98
  4929.9  396.09  4949.9  395.20  4958.0  394.41  4963.1  394.36  4980.0  392.70
  4990.1  388.45  4995.6  387.44  4995.8  386.94  4999.3  386.94  4999.6  387.44
  5010.3  387.89  5020.5  387.61  5036.1  394.20  5071.4  397.12  5132.5  400.63
  5144.9  400.89  5152.9  401.56  5251.5  404.52  5264.9  404.80  5274.7  404.38
#Mann=5,-1,0
  4706.3    0.07       0  4722.7    0.12       0  4995.6    0.07       0
  4999.6    0.12       0  5251.5    0.05       0
Bank Sta=4995.6,4999.6
Exp/Cntr=0.3,0.1

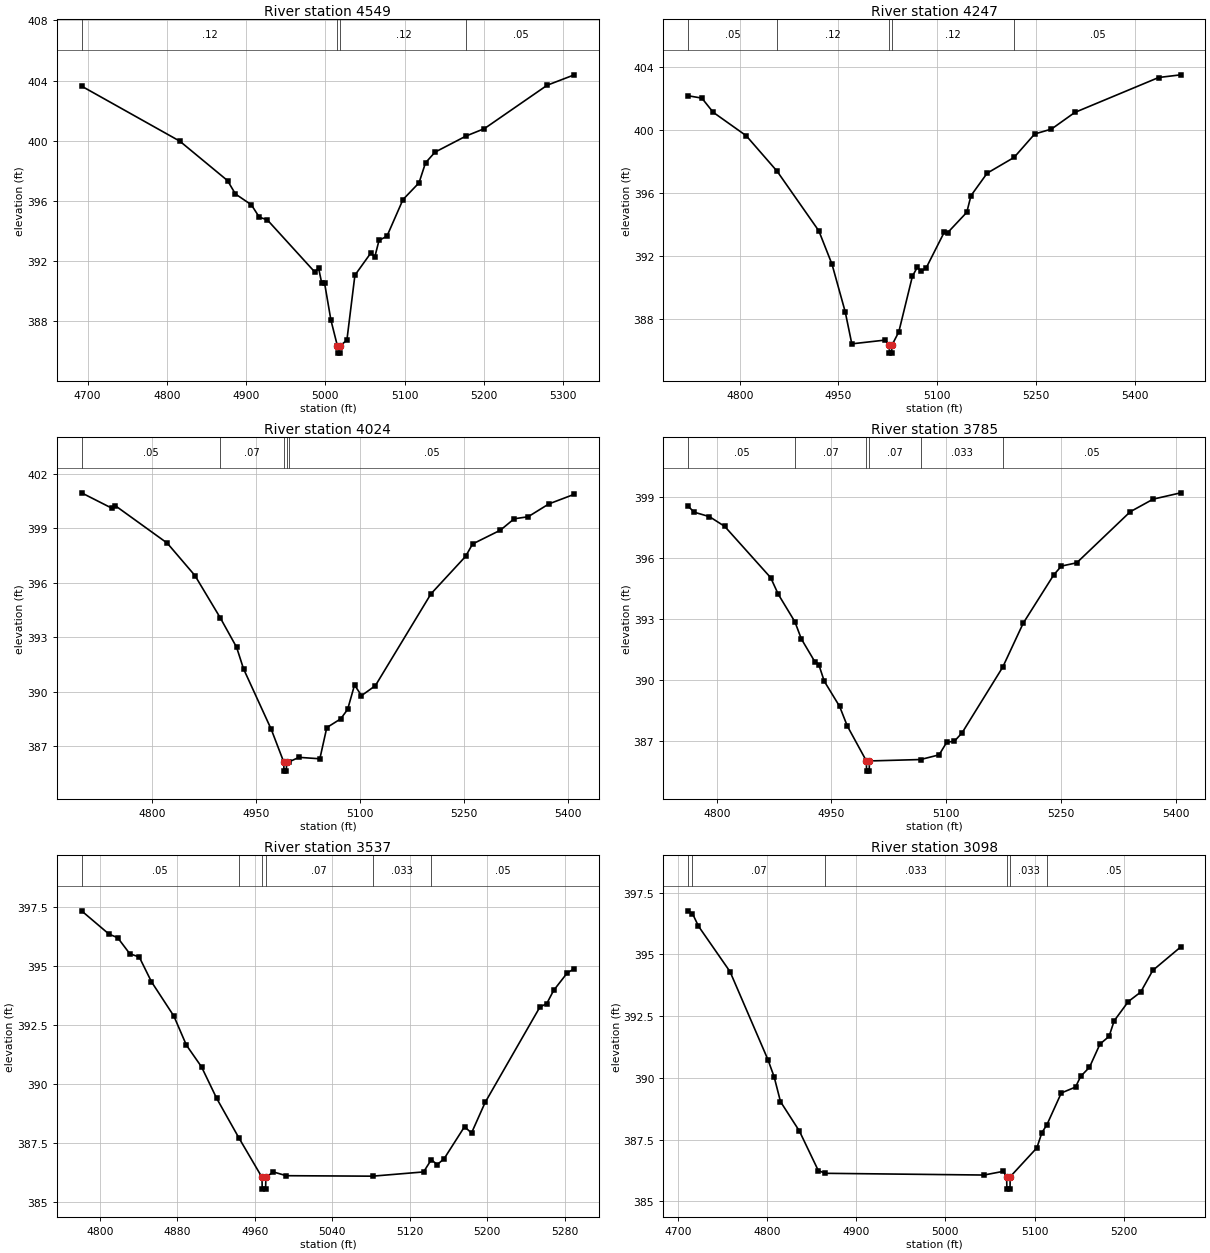
Type RM Length L Ch R = 1,4549,302,302,302
BEGIN DESCRIPTION:
South Twin Creek Trib D4549.3
END DESCRIPTION:
XS GIS Cut Line= 3
      2736522.44      6809680.58      2736828.11      6809655.35
      2737139.81      6809608.63
#Sta/Elev= 30
  4692.4  403.63  4816.4  399.97  4876.6  397.35  4886.6  396.46  4906.7  395.74
  4916.7  394.92  4926.8  394.74  4986.6  391.28  4991.6  391.52  4995.5  390.54
  4999.1  390.54  5007.1  388.08  5015.2  386.38  5015.5  385.88  5019.0  385.88
  5019.2  386.38  5027.3  386.75  5037.4  391.06  5057.4  392.53  5062.5  392.27
  5067.8  393.37  5077.9  393.66  5098.1  396.09  5118.3  397.20  5126.5  398.53
  5138.5  399.24  5178.0  400.32  5200.7  400.80  5280.1  403.69  5314.3  404.38
#Mann=4,-1,0
  4692.4    0.12       0  5015.2    0.07       0  5019.2    0.12       0
  5178.0    0.05       0
Bank Sta=5015.2,5019.2
Exp/Cntr=0.3,0.1

Type RM Length L Ch R = 1,4247,223,223,223
BEGIN DESCRIPTION:
South Twin Creek Trib D4247.36
END DESCRIPTION:
XS GIS Cut Line= 3
      2736497.96      6809937.61      2736776.04      6809913.89
      2737230.96      6809796.95
#Sta/Elev= 30
  4721.4  402.19  4742.4  402.04  4759.6  401.14  4809.8  399.65  4856.8  397.39
  4920.2  393.60  4940.2  391.48  4960.3  388.45  4970.3  386.42  5021.1  386.66
  5027.2  386.33  5027.5  385.83  5031.0  385.83  5031.2  386.33  5041.7  387.18
  5062.4  390.72  5070.0  391.30  5075.1  391.02  5083.0  391.22  5110.7  393.51
  5115.8  393.48  5145.0  394.78  5151.4  395.84  5176.0  397.27  5216.9  398.27
  5248.2  399.76  5273.6  400.07  5309.2  401.13  5436.6  403.35  5470.2  403.52
#Mann=5,-1,0
  4721.4    0.05       0  4856.8    0.12       0  5027.2    0.07       0
  5031.2    0.12       0  5216.9    0.05       0
Bank Sta=5027.2,5031.2
Exp/Cntr=0.3,0.1

Type RM Length L Ch R = 1,4024,239,239,239
BEGIN DESCRIPTION:
South Twin Creek Trib D4024.41
END DESCRIPTION:
XS GIS Cut Line= 3
      2736482.62      6810116.92      2736786.07      6810111.12
      2737192.62      6810105.66
#Sta/Elev= 30
  4698.7  400.96  4742.0  400.12  4747.0  400.26  4822.1  398.19  4862.1  396.40
  4898.6  394.07  4922.1  392.45  4932.1  391.26  4972.1  387.92  4990.1  386.12
  4990.4  385.62  4993.9  385.62  4994.1  386.12  4997.6  386.13  5012.1  386.38
  5042.1  386.30  5052.1  388.02  5072.1  388.50  5082.1  389.02  5092.1  390.37
  5102.1  389.78  5122.1  390.33  5202.2  395.39  5252.2  397.46  5262.2  398.14
  5302.2  398.90  5322.2  399.53  5342.2  399.64  5372.2  400.35  5408.8  400.88
#Mann=5,-1,0
  4698.7    0.05       0  4898.6    0.07       0  4990.1    0.05       0
  4994.1    0.07       0  4997.6    0.05       0
Bank Sta=4990.1,4994.1
Exp/Cntr=0.3,0.1

Type RM Length L Ch R = 1,3785,248,248,248
BEGIN DESCRIPTION:
South Twin Creek Trib D3785.02
END DESCRIPTION:
XS GIS Cut Line= 3
      2736538.10      6810305.85      2736774.84      6810320.11
      2737182.05      6810310.33
#Sta/Elev= 30
  4762.4  398.57  4770.3  398.27  4790.4  398.05  4810.4  397.57  4870.5  395.05
  4880.5  394.23  4902.2  392.88  4910.6  392.04  4928.4  390.91  4933.4  390.78
  4940.6  389.96  4960.7  388.72  4970.7  387.76  4995.7  386.04  4995.9  385.54
  4999.4  385.54  4999.7  386.04  5066.6  386.11  5090.8  386.34  5100.8  386.96
  5110.8  387.01  5120.8  387.42  5174.0  390.65  5200.8  392.81  5240.8  395.19
  5250.8  395.62  5270.8  395.78  5340.8  398.29  5370.8  398.91  5406.9  399.22
#Mann=6,-1,0
  4762.4    0.05       0  4902.2    0.07       0  4995.7    0.07       0
  4999.7    0.07       0  5066.6   0.033       0  5174.0    0.05       0
Bank Sta=4995.7,4999.7
Exp/Cntr=0.3,0.1

Type RM Length L Ch R = 1,3537,439,439,439
BEGIN DESCRIPTION:
South Twin Creek Trib D3536.81
END DESCRIPTION:
XS GIS Cut Line= 3
      2736533.90      6810403.14      2736720.63      6810513.65
      2736925.25      6810722.00
#Sta/Elev= 30
  4781.1  397.34  4809.5  396.35  4818.4  396.20  4830.9  395.52  4840.7  395.38
  4853.3  394.33  4876.5  392.87  4889.4  391.64  4905.0  390.72  4920.7  389.38
  4943.4  387.72  4967.5  386.03  4967.7  385.53  4971.2  385.53  4971.5  386.03
  4979.2  386.26  4992.5  386.10  5081.7  386.08  5134.4  386.26  5142.4  386.78
  5148.5  386.57  5155.6  386.82  5176.7  388.18  5183.9  387.91  5198.0  389.21
  5254.6  393.26  5261.6  393.40  5268.7  393.96  5282.9  394.71  5290.1  394.88
#Mann=6,-1,0
  4781.1    0.05       0  4943.4    0.07       0  4967.5    0.07       0
  4971.5    0.07       0  5081.7   0.033       0  5142.4    0.05       0
Bank Sta=4967.5,4971.5
Exp/Cntr=0.3,0.1

Type RM Length L Ch R = 1,3098,241,241,241
BEGIN DESCRIPTION:
South Twin Creek Trib D3098.12
END DESCRIPTION:
XS GIS Cut Line= 3
      2736460.12      6810570.26      2736670.29      6810776.56
      2736895.23      6810903.12
#Sta/Elev= 30
  4711.4  396.76  4716.4  396.65  4723.1  396.14  4758.5  394.30  4801.0  390.74
  4808.0  390.04  4815.1  389.04  4836.3  387.85  4857.5  386.25  4865.4  386.14
  5043.3  386.07  5065.0  386.22  5068.7  386.00  5069.0  385.50  5072.5  385.50
  5072.7  386.00  5102.6  387.17  5108.3  387.79  5113.8  388.10  5130.0  389.39
  5146.0  389.63  5151.7  390.06  5161.6  390.43  5173.4  391.37  5183.6  391.68
  5189.3  392.31  5205.2  393.09  5219.0  393.47  5232.6  394.35  5264.0  395.30
#Mann=6,-1,0
  4711.4    0.05       0  4716.4    0.07       0  4865.4   0.033       0
  5068.7   0.033       0  5072.7   0.033       0  5113.8    0.05       0
Bank Sta=5068.7,5072.7
Exp/Cntr=0.3,0.1

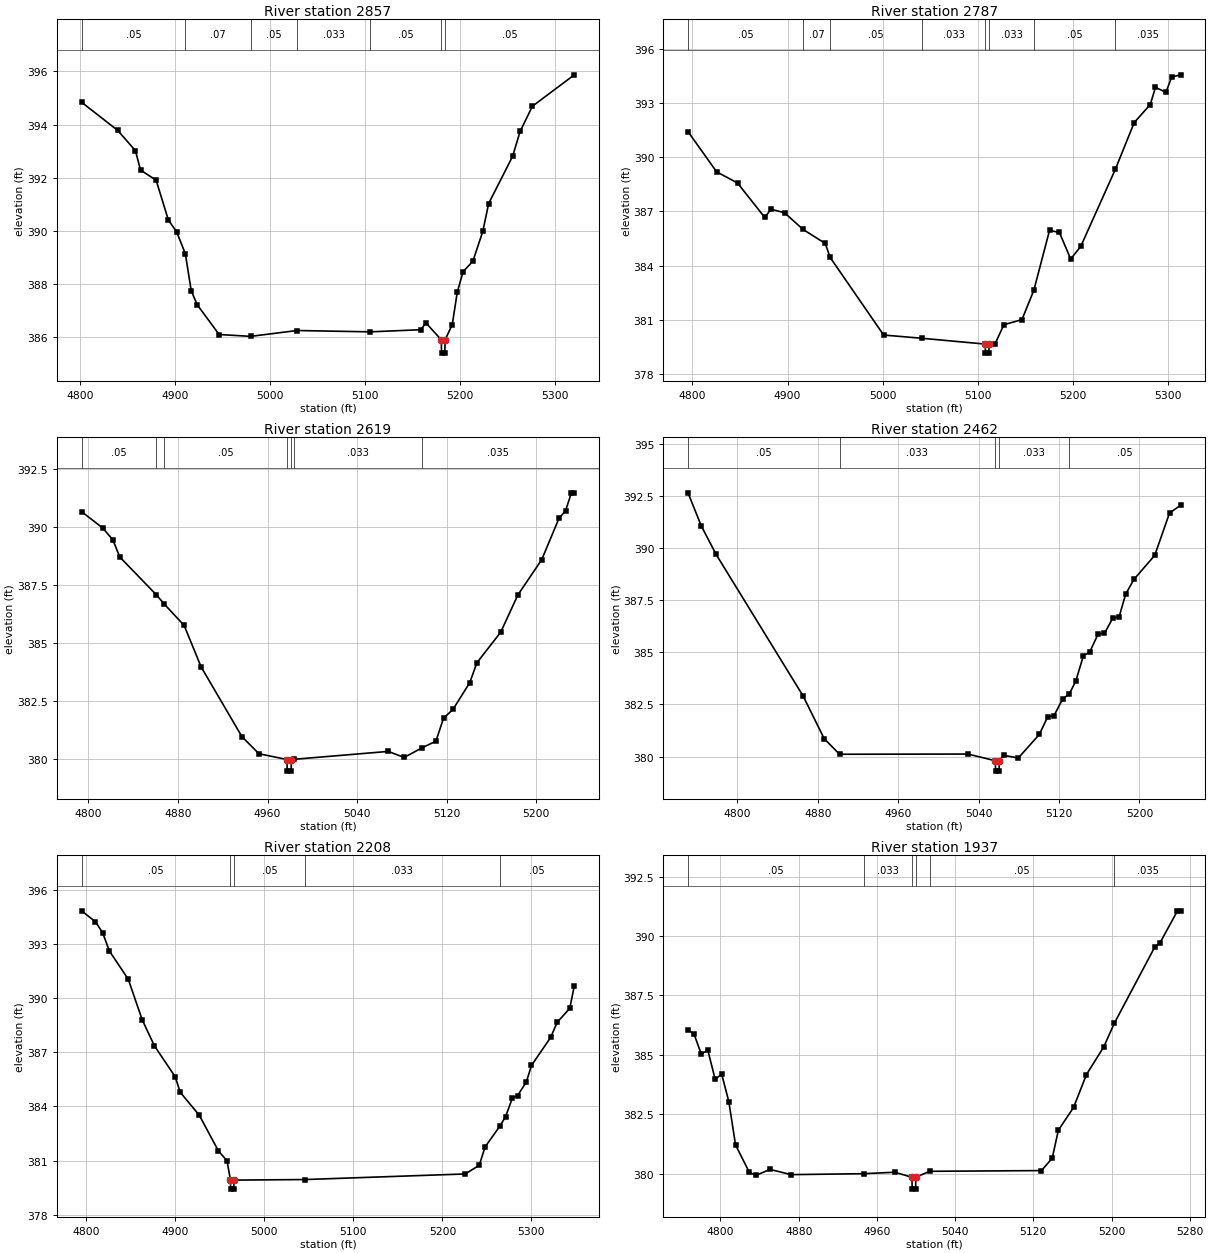
Type RM Length L Ch R = 1,2857,70,70,70
BEGIN DESCRIPTION:
South Twin Creek Trib D2857.24
END DESCRIPTION:
XS GIS Cut Line= 6
      2736397.50      6810728.42      2736462.86      6810887.60
      2736477.02      6810910.45      2736526.01      6810953.17
      2736598.87      6810980.87      2736768.21      6811031.64
#Sta/Elev= 30
  4801.6  394.84  4839.7  393.78  4858.3  393.02  4863.7  392.29  4880.1  391.91
  4893.0  390.41  4901.7  389.97  4910.9  389.14  4917.0  387.76  4923.3  387.23
  4946.4  386.11  4979.5  386.04  5028.6  386.26  5105.3  386.21  5158.8  386.29
  5164.0  386.55  5180.3  385.91  5180.5  385.41  5184.0  385.41  5184.3  385.91
  5191.8  386.48  5197.1  387.70  5203.2  388.47  5213.6  388.87  5224.0  389.99
  5230.1  391.03  5255.4  392.81  5263.2  393.74  5276.2  394.69  5320.3  395.87
#Mann=7,-1,0
  4801.6    0.05       0  4910.9    0.07       0  4979.5    0.05       0
  5028.6   0.033       0  5105.3    0.05       0  5180.3    0.05       0
  5184.3    0.05       0
Bank Sta=5180.3,5184.3
Exp/Cntr=0.3,0.1

Type RM Length L Ch R = 1,2787,168,168,168
BEGIN DESCRIPTION:
South Twin Creek Trib D2787.28
END DESCRIPTION:
XS GIS Cut Line= 4
      2736274.54      6810829.45      2736431.66      6810963.06
      2736532.81      6811038.19      2736699.98      6811120.08
#Sta/Elev= 30
  4795.3  391.41  4825.4  389.19  4847.4  388.57  4876.0  386.67  4882.6  387.12
  4896.8  386.93  4916.2  386.01  4939.7  385.23  4944.8  384.46  5001.1  380.17
  5041.5  379.99  5108.0  379.67  5108.2  379.17  5111.7  379.17  5112.0  379.67
  5118.4  379.69  5127.6  380.74  5146.6  381.02  5159.1  382.64  5175.6  385.95
  5186.0  385.84  5197.9  384.37  5208.5  385.07  5244.8  389.32  5264.7  391.91
  5281.6  392.91  5287.1  393.86  5298.1  393.58  5304.1  394.43  5313.7  394.55
#Mann=8,-1,0
  4795.3    0.05       0  4916.2    0.07       0  4944.8    0.05       0
  5041.5   0.033       0  5108.0    0.05       0  5112.0   0.033       0
  5159.1    0.05       0  5244.8   0.035       0
Bank Sta=5108,5112
Exp/Cntr=0.3,0.1

Type RM Length L Ch R = 1,2619,157,157,157
BEGIN DESCRIPTION:
South Twin Creek Trib D2618.53
END DESCRIPTION:
XS GIS Cut Line= 3
      2736202.45      6810987.42      2736378.11      6811099.84
      2736575.54      6811221.39
#Sta/Elev= 30
  4793.8  390.66  4812.8  389.95  4821.8  389.44  4828.0  388.70  4860.7  387.07
  4867.8  386.67  4885.5  385.75  4900.7  383.96  4937.1  380.96  4952.3  380.22
  4977.4  379.97  4977.6  379.47  4981.1  379.47  4981.4  379.97  4983.6  379.98
  5067.9  380.32  5082.1  380.06  5098.3  380.48  5110.5  380.76  5117.3  381.75
  5125.9  382.14  5140.8  383.29  5147.1  384.14  5168.4  385.46  5183.8  387.07
  5205.1  388.59  5220.5  390.37  5226.4  390.70  5231.6  391.47  5234.2  391.47
#Mann=7,-1,0
  4793.8    0.05       0  4860.7    0.07       0  4867.8    0.05       0
  4977.4   0.033       0  4981.4    0.05       0  4983.6   0.033       0
  5098.3   0.035       0
Bank Sta=4977.4,4981.4
Exp/Cntr=0.3,0.1

Type RM Length L Ch R = 1,2462,254,254,254
BEGIN DESCRIPTION:
South Twin Creek Trib D2461.52
END DESCRIPTION:
XS GIS Cut Line= 3
      2736120.82      6811098.07      2736325.18      6811239.29
      2736520.29      6811382.45
#Sta/Elev= 30
  4750.8  392.66  4764.0  391.07  4778.8  389.70  4865.3  382.91  4886.3  380.86
  4901.6  380.11  5029.3  380.12  5056.6  379.80  5056.9  379.30  5060.4  379.30
  5060.6  379.80  5064.8  380.06  5079.5  379.93  5100.4  381.06  5108.8  381.91
  5115.0  381.96  5123.5  382.75  5130.4  383.02  5136.7  383.62  5144.3  384.84
  5150.5  385.01  5159.0  385.89  5165.2  385.91  5173.6  386.65  5179.8  386.70
  5186.3  387.79  5194.5  388.50  5215.3  389.66  5230.0  391.69  5241.2  392.07
#Mann=5,-1,0
  4750.8    0.05       0  4901.6   0.033       0  5056.6   0.033       0
  5060.6   0.033       0  5130.4    0.05       0
Bank Sta=5056.6,5060.6
Exp/Cntr=0.3,0.1

Type RM Length L Ch R = 1,2208,271,271,271
BEGIN DESCRIPTION:
South Twin Creek Trib D2208.06
END DESCRIPTION:
XS GIS Cut Line= 3
      2735965.63      6811289.26      2736143.21      6811395.18
      2736442.61      6811570.25
#Sta/Elev= 30
  4794.6  394.83  4810.1  394.23  4818.3  393.62  4825.7  392.62  4847.1  391.04
  4862.7  388.80  4876.5  387.35  4899.7  385.65  4905.5  384.78  4926.9  383.51
  4948.3  381.54  4958.0  380.99  4961.9  379.92  4962.1  379.42  4965.6  379.42
  4965.9  379.92  5045.2  379.95  5225.7  380.26  5241.4  380.74  5247.9  381.75
  5265.0  382.94  5271.0  383.44  5278.6  384.46  5284.4  384.60  5294.2  385.34
  5300.1  386.27  5321.6  387.82  5329.0  388.66  5343.1  389.43  5348.2  390.68
#Mann=5,-1,0
  4794.6    0.05       0  4961.9    0.05       0  4965.9    0.05       0
  5045.2   0.033       0  5265.0    0.05       0
Bank Sta=4961.9,4965.9
Exp/Cntr=0.3,0.1

Type RM Length L Ch R = 1,1937,55,55,55
BEGIN DESCRIPTION:
South Twin Creek Trib D1936.57
END DESCRIPTION:
XS GIS Cut Line= 4
      2736005.02      6811453.27      2736178.87      6811610.66
      2736275.52      6811673.99      2736416.17      6811736.55
#Sta/Elev= 30
  4766.8  386.05  4772.9  385.88  4780.3  385.04  4787.1  385.19  4794.5  383.98
  4801.3  384.18  4808.6  383.02  4815.4  381.21  4829.6  380.05  4836.4  379.93
  4850.6  380.18  4872.2  379.96  4946.4  380.00  4978.3  380.06  4995.8  379.85
  4996.1  379.35  4999.6  379.35  4999.8  379.85  5013.9  380.10  5128.3  380.13
  5139.3  380.65  5145.6  381.83  5161.2  382.79  5174.3  384.17  5192.1  385.34
  5202.7  386.32  5244.0  389.52  5249.5  389.71  5267.3  391.05  5270.8  391.06
#Mann=6,-1,0
  4766.8    0.05       0  4946.4   0.033       0  4995.8   0.033       0
  4999.8   0.033       0  5013.9    0.05       0  5202.7   0.035       0
Bank Sta=4995.8,4999.8
Exp/Cntr=0.3,0.1

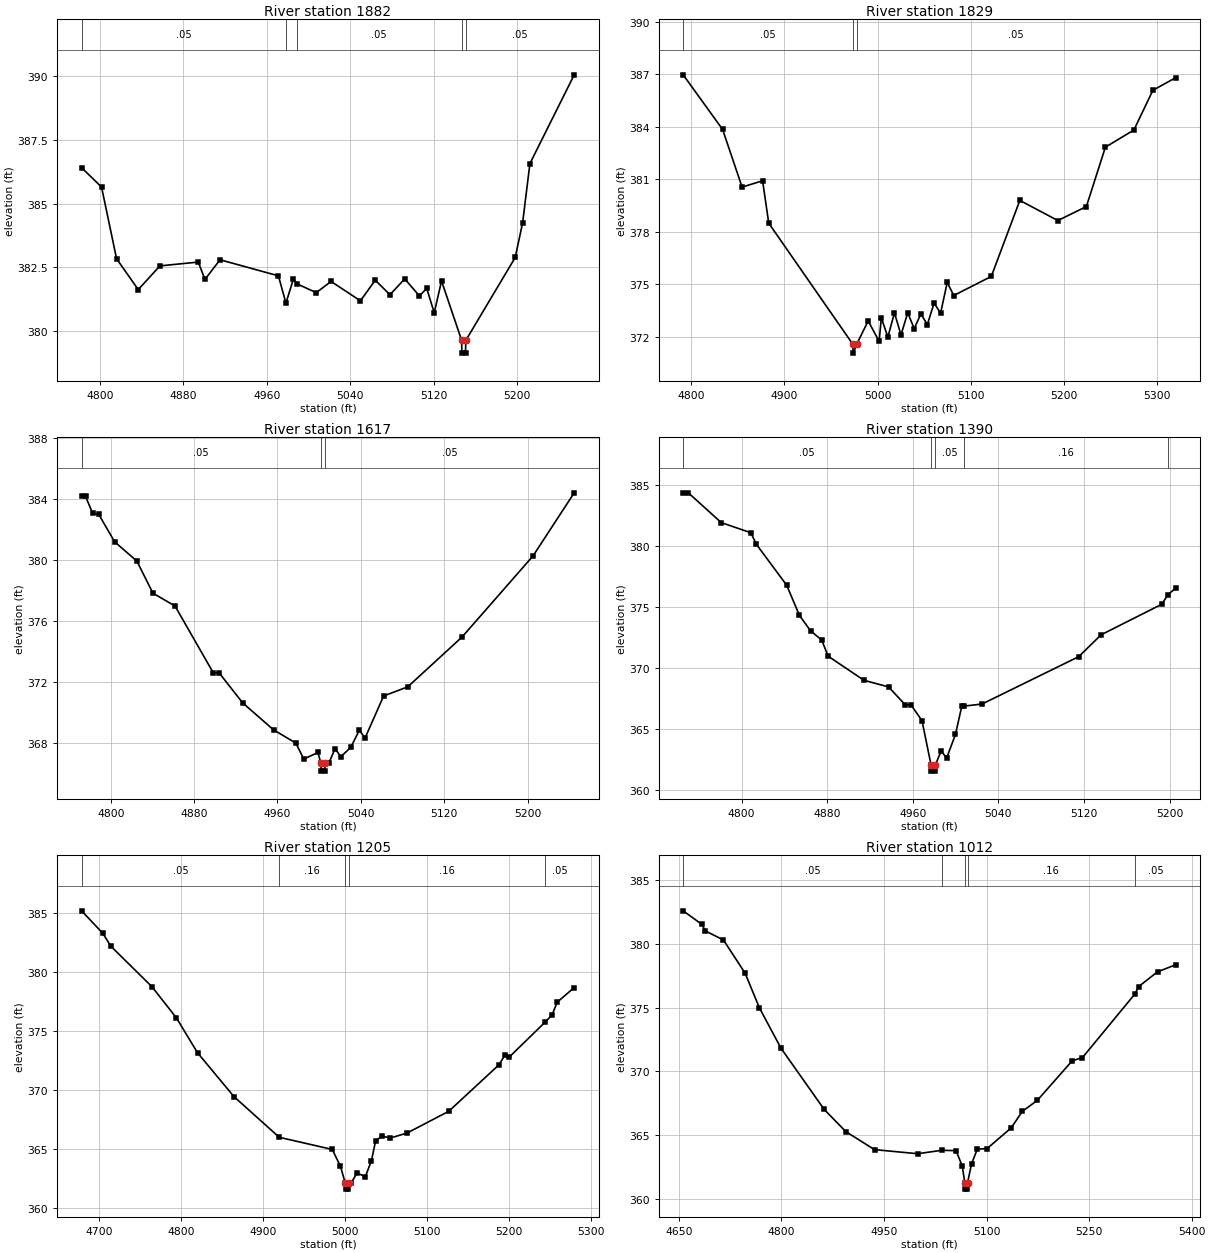
Type RM Length L Ch R = 1,1882,53,53,53
BEGIN DESCRIPTION:
South Twin Creek Trib D1881.67
END DESCRIPTION:
XS GIS Cut Line= 3
      2735968.36      6811512.16      2736139.37      6811648.69
      2736321.29      6811825.77
#Sta/Elev= 30
  4782.3  386.41  4801.5  385.65  4815.9  382.84  4836.7  381.63  4857.5  382.56
  4894.3  382.71  4900.7  382.03  4915.2  382.80  4971.2  382.17  4978.4  381.10
  4985.6  382.05  4988.8  381.86  5007.5  381.51  5021.7  381.95  5049.9  381.19
  5064.1  382.00  5078.2  381.43  5092.4  382.05  5106.5  381.38  5113.5  381.68
  5120.7  380.72  5127.7  381.97  5147.0  379.64  5147.2  379.14  5150.7  379.14
  5151.0  379.64  5198.4  382.89  5205.5  384.25  5212.5  386.57  5255.0  390.05
#Mann=5,-1,0
  4782.3    0.05       0  4978.4   0.033       0  4988.8    0.05       0
  5147.0    0.05       0  5151.0    0.05       0
Bank Sta=5147,5151
Exp/Cntr=0.3,0.1

Type RM Length L Ch R = 1,1829,212,212,212
BEGIN DESCRIPTION:
South Twin Creek Trib D1829.35
END DESCRIPTION:
XS GIS Cut Line= 4
      2735929.39      6811528.13      2736090.50      6811663.12
      2736167.04      6811737.66      2736208.44      6811945.14
#Sta/Elev= 30
  4791.3  386.97  4833.6  383.85  4854.5  380.56  4876.5  380.92  4883.1  378.50
  4973.4  371.58  4973.7  371.08  4977.4  371.58  4989.8  372.92  5001.5  371.75
  5003.9  373.09  5010.9  372.00  5018.0  373.38  5025.0  372.12  5032.2  373.38
  5039.2  372.48  5046.3  373.32  5053.3  372.71  5060.5  373.94  5067.5  373.36
  5074.6  375.12  5081.6  374.37  5121.9  375.46  5152.5  379.80  5193.3  378.65
  5223.9  379.45  5244.3  382.84  5274.9  383.82  5295.3  386.09  5319.9  386.81
#Mann=3,-1,0
  4791.3    0.05       0  4973.4    0.05       0  4977.4    0.05       0
Bank Sta=4973.4,4977.4
Exp/Cntr=0.3,0.1

Type RM Length L Ch R = 1,1617,227,227,227
BEGIN DESCRIPTION:
South Twin Creek Trib D1617.12
END DESCRIPTION:
XS GIS Cut Line= 3
      2735813.92      6811609.50      2735936.06      6811807.21
      2736033.28      6812027.08
#Sta/Elev= 30
  4772.0  384.19  4775.8  384.19  4782.6  383.07  4788.4  383.01  4803.8  381.20
  4825.1  379.94  4840.5  377.84  4861.7  377.00  4898.4  372.63  4904.3  372.60
  4926.6  370.66  4956.3  368.89  4977.6  368.03  4985.3  366.98  4998.9  367.41
  5001.7  366.69  5001.9  366.19  5005.4  366.19  5005.7  366.69  5009.2  366.69
  5015.3  367.67  5020.8  367.13  5030.4  367.75  5038.6  368.87  5044.1  368.36
  5061.9  371.11  5085.1  371.71  5137.3  374.98  5205.3  380.28  5244.8  384.41
#Mann=3,-1,0
  4772.0    0.05       0  5001.7    0.05       0  5005.7    0.05       0
Bank Sta=5001.7,5005.7
Exp/Cntr=0.3,0.1

Type RM Length L Ch R = 1,1390,185,185,185
BEGIN DESCRIPTION:
South Twin Creek Trib D1390.34
END DESCRIPTION:
XS GIS Cut Line= 3
      2735672.88      6811666.79      2735745.98      6811917.44
      2735805.23      6812107.63
#Sta/Elev= 30
  4745.5  384.33  4750.3  384.33  4781.1  381.89  4808.7  381.06  4813.9  380.11
  4842.2  376.76  4854.1  374.29  4864.5  373.03  4874.9  372.27  4880.9  370.95
  4914.4  368.97  4937.4  368.43  4953.1  366.95  4958.3  366.96  4968.6  365.67
  4977.1  362.03  4977.3  361.53  4980.8  361.53  4981.1  362.03  4986.5  363.18
  4991.7  362.61  4999.9  364.54  5005.8  366.85  5007.5  366.85  5024.8  367.03
  5115.1  370.91  5136.0  372.70  5192.6  375.20  5198.5  375.99  5205.8  376.54
#Mann=5,-1,0
  4745.5    0.05       0  4977.1    0.05       0  4981.1    0.05       0
  5007.5    0.16       0  5198.5    0.05       0
Bank Sta=4977.1,4981.1
Exp/Cntr=0.3,0.1

Type RM Length L Ch R = 1,1205,193,193,193
BEGIN DESCRIPTION:
South Twin Creek Trib D1205.47
END DESCRIPTION:
XS GIS Cut Line= 3
      2735585.16      6811645.23      2735575.60      6811971.86
      2735626.20      6812241.48
#Sta/Elev= 30
  4678.9  385.15  4704.7  383.26  4714.7  382.15  4764.7  378.73  4794.7  376.08
  4820.4  373.13  4864.8  369.42  4920.1  365.97  4984.8  364.94  4994.8  363.51
  5000.7  362.08  5001.0  361.58  5004.5  361.58  5004.7  362.08  5007.8  362.08
  5015.0  362.96  5025.1  362.62  5032.6  363.99  5037.7  365.67  5045.5  366.07
  5055.7  365.91  5076.0  366.33  5126.9  368.17  5187.9  372.09  5195.3  372.90
  5200.4  372.74  5244.6  375.73  5253.0  376.33  5259.2  377.41  5280.0  378.65
#Mann=5,-1,0
  4678.9    0.05       0  4920.1    0.16       0  5000.7    0.07       0
  5004.7    0.16       0  5244.6    0.05       0
Bank Sta=5000.7,5004.7
Exp/Cntr=0.3,0.1

Type RM Length L Ch R = 1,1012,255,255,255
BEGIN DESCRIPTION:
South Twin Creek Trib D1012.06
END DESCRIPTION:
XS GIS Cut Line= 3
      2735521.07      6811635.02      2735412.11      6811967.99
      2735586.36      6812294.68
#Sta/Elev= 30
  4656.3  382.59  4683.5  381.53  4688.8  381.01  4715.2  380.30  4746.8  377.70
  4767.8  374.97  4799.4  371.80  4862.5  367.00  4894.1  365.26  4936.2  363.84
  4999.3  363.52  5034.7  363.79  5055.4  363.76  5064.5  362.55  5068.2  361.24
  5068.5  360.74  5072.0  360.74  5072.2  361.24  5078.1  362.73  5086.5  363.88
  5100.7  363.92  5136.1  365.55  5152.4  366.85  5174.3  367.71  5225.4  370.82
  5240.2  371.06  5317.3  376.08  5322.4  376.64  5350.1  377.80  5376.9  378.36
#Mann=5,-1,0
  4656.3    0.05       0  5034.7    0.16       0  5068.2    0.05       0
  5072.2    0.16       0  5317.3    0.05       0
Bank Sta=5068.2,5072.2
Exp/Cntr=0.3,0.1

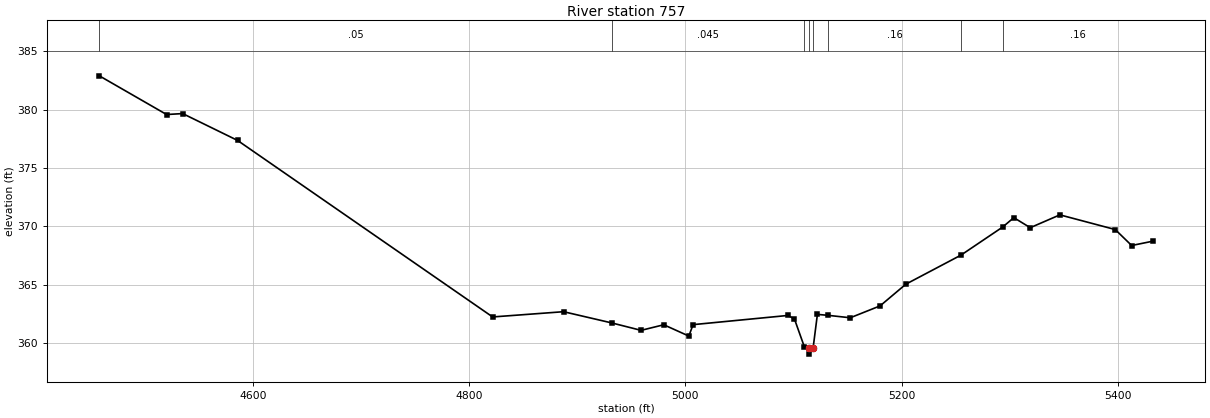
Type RM Length L Ch R = 1,757,0,0,0
BEGIN DESCRIPTION:
South Twin Creek Trib D757.093
END DESCRIPTION:
XS GIS Cut Line= 3
      2735494.95      6811512.91      2735187.53      6811959.41
      2735420.98      6812323.26
#Sta/Elev= 30
  4457.9  382.91  4520.1  379.59  4535.0  379.67  4585.7  377.37  4821.7  362.22
  4887.3  362.67  4932.2  361.70  4959.0  361.07  4980.0  361.55  5003.2  360.58
  5007.1  361.56  5095.0  362.35  5100.9  362.04  5110.1  359.64  5114.1  359.53
  5114.4  359.03  5118.1  359.53  5122.1  362.44  5131.8  362.36  5152.5  362.15
  5180.1  363.17  5203.9  365.03  5255.0  367.53  5293.4  369.93  5303.8  370.74
  5319.0  369.88  5346.4  370.98  5397.6  369.72  5412.8  368.35  5432.3  368.72
#Mann=8,-1,0
  4457.9    0.05       0  4932.2   0.045       0  5110.1    0.05       0
  5114.1   0.045       0  5118.1    0.05       0  5131.8    0.16       0
  5255.0    0.12       0  5293.4    0.16       0
Bank Sta=5114.1,5118.1
Exp/Cntr=0.3,0.1

Chan Stop Cuts=-1