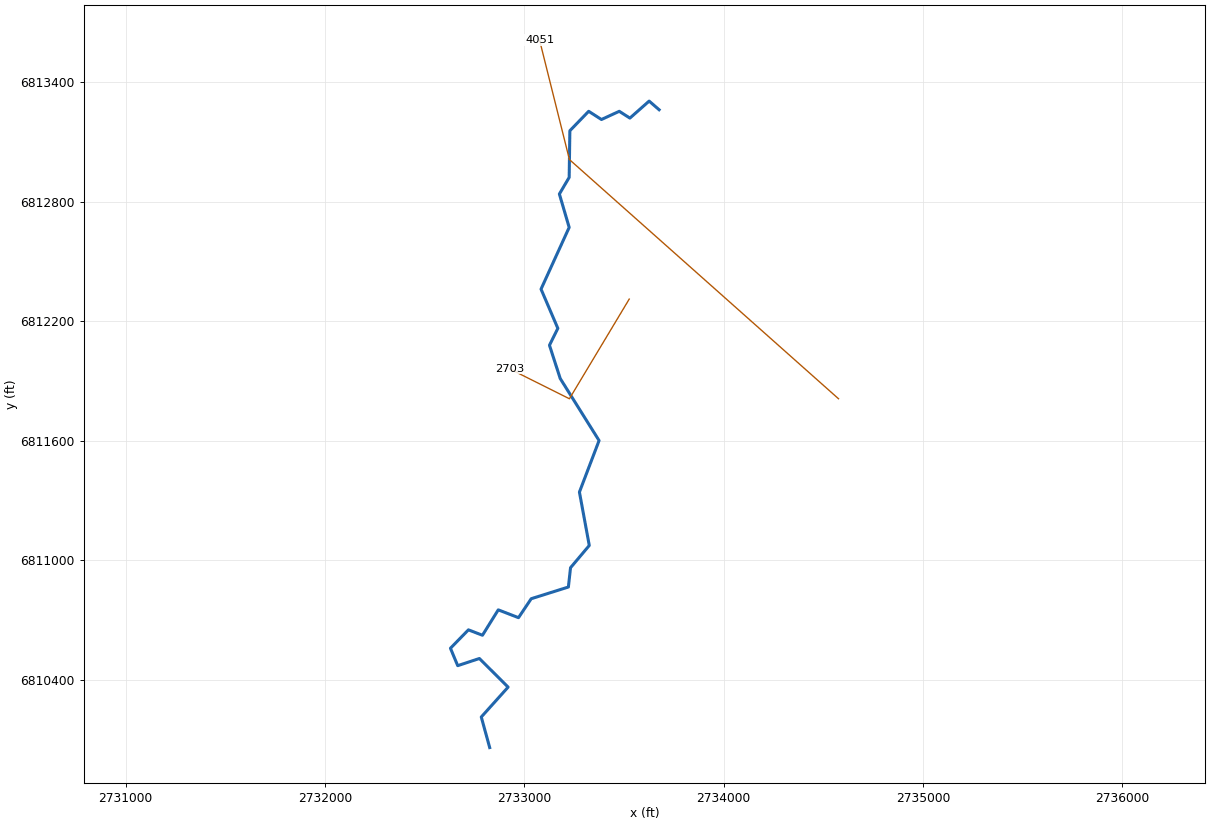
--- South Twin Creek Trib E.prj (project) ---

Proj Title=South Twin Creek Trib E Base Level Engineering
Current Plan=p01
Default Exp/Contr=0.3,0.1
English Units
Geom File=g01
Flow File=f01
Plan File=p01
BEGIN DESCRIPTION:
South Twin Creek Trib E
END DESCRIPTION:

--- South Twin Creek Trib E.p01 (plan) ---

Plan Title=Multiple Run
Short Identifier=Multiple
Geom File=g01
Flow File=f01
Subcritical Flow
K Sum by GR= 0
Std Step Tol= 0.01
Critical Tol= 0.01
Num of Std Step Trials= 20
Max Error Tol= 0.3
Flow Tol Ratio= 0.001
Split Flow NTrial= 30
Split Flow Tol= 0.02
Split Flow Ratio= 0.02
Log Output Level= 0
Friction Slope Method= 1
Unsteady Friction Slope Method= 2
Unsteady Bridges Friction Slope Method= 1
Parabolic Critical Depth
Global Vel Dist=  1 , 1 , 1
Global Log Level= 0
CheckData=True
Encroach Param= -1, 0, 0, 0
BEGIN DESCRIPTION:
Multiple Run
END DESCRIPTION:

--- South Twin Creek Trib E.f01 (steady flow) ---

Flow Title=Multiple
Number of Profiles=7
Profile Names=10-year,25-year,50-year,1pct_min,100-year,1pct_plu,500-year
River Rch & RM= South Twin Creek,Reach-1,4051
     167     205     233     132     264     527     337
Boundary for River Rch & Prof#=South Twin Creek,Reach-1,1
Up Type=0
Dn Type=3
Dn Slope=0.005
Boundary for River Rch & Prof#=South Twin Creek,Reach-1,2
Up Type=0
Dn Type=3
Dn Slope=0.005
Boundary for River Rch & Prof#=South Twin Creek,Reach-1,3
Up Type=0
Dn Type=3
Dn Slope=0.005
Boundary for River Rch & Prof#=South Twin Creek,Reach-1,4
Up Type=0
Dn Type=3
Dn Slope=0.005
Boundary for River Rch & Prof#=South Twin Creek,Reach-1,5
Up Type=0
Dn Type=3
Dn Slope=0.005
Boundary for River Rch & Prof#=South Twin Creek,Reach-1,6
Up Type=0
Dn Type=3
Dn Slope=0.005
Boundary for River Rch & Prof#=South Twin Creek,Reach-1,7
Up Type=0
Dn Type=3
Dn Slope=0.005

--- South Twin Creek Trib E.g01 (geometry) ---

Geom Title=Existing Conditions

River Reach=South Twin Creek,Reach-1
Reach XY= 30
      2733676.00      6813261.00      2733626.00      6813304.39
      2733529.34      6813219.01      2733476.09      6813253.16
      2733386.64      6813211.99      2733322.58      6813253.19
      2733228.17      6813155.58      2733224.76      6812921.50
      2733175.62      6812838.19      2733224.75      6812670.70
      2733083.56      6812361.00      2733167.90      6812164.29
      2733125.89      6812079.46      2733179.82      6811912.58
      2733374.75      6811601.30      2733276.18      6811342.73
      2733325.59      6811074.92      2733231.56      6810963.36
      2733220.75      6810866.44      2733034.35      6810807.81
      2732970.53      6810712.72      2732868.99      6810751.96
      2732789.68      6810624.51      2732719.32      6810651.70
      2732629.10      6810559.31      2732665.51      6810471.98
      2732774.35      6810507.84      2732918.41      6810364.33
      2732783.76      6810214.42      2732826.00      6810061.00

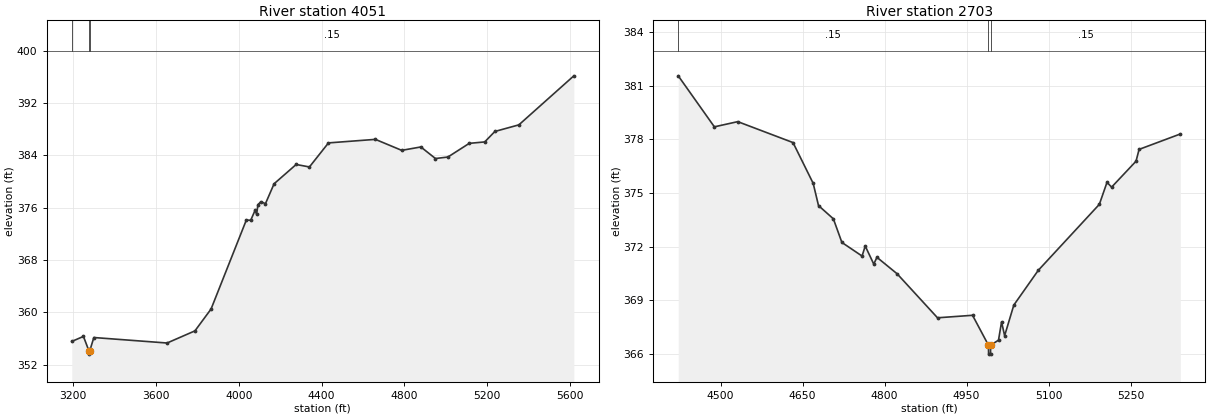
Type RM Length L Ch R = 1,4051,1348,1348,1348
BEGIN DESCRIPTION:
South Twin Creek Trib E 2.0
END DESCRIPTION:
XS GIS Cut Line= 3
      2734575.97      6811811.03      2733226.00      6813011.00
      2733075.99      6813611.03
#Sta/Elev= 30
  3193.9  355.53  3250.3  356.30  3276.7  354.09  3277.0  353.59  3280.7  354.09
  3300.5  356.13  3654.2  355.29  3788.8  357.15  3866.6  360.49  4036.8  374.09
  4058.1  374.07  4079.0  375.57  4086.5  375.00  4093.2  376.46  4107.4  376.91
  4129.2  376.60  4171.0  379.65  4277.6  382.60  4341.6  382.22  4433.6  385.90
  4660.2  386.44  4787.3  384.76  4879.7  385.28  4950.3  383.51  5010.4  383.74
  5113.5  385.83  5188.2  386.05  5237.2  387.65  5353.1  388.66  5618.6  396.16
#Mann=3,-1,0
  3193.9    0.15       0  3276.7    0.05       0  3280.7    0.15       0
Bank Sta=3276.7,3280.7
Exp/Cntr=0.3,0.1

Type RM Length L Ch R = 1,2703,0,0,0
BEGIN DESCRIPTION:
South Twin Creek Trib E 1.0
END DESCRIPTION:
XS GIS Cut Line= 3
      2733526.02      6812311.04      2733226.00      6811811.00
      2732926.04      6811960.98
#Sta/Elev= 30
  4422.5  381.55  4488.6  378.70  4531.4  378.99  4632.5  377.82  4669.4  375.54
  4679.1  374.30  4706.3  373.56  4721.9  372.24  4758.8  371.48  4764.6  372.04
  4780.2  371.03  4786.0  371.41  4822.9  370.49  4896.8  368.03  4960.9  368.17
  4990.0  366.50  4990.3  366.00  4993.8  366.00  4994.0  366.50  5008.4  366.78
  5014.0  367.80  5019.6  367.03  5036.4  368.74  5081.1  370.68  5192.9  374.37
  5206.9  375.60  5215.3  375.33  5260.0  376.78  5265.6  377.44  5341.0  378.30
#Mann=3,-1,0
  4422.5    0.15       0  4990.0    0.05       0  4994.0    0.15       0
Bank Sta=4990,4994
Exp/Cntr=0.3,0.1

Chan Stop Cuts=-1