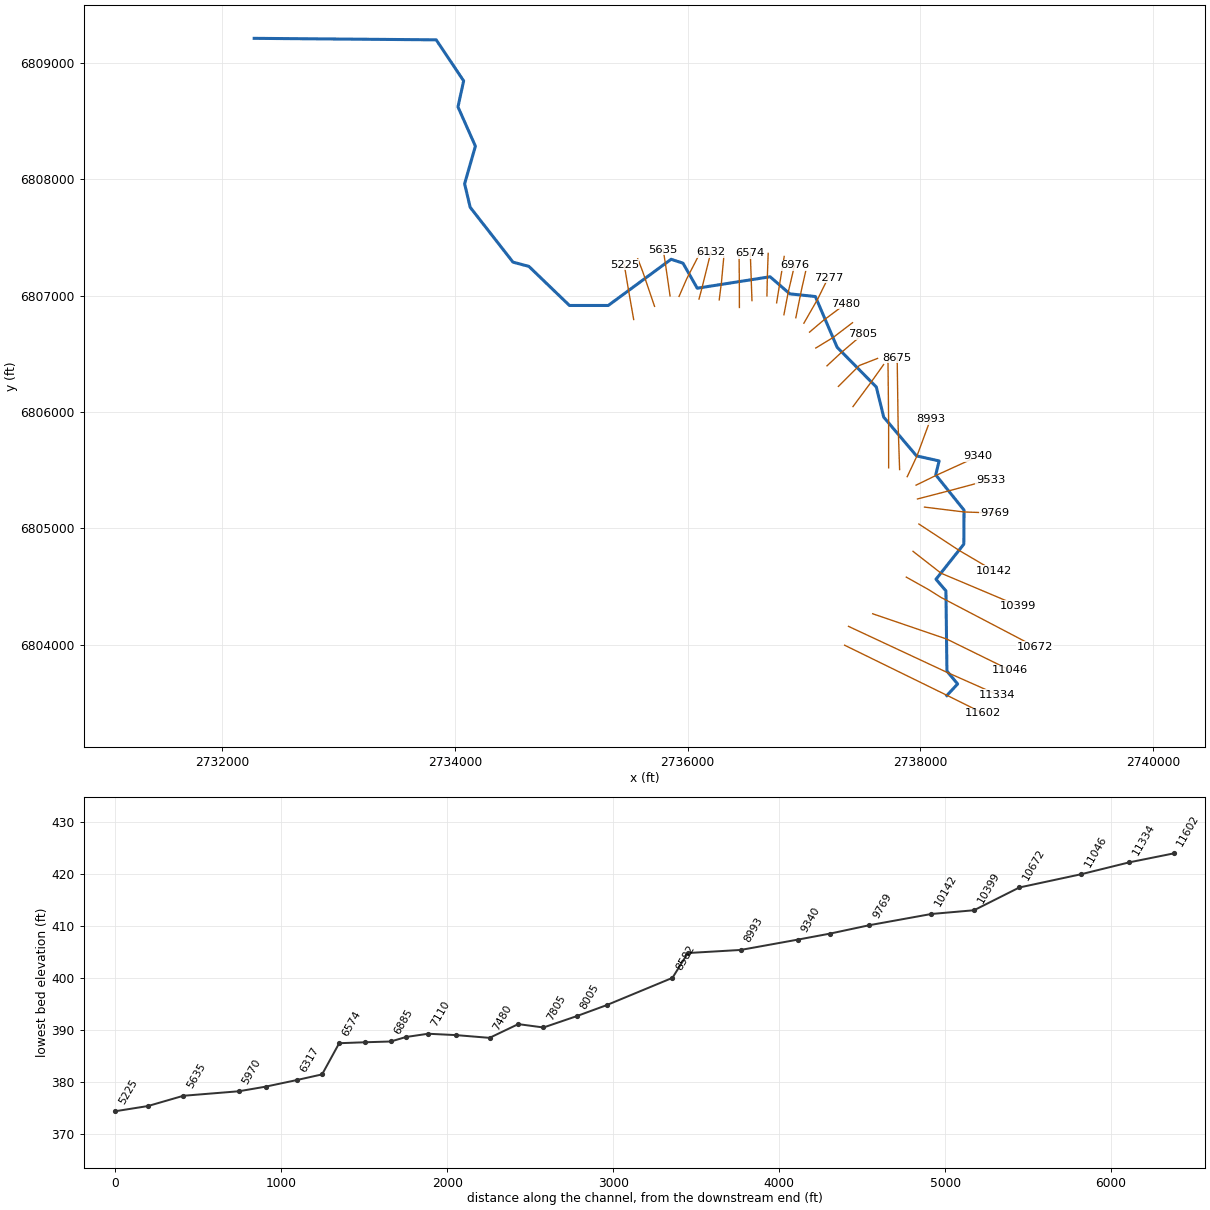
--- South Twin Creek Trib F.prj (project) ---

Proj Title=South Twin Creek Trib F Base Level Engineering
Current Plan=p01
Default Exp/Contr=0.3,0.1
English Units
Geom File=g01
Flow File=f01
Plan File=p01
Y Axis Title=Elevation
X Axis Title(PF)=Main Channel Distance
X Axis Title(XS)=Station
BEGIN DESCRIPTION:
South Twin Creek Trib F
END DESCRIPTION:
DSS Export Rating Curves= 0
DSS Export Rating Curve Sorted= 0
DSS Export Volume Flow Curves= 0
DXF OffsetX= 0
DXF OffsetY= 0
DXF ScaleX= 1
DXF ScaleY= 10

--- South Twin Creek Trib F.p01 (plan) ---

Plan Title=Multiple Run
Short Identifier=Multiple
Geom File=g01
Flow File=f01
Subcritical Flow
K Sum by GR= 0
Std Step Tol= 0.01
Critical Tol= 0.01
Num of Std Step Trials= 20
Max Error Tol= 0.3
Flow Tol Ratio= 0.001
Split Flow NTrial= 30
Split Flow Tol= 0.02
Split Flow Ratio= 0.02
Log Output Level= 0
Friction Slope Method= 1
Unsteady Friction Slope Method= 2
Unsteady Bridges Friction Slope Method= 1
Parabolic Critical Depth
Global Vel Dist=  1 , 1 , 1
Global Log Level= 0
CheckData=True
Encroach Param= -1, 0, 0, 0
BEGIN DESCRIPTION:
Multiple Run
END DESCRIPTION:

--- South Twin Creek Trib F.f01 (steady flow) ---

Flow Title=Multiple
Number of Profiles=7
Profile Names=10-year,25-year,50-year,1pct_min,100-year,1pct_plu,500-year
River Rch & RM= South Twin Creek,Reach-1,11602
     416     545     647     382     761    1519    1054
River Rch & RM= South Twin Creek,Reach-1,3965
     692     935    1133     681    1359    2711    1953
Boundary for River Rch & Prof#=South Twin Creek,Reach-1,1
Up Type=0
Dn Type=3
Dn Slope=0.005
Boundary for River Rch & Prof#=South Twin Creek,Reach-1,2
Up Type=0
Dn Type=3
Dn Slope=0.005
Boundary for River Rch & Prof#=South Twin Creek,Reach-1,3
Up Type=0
Dn Type=3
Dn Slope=0.005
Boundary for River Rch & Prof#=South Twin Creek,Reach-1,4
Up Type=0
Dn Type=3
Dn Slope=0.005
Boundary for River Rch & Prof#=South Twin Creek,Reach-1,5
Up Type=0
Dn Type=3
Dn Slope=0.005
Boundary for River Rch & Prof#=South Twin Creek,Reach-1,6
Up Type=0
Dn Type=3
Dn Slope=0.005
Boundary for River Rch & Prof#=South Twin Creek,Reach-1,7
Up Type=0
Dn Type=3
Dn Slope=0.005

--- South Twin Creek Trib F.g01 (geometry) ---

Geom Title=Existing Conditions
Program Version=4.10

River Reach=South Twin Creek,Reach-1
Reach XY= 30
        2738226.        6803561.      2738319.02      6803660.99
      2738227.06      6803771.43      2738218.63      6804461.09
       2738133.1        6804561.      2738372.32      6804862.59
      2738374.03      6805155.11      2738131.05      6805458.48
      2738159.89      6805578.17      2737965.88      6805621.35
      2737684.02      6805954.66      2737620.53      6806213.45
      2737284.13      6806554.93      2737096.58      6806991.43
      2736877.71      6807014.36      2736707.73      6807161.34
      2736081.88      6807062.96      2735959.72      6807278.23
      2735857.52      6807311.69      2735317.54      6806914.46
      2734984.44       6806914.4      2734635.79      6807250.48
      2734499.13      6807287.18      2734131.48      6807758.56
      2734083.56        6807961.      2734176.47      6808283.89
       2734026.6      6808621.62      2734075.34      6808845.15
      2733839.63      6809198.05        2732276.        6809211.

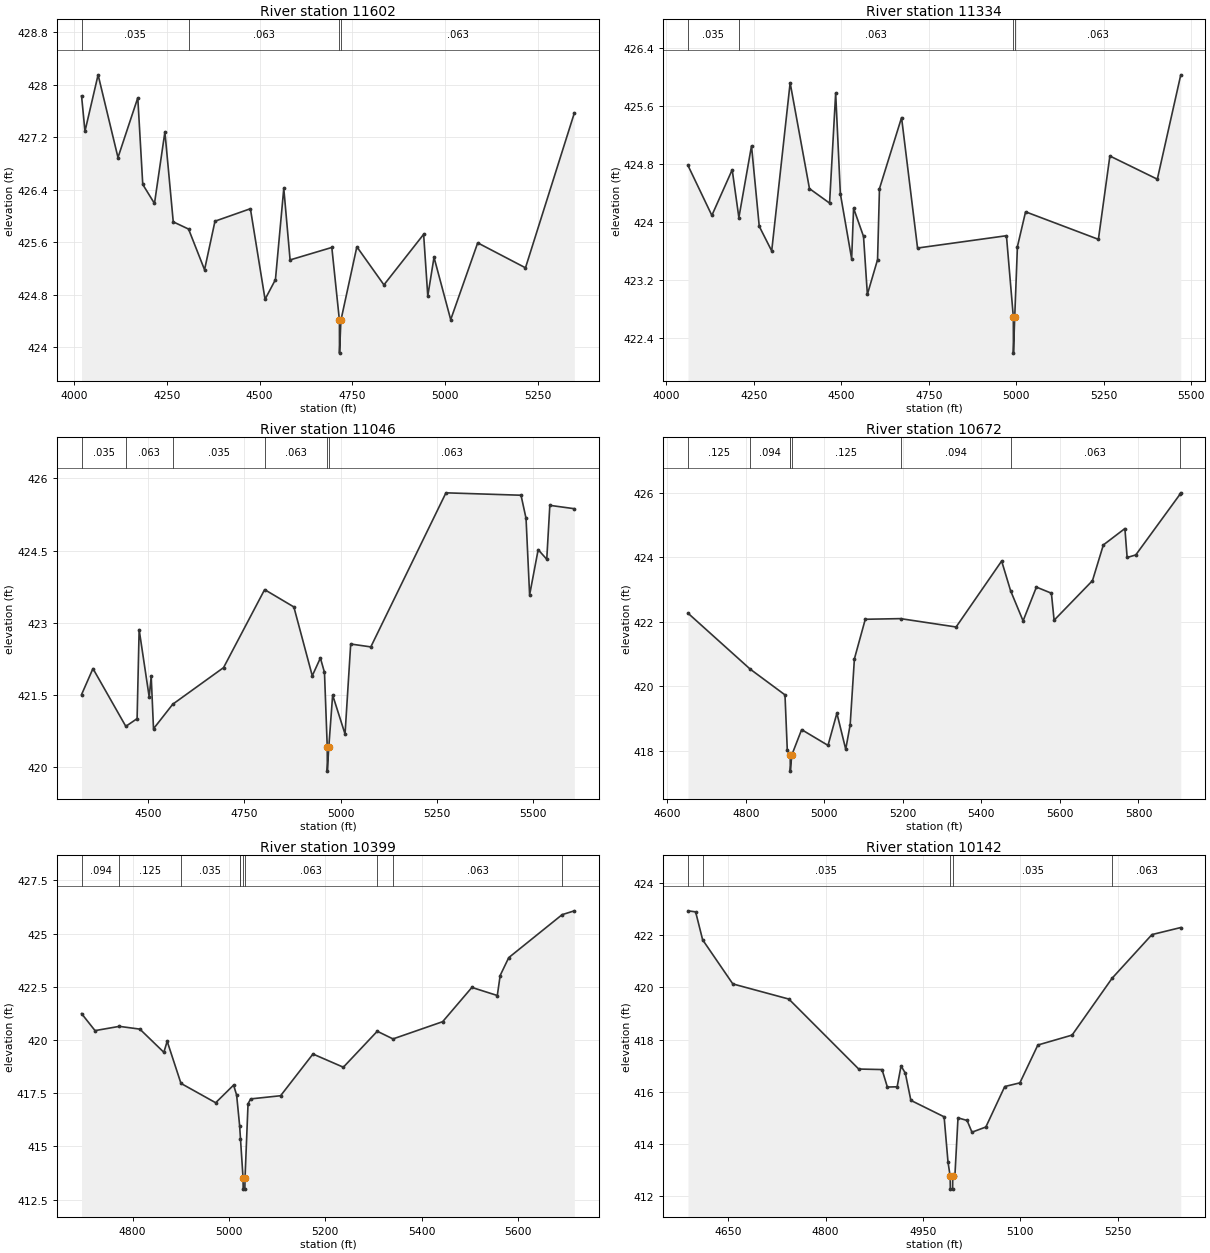
Type RM Length L Ch R = 1 ,11602   ,268,268,268
BEGIN DESCRIPTION:
South Twin Creek Trib F11601.99
END DESCRIPTION:
XS GIS Cut Line= 3
      2737347.78      6803994.11      2738227.93      6803562.91
      2738540.07      6803407.92
#Sta/Elev= 30
  4019.9  427.83  4029.1  427.29  4064.5  428.15  4118.1  426.89  4171.5   427.8
  4184.9  426.48  4216.5  426.19  4244.6  427.28  4267.1  425.91  4308.4   425.8
  4351.5  425.18  4379.6  425.92  4475.1  426.11  4514.6  424.73  4542.6  425.03
  4565.1  426.42  4582.1  425.33  4694.6  425.52  4715.1  424.41  4715.3  423.91
  4719.1  424.41  4762.1  425.53  4835.1  424.95  4942.1  425.72  4953.3  424.78
  4970.1  425.37  5015.1  424.42  5087.9  425.59  5216.7  425.21  5348.5  427.57
#Mann= 4 ,-1 , 0
  4019.9    .035       0  4308.4    .063       0  4715.1    .063       0
  4719.1    .063       0
Bank Sta=4715.1,4719.1
XS Rating Curve= 0 ,0
Exp/Cntr=0.3,0.1

Type RM Length L Ch R = 1 ,11334   ,288,288,288
BEGIN DESCRIPTION:
South Twin Creek Trib F11334.46
END DESCRIPTION:
XS GIS Cut Line= 3
      2737381.45      6804155.97      2738230.34      6803759.38
      2738661.23      6803568.36
#Sta/Elev= 30
    4062  424.78  4130.3  424.09  4188.4  424.72  4207.5  424.06  4243.6  425.05
  4265.7  423.94  4301.3   423.6    4354  425.92  4409.2  424.46  4466.7  424.26
  4484.1  425.78  4497.5  424.39  4529.8  423.49  4535.3  424.19  4563.7   423.8
  4574.7     423  4603.8  423.48  4609.3  424.46  4672.4  425.44  4718.1  423.64
  4972.1  423.81  4991.8  422.69  4992.1  422.19  4995.8  422.69  5003.5  423.66
  5026.8  424.14  5234.9  423.76  5267.7  424.91  5403.3  424.59  5470.3  426.03
#Mann= 4 ,-1 , 0
    4062    .035       0  4207.5    .063       0  4991.8    .063       0
  4995.8    .063       0
Bank Sta=4991.8,4995.8
XS Rating Curve= 0 ,0
Exp/Cntr=0.3,0.1

Type RM Length L Ch R = 1 ,11046   ,374,374,374
BEGIN DESCRIPTION:
South Twin Creek Trib F11046.1
END DESCRIPTION:
XS GIS Cut Line= 3
      2737589.21      6804264.28      2738225.71      6804046.63
      2738770.33      6803779.01
#Sta/Elev= 30
    4327  421.51  4356.6  422.05  4441.9  420.85  4471.2  421.01  4476.5  422.86
  4502.6  421.46  4507.8  421.89  4513.8   420.8  4563.8  421.31  4695.7  422.07
  4802.3  423.69  4878.2  423.33    4926   421.9  4947.1  422.27  4957.7  421.97
  4964.9  420.42  4965.1  419.92  4968.9  420.42  4978.9   421.5  5011.1  420.69
  5025.8  422.56    5078   422.5  5273.1   425.7    5468  425.65    5481  425.17
  5490.3  423.58  5512.5  424.52  5534.8  424.32  5542.8  425.44  5606.5  425.37
#Mann= 6 ,-1 , 0
    4327    .035       0  4441.9    .063       0  4563.8    .035       0
  4802.3    .063       0  4964.9    .063       0  4968.9    .063       0
Bank Sta=4964.9,4968.9
XS Rating Curve= 0 ,0
Exp/Cntr=0.3,0.1

Type RM Length L Ch R = 1 ,10672   ,273,273,273
BEGIN DESCRIPTION:
South Twin Creek Trib F10672.28
END DESCRIPTION:
XS GIS Cut Line= 4
        2737878.      6804579.23      2738070.12      6804471.49
      2738176.12      6804404.74      2738981.66      6803982.35
#Sta/Elev= 30
  4652.6  422.27  4811.1  420.53  4899.7  419.73  4905.6  418.01  4912.8  417.86
    4913  417.86  4913.3  417.36    4917  417.86  4942.1  418.65  5009.3  418.16
  5031.9  419.16  5054.4  418.04  5065.7   418.8  5076.5  420.85  5104.2  422.08
    5194   422.1  5335.5  421.84  5451.5  423.89  5474.2  422.97  5506.1  422.03
    5540  423.08  5578.2  422.89  5585.1  422.05  5682.8  423.28  5710.5  424.39
  5765.4   424.9  5771.1     424  5793.1  424.08  5905.4  425.96  5907.7  426.01
#Mann= 8 ,-1 , 0
  4652.6    .125       0  4811.1    .094       0  4912.8    .125       0
    4913     .07       0    4917    .125       0    5194    .094       0
  5474.2    .063       0  5905.4    .094       0
Bank Sta=4913,4917
XS Rating Curve= 0 ,0
Exp/Cntr=0.3,0.1

Type RM Length L Ch R = 1 ,10399   ,257,257,257
BEGIN DESCRIPTION:
South Twin Creek Trib F10398.78
END DESCRIPTION:
XS GIS Cut Line= 3
      2737935.85       6804800.8      2738177.08      6804612.57
      2738837.94       6804333.6
#Sta/Elev= 30
    4694  421.24    4722  420.44  4772.5  420.64  4815.1  420.51  4864.9  419.42
  4871.8  419.94  4900.4  417.96  4972.5  417.05  5009.7  417.88    5016  417.41
  5022.2  415.98    5024  415.36  5029.4  413.49  5029.6  412.99  5033.1  412.99
  5033.4  413.49  5039.7     417  5045.1  417.23  5107.3  417.38  5174.5  419.34
  5237.6  418.72    5308  420.41  5340.7  420.05  5443.8  420.86  5504.5  422.47
  5557.3  422.09  5563.2  423.03    5581  423.87  5691.9  425.89  5717.3  426.07
#Mann= 10 ,-1 , 0
    4694    .094       0  4772.5    .125       0  4900.4    .035       0
  5022.2    .125       0    5024    .063       0  5029.4    .035       0
  5033.4    .063       0    5308    .035       0  5340.7    .063       0
  5691.9    .094       0
Bank Sta=5029.4,5033.4
XS Rating Curve= 0 ,0
Exp/Cntr=0.3,0.1

Type RM Length L Ch R = 1 ,10142   ,373,373,373
BEGIN DESCRIPTION:
South Twin Creek Trib F10141.65
END DESCRIPTION:
XS GIS Cut Line= 3
      2737986.14       6805035.8      2738329.75      6804810.16
       2738629.6      6804633.68
#Sta/Elev= 30
  4588.1  422.93  4599.9  422.89  4610.7  421.82  4657.2  420.13  4743.5  419.55
  4851.1  416.87    4887  416.85  4895.2  416.18  4910.3  416.19  4916.3  416.99
  4922.9  416.71  4931.4  415.67  4982.6  415.04  4988.6  413.31  4991.9  412.77
  4992.2  412.27  4995.7  412.27  4995.9  412.77  4999.2  412.77    5004     415
    5018   414.9  5025.5  414.45  5046.9  414.65    5076   416.2  5099.3  416.34
    5127  417.79  5179.7  418.17  5241.4  420.35  5302.7  422.02  5347.1  422.29
#Mann= 5 ,-1 , 0
  4588.1    .063       0  4610.7    .035       0  4991.9    .035       0
  4995.9    .035       0  5241.4    .063       0
Bank Sta=4991.9,4995.9
XS Rating Curve= 0 ,0
Exp/Cntr=0.3,0.1

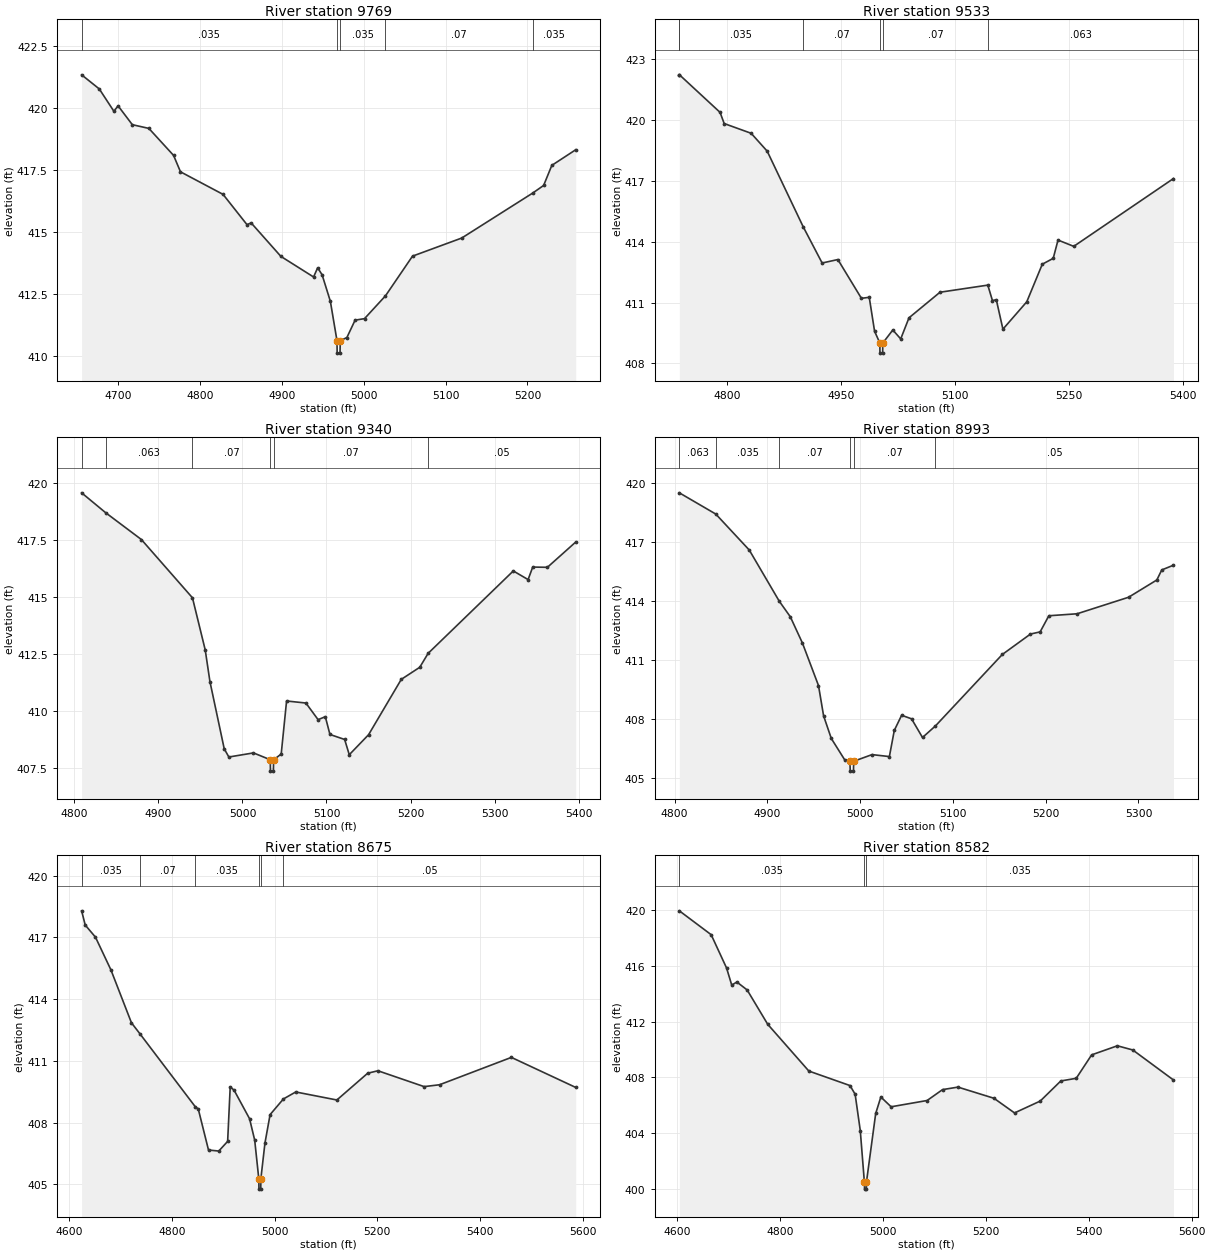
Type RM Length L Ch R = 1 ,9769    ,236,236,236
BEGIN DESCRIPTION:
South Twin Creek Trib F9768.5
END DESCRIPTION:
XS GIS Cut Line= 3
      2738034.56      6805181.15      2738373.84       6805139.4
      2738635.15      6805130.45
#Sta/Elev= 30
  4655.7  421.34  4677.3  420.77  4695.1  419.87  4700.2  420.09  4717.6  419.33
  4737.8  419.18    4768  418.09  4776.4  417.43  4828.4  416.52  4857.6   415.3
  4862.7  415.37    4899  414.02  4938.9  413.19  4943.9  413.56  4949.3  413.28
  4959.4  412.21  4967.5  410.62  4967.7  410.12  4971.2  410.12  4971.5  410.62
  4979.6  410.75  4989.6  411.45  5001.1  411.51  5026.7  412.43  5059.7  414.03
  5119.8  414.76  5206.3  416.57  5219.8  416.88  5229.8  417.69    5259  418.32
#Mann= 5 ,-1 , 0
  4655.7    .035       0  4967.5    .035       0  4971.5    .035       0
  5026.7     .07       0  5206.3    .035       0
Bank Sta=4967.5,4971.5
XS Rating Curve= 0 ,0
Exp/Cntr=0.3,0.1

Type RM Length L Ch R = 1 ,9533    ,193,193,193
BEGIN DESCRIPTION:
South Twin Creek Trib F9533.11
END DESCRIPTION:
XS GIS Cut Line= 3
       2737974.1      6805251.14      2738231.73      6805317.87
      2738602.73      6805417.19
#Sta/Elev= 30
  4737.5  422.22  4737.7  422.22  4791.1  420.37  4796.5  419.82    4832  419.34
  4853.1  418.46  4900.4  414.74  4925.4  412.95  4946.1  413.12  4977.1  411.21
  4987.4  411.26  4994.4  409.59  5001.3  409.01  5001.5  408.51    5005  408.51
  5005.3  409.01  5018.4  409.65  5028.8  409.21  5039.7  410.25  5080.5  411.51
  5143.4  411.86  5149.5   411.1  5154.6  411.14  5163.3  409.69  5194.7  411.04
  5215.1  412.89  5229.5  413.18  5235.8  414.08  5256.5  413.77  5387.7  417.11
#Mann= 6 ,-1 , 0
  4737.5    .063       0  4737.7    .035       0  4900.4     .07       0
  5001.3     .07       0  5005.3     .07       0  5143.4    .063       0
Bank Sta=5001.3,5005.3
XS Rating Curve= 0 ,0
Exp/Cntr=0.3,0.1

Type RM Length L Ch R = 1 ,9340    ,347,347,347
BEGIN DESCRIPTION:
South Twin Creek Trib F9339.91
END DESCRIPTION:
XS GIS Cut Line= 3
      2737962.06       6805369.9      2738134.74      6805454.11
      2738494.86      6805618.53
#Sta/Elev= 30
  4808.6  419.58  4837.1  418.71  4879.7  417.53  4940.5  414.97  4955.7  412.68
  4961.3  411.29  4978.3  408.34  4983.8  407.98  5013.1  408.16  5033.1  407.86
  5033.3  407.36  5036.8  407.36  5037.1  407.86  5046.1  408.11  5052.5  410.44
  5075.5  410.35    5090  409.62  5098.6  409.75  5104.1  408.97  5121.6  408.75
  5127.1  408.08  5150.1  408.96    5189  411.39    5211  411.92  5220.9  412.53
  5322.3  416.15  5339.9  415.77  5345.4  416.32  5362.9  416.31  5396.6  417.42
#Mann= 6 ,-1 , 0
  4808.6    .035       0  4837.1    .063       0  4940.5     .07       0
  5033.1     .07       0  5037.1     .07       0  5220.9     .05       0
Bank Sta=5033.1,5037.1
XS Rating Curve= 0 ,0
Exp/Cntr=0.3,0.1

Type RM Length L Ch R = 1 ,8993    ,318,318,318
BEGIN DESCRIPTION:
South Twin Creek Trib F8992.9
END DESCRIPTION:
XS GIS Cut Line= 3
      2737886.03      6805442.73      2737970.01      6805621.33
       2738086.1      6805935.83
#Sta/Elev= 30
  4805.1  419.51  4844.4  418.43  4880.5   416.6  4912.8     414  4924.7  413.21
  4937.8  411.87  4955.1  409.71  4960.6  408.17  4968.9  407.02  4983.4  405.93
    4989  405.86  4989.3  405.36  4992.8  405.36    4993  405.86  5012.8   406.2
  5031.5   406.1  5036.8  407.43  5044.7   408.2  5055.4  408.02  5067.2  407.07
  5081.2  407.66  5153.2  411.29  5183.6  412.33    5194  412.44  5203.4  413.26
  5233.8  413.36  5289.3   414.2  5319.8  415.08  5325.1  415.59  5337.7  415.83
#Mann= 6 ,-1 , 0
  4805.1    .063       0  4844.4    .035       0  4912.8     .07       0
    4989     .07       0    4993     .07       0  5081.2     .05       0
Bank Sta=4989,4993
XS Rating Curve= 0 ,0
Exp/Cntr=0.3,0.1

Type RM Length L Ch R = 1 ,8675    ,93,93,93
BEGIN DESCRIPTION:
South Twin Creek Trib F8674.83
END DESCRIPTION:
XS GIS Cut Line= 3
      2737820.58      6805503.97      2737807.93      6805882.49
       2737799.6       6806466.4
#Sta/Elev= 30
  4624.1  418.29  4631.1   417.6  4651.1  417.01  4681.2  415.42  4721.2  412.85
  4737.9  412.31  4845.9  408.76  4851.3  408.67  4871.3  406.67  4891.3  406.62
  4908.6  407.09  4913.6  409.74  4921.3  409.57  4951.3  408.19  4961.3  407.15
  4969.3  405.27  4969.6  404.77  4973.1  404.77  4973.3  405.27  4981.3  407.01
  4991.3  408.39  5017.2  409.15  5041.3  409.49  5121.4   409.1  5181.4   410.4
  5201.4  410.52  5291.4  409.75  5321.4  409.84  5461.4  411.17  5586.8  409.71
#Mann= 6 ,-1 , 0
  4624.1    .035       0  4737.9     .07       0  4845.9    .035       0
  4969.3    .035       0  4973.3    .035       0  5017.2     .05       0
Bank Sta=4969.3,4973.3
XS Rating Curve= 0 ,0
Exp/Cntr=0.3,0.1

Type RM Length L Ch R = 1 ,8582    ,397,397,397
BEGIN DESCRIPTION:
South Twin Creek Trib F8581.98
END DESCRIPTION:
XS GIS Cut Line= 3
      2737726.47      6805519.08      2737726.22      6805917.35
      2737720.23      6806480.05
#Sta/Elev= 30
  4603.6  419.94  4665.5  418.23  4695.5  415.84  4705.5  414.62  4715.5  414.84
  4735.5  414.27  4775.5  411.81  4855.5  408.46  4935.5  407.42  4945.5   406.8
  4955.5   404.2  4963.5   400.5  4963.8     400  4967.3     400  4967.5   400.5
  4985.5  405.42  4995.5   406.6  5015.5   405.9  5085.5  406.35  5115.5  407.13
  5145.5  407.31  5215.5  406.51  5255.5  405.46  5305.5  406.31  5345.5  407.75
  5375.5  407.94  5405.5  409.62  5455.5  410.27  5485.5  409.97  5564.6  407.82
#Mann= 3 ,-1 , 0
  4603.6    .035       0  4963.5    .035       0  4967.5    .035       0
Bank Sta=4963.5,4967.5
XS Rating Curve= 0 ,0
Exp/Cntr=0.3,0.1

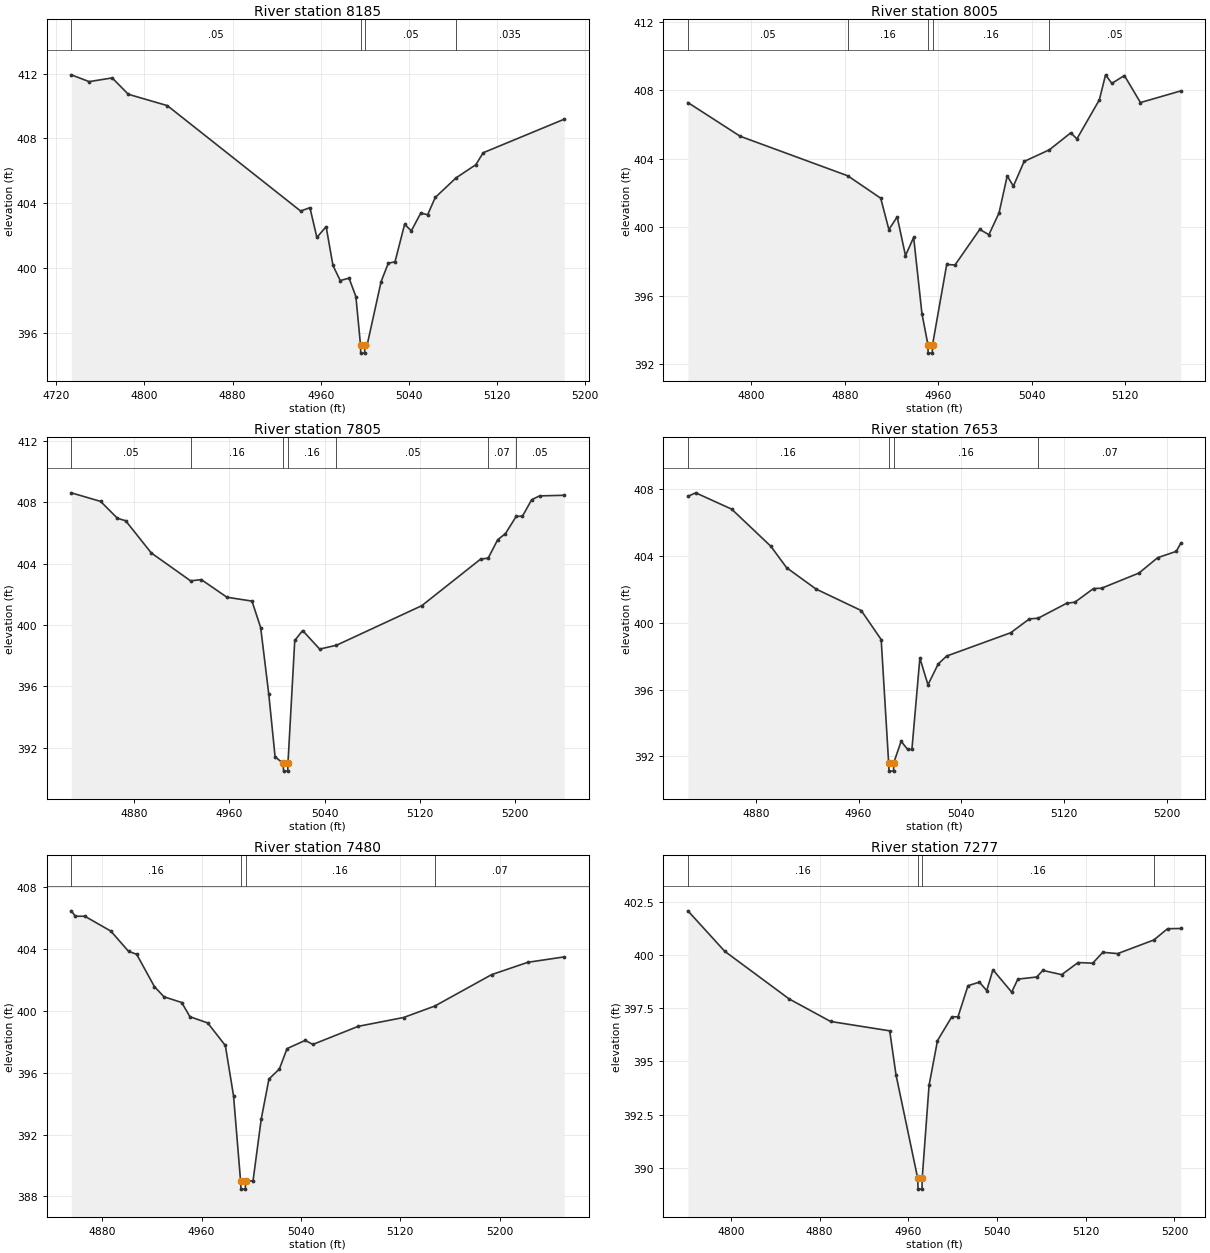
Type RM Length L Ch R = 1 ,8185    ,180,180,180
BEGIN DESCRIPTION:
South Twin Creek Trib F8184.82
END DESCRIPTION:
XS GIS Cut Line= 3
      2737419.79      6806045.06      2737578.35      6806258.83
      2737683.31      6806406.35
#Sta/Elev= 30
  4733.7  411.93  4749.9  411.51  4770.8  411.74  4785.4  410.73  4820.8  410.03
  4941.8  403.52  4950.2  403.73  4956.5  401.89  4964.9  402.56  4971.1  400.16
  4977.7  399.23  4985.7  399.38  4991.9  398.24  4996.1  395.25  4996.3  394.75
  4999.8  394.75  5000.1  395.25  5002.1  395.25  5014.8  399.17  5021.3   400.3
  5027.4  400.39  5036.1   402.7  5042.2   402.3  5050.8   403.4    5057  403.29
  5063.9  404.36  5082.8  405.57  5100.7  406.38  5107.4  407.12  5180.9  409.19
#Mann= 4 ,-1 , 0
  4733.7     .05       0  4996.1     .05       0  5000.1     .05       0
  5082.8    .035       0
Bank Sta=4996.1,5000.1
XS Rating Curve= 0 ,0
Exp/Cntr=0.3,0.1

Type RM Length L Ch R = 1 ,8005    ,200,200,200
BEGIN DESCRIPTION:
South Twin Creek Trib F8005.04
END DESCRIPTION:
XS GIS Cut Line= 3
      2737294.71      6806218.86      2737474.67      6806398.49
      2737630.97      6806459.35
#Sta/Elev= 30
  4745.6  407.28  4790.4  405.31  4882.5     403  4910.7  401.69  4917.7  399.86
  4924.8   400.6  4931.9  398.34  4938.9   399.4    4946  394.95  4951.1  393.14
  4951.3  392.64  4954.8  392.64  4955.1  393.14  4967.2  397.82  4974.3  397.79
  4995.5  399.87  5003.3  399.56    5012  400.83    5019  402.99  5024.3   402.4
  5033.5  403.84  5055.1  404.52  5073.4  405.51  5078.7  405.16  5097.9  407.44
  5103.2   408.9  5108.6   408.4  5119.3  408.86  5133.1  407.28  5167.6  407.96
#Mann= 5 ,-1 , 0
  4745.6     .05       0  4882.5     .16       0  4951.1     .07       0
  4955.1     .16       0  5055.1     .05       0
Bank Sta=4951.1,4955.1
XS Rating Curve= 0 ,0
Exp/Cntr=0.3,0.1

Type RM Length L Ch R = 1 ,7805    ,152,152,152
BEGIN DESCRIPTION:
South Twin Creek Trib F7804.6
END DESCRIPTION:
XS GIS Cut Line= 3
      2737196.77      6806395.79      2737323.06      6806513.09
      2737506.82      6806669.38
#Sta/Elev= 30
  4827.5  408.61  4852.1  408.05  4866.2  406.95  4873.1  406.79  4894.6  404.69
  4927.6  402.87  4936.6  402.95  4958.1   401.8  4979.1  401.55  4986.4  399.82
  4993.2  395.48  4998.5   391.4  5005.3  390.96  5005.6  390.46  5009.1  390.46
  5009.3  390.96    5015  398.98  5021.6  399.63  5035.9  398.42    5050  398.67
  5121.6  401.25    5171  404.29  5177.3  404.35  5185.3  405.55  5191.8  405.95
  5200.8  407.07  5206.1  407.09  5213.8  408.16  5220.4  408.41  5241.1  408.45
#Mann= 7 ,-1 , 0
  4827.5     .05       0  4927.6     .16       0  5005.3     .07       0
  5009.3     .16       0    5050     .05       0  5177.3     .07       0
  5200.8     .05       0
Bank Sta=5005.3,5009.3
XS Rating Curve= 0 ,0
Exp/Cntr=0.3,0.1

Type RM Length L Ch R = 1 ,7653    ,173,173,173
BEGIN DESCRIPTION:
South Twin Creek Trib F7653.32
END DESCRIPTION:
XS GIS Cut Line= 3
      2737100.79      6806548.92      2737249.77      6806639.49
      2737416.03      6806766.39
#Sta/Elev= 30
  4827.2  407.59  4833.3   407.8  4861.3  406.82  4891.8  404.59    4904  403.31
  4926.9  402.03  4962.1  400.74  4977.6     399  4983.4  391.61  4983.7  391.11
  4987.2  391.11  4987.4  391.61  4993.1   392.9  4998.2  392.41  5001.5  392.41
  5007.7  397.89    5014  396.29    5022  397.54  5028.5  398.01  5078.4  399.41
  5092.9  400.24  5099.7  400.28    5122  401.18  5128.3  401.24  5142.8  402.06
  5149.1  402.08  5178.2  402.99  5192.7  403.91  5207.2  404.29  5210.7  404.78
#Mann= 4 ,-1 , 0
  4827.2     .16       0  4983.4     .07       0  4987.4     .16       0
  5099.7     .07       0
Bank Sta=4983.4,4987.4
XS Rating Curve= 0 ,0
Exp/Cntr=0.3,0.1

Type RM Length L Ch R = 1 ,7480    ,203,203,203
BEGIN DESCRIPTION:
South Twin Creek Trib F7479.65
END DESCRIPTION:
XS GIS Cut Line= 3
      2737046.85      6806685.34      2737158.19      6806780.19
      2737358.69      6806930.41
#Sta/Elev= 30
  4855.1  406.47  4858.3  406.12    4866  406.12  4886.9  405.16  4901.2  403.85
  4907.7  403.66    4922  401.57  4929.7  400.91    4944  400.54  4950.6  399.62
  4964.9  399.22  4979.1  397.76  4985.7  394.51  4991.4  388.97  4991.7  388.47
  4995.2  388.47  4995.4  388.97  5001.4  389.01    5008     393  5014.2  395.59
  5022.6  396.24  5028.8  397.56  5043.4  398.09  5049.6  397.83  5086.1     399
  5122.6  399.57  5147.7  400.31  5193.4  402.34  5222.6  403.14  5251.9  403.49
#Mann= 4 ,-1 , 0
  4855.1     .16       0  4991.4     .07       0  4995.4     .16       0
  5147.7     .07       0
Bank Sta=4991.4,4995.4
XS Rating Curve= 0 ,0
Exp/Cntr=0.3,0.1

Type RM Length L Ch R = 1 ,7277    ,167,167,167
BEGIN DESCRIPTION:
South Twin Creek Trib F7276.85
END DESCRIPTION:
XS GIS Cut Line= 3
      2736998.34      6806762.15        2737118.      6806971.47
      2737207.43      6807154.14
#Sta/Elev= 30
  4761.2  402.08  4794.4  400.18  4852.5  397.94  4889.9  396.88  4943.2  396.44
  4948.9  394.37  4968.5   389.5  4968.8     389  4972.3     389  4972.5   389.5
  4978.7  393.88  4986.3  395.98  4999.2   397.1  5004.8   397.1  5013.8  398.56
  5024.1  398.73  5030.7  398.33  5036.3  399.31  5053.2  398.26  5058.8  398.87
  5075.8  398.97  5081.3  399.28  5098.3  399.08  5113.1  399.65  5126.3  399.62
  5135.4  400.13  5148.8  400.07  5181.4  400.71  5193.8  401.24  5205.7  401.25
#Mann= 4 ,-1 , 0
  4761.2     .16       0  4968.5     .07       0  4972.5     .16       0
  5181.4     .05       0
Bank Sta=4968.5,4972.5
XS Rating Curve= 0 ,0
Exp/Cntr=0.3,0.1

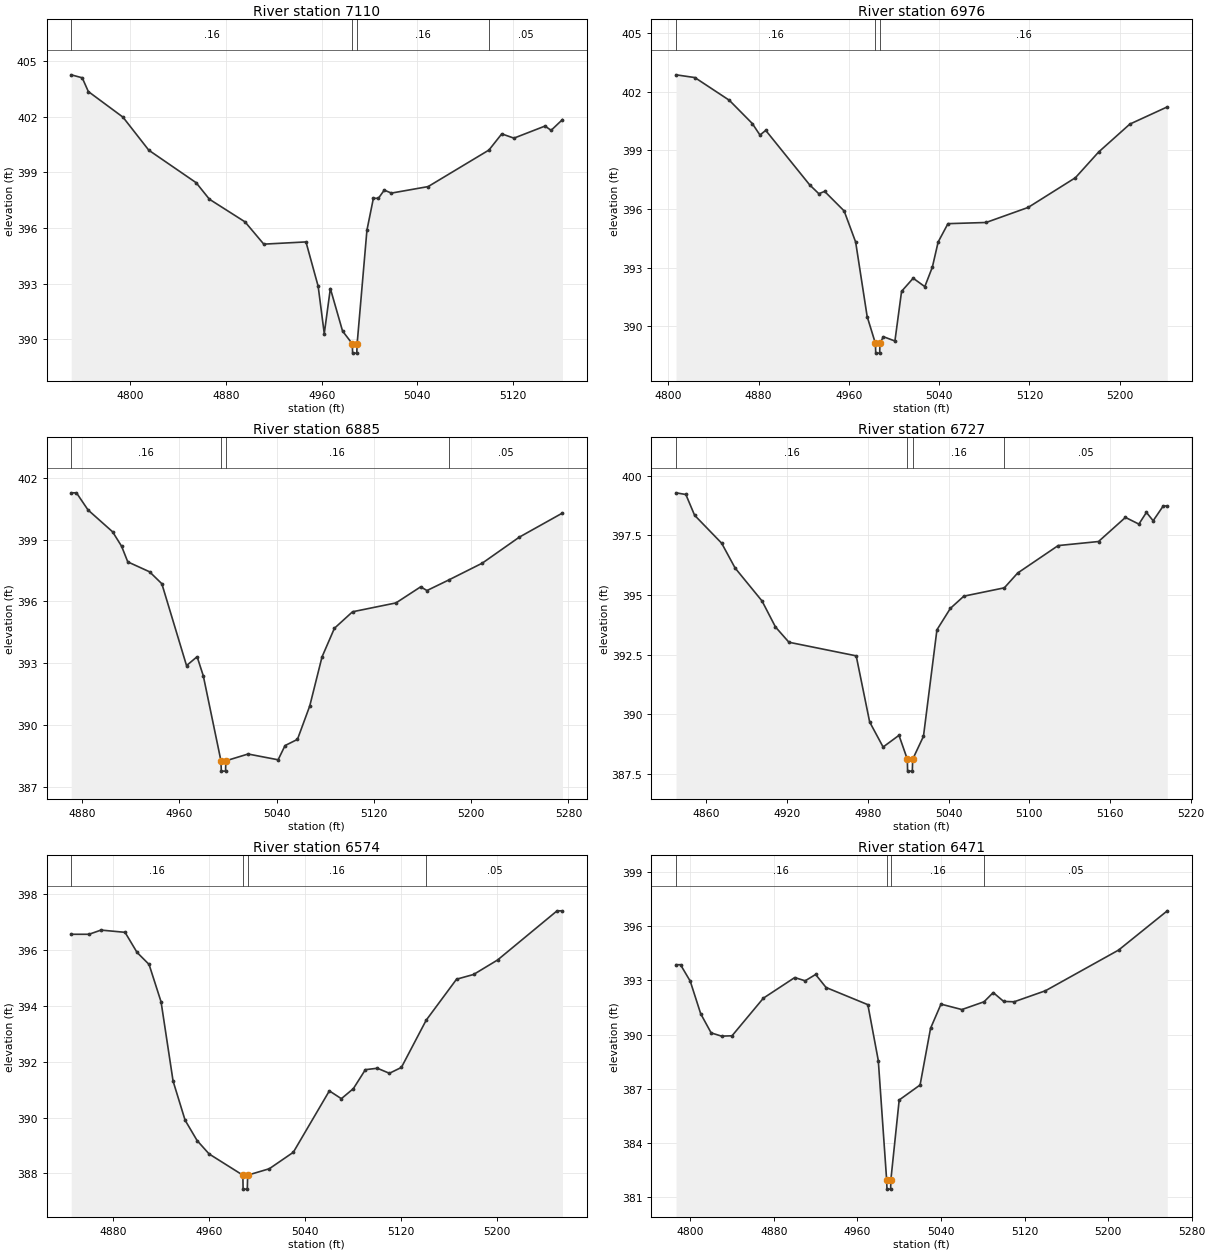
Type RM Length L Ch R = 1 ,7110    ,134,134,134
BEGIN DESCRIPTION:
South Twin Creek Trib F7109.55
END DESCRIPTION:
XS GIS Cut Line= 3
      2736928.85      6806808.55      2736979.22       6807056.5
      2737014.17      6807210.57
#Sta/Elev= 30
  4750.5  404.25  4759.7  404.09  4764.8  403.35  4793.8  401.97  4815.4  400.19
    4855  398.44  4866.1  397.55  4895.9  396.33  4911.6  395.13  4946.9  395.25
  4957.1  392.86  4962.2  390.31  4967.3  392.74  4977.5  390.45  4985.7  389.76
  4985.9  389.26  4989.4  389.26  4989.7  389.76  4997.9  395.88  5003.3   397.6
  5007.5   397.6  5012.4  398.04  5018.4  397.88  5049.1  398.23    5100   400.2
  5110.7  401.07  5120.9  400.84  5146.9  401.49    5152  401.26  5161.5  401.84
#Mann= 4 ,-1 , 0
  4750.5     .16       0  4985.7     .07       0  4989.7     .16       0
    5100     .05       0
Bank Sta=4985.7,4989.7
XS Rating Curve= 0 ,0
Exp/Cntr=0.3,0.1

Type RM Length L Ch R = 1 ,6976    ,91,91,91
BEGIN DESCRIPTION:
South Twin Creek Trib F6976.07
END DESCRIPTION:
XS GIS Cut Line= 3
      2736826.74      6806834.64      2736863.05      6807025.17
      2736918.14      6807260.25
#Sta/Elev= 30
  4806.8  402.86  4823.5  402.72    4854  401.56  4874.4  400.37  4881.2  399.78
  4886.3  400.02  4925.3  397.23  4933.4  396.78  4938.5   396.9  4955.8   395.9
    4966  394.31  4976.2   390.5  4983.5  389.13  4983.8  388.63  4987.3  388.63
  4987.5  389.13  4990.6  389.47  5000.8  389.25  5006.7  391.79    5017  392.46
  5027.3  392.03    5034  393.03  5039.1  394.31  5047.8  395.25  5081.6  395.31
  5118.9  396.08  5160.8   397.6  5181.3  398.91    5209  400.34  5242.2  401.22
#Mann= 3 ,-1 , 0
  4806.8     .16       0  4983.5     .07       0  4987.5     .16       0
Bank Sta=4983.5,4987.5
XS Rating Curve= 0 ,0
Exp/Cntr=0.3,0.1

Type RM Length L Ch R = 1 ,6885    ,158,158,158
BEGIN DESCRIPTION:
South Twin Creek Trib F6884.79
END DESCRIPTION:
XS GIS Cut Line= 3
       2736764.1      6806937.42      2736784.91      6807067.78
      2736829.08      6807336.05
#Sta/Elev= 30
  4871.2  401.27  4875.5  401.27    4885  400.44  4905.2  399.38  4912.6  398.68
  4917.7  397.92  4935.6  397.44  4945.7  396.86    4966  392.89  4974.7  393.32
  4979.8  392.39  4994.3  388.27  4994.6  387.77  4998.1  387.77  4998.3  388.27
  5016.6   388.6  5041.3  388.32    5047  389.01  5057.2  389.31  5067.3  390.93
  5077.4  393.31  5087.6   394.7  5102.5   395.5  5138.2  395.93  5158.5  396.71
  5163.7  396.53  5181.5  397.04  5209.2  397.86  5239.6  399.12  5275.1  400.29
#Mann= 4 ,-1 , 0
  4871.2     .16       0  4994.3     .07       0  4998.3     .16       0
  5181.5     .05       0
Bank Sta=4994.3,4998.3
XS Rating Curve= 0 ,0
Exp/Cntr=0.3,0.1

Type RM Length L Ch R = 1 ,6727    ,153,153,153
BEGIN DESCRIPTION:
South Twin Creek Trib F6727.39
END DESCRIPTION:
XS GIS Cut Line= 3
      2736680.88      6806997.16      2736684.31      6807162.81
      2736691.54      6807362.09
#Sta/Elev= 30
  4837.4  399.28  4844.7  399.21  4851.2  398.34  4871.3  397.17  4881.3  396.13
  4901.3  394.75  4911.3  393.66  4921.3  393.02  4971.3  392.45  4981.3  389.68
  4991.3  388.63  5003.1  389.12  5009.3  388.12  5009.5  387.62    5013  387.62
  5013.3  388.12  5021.3  389.08  5031.3  393.54  5041.3  394.44  5051.3  394.95
  5081.4   395.3  5091.3  395.92  5121.4  397.07  5151.4  397.24  5171.4  398.25
  5181.4  397.97    5187  398.46    5192  398.11  5199.5  398.73  5202.5  398.73
#Mann= 4 ,-1 , 0
  4837.4     .16       0  5009.3     .07       0  5013.3     .16       0
  5081.4     .05       0
Bank Sta=5009.3,5013.3
XS Rating Curve= 0 ,0
Exp/Cntr=0.3,0.1

Type RM Length L Ch R = 1 ,6574    ,103,103,103
BEGIN DESCRIPTION:
South Twin Creek Trib F6573.69
END DESCRIPTION:
XS GIS Cut Line= 3
      2736552.25      6806956.22       2736546.7      6807113.01
      2736537.98      6807364.97
#Sta/Elev= 30
  4845.3  396.57  4860.1  396.57  4870.1  396.72  4890.1  396.64  4900.1  395.92
  4910.1  395.49  4920.1  394.15  4930.1  391.31  4940.1  389.91  4950.1  389.18
  4960.1   388.7  4988.2  387.94  4988.4  387.44  4991.9  387.44  4992.2  387.94
  5010.2  388.17  5030.2  388.76  5060.2  390.96  5070.2  390.68  5080.2  391.04
  5090.2  391.72  5100.2  391.77  5110.2  391.59  5120.2   391.8  5140.8  393.49
  5166.1  394.96  5180.3  395.13  5200.3  395.65  5249.8  397.41  5254.3  397.41
#Mann= 4 ,-1 , 0
  4845.3     .16       0  4988.2     .07       0  4992.2     .16       0
  5140.8     .05       0
Bank Sta=4988.2,4992.2
XS Rating Curve= 0 ,0
Exp/Cntr=0.3,0.1

Type RM Length L Ch R = 1 ,6471    ,154,154,154
BEGIN DESCRIPTION:
South Twin Creek Trib F6470.61
END DESCRIPTION:
XS GIS Cut Line= 3
      2736444.27       6806897.4      2736443.69      6807115.99
      2736441.39      6807367.58
#Sta/Elev= 30
  4786.4  393.86  4790.7  393.86    4800  392.95    4810  391.15    4820  390.09
    4830  389.91    4840  389.93    4870  392.01    4900  393.15    4910  392.97
    4920  393.32    4930   392.6    4970  391.65    4980  388.56    4988  381.95
  4988.3  381.45  4991.8  381.45    4992  381.95    5000  386.38    5020  387.21
    5030  390.34    5040  391.68    5060  391.38  5081.2  391.81    5090  392.32
    5100  391.83    5110  391.81    5140  392.42    5210  394.67  5256.6  396.84
#Mann= 4 ,-1 , 0
  4786.4     .16       0    4988     .07       0    4992     .16       0
  5081.2     .05       0
Bank Sta=4988,4992
XS Rating Curve= 0 ,0
Exp/Cntr=0.3,0.1

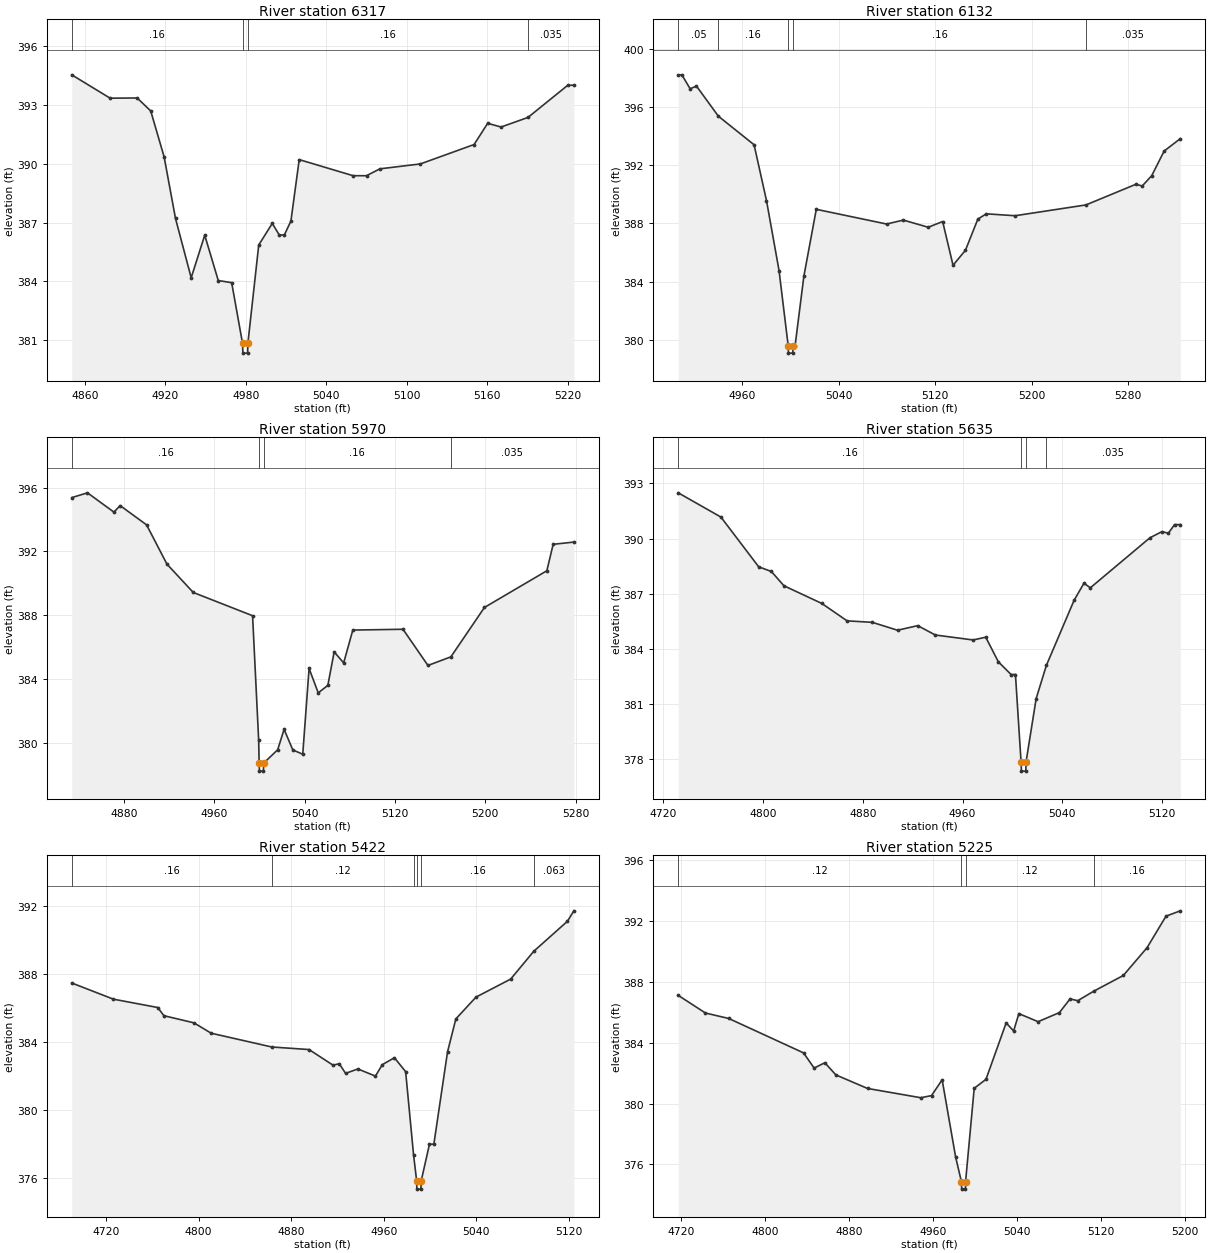
Type RM Length L Ch R = 1 ,6317    ,185,185,185
BEGIN DESCRIPTION:
South Twin Creek Trib F6316.6
END DESCRIPTION:
XS GIS Cut Line= 3
      2736270.81      6806962.61      2736290.33      6807116.36
      2736310.53      6807335.04
#Sta/Elev= 30
  4850.1  394.53  4878.7  393.34  4898.9  393.35    4909  392.69    4919  390.35
  4927.5  387.21  4939.2  384.19  4949.3  386.36  4959.4  384.05  4969.4  383.94
  4977.5  380.85  4977.8  380.35  4981.3  380.35  4981.5  380.85  4989.6  385.86
  4999.7  386.96  5004.9  386.37  5008.7  386.37  5013.6  387.08  5019.8  390.21
    5060  389.39    5070  389.39    5080  389.74  5110.2  389.99  5150.3  390.98
  5160.4  392.06  5170.4  391.87  5190.5  392.36  5220.2     394  5224.7     394
#Mann= 4 ,-1 , 0
  4850.1     .16       0  4977.5     .07       0  4981.5     .16       0
  5190.5    .035       0
Bank Sta=4977.5,4981.5
XS Rating Curve= 0 ,0
Exp/Cntr=0.3,0.1

Type RM Length L Ch R = 1 ,6132    ,162,162,162
BEGIN DESCRIPTION:
South Twin Creek Trib F6132.08
END DESCRIPTION:
XS GIS Cut Line= 3
      2736097.46      6806970.22      2736121.77      6807061.72
      2736199.31      6807373.96
#Sta/Elev= 30
  4906.9   398.2  4909.9   398.2  4916.8  397.24    4922  397.43  4940.2  395.36
  4969.8   393.4  4980.1  389.57  4990.5  384.77  4998.1   379.6  4998.3   379.1
  5001.8   379.1  5002.1   379.6  5003.8   379.6  5011.1  384.38  5021.4  388.97
  5079.7  387.96  5093.6  388.23  5114.2  387.74  5126.2  388.13  5134.8  385.13
  5145.1  386.16  5155.4   388.3  5162.4  388.66  5186.3  388.53    5245  389.27
  5286.5  390.69  5291.7  390.57  5299.6  391.28  5309.9  392.97  5323.3  393.82
#Mann= 5 ,-1 , 0
  4906.9     .05       0  4940.2     .16       0  4998.1     .07       0
  5002.1     .16       0    5245    .035       0
Bank Sta=4998.1,5002.1
XS Rating Curve= 0 ,0
Exp/Cntr=0.3,0.1

Type RM Length L Ch R = 1 ,5970    ,335,335,335
BEGIN DESCRIPTION:
South Twin Creek Trib F5970.21
END DESCRIPTION:
XS GIS Cut Line= 3
       2735925.8      6806992.44      2735992.92      6807146.63
      2736119.47      6807392.06
#Sta/Elev= 30
    4834  395.37  4847.9  395.67  4871.3  394.46  4876.8  394.87  4900.2  393.66
  4918.2   391.2  4941.5  389.42    4994  387.96  4999.4  380.14  4999.8  378.71
  5000.1  378.21  5003.6  378.21  5003.8  378.71  5016.2  379.55  5021.9  380.83
  5029.6  379.54  5038.4  379.27    5044  384.65  5052.1  383.12  5060.6  383.59
  5066.2  385.69  5074.6     385  5082.7  387.06  5127.1  387.11  5149.2  384.84
  5169.5  385.38  5199.2  388.48  5254.4  390.78    5260  392.44  5278.3  392.58
#Mann= 4 ,-1 , 0
    4834     .16       0  4999.8     .07       0  5003.8     .16       0
  5169.5    .035       0
Bank Sta=4999.8,5003.8
XS Rating Curve= 0 ,0
Exp/Cntr=0.3,0.1

Type RM Length L Ch R = 1 ,5635    ,213,213,213
BEGIN DESCRIPTION:
South Twin Creek Trib F5634.83
END DESCRIPTION:
XS GIS Cut Line= 3
      2735848.48      6806997.13      2735809.99      6807264.61
      2735789.44      6807395.06
#Sta/Elev= 30
  4732.2  392.49  4766.4  391.17  4796.7  388.46  4806.8  388.21  4816.9  387.43
  4847.2  386.47  4867.5  385.52  4887.7  385.44  4907.9  385.01  4924.1  385.26
  4938.2  384.75  4968.5  384.48  4978.6  384.63  4988.7  383.29  4998.9   382.6
  5002.4   382.6  5006.9  377.84  5007.2  377.34  5010.7  377.34  5010.9  377.84
    5019  381.29  5027.2   383.1  5049.4  386.64  5057.3  387.57  5062.4  387.32
  5110.1  390.04  5119.8  390.38  5124.9  390.29  5129.9  390.76  5134.5  390.76
#Mann= 4 ,-1 , 0
  4732.2     .16       0  5006.9     .07       0  5010.9     .16       0
  5027.2    .035       0
Bank Sta=5006.9,5010.9
XS Rating Curve= 0 ,0
Exp/Cntr=0.3,0.1

Type RM Length L Ch R = 1 ,5422    ,197,197,197
BEGIN DESCRIPTION:
South Twin Creek Trib F5421.93
END DESCRIPTION:
XS GIS Cut Line= 3
      2735715.32      6806906.91      2735614.56      6807203.27
      2735571.05      6807316.15
#Sta/Elev= 30
  4690.4  387.48  4726.4  386.53  4764.7  386.04    4770  385.56    4796  385.14
  4810.9  384.53  4863.3  383.72  4895.5  383.57  4916.3  382.65  4921.6  382.74
  4927.1  382.17  4937.7  382.43  4952.9  382.01  4958.8  382.68  4969.3  383.09
    4979  382.27  4985.9  377.35  4988.5  375.87  4988.7  375.37  4992.2  375.37
  4992.5  375.87  4999.6  378.01  5003.4  378.01  5015.2  383.43  5022.4  385.37
  5039.8  386.65  5069.8  387.71  5089.7  389.34  5118.9  391.11  5124.4  391.72
#Mann= 6 ,-1 , 0
  4690.4     .16       0  4863.3     .12       0  4985.9     .16       0
  4988.5     .07       0  4992.5     .16       0  5089.7    .063       0
Bank Sta=4988.5,4992.5
XS Rating Curve= 0 ,0
Exp/Cntr=0.3,0.1

Type RM Length L Ch R = 1 ,5225    ,351,351,351
BEGIN DESCRIPTION:
South Twin Creek Trib F5225.06
END DESCRIPTION:
XS GIS Cut Line= 3
        2735536.      6806793.61      2735486.27      6807078.15
      2735455.39      6807264.46
#Sta/Elev= 30
  4717.6  387.11  4743.5  385.95  4765.7  385.59  4836.8  383.33  4846.9  382.33
  4857.1  382.68  4867.6  381.88  4897.7  380.99  4948.4  380.38  4958.6  380.52
  4968.7  381.56  4981.5  376.49    4987  374.87  4987.3  374.37  4990.8  374.37
    4991  374.87  4999.2     381  5010.4  381.59  5029.6   385.3  5036.7  384.77
  5041.7  385.91    5060  385.38  5080.3  385.98  5090.4  386.88  5097.7  386.76
  5112.8  387.38  5141.1  388.42  5163.7  390.25  5181.7  392.32  5195.3  392.67
#Mann= 4 ,-1 , 0
  4717.6     .12       0    4987     .07       0    4991     .12       0
  5112.8     .16       0
Bank Sta=4987,4991
XS Rating Curve= 0 ,0
Exp/Cntr=0.3,0.1