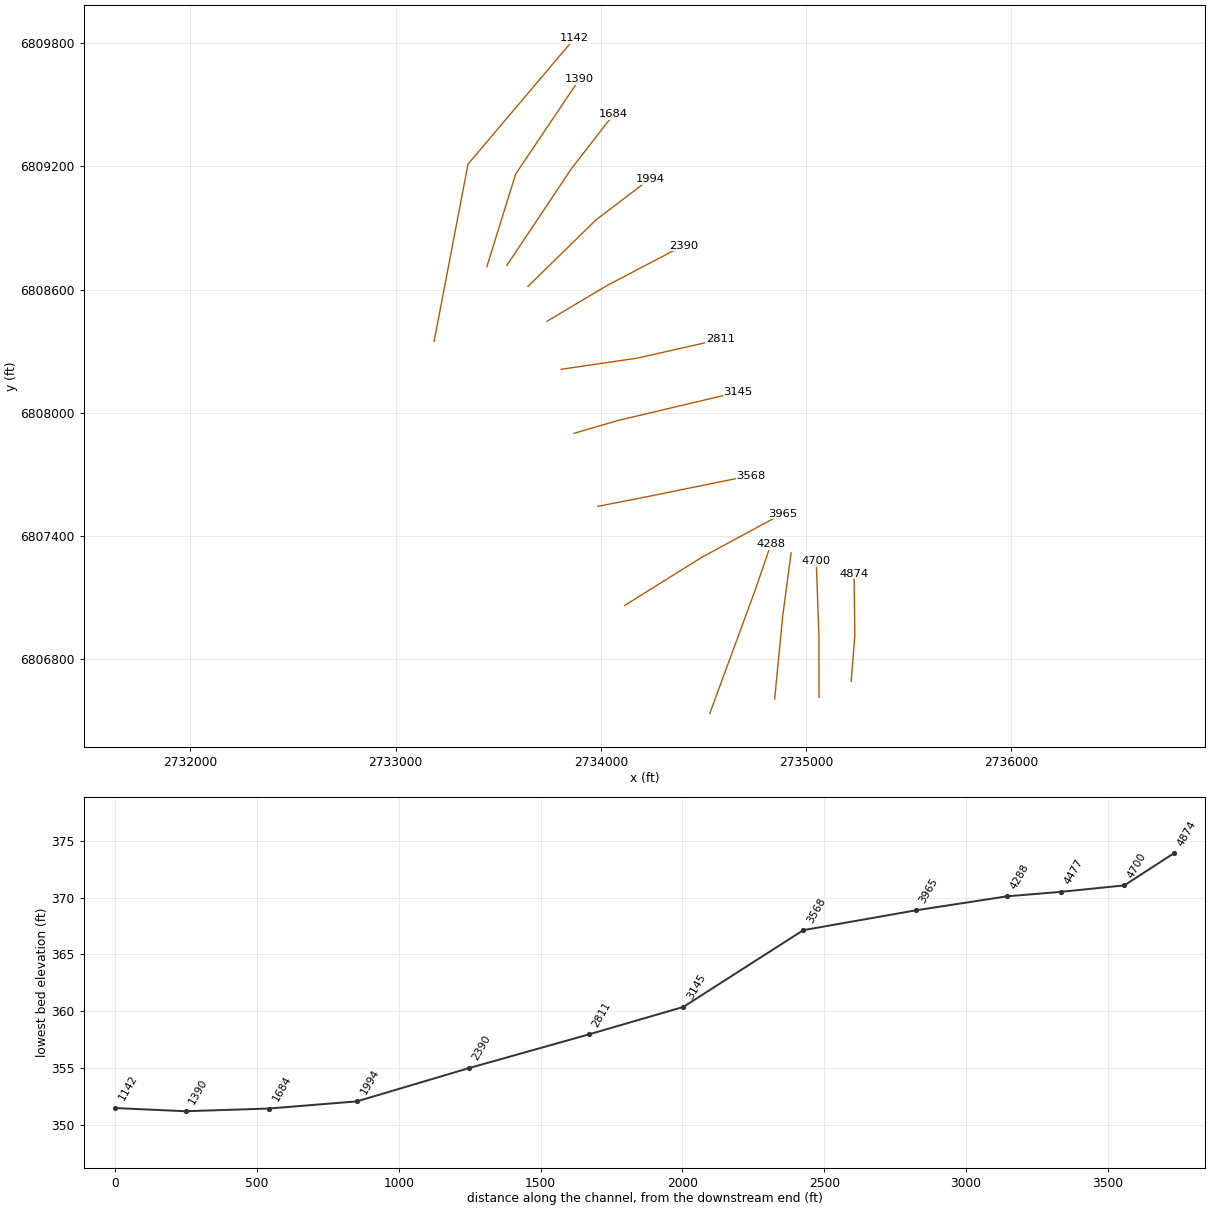
HEC-RAS study South Twin Creek Trib F.prj: South Twin Creek Trib F Base Level Engineering

--- South Twin Creek Trib F.g01 (geometry) --- (continued)

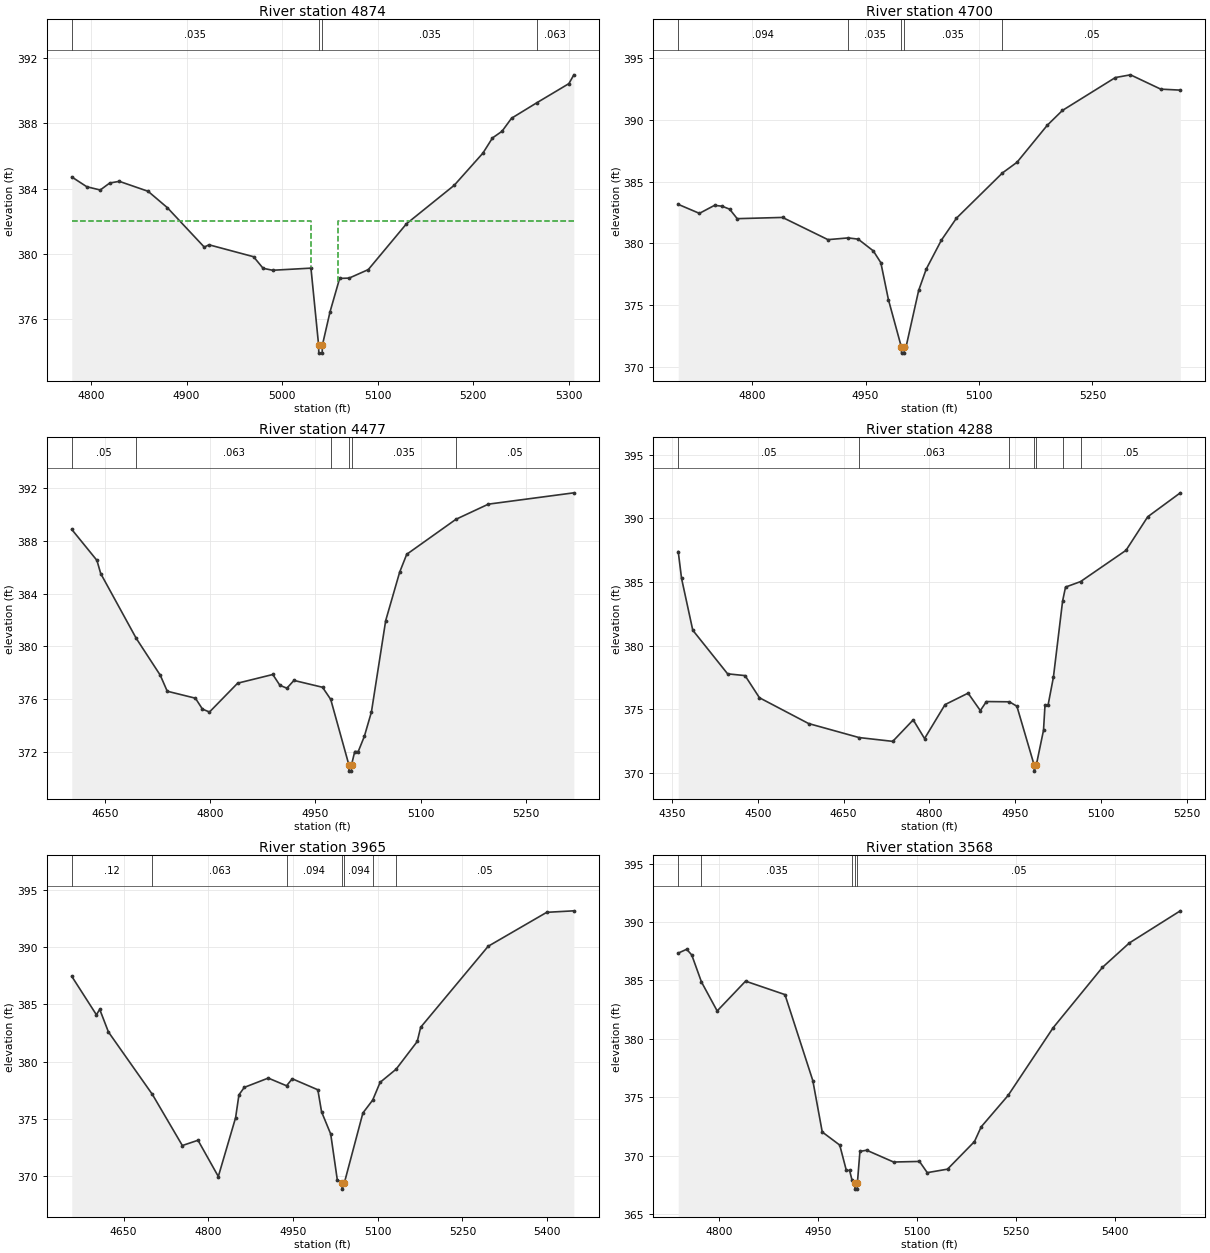
Type RM Length L Ch R = 1 ,4874    ,174,174,174
BEGIN DESCRIPTION:
South Twin Creek Trib F4874.47
END DESCRIPTION:
XS GIS Cut Line= 3
      2735219.68      6806691.32      2735237.55      6806915.11
      2735233.74      6807216.18
#Sta/Elev= 30
  4779.8  384.71  4795.5  384.11  4809.6  383.91  4819.6  384.34  4829.6  384.44
  4859.7  383.83  4879.8  382.83  4918.5  380.41  4923.5  380.55  4970.1  379.82
  4980.1  379.11  4990.1  378.99  5030.2  379.12  5038.2  374.41  5038.4  373.91
  5041.9  373.91  5042.2  374.41  5050.2  376.45  5060.2  378.49  5070.2  378.51
  5090.2  379.03  5130.2  381.84  5180.2   384.2  5210.2  386.17  5220.2   387.1
  5230.2  387.51  5240.2  388.31  5266.7  389.26  5300.2  390.43  5305.4  390.97
#Mann= 4 ,-1 , 0
  4779.8    .035       0  5038.2    .035       0  5042.2    .035       0
  5266.7    .063       0
#XS Ineff= 2 , 0
       0    5030     382    5059       0     382
Permanent Ineff=
       F       F
Bank Sta=5038.2,5042.2
XS Rating Curve= 0 ,0
Exp/Cntr=0.3,0.1

Type RM Length L Ch R = 1 ,4700    ,223,223,223
BEGIN DESCRIPTION:
South Twin Creek Trib F4699.77
END DESCRIPTION:
XS GIS Cut Line= 3
      2735062.99      6806613.02      2735062.49      6806914.32
      2735049.52      6807276.89
#Sta/Elev= 30
  4702.2  383.15  4730.2  382.42  4750.2  383.07  4760.2     383  4770.2  382.76
  4780.2  381.99  4840.2  382.09  4900.2  380.29    4927  380.43  4940.2  380.33
  4960.2  379.38  4970.2  378.42  4980.2  375.43  4997.3  371.59  4997.6  371.09
  5001.1  371.09  5001.3  371.59  5003.5  371.59  5020.2  376.17  5030.2   377.9
  5050.2  380.24  5070.2  382.03  5131.1   385.7  5150.3  386.56  5190.3  389.56
  5210.3  390.76  5280.4  393.43  5300.4  393.65  5340.4  392.49  5366.3  392.41
#Mann= 5 ,-1 , 0
  4702.2    .094       0    4927    .035       0  4997.3    .035       0
  5001.3    .035       0  5131.1     .05       0
Bank Sta=4997.3,5001.3
XS Rating Curve= 0 ,0
Exp/Cntr=0.3,0.1

Type RM Length L Ch R = 1 ,4477    ,189,189,189
BEGIN DESCRIPTION:
South Twin Creek Trib F4476.73
END DESCRIPTION:
XS GIS Cut Line= 3
      2734846.99      6806605.31      2734885.99      6807008.86
        2734927.      6807317.51
#Sta/Elev= 30
  4602.1  388.88    4638  386.53  4643.4  385.53  4694.2   380.6  4728.4  377.81
  4738.4  376.59  4778.6  376.06  4788.7  375.23  4798.7  375.01  4838.9   377.2
  4889.1  377.86  4899.2  377.04  4909.2  376.82  4919.3  377.41  4960.1  376.89
  4971.8  375.97  4997.6  371.02  4997.9  370.52  5001.4  370.52  5001.6  371.02
  5006.1  372.01  5011.1  372.01  5019.8  373.16  5029.9  375.01  5050.3  381.96
  5070.2  385.63  5080.3  386.99  5150.6  389.65  5196.9   390.8  5318.9  391.66
#Mann= 6 ,-1 , 0
  4602.1     .05       0  4694.2    .063       0  4971.8    .035       0
  4997.6    .035       0  5001.6    .035       0  5150.6     .05       0
Bank Sta=4997.6,5001.6
XS Rating Curve= 0 ,0
Exp/Cntr=0.3,0.1

Type RM Length L Ch R = 1 ,4288    ,323,323,323
BEGIN DESCRIPTION:
South Twin Creek Trib F4287.58
END DESCRIPTION:
XS GIS Cut Line= 3
        2734531.      6806535.54      2734752.79      6807138.19
      2734829.14      6807360.79
#Sta/Elev= 30
  4360.9  387.39  4366.7  385.28  4386.3  381.21  4447.2  377.78  4477.7  377.64
  4502.8   375.9  4588.8  373.87  4676.9  372.77  4735.8  372.47  4771.6  374.16
  4791.4  372.69  4827.2  375.36  4867.5  376.26  4888.9  374.89  4899.5   375.6
  4939.8  375.58  4952.8  375.23  4982.8  370.63    4983  370.13  4986.8  370.63
  4999.3  373.34  5001.9   375.3  5007.2   375.3  5016.6  377.51  5032.7  383.51
  5037.8   384.6    5064  385.03  5143.5  387.49  5181.5  390.13  5238.4  392.01
#Mann= 7 ,-1 , 0
  4360.9     .05       0  4676.9    .063       0  4939.8    .094       0
  4982.8     .07       0  4986.8    .094       0  5032.7    .035       0
    5064     .05       0
Bank Sta=4982.8,4986.8
XS Rating Curve= 0 ,0
Exp/Cntr=0.3,0.1

Type RM Length L Ch R = 1 ,3965    ,397,397,397
BEGIN DESCRIPTION:
South Twin Creek Trib F3965.14
END DESCRIPTION:
XS GIS Cut Line= 3
      2734116.45      6807061.36      2734492.51      6807296.22
      2734884.55      6807508.09
#Sta/Elev= 30
  4558.3  387.44  4601.9  384.09  4607.8  384.56  4623.2  382.59  4701.1  377.14
  4754.1  372.69  4781.8  373.15  4817.8  369.99  4848.4  375.12  4854.3  377.11
  4863.8  377.76  4906.2  378.57  4938.6   377.9  4948.7  378.51    4994  377.55
  5000.6  375.63  5016.8  373.69  5028.4  369.72  5036.7  369.39  5036.9  368.89
  5040.7  369.39  5073.8  375.53  5091.1  376.65  5104.3   378.2  5132.5  379.34
    5170  381.76  5176.1     383  5295.6  390.06  5399.3  393.02  5447.3  393.15
#Mann= 7 ,-1 , 0
  4558.3     .12       0  4701.1    .063       0  4938.6    .094       0
  5036.7     .07       0  5040.7    .094       0  5091.1    .035       0
  5132.5     .05       0
Bank Sta=5036.7,5040.7
XS Rating Curve= 0 ,0
Exp/Cntr=0.3,0.1

Type RM Length L Ch R = 1 ,3568    ,423,423,423
BEGIN DESCRIPTION:
South Twin Creek Trib F3568.27
END DESCRIPTION:
XS GIS Cut Line= 3
      2733985.91      6807544.03      2734240.62      6807594.21
      2734731.68      6807693.99
#Sta/Elev= 30
  4738.1  387.34  4750.9  387.67  4758.6  387.18  4773.3  384.87  4797.1  382.39
  4840.1  384.94  4899.8  383.79    4942  376.43  4956.3  372.03  4982.8  370.91
  4992.8  368.74  4997.7  368.74  5001.3  367.94  5005.5  367.64  5005.8  367.14
  5009.3  367.14  5009.5  367.64  5013.4  370.37  5023.6  370.47  5064.4  369.46
  5103.6  369.51  5115.4  368.55  5146.1  368.85  5186.9  371.21  5197.1  372.47
  5237.9  375.16  5306.1  380.95  5380.8  386.12  5421.6  388.21  5498.8  390.96
#Mann= 5 ,-1 , 0
  4738.1    .063       0  4773.3    .035       0  5001.3     .05       0
  5005.5    .035       0  5009.5     .05       0
Bank Sta=5005.5,5009.5
XS Rating Curve= 0 ,0
Exp/Cntr=0.3,0.1

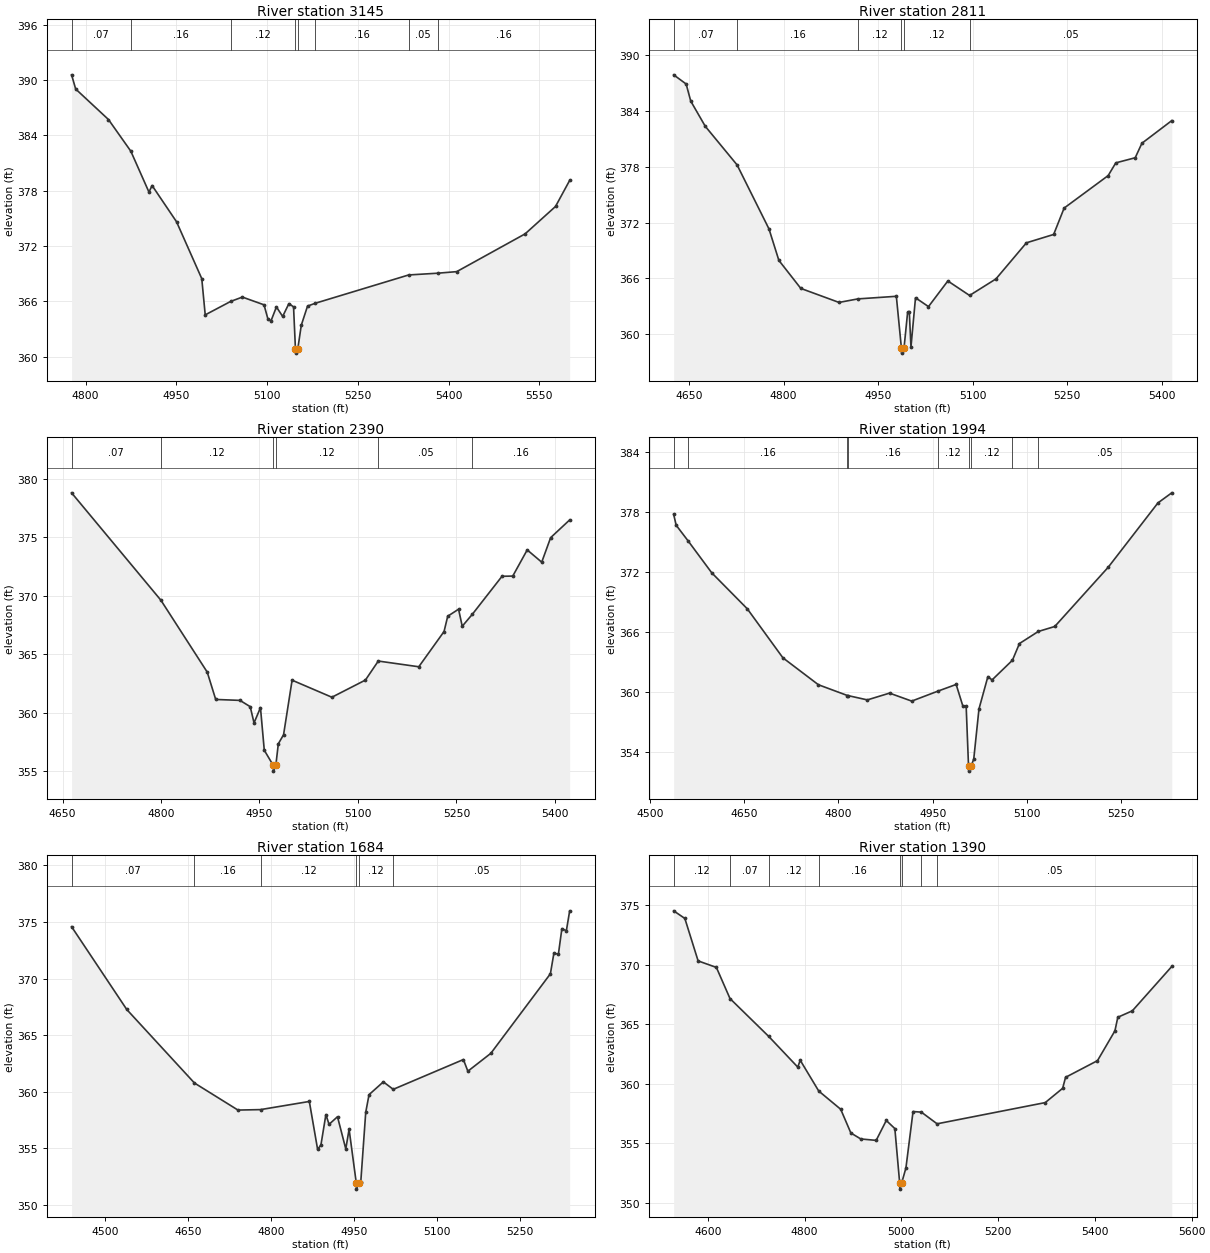
Type RM Length L Ch R = 1 ,3145    ,334,334,334
BEGIN DESCRIPTION:
South Twin Creek Trib F3145.02
END DESCRIPTION:
XS GIS Cut Line= 3
      2733869.43      6807899.76      2734081.95      6807961.93
      2734667.67      6808100.45
#Sta/Elev= 30
  4776.7  390.56  4783.5  389.02  4837.7  385.71  4874.6  382.28  4904.6  377.84
  4909.8  378.55  4950.2  374.62  4991.9  368.45  4997.6  364.52  5039.7  365.98
    5059  366.45  5094.8  365.61  5101.3  364.06  5106.4  363.88  5115.3  365.38
  5125.6  364.35  5135.9  365.74  5143.6  365.39  5146.7  360.87    5147  360.37
  5150.7  360.87  5156.4   363.4  5166.7  365.47  5179.5  365.78  5333.9  368.85
  5381.8  369.04  5413.3  369.21  5526.4  373.31  5576.6  376.28    5600  379.11
#Mann= 8 ,-1 , 0
  4776.7     .07       0  4874.6     .16       0  5039.7     .12       0
  5146.7     .07       0  5150.7     .12       0  5179.5     .16       0
  5333.9     .05       0  5381.8     .16       0
Bank Sta=5146.7,5150.7
XS Rating Curve= 0 ,0
Exp/Cntr=0.3,0.1

Type RM Length L Ch R = 1 ,2811    ,421,421,421
BEGIN DESCRIPTION:
South Twin Creek Trib F2811.15
END DESCRIPTION:
XS GIS Cut Line= 3
      2733806.44      6808211.74      2734176.43      6808265.92
       2734582.6      6808357.46
#Sta/Elev= 30
  4625.6  387.91  4645.4  386.92  4652.7  385.08  4675.7  382.37  4726.2  378.21
  4776.8  371.32  4792.5  367.93  4827.3  364.91  4887.9   363.4  4917.9  363.78
  4978.9  364.06    4987  358.44  4987.2  357.94    4991  358.44  4996.8  362.34
  4999.5  362.34  5002.1   358.6  5009.3   363.9  5029.9  362.95  5060.6  365.71
  5095.1  364.15  5136.9  365.93  5185.3  369.82  5228.5  370.72  5245.1  373.56
    5315  377.06  5327.1  378.43  5357.9  378.98  5368.5  380.54  5415.9  382.98
#Mann= 6 ,-1 , 0
  4625.6     .07       0  4726.2     .16       0  4917.9     .12       0
    4987     .07       0    4991     .12       0  5095.1     .05       0
Bank Sta=4987,4991
XS Rating Curve= 0 ,0
Exp/Cntr=0.3,0.1

Type RM Length L Ch R = 1 ,2390    ,396,396,396
BEGIN DESCRIPTION:
South Twin Creek Trib F2389.62
END DESCRIPTION:
XS GIS Cut Line= 3
      2733738.37      6808446.09      2734030.22      6808619.66
      2734401.69      6808814.22
#Sta/Elev= 30
  4663.7  378.82  4799.8  369.62  4870.4  363.46  4883.3  361.12  4920.3  361.04
  4935.9   360.5  4941.7  359.11  4951.5  360.42  4957.3  356.77  4970.9  355.48
  4971.2  354.98  4974.9  355.48  4978.7  357.32  4986.7   358.1  4999.7  362.77
  5060.3  361.31  5111.4  362.78    5131  364.41  5192.7  363.92  5231.2  366.94
  5236.8  368.25  5253.3  368.85  5258.9  367.39  5274.5  368.43  5319.5  371.67
  5335.9  371.69  5357.9  373.93    5380  372.88  5393.6  374.98  5422.6   376.5
#Mann= 6 ,-1 , 0
  4663.7     .07       0  4799.8     .12       0  4970.9     .07       0
  4974.9     .12       0    5131     .05       0  5274.5     .16       0
Bank Sta=4970.9,4974.9
XS Rating Curve= 0 ,0
Exp/Cntr=0.3,0.1

Type RM Length L Ch R = 1 ,1994    ,310,310,310
BEGIN DESCRIPTION:
South Twin Creek Trib F1994.38
END DESCRIPTION:
XS GIS Cut Line= 3
      2733645.31      6808615.95      2733975.87       6808938.9
       2734238.8      6809139.08
#Sta/Elev= 30
  4537.8  377.78  4541.8  376.69  4560.9  375.11  4598.4  371.92    4655  368.31
  4711.6   363.4  4768.1   360.7  4814.3  359.62  4814.7  359.62    4846  359.18
  4881.3  359.86  4916.6  359.06  4957.9  360.05  4987.3  360.73  4997.9  358.58
  5003.2  358.58    5007  352.54  5007.3  352.04    5011  352.54  5015.3  353.25
  5023.6  358.27  5037.8  361.52  5044.4  361.18  5076.9  363.16    5088  364.83
    5118  366.04  5144.2  366.54  5229.4  372.49  5308.4  378.93  5330.4  379.94
#Mann= 9 ,-1 , 0
  4537.8     .07       0  4560.9     .16       0  4814.3     .12       0
  4814.7     .16       0  4957.9     .12       0    5007     .07       0
    5011     .12       0  5076.9     .16       0    5118     .05       0
Bank Sta=5007,5011
XS Rating Curve= 0 ,0
Exp/Cntr=0.3,0.1

Type RM Length L Ch R = 1 ,1684    ,294,294,294
BEGIN DESCRIPTION:
South Twin Creek Trib F1684.23
END DESCRIPTION:
XS GIS Cut Line= 3
      2733542.18      6808717.87      2733856.45      6809188.57
       2734062.2      6809453.86
#Sta/Elev= 30
  4438.8  374.58  4538.7  367.27  4661.2  360.78    4740  358.39  4780.9  358.43
  4869.2  359.15  4884.2  354.92  4890.2  355.31  4899.2  357.99  4904.9  357.13
  4920.2   357.8  4935.2  354.96  4941.2   356.7  4954.3  351.91  4954.5  351.41
  4958.3  351.91  4962.3  352.02  4971.3  358.19  4977.3  359.75  5003.2  360.88
  5021.1  360.22  5148.1  362.85  5156.2  361.82  5197.8   363.4  5305.6  370.42
  5311.9  372.23  5320.1  372.16  5326.4  374.41  5334.5  374.22  5340.5  375.98
#Mann= 6 ,-1 , 0
  4438.8     .07       0  4661.2     .16       0  4780.9     .12       0
  4954.3     .07       0  4958.3     .12       0  5021.1     .05       0
Bank Sta=4954.3,4958.3
XS Rating Curve= 0 ,0
Exp/Cntr=0.3,0.1

Type RM Length L Ch R = 1 ,1390    ,248,248,248
BEGIN DESCRIPTION:
South Twin Creek Trib F1389.63
END DESCRIPTION:
XS GIS Cut Line= 3
      2733444.94       6808711.3      2733585.02      6809162.69
      2733895.82      6809624.65
#Sta/Elev= 30
  4529.5  374.52  4552.6  373.88    4580  370.32  4617.8  369.77  4645.9  367.16
    4726  363.98  4785.9  361.41  4791.1  361.98  4829.3   359.4  4874.7  357.87
  4895.7  355.88  4916.2  355.38    4948  355.26  4968.9  356.93  4986.6  356.25
  4996.6  351.67  4996.9  351.17  5000.6  351.67  5009.5  352.95  5024.2  357.68
  5041.4  357.63  5073.9  356.65  5297.4  358.43  5333.4  359.63  5339.4  360.55
  5405.4  361.95  5441.4  364.45  5447.4  365.59  5477.4  366.13  5558.9  369.85
#Mann= 8 ,-1 , 0
  4529.5     .12       0  4645.9     .07       0    4726     .12       0
  4829.3     .16       0  4996.6     .07       0  5000.6     .16       0
  5041.4     .12       0  5073.9     .05       0
Bank Sta=4996.6,5000.6
XS Rating Curve= 0 ,0
Exp/Cntr=0.3,0.1

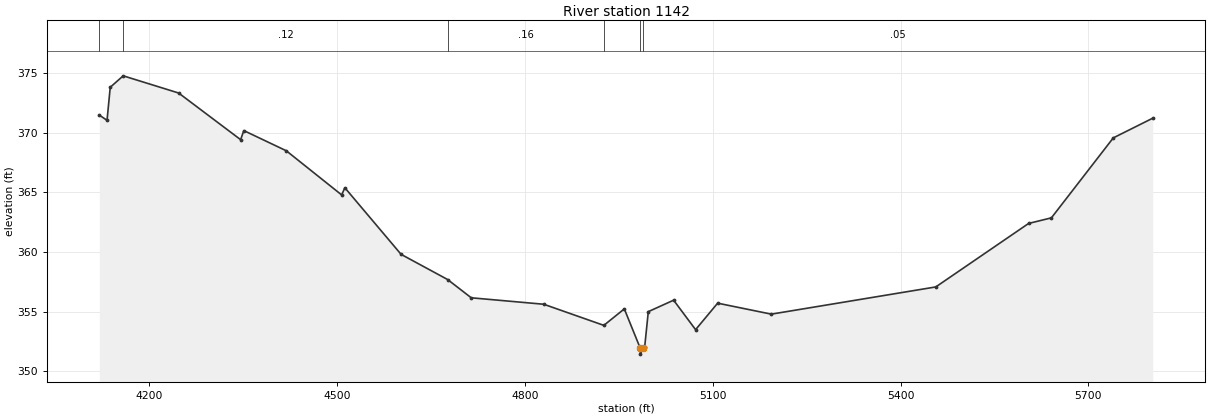
Type RM Length L Ch R = 1 ,1142    ,0,0,0
BEGIN DESCRIPTION:
South Twin Creek Trib F1142.253
END DESCRIPTION:
XS GIS Cut Line= 3
      2733187.96      6808347.77      2733353.17      6809211.31
      2733871.78      6809823.99
#Sta/Elev= 30
  4120.8  371.48  4133.1  371.04  4138.2  373.81  4158.9  374.77  4247.4  373.33
  4346.4  369.42  4351.5  370.18  4419.3  368.49  4507.7  364.79  4512.8  365.39
  4602.6  359.81  4676.9   357.7  4714.6  356.17  4830.3  355.63  4926.3  353.86
    4959  355.24  4984.4  351.95  4984.7  351.45  4988.4  351.95  4991.5  352.05
  4997.3  355.01  5037.7  355.97  5072.8   353.5    5108  355.72  5193.7   354.8
  5456.3  357.08  5604.5   362.4  5640.9  362.87  5739.7  369.57  5802.7  371.22
#Mann= 6 ,-1 , 0
  4120.8    .035       0  4158.9     .12       0  4676.9     .16       0
  4926.3     .05       0  4984.4     .05       0  4988.4     .05       0
Bank Sta=4984.4,4988.4
XS Rating Curve= 0 ,0
Exp/Cntr=0.3,0.1

Chan Stop Cuts=-1
Use User Specified Reach Order=0
Composite Channel Slope=5