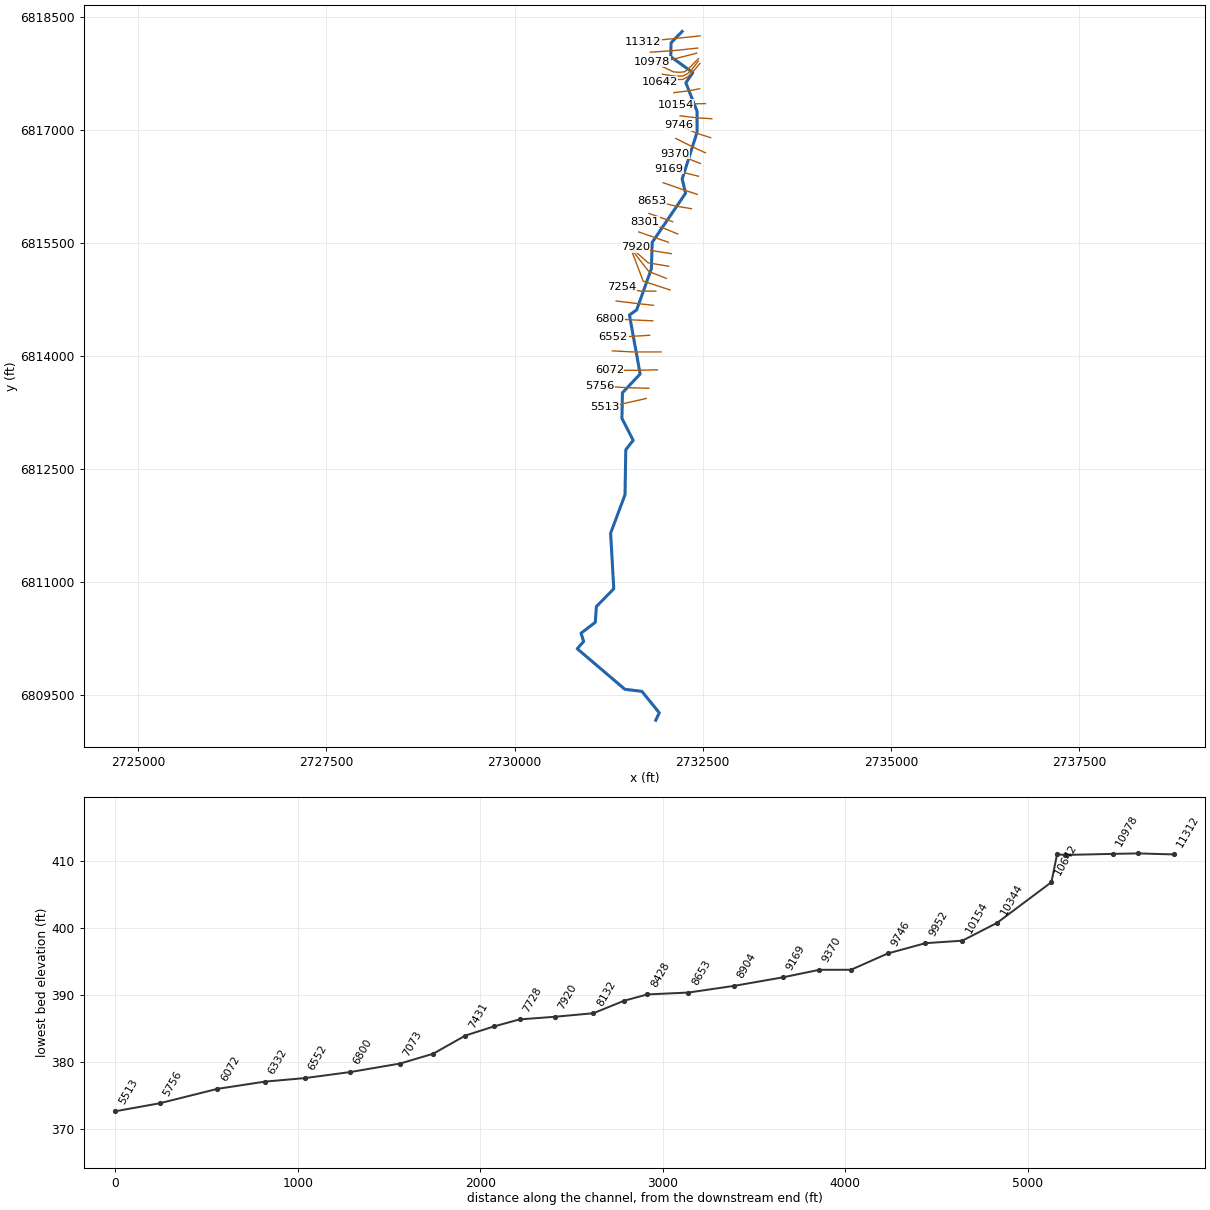
--- South Twin Creek Trib G.prj (project) ---

Proj Title=South Twin Creek Trib G Base Level Engineering
Current Plan=p01
Default Exp/Contr=0.3,0.1
English Units
Geom File=g01
Flow File=f01
Plan File=p01
BEGIN DESCRIPTION:
South Twin Creek Trib G
END DESCRIPTION:

--- South Twin Creek Trib G.p01 (plan) ---

Plan Title=Multiple Run
Short Identifier=Multiple
Geom File=g01
Flow File=f01
Subcritical Flow
K Sum by GR= 0
Std Step Tol= 0.01
Critical Tol= 0.01
Num of Std Step Trials= 20
Max Error Tol= 0.3
Flow Tol Ratio= 0.001
Split Flow NTrial= 30
Split Flow Tol= 0.02
Split Flow Ratio= 0.02
Log Output Level= 0
Friction Slope Method= 1
Unsteady Friction Slope Method= 2
Unsteady Bridges Friction Slope Method= 1
Parabolic Critical Depth
Global Vel Dist=  1 , 1 , 1
Global Log Level= 0
CheckData=True
Encroach Param= -1, 0, 0, 0
BEGIN DESCRIPTION:
Multiple Run
END DESCRIPTION:

--- South Twin Creek Trib G.f01 (steady flow) ---

Flow Title=Multiple
Number of Profiles=7
Profile Names=10-year,25-year,50-year,1pct_min,100-year,1pct_plu,500-year
River Rch & RM= South Twin Creek,Reach-1,11312
     195     241     276     157     314     626     404
River Rch & RM= South Twin Creek,Reach-1,7254
     493     649     771     455     908    1812    1258
Boundary for River Rch & Prof#=South Twin Creek,Reach-1,1
Up Type=0
Dn Type=3
Dn Slope=0.005
Boundary for River Rch & Prof#=South Twin Creek,Reach-1,2
Up Type=0
Dn Type=3
Dn Slope=0.005
Boundary for River Rch & Prof#=South Twin Creek,Reach-1,3
Up Type=0
Dn Type=3
Dn Slope=0.005
Boundary for River Rch & Prof#=South Twin Creek,Reach-1,4
Up Type=0
Dn Type=3
Dn Slope=0.005
Boundary for River Rch & Prof#=South Twin Creek,Reach-1,5
Up Type=0
Dn Type=3
Dn Slope=0.005
Boundary for River Rch & Prof#=South Twin Creek,Reach-1,6
Up Type=0
Dn Type=3
Dn Slope=0.005
Boundary for River Rch & Prof#=South Twin Creek,Reach-1,7
Up Type=0
Dn Type=3
Dn Slope=0.005

--- South Twin Creek Trib G.g01 (geometry) ---

Geom Title=Existing Conditions

River Reach=South Twin Creek,Reach-1
Reach XY= 30
      2732226.00      6818311.00      2732079.15      6818159.35
      2732076.15      6817975.06      2732368.52      6817764.62
      2732275.76      6817629.46      2732424.62      6817251.34
      2732424.78      6816971.50      2732226.93      6816351.15
      2732272.33      6816162.58      2731829.13      6815509.37
      2731817.93      6815157.69      2731622.51      6814612.27
      2731526.68      6814545.16      2731668.69      6813760.90
      2731433.32      6813511.10      2731426.91      6813170.84
      2731576.30      6812879.39      2731478.07      6812755.14
      2731467.92      6812157.70      2731276.52      6811645.78
      2731318.21      6810907.58      2731087.24      6810671.00
      2731072.48      6810462.28      2730883.49      6810317.07
      2730918.15      6810207.59      2730833.09      6810111.00
      2731465.95      6809572.11      2731692.68      6809544.36
      2731923.02      6809259.66      2731876.00      6809161.00

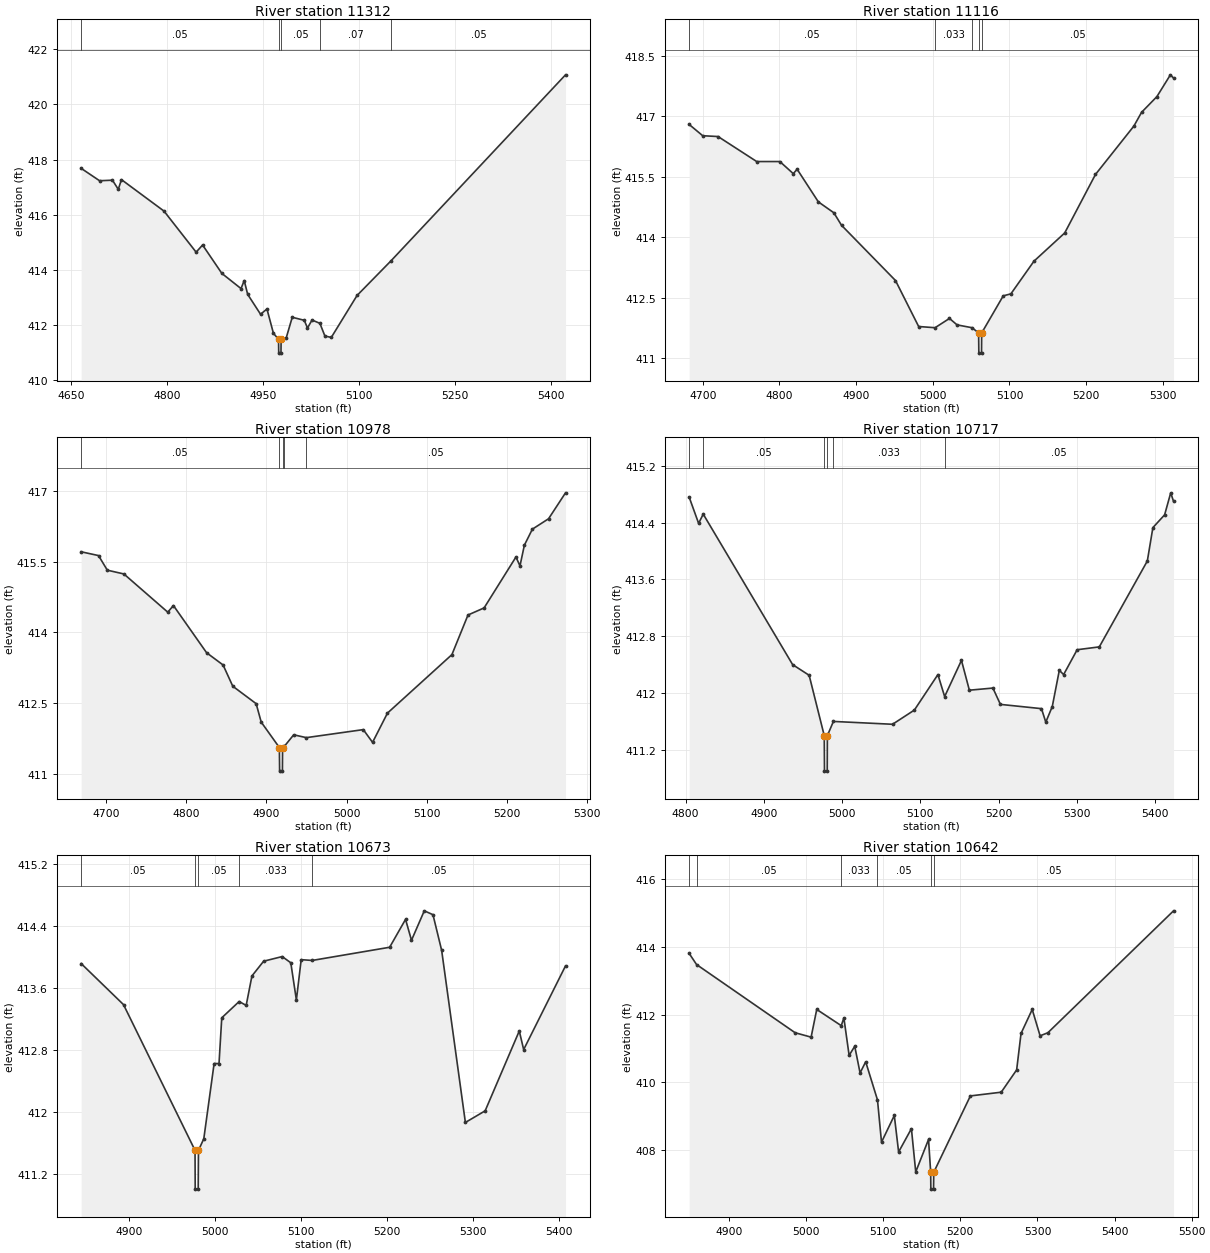
Type RM Length L Ch R = 1,11312,196,196,196
BEGIN DESCRIPTION:
South Twin Creek Trib G11312.433
END DESCRIPTION:
XS GIS Cut Line= 3
      2732464.65      6818252.44      2732132.46      6818217.73
      2731712.04      6818175.89
#Sta/Elev= 30
  4666.0  417.68  4694.8  417.23  4714.9  417.25  4724.0  416.92  4729.0  417.27
  4795.4  416.13  4845.6  414.64  4855.7  414.90  4885.8  413.87  4915.7  413.32
  4920.7  413.61  4926.1  413.11  4946.2  412.39  4956.2  412.58  4966.3  411.70
  4974.3  411.48  4974.6  410.98  4978.1  410.98  4978.3  411.48  4986.4  411.54
  4995.7  412.28  5014.5  412.17  5019.5  411.89  5026.6  412.18  5038.9  412.06
  5046.7  411.60  5056.7  411.55  5096.9  413.07  5150.1  414.33  5422.5  421.07
#Mann=5,-1,0
  4666.0    0.05       0  4974.3    0.05       0  4978.3    0.05       0
  5038.9    0.07       0  5150.1    0.05       0
Bank Sta=4974.3,4978.3
Exp/Cntr=0.3,0.1

Type RM Length L Ch R = 1,11116,138,138,138
BEGIN DESCRIPTION:
South Twin Creek Trib G11116.19
END DESCRIPTION:
XS GIS Cut Line= 3
      2732433.62      6818090.46      2732115.44      6818056.99
      2731804.39      6818035.89
#Sta/Elev= 30
  4682.3  416.80  4700.0  416.52  4720.0  416.50  4770.4  415.88  4800.6  415.88
  4818.1  415.58  4823.1  415.69  4850.8  414.88  4871.0  414.61  4881.0  414.30
  4951.4  412.93  4981.6  411.79  5003.0  411.76  5021.8  411.99  5031.7  411.83
  5051.3  411.76  5059.8  411.63  5060.1  411.13  5063.6  411.13  5063.8  411.63
  5091.9  412.55  5101.9  412.60  5132.0  413.41  5172.1  414.11  5212.2  415.56
  5262.3  416.76  5272.3  417.10  5292.3  417.49  5309.9  418.03  5314.0  417.95
#Mann=5,-1,0
  4682.3    0.05       0  5003.0   0.033       0  5051.3    0.05       0
  5059.8    0.05       0  5063.8    0.05       0
Bank Sta=5059.8,5063.8
Exp/Cntr=0.3,0.1

Type RM Length L Ch R = 1,10978,261,261,261
BEGIN DESCRIPTION:
South Twin Creek Trib G10977.93
END DESCRIPTION:
XS GIS Cut Line= 3
      2732417.67      6818022.56      2732093.23      6817938.71
      2731824.87      6817909.88
#Sta/Elev= 30
  4668.5  415.71  4690.2  415.63  4701.2  415.32  4721.9  415.24  4776.7  414.43
  4783.8  414.57  4825.2  413.57  4845.8  413.31  4857.9  412.86  4887.1  412.49
  4893.4  412.10  4916.1  411.56  4916.4  411.06  4919.9  411.06  4920.1  411.56
  4922.5  411.59  4934.0  411.83  4949.8  411.77  5020.9  411.94  5032.5  411.67
  5051.1  412.29  5131.6  413.53  5151.7  414.37  5171.8  414.52  5211.6  415.60
  5216.6  415.41  5222.1  415.85  5232.1  416.19  5252.3  416.41  5273.5  416.96
#Mann=5,-1,0
  4668.5    0.05       0  4916.1    0.05       0  4920.1    0.05       0
  4922.5   0.033       0  4949.8    0.05       0
Bank Sta=4916.1,4920.1
Exp/Cntr=0.3,0.1

Type RM Length L Ch R = 1,10717,44,44,44
BEGIN DESCRIPTION:
South Twin Creek Trib G10716.92
END DESCRIPTION:
XS GIS Cut Line= 6
      2732443.14      6817950.90      2732307.49      6817811.32
      2732256.52      6817775.05      2732189.42      6817768.27
      2732111.80      6817774.41      2731915.69      6817866.60
#Sta/Elev= 30
  4804.5  414.76  4816.6  414.39  4822.5  414.52  4936.8  412.40  4957.9  412.25
  4977.2  411.40  4977.5  410.90  4981.0  410.90  4981.2  411.40  4988.9  411.60
  5064.5  411.56  5092.4  411.76  5122.5  412.26  5131.1  411.95  5152.6  412.46
  5162.7  412.04  5192.8  412.07  5202.4  411.84  5254.9  411.78  5260.4  411.59
  5268.7  411.81  5277.7  412.32  5283.2  412.26  5300.5  412.61  5328.8  412.65
  5390.2  413.86  5397.3  414.33  5412.3  414.51  5420.1  414.82  5423.7  414.70
#Mann=6,-1,0
  4804.5    0.16       0  4822.5    0.05       0  4977.2   0.033       0
  4981.2    0.05       0  4988.9   0.033       0  5131.1    0.05       0
Bank Sta=4977.2,4981.2
Exp/Cntr=0.3,0.1

Type RM Length L Ch R = 1,10673,31,31,31
BEGIN DESCRIPTION:
South Twin Creek Trib G10672.62
END DESCRIPTION:
XS GIS Cut Line= 6
      2732440.35      6817915.93      2732344.07      6817790.27
      2732301.95      6817752.91      2732236.60      6817718.90
      2732144.06      6817715.42      2731963.63      6817743.65
#Sta/Elev= 30
  4844.6  413.91  4893.9  413.38  4977.1  411.50  4977.3  411.00  4980.8  411.00
  4981.1  411.50  4987.3  411.65  4999.3  412.62  5005.0  412.62  5008.2  413.21
  5028.4  413.42  5036.6  413.37  5043.3  413.75  5056.9  413.94  5078.5  414.00
  5088.5  413.92  5095.0  413.44  5100.6  413.96  5113.4  413.95  5203.5  414.12
  5222.0  414.48  5228.9  414.21  5243.8  414.59  5253.9  414.54  5264.0  414.08
  5291.6  411.86  5314.6  412.01  5354.3  413.04  5359.4  412.80  5408.1  413.88
#Mann=5,-1,0
  4844.6    0.05       0  4977.1    0.05       0  4981.1    0.05       0
  5028.4   0.033       0  5113.4    0.05       0
Bank Sta=4977.1,4981.1
Exp/Cntr=0.3,0.1

Type RM Length L Ch R = 1,10642,298,298,298
BEGIN DESCRIPTION:
South Twin Creek Trib G10642.29
END DESCRIPTION:
XS GIS Cut Line= 6
      2732463.40      6817886.44      2732364.73      6817768.50
      2732298.91      6817707.21      2732232.46      6817673.17
      2732119.61      6817672.91      2731925.28      6817640.13
#Sta/Elev= 30
  4848.2  413.81  4857.8  413.48  4985.7  411.46  5006.4  411.33  5013.7  412.15
  5045.5  411.67  5048.9  411.90  5055.7  410.79  5063.0  411.06  5069.9  410.27
  5077.2  410.60  5092.5  409.47  5097.7  408.22  5114.3  409.01  5119.9  407.93
  5136.5  408.62  5142.1  407.34  5158.7  408.30  5161.5  407.33  5161.7  406.83
  5165.2  406.83  5165.5  407.33  5213.0  409.59  5253.0  409.70  5273.0  410.36
  5278.7  411.44  5293.2  412.15  5303.4  411.37  5313.5  411.46  5476.5  415.07
#Mann=6,-1,0
  4848.2    0.16       0  4857.8    0.05       0  5045.5   0.033       0
  5092.5    0.05       0  5161.5    0.05       0  5165.5    0.05       0
Bank Sta=5161.5,5165.5
Exp/Cntr=0.3,0.1

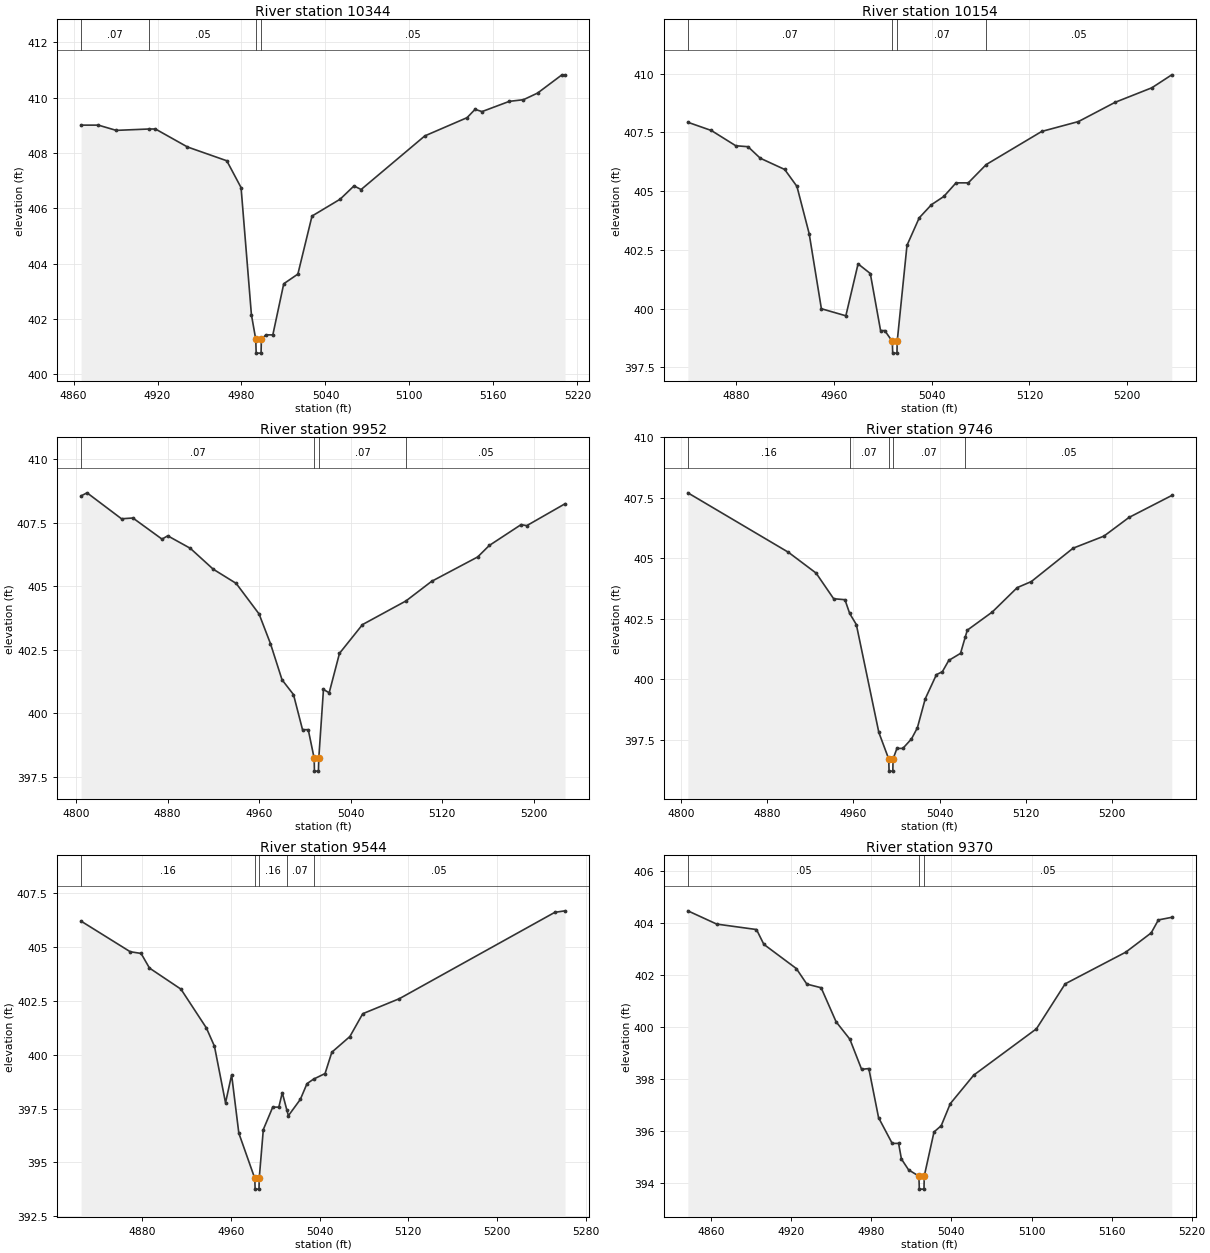
Type RM Length L Ch R = 1,10344,190,190,190
BEGIN DESCRIPTION:
South Twin Creek Trib G10343.65
END DESCRIPTION:
XS GIS Cut Line= 3
      2732458.10      6817550.45      2732326.46      6817523.98
      2732116.50      6817498.26
#Sta/Elev= 30
  4865.4  409.01  4877.7  409.01  4890.5  408.82  4914.0  408.87  4918.5  408.87
  4941.4  408.22  4969.5  407.72  4979.7  406.75  4987.1  402.15  4990.2  401.26
  4990.5  400.76  4994.0  400.76  4994.2  401.26  4997.4  401.42  5002.4  401.42
  5010.2  403.27  5020.3  403.62  5030.4  405.72  5050.5  406.33  5060.4  406.81
  5065.5  406.68  5111.0  408.62  5141.2  409.28  5146.9  409.58  5151.9  409.50
  5171.4  409.87  5181.5  409.93  5191.6  410.17  5209.0  410.83  5211.2  410.83
#Mann=4,-1,0
  4865.4    0.07       0  4914.0    0.05       0  4990.2    0.05       0
  4994.2    0.05       0
Bank Sta=4990.2,4994.2
Exp/Cntr=0.3,0.1

Type RM Length L Ch R = 1,10154,202,202,202
BEGIN DESCRIPTION:
South Twin Creek Trib G10153.66
END DESCRIPTION:
XS GIS Cut Line= 3
      2732535.17      6817352.42      2732374.21      6817349.93
      2732139.80      6817337.95
#Sta/Elev= 30
  4840.7  407.93  4859.9  407.58  4879.9  406.93  4889.9  406.89  4899.9  406.40
  4919.9  405.92  4929.9  405.20  4939.9  403.19  4949.9  399.99  4969.9  399.69
  4979.9  401.90  4989.9  401.49  4998.3  399.06  5001.7  399.06  5007.9  398.60
  5008.2  398.10  5011.7  398.10  5011.9  398.60  5019.9  402.69  5029.9  403.86
  5039.9  404.42  5050.0  404.77  5060.0  405.35  5070.0  405.35  5084.7  406.13
  5130.1  407.54  5160.1  407.96  5190.1  408.78  5220.2  409.40  5236.4  409.95
#Mann=4,-1,0
  4840.7    0.07       0  5007.9    0.07       0  5011.9    0.07       0
  5084.7    0.05       0
Bank Sta=5007.9,5011.9
Exp/Cntr=0.3,0.1

Type RM Length L Ch R = 1,9952,206,206,206
BEGIN DESCRIPTION:
South Twin Creek Trib G9951.69
END DESCRIPTION:
XS GIS Cut Line= 3
      2732621.19      6817151.41      2732425.17      6817164.11
      2732200.20      6817190.10
#Sta/Elev= 30
  4804.5  408.55  4809.7  408.67  4839.8  407.65  4849.8  407.68  4875.2  406.85
  4880.2  406.98  4899.9  406.49  4919.9  405.67  4940.0  405.11  4960.0  403.91
  4970.0  402.74  4980.1  401.32  4990.1  400.74  4998.0  399.36  5003.0  399.36
  5008.2  398.23  5008.4  397.73  5011.9  397.73  5012.2  398.23  5016.3  400.94
  5021.3  400.81  5030.3  402.36  5050.4  403.49  5088.4  404.42  5110.8  405.19
  5151.1  406.15  5161.2  406.60  5189.0  407.42  5194.0  407.38  5227.4  408.24
#Mann=4,-1,0
  4804.5    0.07       0  5008.2    0.07       0  5012.2    0.07       0
  5088.4    0.05       0
Bank Sta=5008.2,5012.2
Exp/Cntr=0.3,0.1

Type RM Length L Ch R = 1,9746,202,202,202
BEGIN DESCRIPTION:
South Twin Creek Trib G9745.69
END DESCRIPTION:
XS GIS Cut Line= 3
      2732605.09      6816899.91      2732418.97      6816959.40
      2732186.83      6817063.24
#Sta/Elev= 30
  4806.1  407.71  4899.6  405.25  4925.3  404.39  4941.6  403.33  4952.1  403.29
  4956.5  402.72  4962.7  402.26  4983.6  397.80  4992.8  396.70  4993.1  396.20
  4996.6  396.20  4996.8  396.70  5000.4  397.14  5005.9  397.14  5013.9  397.53
  5019.4  397.99  5026.7  399.19  5037.1  400.19  5042.6  400.31  5048.6  400.78
  5059.5  401.07  5064.0  401.76  5065.8  402.03  5089.0  402.78  5112.2  403.79
  5125.3  404.04  5164.1  405.42  5192.8  405.92  5216.0  406.69  5255.8  407.60
#Mann=5,-1,0
  4806.1    0.16       0  4956.5    0.07       0  4992.8    0.07       0
  4996.8    0.07       0  5064.0    0.05       0
Bank Sta=4992.8,4996.8
Exp/Cntr=0.3,0.1

Type RM Length L Ch R = 1,9544,174,174,174
BEGIN DESCRIPTION:
South Twin Creek Trib G9544.48
END DESCRIPTION:
XS GIS Cut Line= 3
      2732535.06      6816699.12      2732375.63      6816773.29
      2732142.40      6816889.91
#Sta/Elev= 30
  4824.9  406.21  4869.2  404.79  4879.0  404.71  4886.6  404.03  4915.0  403.05
  4937.9  401.25  4945.2  400.40  4955.2  397.77  4960.7  399.07  4967.2  396.36
  4981.6  394.26  4981.9  393.76  4985.4  393.76  4985.6  394.26  4989.3  396.53
  4997.8  397.57  5003.3  397.57  5006.4  398.24  5010.5  397.44  5011.9  397.17
  5022.7  397.93  5028.7  398.66  5034.6  398.87  5045.0  399.13  5051.1  400.12
  5067.4  400.85  5079.0  401.91  5112.1  402.61  5252.3  406.62  5261.5  406.69
#Mann=5,-1,0
  4824.9    0.16       0  4981.6    0.07       0  4985.6    0.16       0
  5010.5    0.07       0  5034.6    0.05       0
Bank Sta=4981.6,4985.6
Exp/Cntr=0.3,0.1

Type RM Length L Ch R = 1,9370,201,201,201
BEGIN DESCRIPTION:
South Twin Creek Trib G9369.97
END DESCRIPTION:
XS GIS Cut Line= 3
      2732468.94      6816557.28      2732322.03      6816614.87
      2732131.68      6816689.64
#Sta/Elev= 30
  4842.7  404.46  4864.3  403.95  4894.1  403.74  4899.6  403.17  4923.9  402.24
  4931.8  401.64  4942.5  401.50  4953.7  400.19  4964.0  399.52  4972.8  398.36
  4978.2  398.39  4985.5  396.50  4995.7  395.51  5000.5  395.51  5002.6  394.91
  5008.0  394.49  5015.7  394.25  5016.0  393.75  5019.5  393.75  5019.7  394.25
  5027.0  395.95  5032.4  396.19  5039.2  397.04  5056.8  398.14  5103.7  399.92
  5125.2  401.65  5170.6  402.87  5189.6  403.61  5195.0  404.11  5205.0  404.21
#Mann=3,-1,0
  4842.7    0.05       0  5015.7    0.05       0  5019.7    0.05       0
Bank Sta=5015.7,5019.7
Exp/Cntr=0.3,0.1

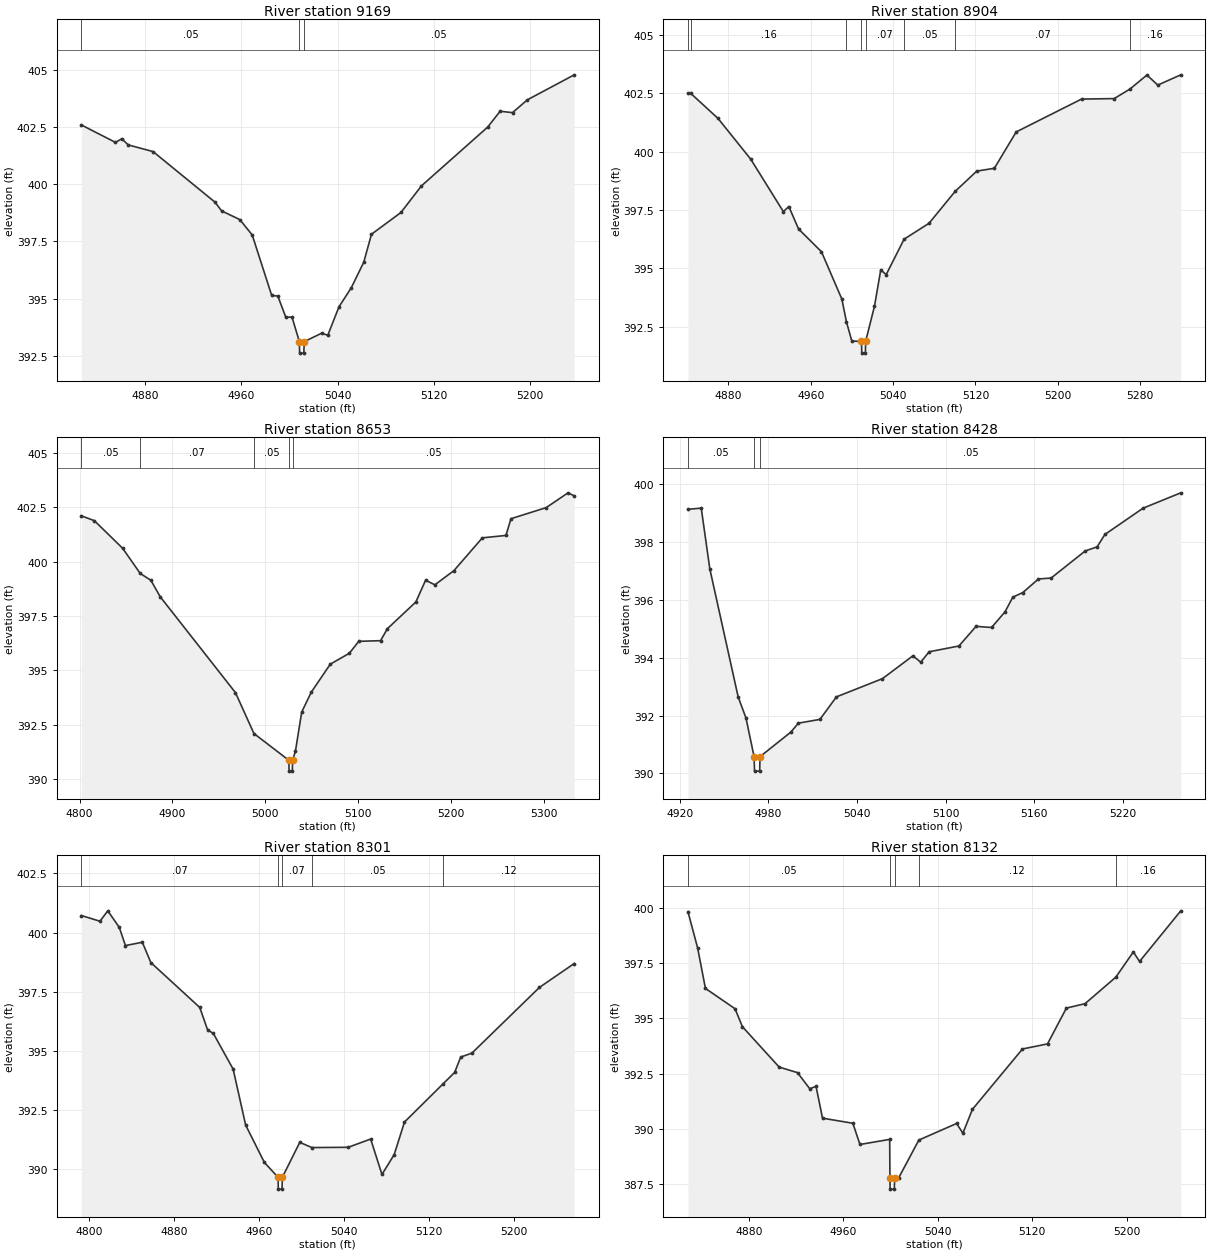
Type RM Length L Ch R = 1,9169,265,265,265
BEGIN DESCRIPTION:
South Twin Creek Trib G9169.14
END DESCRIPTION:
XS GIS Cut Line= 3
      2732443.76      6816388.08      2732276.66      6816429.17
      2732046.15      6816486.04
#Sta/Elev= 30
  4827.0  402.58  4855.3  401.82  4860.5  401.98  4865.9  401.71  4886.5  401.42
  4938.0  399.21  4943.5  398.83  4958.6  398.45  4968.9  397.78  4985.1  395.14
  4990.2  395.11  4996.8  394.19  5002.0  394.19  5008.1  393.12  5008.3  392.62
  5011.8  392.62  5012.1  393.12  5026.6  393.49  5031.7  393.40  5041.0  394.64
  5051.3  395.48  5061.6  396.59  5068.0  397.81  5092.5  398.76  5109.5  399.92
  5164.6  402.49  5174.9  403.18  5185.2  403.12  5197.6  403.68  5236.5  404.77
#Mann=3,-1,0
  4827.0    0.05       0  5008.1    0.05       0  5012.1    0.05       0
Bank Sta=5008.1,5012.1
Exp/Cntr=0.3,0.1

Type RM Length L Ch R = 1,8904,251,251,251
BEGIN DESCRIPTION:
South Twin Creek Trib G8903.59
END DESCRIPTION:
XS GIS Cut Line= 3
      2732427.95      6816146.55      2732275.14      6816197.07
      2731974.93      6816301.50
#Sta/Elev= 30
  4840.7  402.50  4843.5  402.50  4869.9  401.43  4901.7  399.68  4933.4  397.43
  4938.7  397.65  4948.1  396.69  4970.4  395.71  4990.2  393.68  4994.7  392.70
  4999.9  391.88  5009.3  391.86  5009.6  391.36  5013.1  391.36  5013.3  391.86
  5021.9  393.37  5028.0  394.93  5033.3  394.73  5050.7  396.25  5074.9  396.93
  5100.3  398.30  5121.3  399.17  5138.4  399.29  5159.6  400.85  5223.1  402.26
  5254.8  402.28  5270.1  402.69  5286.6  403.29  5297.2  402.86  5319.5  403.30
#Mann=8,-1,0
  4840.7    0.05       0  4843.5    0.16       0  4994.7    0.07       0
  5009.3    0.07       0  5013.3    0.07       0  5050.7    0.05       0
  5100.3    0.07       0  5270.1    0.16       0
Bank Sta=5009.3,5013.3
Exp/Cntr=0.3,0.1

Type RM Length L Ch R = 1,8653,225,225,225
BEGIN DESCRIPTION:
South Twin Creek Trib G8653.19
END DESCRIPTION:
XS GIS Cut Line= 3
      2732349.76      6815956.59      2732152.67      6815989.62
      2731829.44      6816062.16
#Sta/Elev= 30
  4801.9  402.10  4815.8  401.88  4846.3  400.61  4865.3  399.45  4876.7  399.14
  4886.8  398.38  4967.9  393.97  4987.8  392.09  5025.4  390.86  5025.7  390.36
  5029.2  390.36  5029.4  390.86  5032.5  391.27  5039.3  393.08  5049.6  393.99
  5070.1  395.28  5090.6  395.78  5100.8  396.33  5124.3  396.36  5131.6  396.91
  5162.3  398.14  5172.8  399.14  5182.8  398.93  5203.3  399.58  5234.0  401.09
  5259.4  401.20  5264.8  401.97  5302.8  402.48  5326.3  403.16  5333.0  403.02
#Mann=5,-1,0
  4801.9    0.05       0  4865.3    0.07       0  4987.8    0.05       0
  5025.4    0.05       0  5029.4    0.05       0
Bank Sta=5025.4,5029.4
Exp/Cntr=0.3,0.1

Type RM Length L Ch R = 1,8428,127,127,127
BEGIN DESCRIPTION:
South Twin Creek Trib G8427.58
END DESCRIPTION:
XS GIS Cut Line= 3
      2732099.91      6815783.07      2732028.55      6815809.52
      2731784.86      6815893.64
#Sta/Elev= 30
  4925.5  399.14  4934.5  399.18  4940.3  397.08  4959.5  392.65  4964.8  391.92
  4970.3  390.58  4970.6  390.08  4974.1  390.08  4974.3  390.58  4995.2  391.43
  5000.3  391.74  5014.9  391.87  5026.1  392.65  5057.3  393.28  5077.9  394.07
  5083.2  393.85  5088.9  394.21  5109.1  394.41  5120.7  395.09  5131.2  395.05
  5140.3  395.59  5145.6  396.10  5152.4  396.26  5163.0  396.73  5171.5  396.76
  5194.7  397.70  5202.7  397.84  5208.0  398.27  5233.9  399.18  5259.4  399.71
#Mann=3,-1,0
  4925.5    0.05       0  4970.3    0.05       0  4974.3    0.05       0
Bank Sta=4970.3,4974.3
Exp/Cntr=0.3,0.1

Type RM Length L Ch R = 1,8301,169,169,169
BEGIN DESCRIPTION:
South Twin Creek Trib G8301.45
END DESCRIPTION:
XS GIS Cut Line= 3
      2732168.97      6815620.18      2731976.94      6815698.99
      2731735.14      6815783.13
#Sta/Elev= 30
  4793.0  400.72  4810.4  400.48  4817.8  400.92  4828.6  400.22  4834.4  399.45
  4850.3  399.59  4858.3  398.73  4904.3  396.83  4911.7  395.88  4917.1  395.73
  4935.7  394.22  4947.5  391.85  4965.1  390.27  4978.0  389.64  4978.2  389.14
  4981.7  389.14  4982.0  389.64  4998.4  391.12  5009.8  390.90  5043.9  390.91
  5065.1  391.26  5075.7  389.76  5087.2  390.60  5096.9  391.98  5133.5  393.61
  5144.1  394.08  5149.8  394.73  5160.4  394.90  5223.9  397.68  5256.6  398.69
#Mann=5,-1,0
  4793.0    0.07       0  4978.0    0.07       0  4982.0    0.07       0
  5009.8    0.05       0  5133.5    0.12       0
Bank Sta=4978,4982
Exp/Cntr=0.3,0.1

Type RM Length L Ch R = 1,8132,212,212,212
BEGIN DESCRIPTION:
South Twin Creek Trib G8132.41
END DESCRIPTION:
XS GIS Cut Line= 3
      2732043.74      6815510.71      2731879.20      6815567.46
      2731649.48      6815648.06
#Sta/Elev= 30
  4828.3  399.82  4836.5  398.18  4843.1  396.35  4868.2  395.43  4874.4  394.62
  4905.6  392.79  4921.1  392.54  4931.5  391.81  4936.8  391.92  4942.3  390.48
  4968.0  390.25  4974.0  389.29  4999.2  389.52  4999.4  387.77  4999.6  387.27
  5003.1  387.27  5003.4  387.77  5006.7  387.77  5023.9  389.49  5055.9  390.24
  5061.2  389.80  5069.3  390.88  5111.7  393.61  5132.9  393.84  5148.9  395.46
  5164.7  395.66  5190.8  396.86  5205.6  398.00  5210.9  397.57  5245.8  399.86
#Mann=5,-1,0
  4828.3    0.05       0  4999.4    0.05       0  5003.4    0.05       0
  5023.9    0.12       0  5190.8    0.16       0
Bank Sta=4999.4,5003.4
Exp/Cntr=0.3,0.1

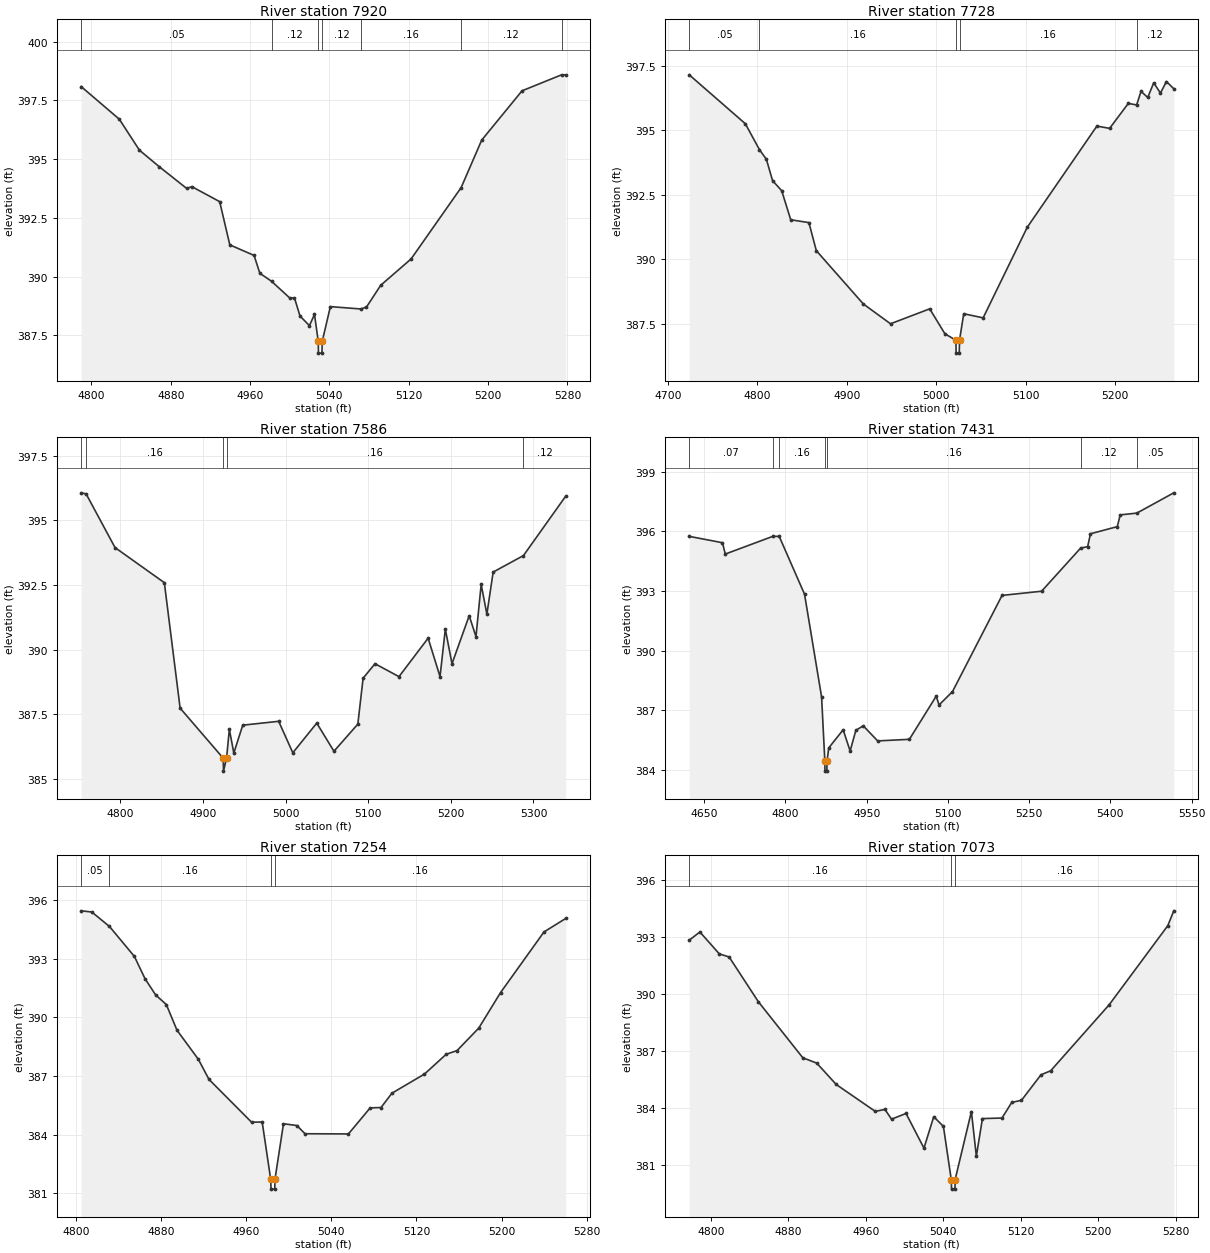
Type RM Length L Ch R = 1,7920,192,192,192
BEGIN DESCRIPTION:
South Twin Creek Trib G7919.75
END DESCRIPTION:
XS GIS Cut Line= 3
      2732084.07      6815359.27      2731871.56      6815392.37
      2731602.80      6815443.19
#Sta/Elev= 30
  4789.7  398.09  4828.2  396.70  4848.5  395.38  4868.7  394.67  4896.2  393.75
  4901.3  393.83  4929.4  393.19  4939.6  391.35  4964.1  390.90  4969.9  390.14
  4981.7  389.80  5000.0  389.09  5004.8  389.09  5010.4  388.32  5019.9  387.91
  5025.0  388.39  5028.8  387.24  5029.0  386.74  5032.5  386.74  5032.8  387.24
  5041.0  388.72  5071.8  388.62  5077.4  388.70  5091.8  389.63  5122.4  390.75
  5172.9  393.79  5193.6  395.81  5234.3  397.91  5274.1  398.59  5278.3  398.59
#Mann=7,-1,0
  4789.7    0.05       0  4981.7    0.12       0  5028.8    0.07       0
  5032.8    0.12       0  5071.8    0.16       0  5172.9    0.12       0
  5274.1    0.05       0
Bank Sta=5028.8,5032.8
Exp/Cntr=0.3,0.1

Type RM Length L Ch R = 1,7728,142,142,142
BEGIN DESCRIPTION:
South Twin Creek Trib G7727.95
END DESCRIPTION:
XS GIS Cut Line= 3
      2732047.86      6815192.16      2731774.42      6815237.68
      2731577.31      6815413.59
#Sta/Elev= 30
  4724.0  397.16  4786.7  395.26  4802.5  394.25  4810.2  393.88  4817.1  393.05
  4827.3  392.66  4837.4  391.53  4857.7  391.42  4866.0  390.33  4918.5  388.26
  4948.9  387.49  4992.7  388.07  5009.7  387.10  5022.0  386.85  5022.2  386.35
  5025.7  386.35  5026.0  386.85  5030.7  387.88  5052.4  387.72  5101.7  391.24
  5179.5  395.17  5193.7  395.08  5214.6  396.05  5223.9  395.99  5228.8  396.52
  5236.3  396.28  5243.0  396.85  5250.5  396.45  5257.2  396.90  5265.4  396.62
#Mann=5,-1,0
  4724.0    0.05       0  4802.5    0.16       0  5022.0    0.07       0
  5026.0    0.16       0  5223.9    0.12       0
Bank Sta=5022,5026
Exp/Cntr=0.3,0.1

Type RM Length L Ch R = 1,7586,155,155,155
BEGIN DESCRIPTION:
South Twin Creek Trib G7585.89
END DESCRIPTION:
XS GIS Cut Line= 3
      2732018.12      6815030.64      2731783.34      6815122.51
      2731577.77      6815386.24
#Sta/Elev= 30
  4752.5  396.07  4758.5  396.03  4793.5  393.95  4853.2  392.59  4872.3  387.73
  4924.5  385.79  4924.8  385.29  4928.5  385.79  4931.9  386.91  4937.3  385.99
  4948.1  387.07  4991.6  387.22  5008.7  386.00  5037.7  387.15  5058.5  386.06
  5087.4  387.11  5093.8  388.89  5108.2  389.45  5137.2  388.95  5172.5  390.44
  5186.9  388.95  5193.3  390.79  5201.4  389.45  5222.2  391.31  5230.4  390.50
  5236.7  392.52  5243.6  391.37  5251.2  393.00  5287.9  393.64  5339.0  395.94
#Mann=5,-1,0
  4752.5    0.07       0  4758.5    0.16       0  4924.5    0.07       0
  4928.5    0.16       0  5287.9    0.12       0
Bank Sta=4924.5,4928.5
Exp/Cntr=0.3,0.1

Type RM Length L Ch R = 1,7431,177,177,177
BEGIN DESCRIPTION:
South Twin Creek Trib G7431.413
END DESCRIPTION:
XS GIS Cut Line= 3
      2732068.30      6814876.62      2731709.36      6814994.17
      2731525.36      6815477.32
#Sta/Elev= 30
  4622.3  395.75  4683.6  395.43  4688.9  394.86  4776.6  395.75  4788.4  395.75
  4835.2  392.84  4866.7  387.67  4872.7  384.44  4872.9  383.94  4876.4  383.94
  4876.7  384.44  4879.9  385.11  4906.5  386.02  4919.4  384.95  4929.9  385.99
  4943.6  386.22  4970.2  385.46  5028.8  385.54  5078.3  387.71  5083.6  387.27
  5108.4  387.94  5199.9  392.78  5272.9  392.99  5345.0  395.16  5357.9  395.23
  5363.2  395.88  5412.7  396.24  5418.1  396.83  5448.8  396.92  5517.0  397.94
#Mann=7,-1,0
  4622.3    0.07       0  4776.6    0.05       0  4788.4    0.16       0
  4872.7    0.07       0  4876.7    0.16       0  5345.0    0.12       0
  5448.8    0.05       0
Bank Sta=4872.7,4876.7
Exp/Cntr=0.3,0.1

Type RM Length L Ch R = 1,7254,181,181,181
BEGIN DESCRIPTION:
South Twin Creek Trib G7253.731
END DESCRIPTION:
XS GIS Cut Line= 3
      2731876.03      6814861.00      2731676.00      6814861.00
      2731425.98      6814911.00
#Sta/Elev= 30
  4805.1  395.44  4815.1  395.38  4831.7  394.64  4855.1  393.11  4865.1  391.97
  4875.1  391.14  4885.1  390.65  4895.1  389.34  4915.1  387.86  4925.1  386.83
  4965.1  384.64  4975.1  384.65  4983.1  381.72  4983.4  381.22  4986.9  381.22
  4987.1  381.72  4995.1  384.56  5007.7  384.47  5015.3  384.05  5056.1  384.04
  5076.5  385.37  5086.7  385.39  5096.9  386.12  5127.5  387.10  5147.9  388.11
  5158.1  388.30  5178.5  389.45  5198.9  391.26  5239.7  394.36  5260.1  395.05
#Mann=4,-1,0
  4805.1    0.05       0  4831.7    0.16       0  4983.1    0.07       0
  4987.1    0.16       0
Bank Sta=4983.1,4987.1
Exp/Cntr=0.3,0.1

Type RM Length L Ch R = 1,7073,273,273,273
BEGIN DESCRIPTION:
South Twin Creek Trib G7073.47
END DESCRIPTION:
XS GIS Cut Line= 3
      2731846.95      6814673.24      2731624.40      6814697.44
      2731349.86      6814730.64
#Sta/Elev= 30
  4777.6  392.82  4788.6  393.25  4808.7  392.10  4818.8  391.94  4849.0  389.59
  4894.9  386.65  4909.3  386.37  4929.4  385.25  4969.7  383.84  4979.7  383.94
  4986.5  383.43  5001.5  383.73  5020.0  381.91  5030.1  383.56  5040.1  383.05
  5048.2  380.26  5048.5  379.76  5052.0  379.76  5052.2  380.26  5069.0  383.83
  5074.1  381.49  5080.4  383.46  5100.6  383.49  5110.7  384.31  5120.7  384.42
  5140.9  385.76  5150.9  385.97  5211.4  389.44  5271.8  393.58  5278.0  394.36
#Mann=3,-1,0
  4777.6    0.16       0  5048.2    0.07       0  5052.2    0.16       0
Bank Sta=5048.2,5052.2
Exp/Cntr=0.3,0.1

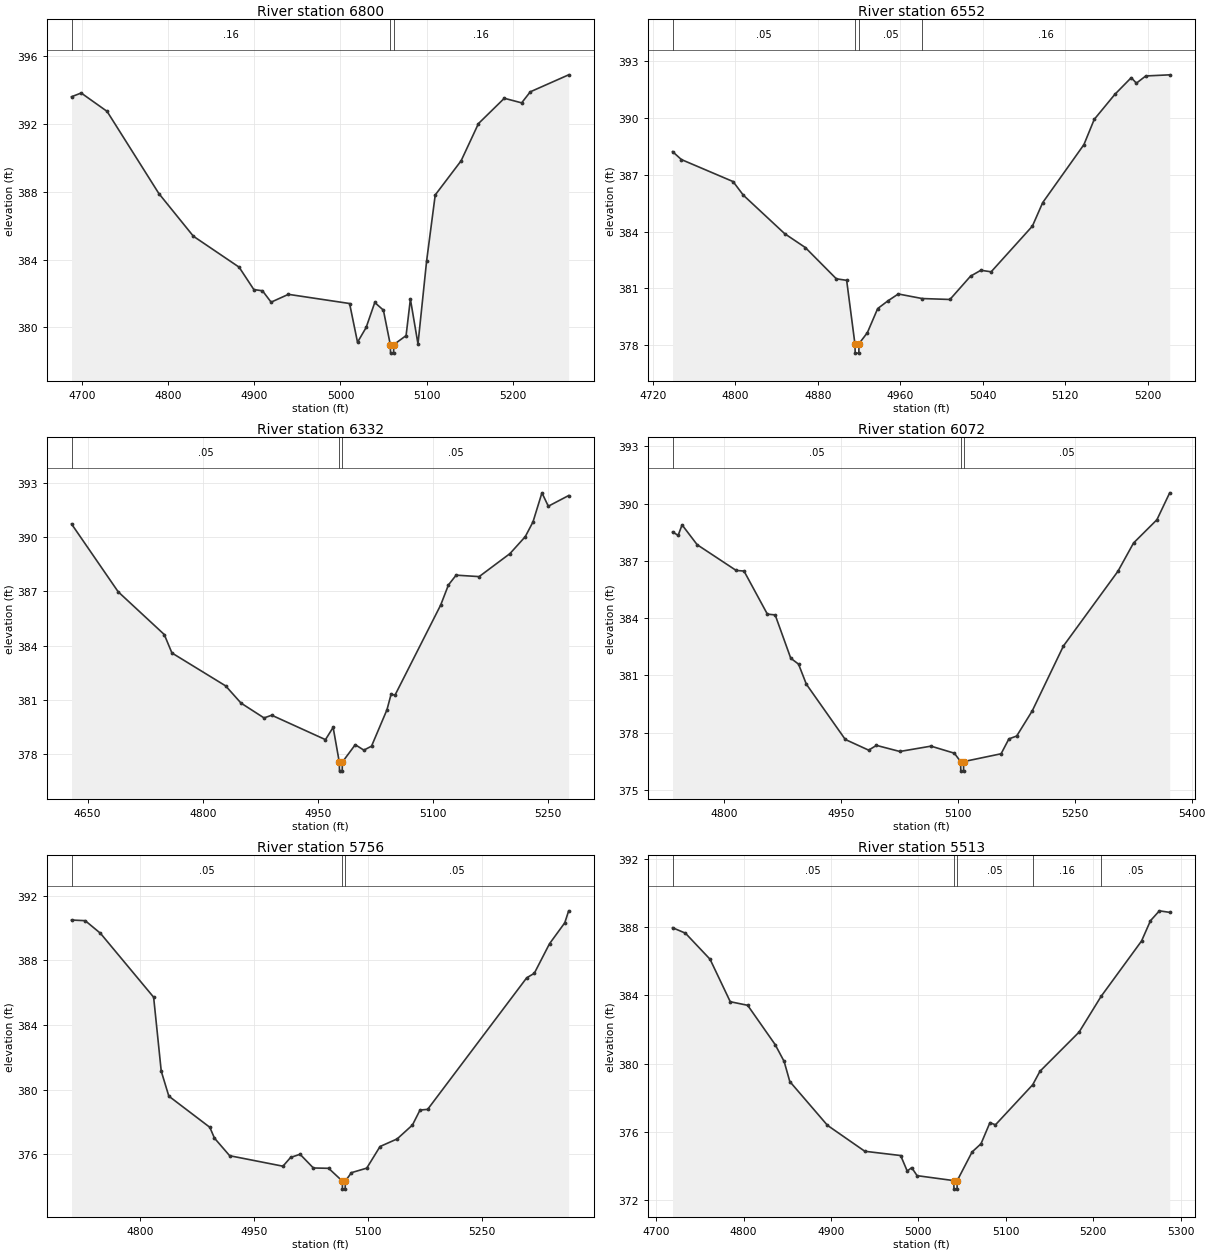
Type RM Length L Ch R = 1,6800,248,248,248
BEGIN DESCRIPTION:
South Twin Creek Trib G6799.95
END DESCRIPTION:
XS GIS Cut Line= 3
      2731837.17      6814466.92      2731519.20      6814481.95
      2731261.55      6814496.68
#Sta/Elev= 30
  4688.2  393.58  4699.4  393.80  4729.4  392.72  4789.5  387.88  4829.5  385.37
  4882.5  383.55  4899.6  382.23  4909.6  382.16  4919.6  381.49  4939.7  381.95
  5010.6  381.41  5019.8  379.13  5029.8  380.00  5039.8  381.47  5049.8  381.02
  5057.8  378.99  5058.1  378.49  5061.6  378.49  5061.8  378.99  5076.1  379.52
  5081.1  381.67  5089.9  379.03  5099.9  383.91  5109.9  387.80  5139.9  389.81
  5160.0  392.00  5190.0  393.49  5210.1  393.22  5220.1  393.87  5264.6  394.87
#Mann=3,-1,0
  4688.2    0.16       0  5057.8    0.07       0  5061.8    0.16       0
Bank Sta=5057.8,5061.8
Exp/Cntr=0.3,0.1

Type RM Length L Ch R = 1,6552,220,220,220
BEGIN DESCRIPTION:
South Twin Creek Trib G6551.54
END DESCRIPTION:
XS GIS Cut Line= 3
      2731794.58      6814275.42      2731531.80      6814258.85
      2731312.83      6814255.43
#Sta/Elev= 30
  4739.0  388.22  4747.6  387.80  4797.7  386.64  4807.7  385.92  4847.8  383.89
  4867.8  383.16  4897.9  381.51  4907.9  381.43  4915.9  378.09  4916.2  377.59
  4919.7  377.59  4919.9  378.09  4928.0  378.67  4938.0  379.94  4948.0  380.35
  4958.0  380.71  4981.1  380.47  5008.1  380.42  5028.1  381.65  5038.1  381.96
  5048.1  381.88  5088.1  384.29  5098.1  385.53  5138.1  388.59  5148.1  389.92
  5168.1  391.24  5184.0  392.12  5189.0  391.83  5198.1  392.21  5221.3  392.27
#Mann=4,-1,0
  4739.0    0.05       0  4915.9    0.07       0  4919.9    0.05       0
  4981.1    0.16       0
Bank Sta=4915.9,4919.9
Exp/Cntr=0.3,0.1

Type RM Length L Ch R = 1,6332,260,260,260
BEGIN DESCRIPTION:
South Twin Creek Trib G6332.42
END DESCRIPTION:
XS GIS Cut Line= 3
      2731946.80      6814053.87      2731573.39      6814053.75
      2731299.57      6814067.98
#Sta/Elev= 30
  4629.1  390.72  4689.9  386.97  4749.9  384.61  4759.9  383.59  4829.9  381.77
  4849.9  380.82  4879.9  380.00  4889.9  380.15  4959.9  378.80  4969.9  379.48
  4977.9  377.56  4978.2  377.06  4981.7  377.06  4981.9  377.56  4998.7  378.52
  5009.9  378.22  5019.9  378.44  5040.0  380.45  5045.4  381.31  5050.5  381.26
  5110.0  386.24  5120.1  387.35  5130.1  387.89  5160.1  387.81  5200.2  389.08
  5220.2  390.02  5230.2  390.83  5241.9  392.44  5250.2  391.70  5276.7  392.29
#Mann=3,-1,0
  4629.1    0.05       0  4977.9    0.05       0  4981.9    0.05       0
Bank Sta=4977.9,4981.9
Exp/Cntr=0.3,0.1

Type RM Length L Ch R = 1,6072,316,316,316
BEGIN DESCRIPTION:
South Twin Creek Trib G6071.74
END DESCRIPTION:
XS GIS Cut Line= 3
      2731897.64      6813816.18      2731625.81      6813809.79
      2731259.61      6813809.80
#Sta/Elev= 30
  4733.7  388.52  4740.9  388.34  4745.9  388.89  4765.3  387.85  4815.4  386.50
  4825.4  386.47  4855.4  384.21  4865.4  384.17  4885.4  381.90  4895.4  381.59
  4905.4  380.54  4955.4  377.64  4985.4  377.08  4995.4  377.33  5025.4  377.01
  5065.4  377.29  5095.4  376.92  5103.4  376.48  5103.7  375.98  5107.2  375.98
  5107.4  376.48  5155.4  376.89  5165.4  377.67  5175.4  377.82  5195.4  379.14
  5235.4  382.54  5305.4  386.46  5325.4  387.94  5355.4  389.16  5371.8  390.57
#Mann=3,-1,0
  4733.7    0.05       0  5103.4    0.05       0  5107.4    0.05       0
Bank Sta=5103.4,5107.4
Exp/Cntr=0.3,0.1

Type RM Length L Ch R = 1,5756,243,243,243
BEGIN DESCRIPTION:
South Twin Creek Trib G5755.97
END DESCRIPTION:
XS GIS Cut Line= 3
      2731783.97      6813571.06      2731486.04      6813579.20
      2731130.86      6813601.15
#Sta/Elev= 30
  4709.7  390.50  4727.7  390.46  4747.7  389.68  4817.7  385.72  4827.7  381.14
  4837.7  379.59  4891.6  377.66  4897.7  376.99  4917.7  375.90  4987.8  375.25
  4997.8  375.79  5010.3  375.99  5027.8  375.14  5047.9  375.12  5065.9  374.33
  5066.1  373.83  5069.6  373.83  5069.9  374.33  5077.9  374.85  5098.0  375.13
  5115.5  376.47  5138.0  376.94  5158.1  377.80  5168.1  378.73  5178.1  378.77
  5308.4  386.92  5318.4  387.20  5338.4  389.03  5358.5  390.33  5363.6  391.07
#Mann=3,-1,0
  4709.7    0.05       0  5065.9    0.05       0  5069.9    0.05       0
Bank Sta=5065.9,5069.9
Exp/Cntr=0.3,0.1

Type RM Length L Ch R = 1,5513,191,191,191
BEGIN DESCRIPTION:
South Twin Creek Trib G5512.52
END DESCRIPTION:
XS GIS Cut Line= 3
      2731750.38      6813436.05      2731474.34      6813373.28
      2731194.45      6813316.90
#Sta/Elev= 30
  4718.8  387.97  4733.5  387.65  4761.7  386.12  4784.8  383.63  4804.7  383.42
  4836.1  381.12  4846.4  380.13  4852.9  378.95  4896.0  376.38  4938.7  374.86
  4979.7  374.61  4987.2  373.70  4992.3  373.90  4998.5  373.43  5040.4  373.14
  5040.7  372.64  5044.2  372.64  5044.4  373.14  5061.4  374.82  5071.6  375.30
  5081.8  376.54  5088.1  376.41  5130.7  378.76  5139.0  379.55  5183.8  381.85
  5208.9  383.94  5255.2  387.19  5265.4  388.38  5275.6  388.96  5287.4  388.87
#Mann=5,-1,0
  4718.8    0.05       0  5040.4    0.05       0  5044.4    0.05       0
  5130.7    0.16       0  5208.9    0.05       0
Bank Sta=5040.4,5044.4
Exp/Cntr=0.3,0.1