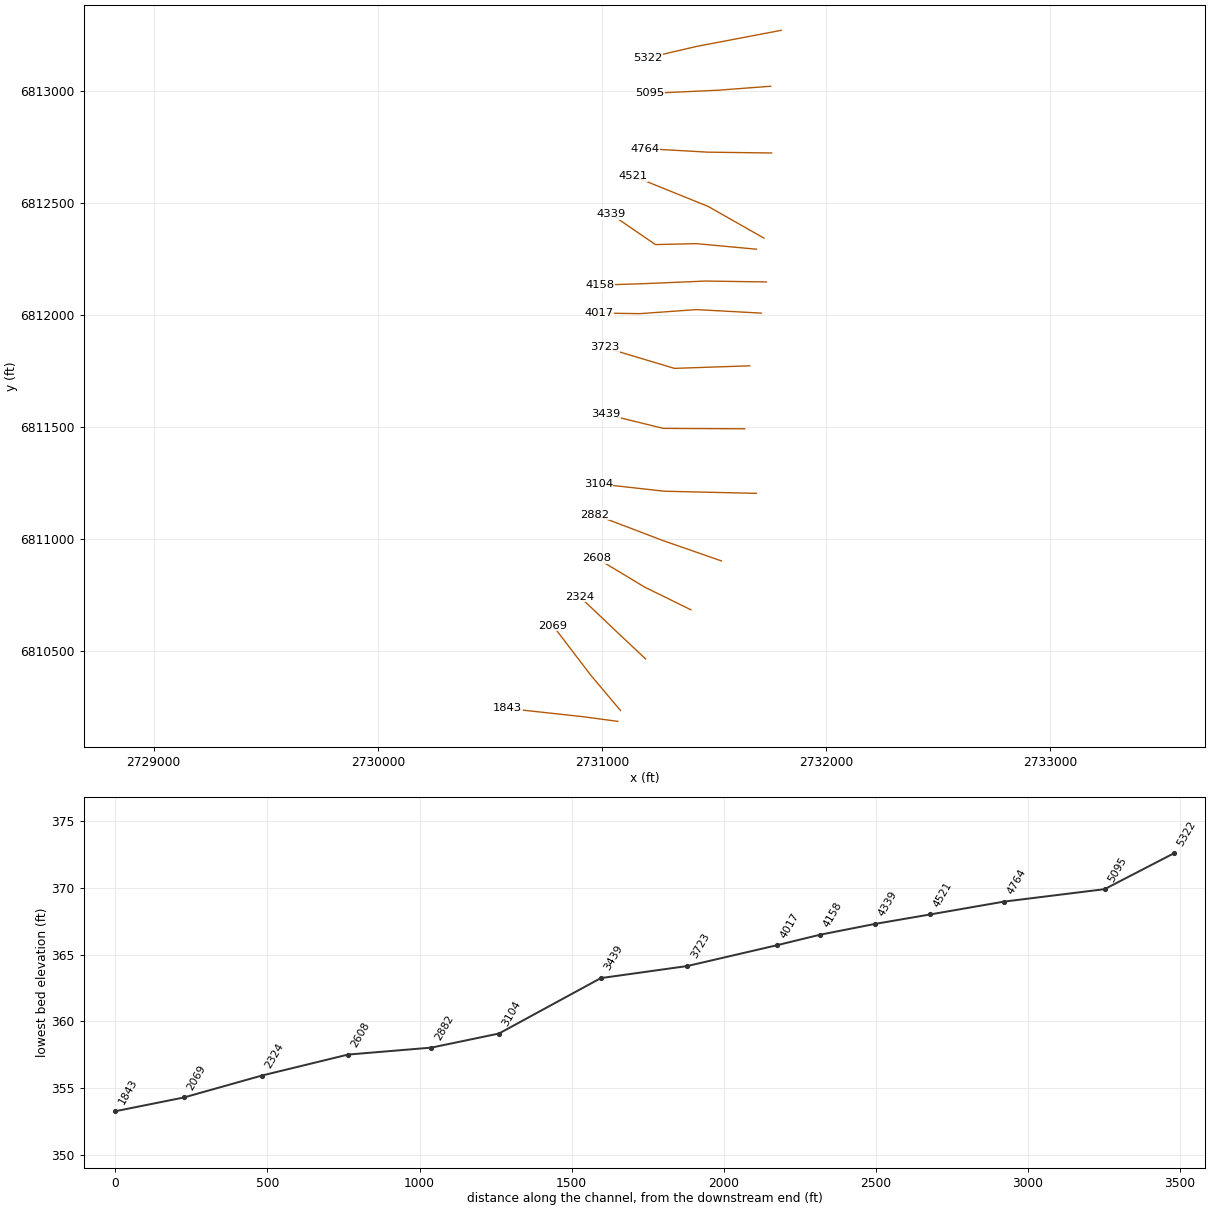
HEC-RAS study South Twin Creek Trib G.prj: South Twin Creek Trib G Base Level Engineering

--- South Twin Creek Trib G.g01 (geometry) --- (continued)

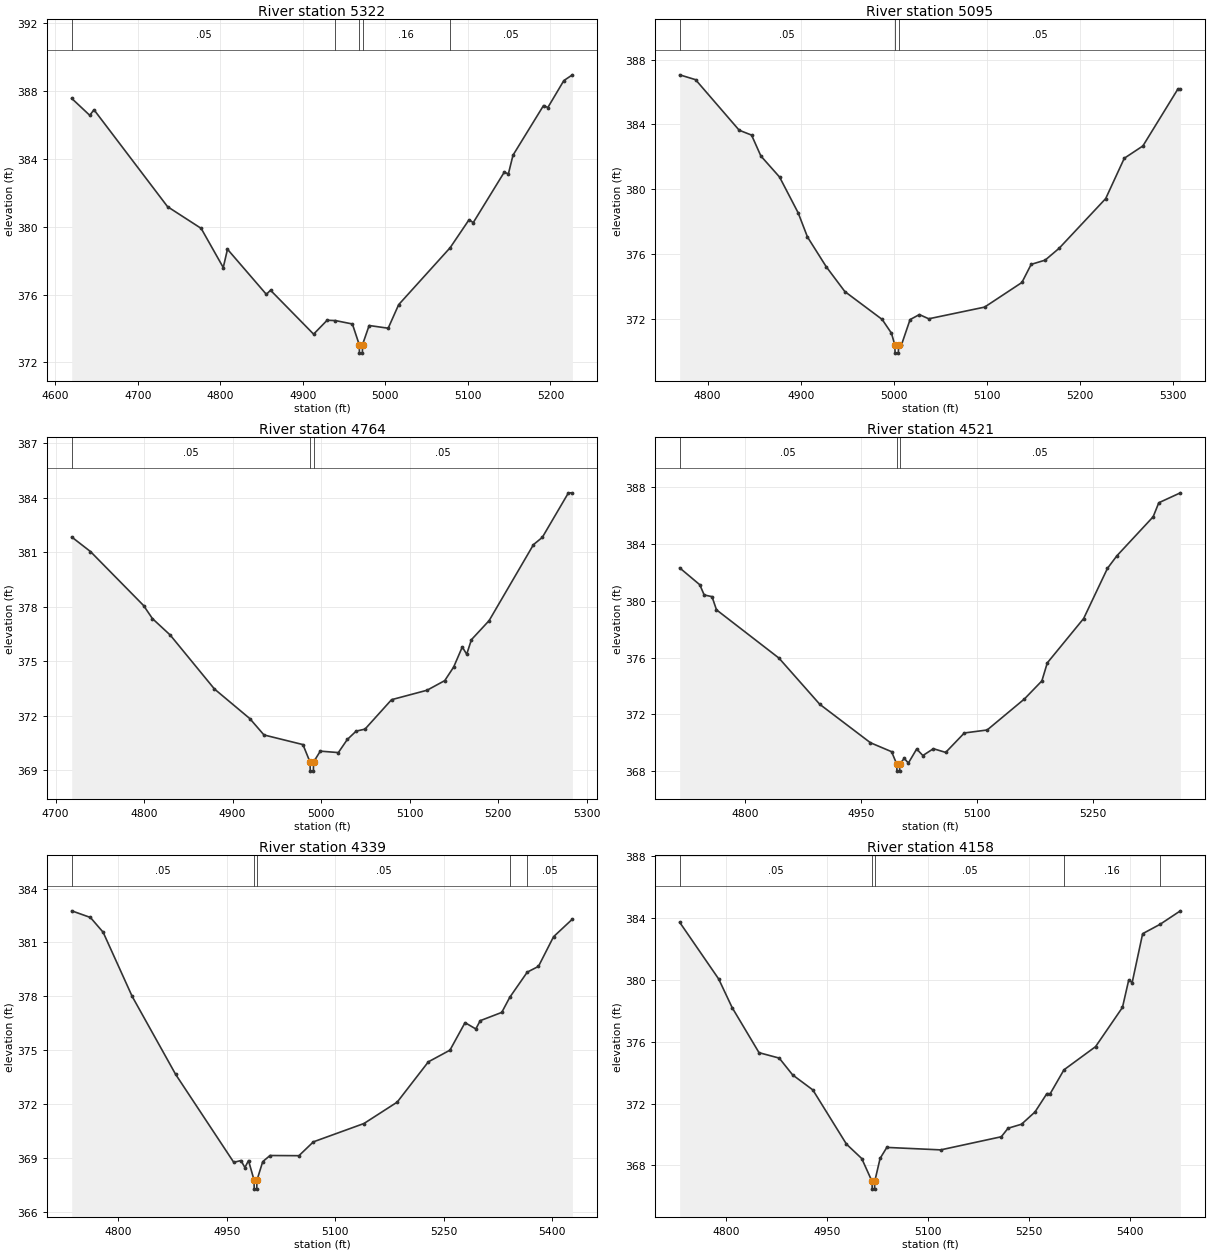
Type RM Length L Ch R = 1,5322,227,227,227
BEGIN DESCRIPTION:
South Twin Creek Trib G5322.08
END DESCRIPTION:
XS GIS Cut Line= 3
      2731800.18      6813270.53      2731423.31      6813198.90
      2731205.83      6813148.33
#Sta/Elev= 30
  4619.8  387.58  4641.7  386.58  4646.8  386.91  4736.0  381.19  4776.7  379.91
  4803.5  377.60  4808.6  378.68  4855.7  376.02  4860.8  376.26  4913.0  373.67
  4929.4  374.49  4939.5  374.47  4960.0  374.27  4968.3  373.05  4968.6  372.55
  4972.1  372.55  4972.3  373.05  4980.3  374.18  5003.4  374.02  5016.1  375.41
  5078.5  378.77  5101.4  380.42  5106.5  380.25  5144.0  383.22  5149.1  383.13
  5154.7  384.23  5191.7  387.16  5196.9  387.04  5216.3  388.63  5226.7  388.97
#Mann=5,-1,0
  4619.8    0.05       0  4939.5    0.16       0  4968.3    0.07       0
  4972.3    0.16       0  5078.5    0.05       0
Bank Sta=4968.3,4972.3
Exp/Cntr=0.3,0.1

Type RM Length L Ch R = 1,5095,331,331,331
BEGIN DESCRIPTION:
South Twin Creek Trib G5094.63
END DESCRIPTION:
XS GIS Cut Line= 3
      2731753.06      6813020.96      2731519.74      6813003.35
      2731215.74      6812989.27
#Sta/Elev= 30
  4769.9  387.06  4787.0  386.76  4833.9  383.64  4847.2  383.34  4857.2  382.05
  4877.3  380.75  4897.3  378.54  4907.3  377.05  4927.4  375.22  4947.5  373.68
  4987.6  371.96  4997.6  371.11  5001.2  370.38  5001.5  369.88  5005.0  369.88
  5005.2  370.38  5008.3  370.38  5017.6  371.95  5027.6  372.26  5037.7  372.00
  5097.7  372.72  5137.8  374.24  5147.8  375.36  5162.8  375.62  5177.8  376.35
  5227.9  379.42  5247.9  381.91  5267.9  382.67  5305.6  386.19  5308.2  386.19
#Mann=3,-1,0
  4769.9    0.05       0  5001.2    0.05       0  5005.2    0.05       0
Bank Sta=5001.2,5005.2
Exp/Cntr=0.3,0.1

Type RM Length L Ch R = 1,4764,243,243,243
BEGIN DESCRIPTION:
South Twin Creek Trib G4764.06
END DESCRIPTION:
XS GIS Cut Line= 3
      2731757.20      6812723.19      2731471.84      6812726.87
      2731192.08      6812742.80
#Sta/Elev= 30
  4718.3  381.83  4739.5  381.03  4799.5  378.06  4809.5  377.34  4829.5  376.44
  4879.5  373.47  4919.5  371.84  4935.5  370.94  4979.5  370.41  4987.5  369.45
  4987.8  368.95  4991.3  368.95  4991.5  369.45  4999.1  370.05  5019.5  369.97
  5029.6  370.69  5039.6  371.15  5049.6  371.26  5079.6  372.88  5119.7  373.40
  5139.7  373.93  5149.8  374.68  5159.5  375.78  5164.5  375.38  5169.8  376.18
  5189.8  377.23  5239.9  381.41  5249.9  381.81  5279.4  384.26  5283.9  384.26
#Mann=3,-1,0
  4718.3    0.05       0  4987.5    0.05       0  4991.5    0.05       0
Bank Sta=4987.5,4991.5
Exp/Cntr=0.3,0.1

Type RM Length L Ch R = 1,4521,182,182,182
BEGIN DESCRIPTION:
South Twin Creek Trib G4520.87
END DESCRIPTION:
XS GIS Cut Line= 3
      2731723.48      6812343.13      2731474.60      6812484.48
      2731140.10      6812619.93
#Sta/Elev= 30
  4715.5  382.32  4741.5  381.13  4747.2  380.41  4757.3  380.29  4763.1  379.36
  4843.8  375.96  4896.6  372.70  4962.1  369.99  4989.4  369.36  4996.0  368.49
  4996.3  367.99  4999.8  367.99  5000.0  368.49  5005.7  368.89  5011.1  368.56
  5021.8  369.55  5029.8  369.09  5043.4  369.57  5059.3  369.31  5083.4  370.68
  5112.9  370.89  5161.1  373.08  5183.6  374.35  5190.6  375.62  5237.6  378.75
  5268.4  382.29  5280.7  383.18  5327.4  385.92  5334.7  386.91  5362.6  387.61
#Mann=3,-1,0
  4715.5    0.05       0  4996.0    0.05       0  5000.0    0.05       0
Bank Sta=4996,5000
Exp/Cntr=0.3,0.1

Type RM Length L Ch R = 1,4339,181,181,181
BEGIN DESCRIPTION:
South Twin Creek Trib G4339.37
END DESCRIPTION:
XS GIS Cut Line= 4
      2731689.30      6812293.84      2731421.15      6812318.70
      2731238.93      6812314.42      2731039.81      6812450.94
#Sta/Elev= 30
  4735.4  382.76  4761.3  382.39  4778.9  381.57  4819.1  378.00  4879.3  373.66
  4959.7  368.77  4969.7  368.87  4975.1  368.48  4980.1  368.87  4987.8  367.78
  4988.0  367.28  4991.5  367.28  4991.8  367.78  4999.8  368.81  5009.9  369.15
  5049.9  369.14  5069.9  369.91  5139.9  370.93  5185.9  372.12  5229.0  374.36
  5258.9  375.01  5279.8  376.54  5294.7  376.19  5300.8  376.65  5330.6  377.11
  5341.7  377.95  5365.9  379.35  5381.4  379.67  5402.3  381.32  5428.4  382.30
#Mann=5,-1,0
  4735.4    0.05       0  4987.8    0.05       0  4991.8    0.05       0
  5341.7    0.16       0  5365.9    0.05       0
Bank Sta=4987.8,4991.8
Exp/Cntr=0.3,0.1

Type RM Length L Ch R = 1,4158,141,141,141
BEGIN DESCRIPTION:
South Twin Creek Trib G4157.98
END DESCRIPTION:
XS GIS Cut Line= 4
      2731733.96      6812147.69      2731463.31      6812151.71
      2731185.69      6812139.99      2730989.94      6812133.67
#Sta/Elev= 30
  4730.9  383.74  4788.9  380.07  4808.9  378.22  4848.9  375.30  4878.9  374.95
  4898.9  373.86  4928.9  372.89  4978.9  369.38  5001.6  368.45  5016.9  366.97
  5017.2  366.47  5020.7  366.47  5020.9  366.97  5028.9  368.46  5038.9  369.17
  5119.0  369.01  5209.1  369.86  5219.1  370.41  5239.1  370.67  5259.1  371.46
  5276.8  372.65  5281.8  372.65  5302.2  374.19  5349.2  375.69  5389.2  378.23
  5398.6  380.02  5403.6  379.83  5419.2  383.00  5445.2  383.61  5475.3  384.48
#Mann=5,-1,0
  4730.9    0.05       0  5016.9    0.05       0  5020.9    0.05       0
  5302.2    0.16       0  5445.2    0.05       0
Bank Sta=5016.9,5020.9
Exp/Cntr=0.3,0.1

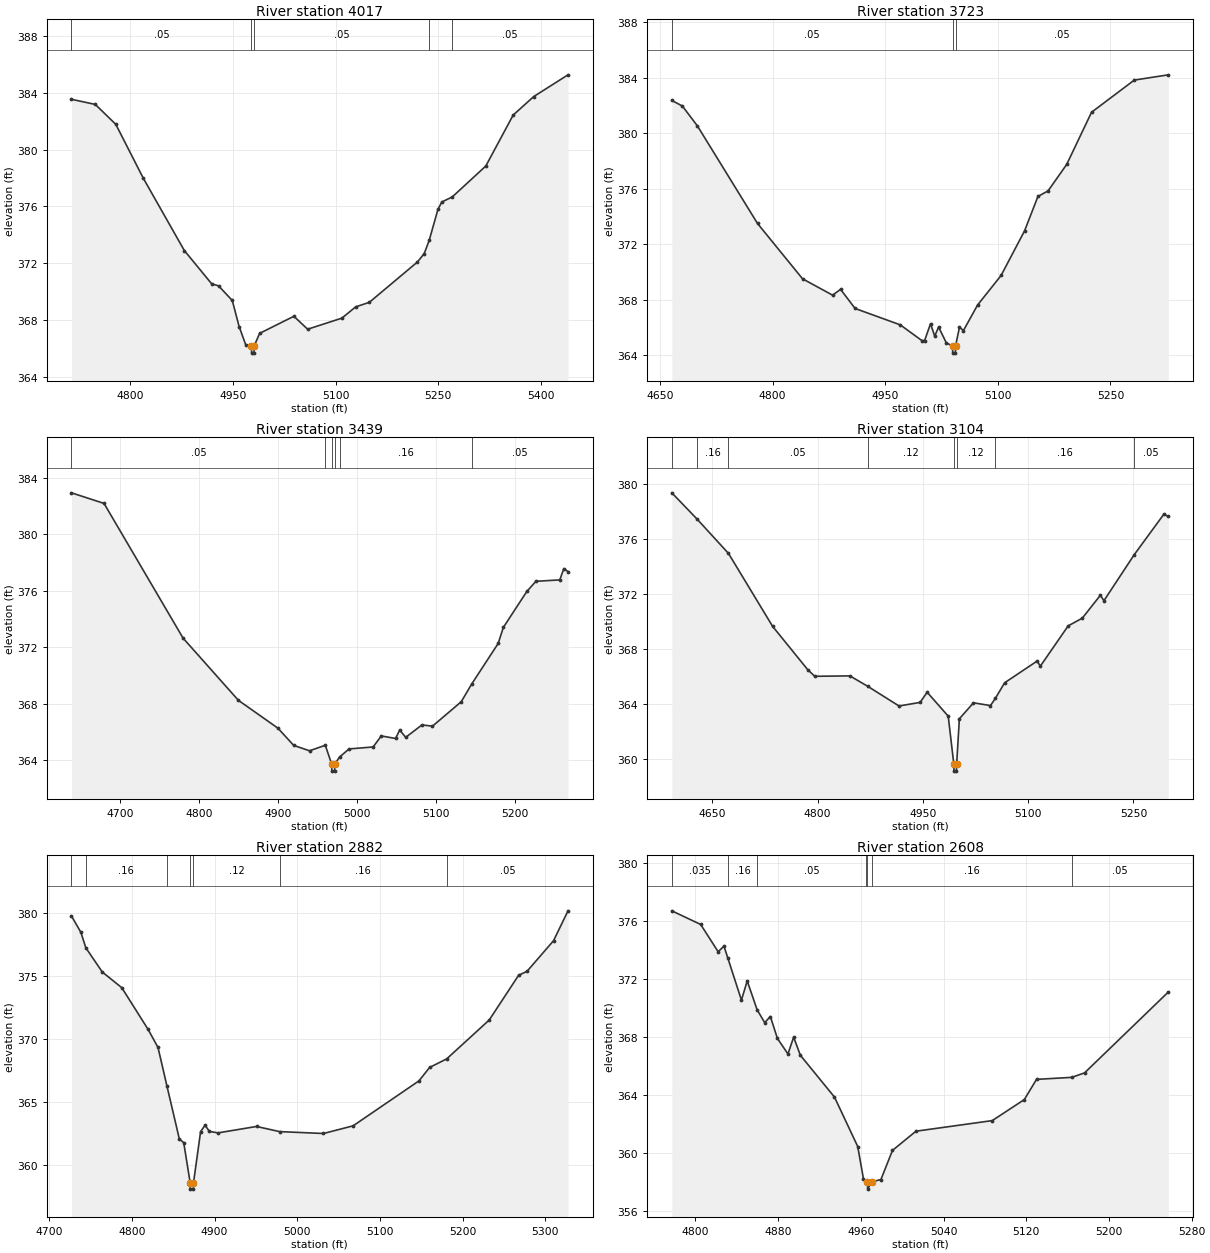
Type RM Length L Ch R = 1,4017,294,294,294
BEGIN DESCRIPTION:
South Twin Creek Trib G4017.23
END DESCRIPTION:
XS GIS Cut Line= 4
      2731710.72      6812008.60      2731422.20      6812024.33
      2731169.72      6812006.27      2730985.81      6812008.87
#Sta/Elev= 30
  4713.9  383.53  4748.7  383.17  4778.7  381.77  4818.8  377.99  4878.9  372.90
  4918.9  370.56  4928.9  370.42  4949.0  369.39  4959.0  367.56  4969.0  366.23
  4977.0  366.19  4977.3  365.69  4980.8  365.69  4981.0  366.19  4989.0  367.08
  5039.1  368.28  5059.2  367.37  5109.3  368.15  5129.4  368.94  5149.4  369.26
  5219.6  372.09  5229.6  372.68  5236.9  373.61  5249.7  375.79  5255.3  376.31
  5270.7  376.67  5319.7  378.84  5359.7  382.42  5389.7  383.72  5439.9  385.25
#Mann=5,-1,0
  4713.9    0.05       0  4977.0    0.05       0  4981.0    0.05       0
  5236.9    0.16       0  5270.7    0.05       0
Bank Sta=4977,4981
Exp/Cntr=0.3,0.1

Type RM Length L Ch R = 1,3723,284,284,284
BEGIN DESCRIPTION:
South Twin Creek Trib G3723.26
END DESCRIPTION:
XS GIS Cut Line= 3
      2731660.00      6811773.44      2731323.53      6811762.06
      2731012.54      6811855.20
#Sta/Elev= 30
  4665.8  382.36  4679.8  381.96  4699.8  380.53  4779.9  373.49  4839.9  369.50
  4879.9  368.32  4890.5  368.74  4909.9  367.36  4970.0  366.18  4998.7  365.05
  5002.5  365.05  5010.3  366.26  5015.9  365.37  5021.1  366.02  5031.2  364.90
  5039.6  364.64  5039.9  364.14  5043.4  364.14  5043.6  364.64  5048.9  366.01
  5054.2  365.77  5073.0  367.61  5104.3  369.74  5135.6  372.96  5153.4  375.44
  5166.9  375.84  5191.7  377.75  5224.8  381.51  5281.7  383.83  5327.1  384.21
#Mann=3,-1,0
  4665.8    0.05       0  5039.6    0.05       0  5043.6    0.05       0
Bank Sta=5039.6,5043.6
Exp/Cntr=0.3,0.1

Type RM Length L Ch R = 1,3439,335,335,335
BEGIN DESCRIPTION:
South Twin Creek Trib G3439.24
END DESCRIPTION:
XS GIS Cut Line= 3
      2731637.21      6811492.35      2731273.95      6811494.20
      2731016.57      6811557.44
#Sta/Elev= 30
  4638.4  382.93  4679.6  382.18  4779.6  372.65  4849.6  368.25  4899.6  366.28
  4919.6  365.06  4939.6  364.68  4959.6  365.07  4967.6  363.74  4967.9  363.24
  4971.4  363.24  4971.6  363.74  4977.7  364.24  4989.6  364.81  5020.1  364.95
  5030.4  365.73  5048.5  365.55  5053.7  366.15  5061.3  365.63  5081.9  366.51
  5095.2  366.42  5131.6  368.15  5144.9  369.41  5178.3  372.27  5184.9  373.41
  5214.7  375.96  5226.1  376.67  5256.3  376.77  5261.4  377.57  5266.7  377.36
#Mann=6,-1,0
  4638.4    0.05       0  4959.6    0.16       0  4967.6    0.07       0
  4971.6    0.16       0  4977.7    0.16       0  5144.9    0.05       0
Bank Sta=4967.6,4971.6
Exp/Cntr=0.3,0.1

Type RM Length L Ch R = 1,3104,222,222,222
BEGIN DESCRIPTION:
South Twin Creek Trib G3103.65
END DESCRIPTION:
XS GIS Cut Line= 3
      2731689.56      6811204.38      2731279.07      6811213.77
      2730984.20      6811246.68
#Sta/Elev= 30
  4592.5  379.35  4628.8  377.42  4673.2  374.94  4736.1  369.63  4786.1  366.48
  4796.1  366.00  4846.1  366.03  4871.3  365.28  4916.1  363.84  4946.2  364.10
  4956.2  364.84  4986.2  363.10  4994.2  359.60  4994.4  359.10  4997.9  359.10
  4998.2  359.60  5002.1  362.91  5022.2  364.07  5046.4  363.87  5053.3  364.39
  5066.6  365.53  5112.6  367.10  5117.6  366.75  5157.1  369.67  5177.2  370.23
  5203.0  371.90  5208.0  371.50  5251.2  374.85  5293.3  377.79  5299.8  377.63
#Mann=8,-1,0
  4592.5    0.05       0  4628.8    0.16       0  4673.2    0.05       0
  4871.3    0.12       0  4994.2    0.07       0  4998.2    0.12       0
  5053.3    0.16       0  5251.2    0.05       0
Bank Sta=4994.2,4998.2
Exp/Cntr=0.3,0.1

Type RM Length L Ch R = 1,2882,274,274,274
BEGIN DESCRIPTION:
South Twin Creek Trib G2881.5
END DESCRIPTION:
XS GIS Cut Line= 3
      2731533.41      6810902.84      2731272.48      6810993.68
      2730969.68      6811108.98
#Sta/Elev= 30
  4727.1  379.80  4738.5  378.49  4744.4  377.27  4764.3  375.34  4787.9  374.09
  4819.7  370.77  4831.7  369.33  4842.5  366.26  4857.5  362.04  4862.8  361.75
  4870.6  358.55  4870.8  358.05  4874.3  358.05  4874.6  358.55  4883.2  362.63
  4888.6  363.14  4893.9  362.64  4904.4  362.53  4950.8  363.04  4978.7  362.63
  5031.7  362.48  5067.6  363.09  5147.2  366.67  5160.1  367.74  5180.7  368.42
  5232.2  371.52  5267.7  375.08  5277.8  375.39  5309.9  377.83  5327.4  380.21
#Mann=7,-1,0
  4727.1   0.035       0  4744.4    0.16       0  4842.5    0.12       0
  4870.6    0.07       0  4874.6    0.12       0  4978.7    0.16       0
  5180.7    0.05       0
Bank Sta=4870.6,4874.6
Exp/Cntr=0.3,0.1

Type RM Length L Ch R = 1,2608,284,284,284
BEGIN DESCRIPTION:
South Twin Creek Trib G2608.21
END DESCRIPTION:
XS GIS Cut Line= 3
      2731397.64      6810684.52      2731191.23      6810785.75
      2730976.83      6810914.92
#Sta/Elev= 30
  4777.2  376.70  4805.1  375.76  4822.0  373.88  4827.6  374.27  4831.2  373.48
  4844.5  370.55  4850.1  371.87  4859.7  369.88  4867.0  369.00  4872.5  369.42
  4879.3  367.91  4889.5  366.84  4895.0  368.00  4901.5  366.75  4934.5  363.87
  4957.0  360.46  4962.5  358.24  4965.1  358.10  4966.4  358.03  4966.6  357.53
  4970.4  358.03  4979.4  358.19  4990.6  360.20  5013.3  361.52  5087.1  362.25
  5118.1  363.70  5129.9  365.09  5164.1  365.23  5176.4  365.54  5257.4  371.11
#Mann=7,-1,0
  4777.2   0.035       0  4831.2    0.16       0  4859.7    0.05       0
  4965.1    0.16       0  4966.4    0.07       0  4970.4    0.16       0
  5164.1    0.05       0
Bank Sta=4966.4,4970.4
Exp/Cntr=0.3,0.1

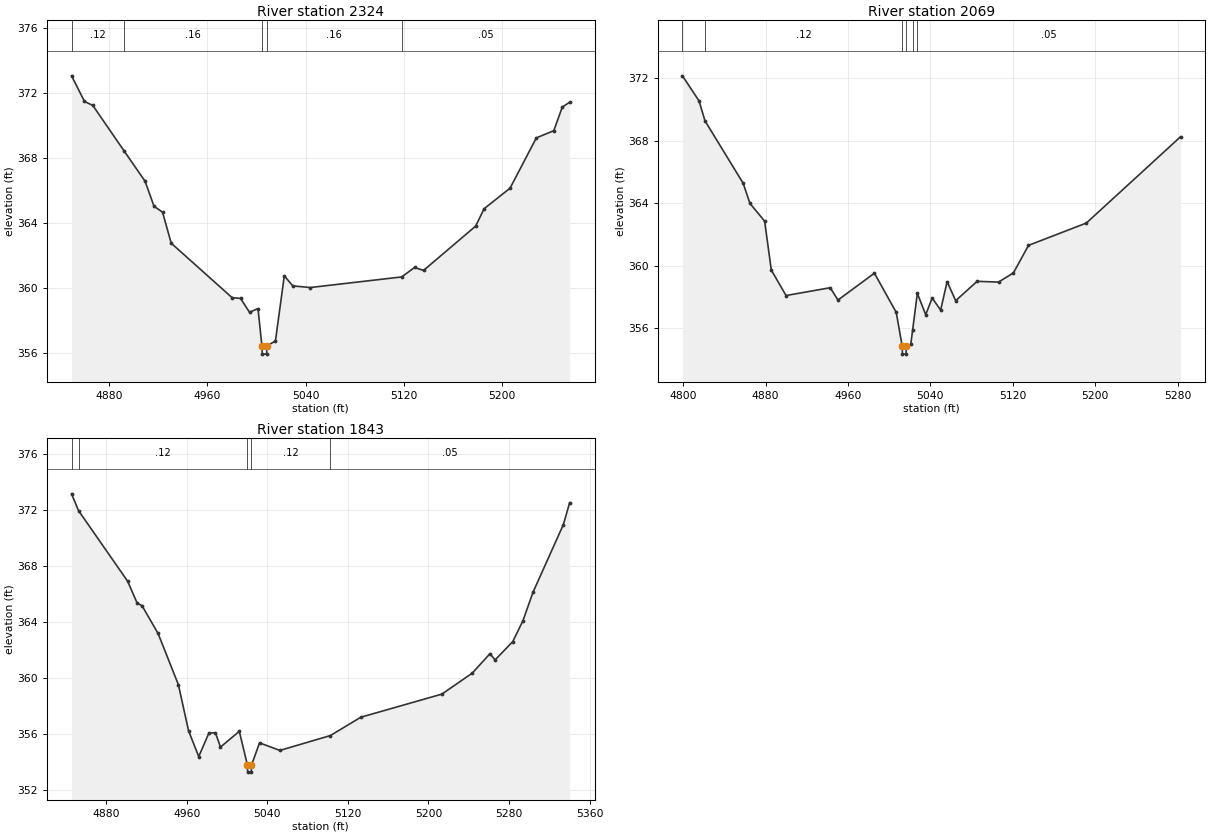
Type RM Length L Ch R = 1,2324,255,255,255
BEGIN DESCRIPTION:
South Twin Creek Trib G2324.03
END DESCRIPTION:
XS GIS Cut Line= 3
      2731195.07      6810465.47      2731080.43      6810573.16
      2730900.45      6810743.80
#Sta/Elev= 30
  4849.6  373.05  4860.1  371.48  4866.9  371.23  4892.5  368.42  4909.4  366.58
  4916.7  365.04  4923.6  364.68  4930.7  362.77  4980.2  359.43  4987.1  359.38
  4994.4  358.53  5001.3  358.76  5004.5  356.46  5004.8  355.96  5008.3  355.96
  5008.5  356.46  5015.5  356.77  5022.7  360.77  5029.6  360.15  5043.8  360.05
  5118.2  360.70  5128.7  361.28  5136.0  361.10  5178.4  363.82  5185.3  364.89
  5206.4  366.15  5227.8  369.24  5242.0  369.68  5248.9  371.13  5254.9  371.43
#Mann=5,-1,0
  4849.6    0.12       0  4892.5    0.16       0  5004.5    0.07       0
  5008.5    0.16       0  5118.2    0.05       0
Bank Sta=5004.5,5008.5
Exp/Cntr=0.3,0.1

Type RM Length L Ch R = 1,2069,226,226,226
BEGIN DESCRIPTION:
South Twin Creek Trib G2069.1
END DESCRIPTION:
XS GIS Cut Line= 3
      2731082.86      6810235.51      2730950.50      6810392.60
      2730781.74      6810613.74
#Sta/Elev= 30
  4799.3  372.14  4815.4  370.54  4821.2  369.26  4858.3  365.26  4864.8  363.98
  4879.1  362.84  4885.6  359.71  4899.9  358.08  4942.8  358.58  4950.3  357.79
  4985.7  359.51  5006.9  357.00  5012.7  354.83  5012.9  354.33  5016.4  354.33
  5016.7  354.83  5021.0  354.95  5022.8  355.87  5027.4  358.22  5035.5  356.85
  5041.8  357.92  5050.0  357.15  5056.3  358.97  5064.6  357.75  5085.4  358.99
  5106.2  358.94  5120.7  359.53  5135.3  361.29  5191.5  362.72  5282.9  368.24
#Mann=6,-1,0
  4799.3   0.035       0  4821.2    0.12       0  5012.7    0.07       0
  5016.7    0.12       0  5022.8    0.16       0  5027.4    0.05       0
Bank Sta=5012.7,5016.7
Exp/Cntr=0.3,0.1

Type RM Length L Ch R = 1,1843,0,0,0
BEGIN DESCRIPTION:
South Twin Creek Trib G1842.96
END DESCRIPTION:
XS GIS Cut Line= 3
      2731071.17      6810186.75      2730917.72      6810207.40
      2730579.87      6810244.32
#Sta/Elev= 30
  4845.5  373.17  4852.4  371.97  4901.2  366.93  4910.5  365.39  4915.6  365.17
  4931.4  363.20  4951.6  359.54  4961.7  356.25  4971.8  354.41  4981.9  356.09
  4988.4  356.11  4993.4  355.09  5012.1  356.21  5020.2  353.80  5020.4  353.30
  5023.9  353.30  5024.2  353.80  5032.2  355.39  5052.4  354.85  5102.5  355.91
  5132.8  357.22  5213.3  358.87  5243.5  360.37  5261.1  361.76  5266.1  361.31
  5283.7  362.62  5293.8  364.11  5303.9  366.16  5334.0  370.98  5340.2  372.54
#Mann=5,-1,0
  4845.5   0.035       0  4852.4    0.12       0  5020.2    0.07       0
  5024.2    0.12       0  5102.5    0.05       0
Bank Sta=5020.2,5024.2
Exp/Cntr=0.3,0.1

Chan Stop Cuts=-1