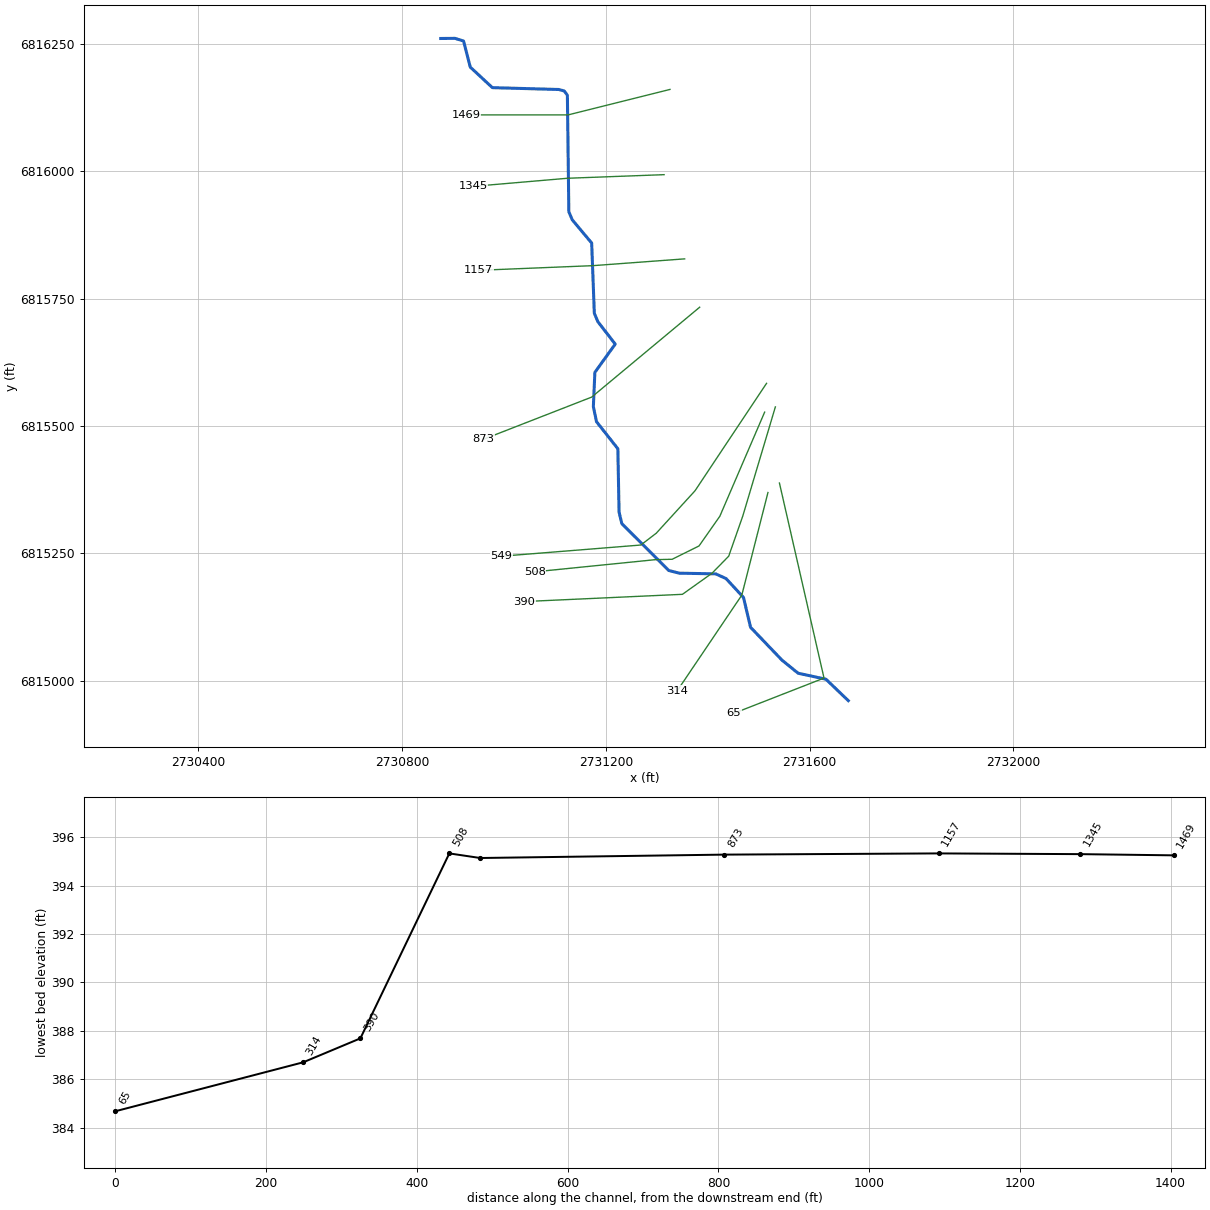
--- South Twin Creek Trib G1.prj (project) ---

Proj Title=South Twin Creek Trib G1 Base Level Engineering
Current Plan=p01
Default Exp/Contr=0.3,0.1
English Units
Geom File=g01
Flow File=f01
Plan File=p01
BEGIN DESCRIPTION:
South Twin Creek Trib G1
END DESCRIPTION:

--- South Twin Creek Trib G1.p01 (plan) ---

Plan Title=Multiple Run
Short Identifier=Multiple
Geom File=g01
Flow File=f01
Subcritical Flow
K Sum by GR= 0
Std Step Tol= 0.01
Critical Tol= 0.01
Num of Std Step Trials= 20
Max Error Tol= 0.3
Flow Tol Ratio= 0.001
Split Flow NTrial= 30
Split Flow Tol= 0.02
Split Flow Ratio= 0.02
Log Output Level= 0
Friction Slope Method= 1
Unsteady Friction Slope Method= 2
Unsteady Bridges Friction Slope Method= 1
Parabolic Critical Depth
Global Vel Dist=  1 , 1 , 1
Global Log Level= 0
CheckData=True
Encroach Param= -1, 0, 0, 0
BEGIN DESCRIPTION:
Multiple Run
END DESCRIPTION:

--- South Twin Creek Trib G1.f01 (steady flow) ---

Flow Title=Multiple
Number of Profiles=7
Profile Names=10-year,25-year,50-year,1pct_min,100-year,1pct_plu,500-year
River Rch & RM= South Twin Creek,Reach-1,1469
     121     145     162      91     181     361     224
Boundary for River Rch & Prof#=South Twin Creek,Reach-1,1
Up Type=0
Dn Type=3
Dn Slope=0.005
Boundary for River Rch & Prof#=South Twin Creek,Reach-1,2
Up Type=0
Dn Type=3
Dn Slope=0.005
Boundary for River Rch & Prof#=South Twin Creek,Reach-1,3
Up Type=0
Dn Type=3
Dn Slope=0.005
Boundary for River Rch & Prof#=South Twin Creek,Reach-1,4
Up Type=0
Dn Type=3
Dn Slope=0.005
Boundary for River Rch & Prof#=South Twin Creek,Reach-1,5
Up Type=0
Dn Type=3
Dn Slope=0.005
Boundary for River Rch & Prof#=South Twin Creek,Reach-1,6
Up Type=0
Dn Type=3
Dn Slope=0.005
Boundary for River Rch & Prof#=South Twin Creek,Reach-1,7
Up Type=0
Dn Type=3
Dn Slope=0.005

--- South Twin Creek Trib G1.g01 (geometry) ---

Geom Title=Existing Conditions

River Reach=South Twin Creek,Reach-1
Reach XY= 30
      2730876.00      6816261.00      2730903.71      6816261.29
      2730920.65      6816256.04      2730933.91      6816204.73
      2730977.27      6816164.46      2731107.68      6816160.86
      2731118.38      6816157.92      2731124.52      6816149.51
      2731127.38      6815920.66      2731134.14      6815904.94
      2731172.21      6815859.43      2731177.40      6815721.44
      2731184.46      6815704.82      2731218.44      6815661.00
      2731178.49      6815605.51      2731175.51      6815538.25
      2731181.69      6815508.69      2731223.61      6815455.47
      2731225.98      6815330.99      2731231.46      6815308.54
      2731323.56      6815216.52      2731344.29      6815211.25
      2731415.67      6815209.90      2731436.10      6815200.61
      2731470.26      6815163.57      2731484.16      6815104.95
      2731545.76      6815040.58      2731577.57      6815014.80
      2731632.14      6815003.06      2731676.00      6814961.00

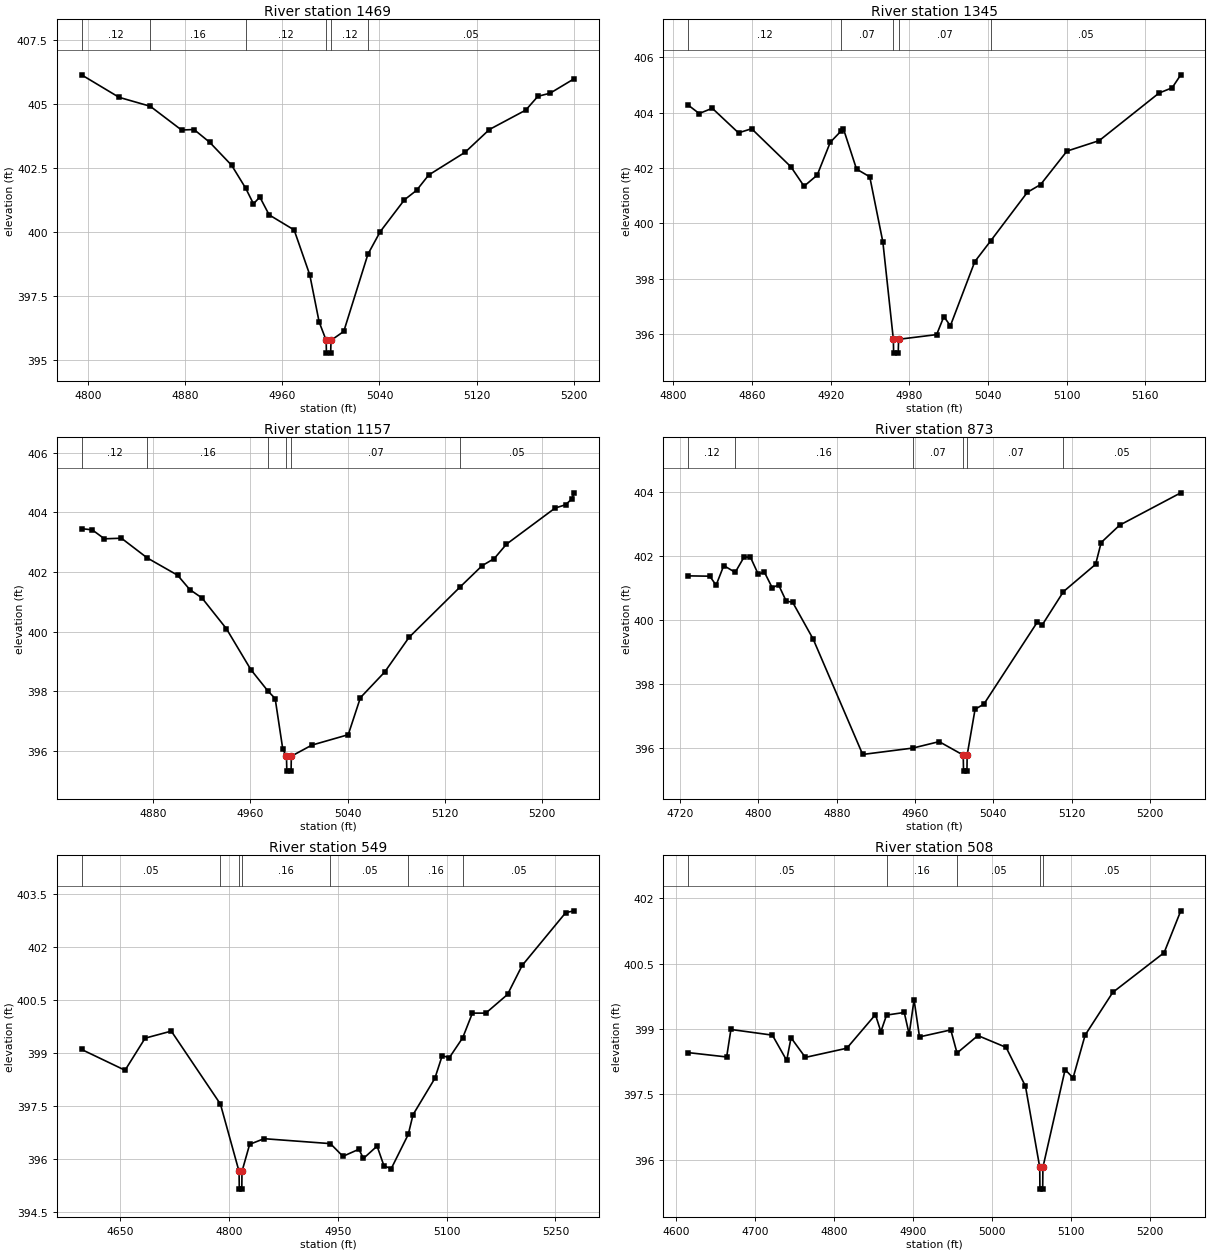
Type RM Length L Ch R = 1,1469,124,124,124
BEGIN DESCRIPTION:
South Twin Creek Trib G11469.394
END DESCRIPTION:
XS GIS Cut Line= 3
      2731325.98      6816160.99      2731126.00      6816111.00
      2730926.03      6816111.00
#Sta/Elev= 30
  4794.5  406.14  4825.4  405.26  4851.1  404.91  4876.9  403.98  4887.2  404.00
  4900.1  403.50  4918.2  402.60  4929.8  401.70  4936.2  401.09  4941.4  401.36
  4949.1  400.66  4969.7  400.07  4982.6  398.31  4990.3  396.47  4996.1  395.75
  4996.3  395.25  4999.8  395.25  5000.1  395.75  5010.6  396.10  5030.5  399.12
  5040.6  400.00  5060.6  401.25  5070.6  401.62  5080.6  402.22  5110.6  403.11
  5130.6  404.00  5160.6  404.76  5170.6  405.30  5180.6  405.42  5200.6  405.99
#Mann=6,-1,0
  4794.5    0.12       0  4851.1    0.16       0  4929.8    0.12       0
  4996.1    0.07       0  5000.1    0.12       0  5030.5    0.05       0
Bank Sta=4996.1,5000.1
Exp/Cntr=0.3,0.1

Type RM Length L Ch R = 1,1345,188,188,188
BEGIN DESCRIPTION:
South Twin Creek Trib G11344.86
END DESCRIPTION:
XS GIS Cut Line= 3
      2731314.46      6815993.64      2731124.97      6815986.59
      2730939.47      6815970.64
#Sta/Elev= 30
  4811.2  404.28  4819.7  403.97  4829.7  404.16  4849.7  403.27  4859.7  403.42
  4889.7  402.04  4899.7  401.34  4909.7  401.74  4919.7  402.93  4927.8  403.33
  4929.7  403.42  4939.7  401.96  4949.8  401.68  4959.8  399.32  4967.8  395.80
  4968.0  395.30  4971.5  395.30  4971.8  395.80  5000.8  395.97  5006.3  396.62
  5011.3  396.29  5029.9  398.61  5042.0  399.36  5070.0  401.12  5080.1  401.40
  5100.2  402.61  5124.8  402.99  5170.4  404.71  5180.4  404.90  5187.0  405.37
#Mann=5,-1,0
  4811.2    0.12       0  4927.8    0.07       0  4967.8    0.07       0
  4971.8    0.07       0  5042.0    0.05       0
Bank Sta=4967.8,4971.8
Exp/Cntr=0.3,0.1

Type RM Length L Ch R = 1,1157,284,284,284
BEGIN DESCRIPTION:
South Twin Creek Trib G11157.21
END DESCRIPTION:
XS GIS Cut Line= 3
      2731354.78      6815828.34      2731175.31      6815815.03
      2730950.26      6815805.85
#Sta/Elev= 30
  4821.1  403.45  4829.9  403.41  4839.9  403.11  4853.9  403.13  4875.1  402.47
  4900.1  401.89  4910.1  401.41  4920.1  401.13  4940.2  400.10  4960.3  398.73
  4974.2  398.02  4980.3  397.76  4986.6  396.06  4989.6  395.83  4989.9  395.33
  4993.4  395.33  4993.6  395.83  5010.4  396.20  5040.4  396.55  5050.4  397.79
  5070.4  398.65  5090.4  399.81  5132.2  401.49  5150.5  402.21  5160.5  402.45
  5170.5  402.93  5210.5  404.14  5219.1  404.25  5224.1  404.44  5226.3  404.65
#Mann=6,-1,0
  4821.1    0.12       0  4875.1    0.16       0  4974.2    0.07       0
  4989.6    0.07       0  4993.6    0.07       0  5132.2    0.05       0
Bank Sta=4989.6,4993.6
Exp/Cntr=0.3,0.1

Type RM Length L Ch R = 1,873,324,324,324
BEGIN DESCRIPTION:
South Twin Creek Trib G1873.43
END DESCRIPTION:
XS GIS Cut Line= 3
      2731384.20      6815733.38      2731172.19      6815556.92
      2730960.27      6815474.29
#Sta/Elev= 30
  4728.1  401.37  4750.3  401.36  4756.8  401.08  4764.6  401.69  4776.3  401.48
  4785.4  401.96  4791.9  401.95  4799.7  401.43  4806.2  401.48  4814.1  401.00
  4820.6  401.09  4828.4  400.58  4834.9  400.55  4855.9  399.40  4906.5  395.80
  4957.9  396.00  4984.6  396.20  5009.2  395.78  5009.5  395.28  5013.0  395.28
  5013.2  395.78  5021.3  397.21  5030.3  397.37  5084.7  399.92  5090.1  399.85
  5111.6  400.88  5144.4  401.73  5150.1  402.41  5168.9  402.95  5231.4  403.96
#Mann=6,-1,0
  4728.1    0.12       0  4776.3    0.16       0  4957.9    0.07       0
  5009.2    0.07       0  5013.2    0.07       0  5111.6    0.05       0
Bank Sta=5009.2,5013.2
Exp/Cntr=0.3,0.1

Type RM Length L Ch R = 1,549,41,41,41
BEGIN DESCRIPTION:
South Twin Creek Trib G1549.12
END DESCRIPTION:
XS GIS Cut Line= 5
      2731515.56      6815584.01      2731375.00      6815372.92
      2731299.03      6815289.74      2731268.71      6815266.52
      2730994.24      6815244.47
#Sta/Elev= 30
  4596.3  399.10  4656.3  398.51  4684.0  399.42  4720.1  399.62  4787.9  397.55
  4813.6  395.64  4813.9  395.14  4817.4  395.14  4817.6  395.64  4828.2  396.41
  4848.1  396.57  4939.6  396.43  4956.9  396.07  4978.9  396.27  4985.2  396.01
  5004.0  396.36  5013.5  395.80  5023.5  395.72  5047.0  396.69  5053.6  397.25
  5083.7  398.28  5093.8  398.92  5103.8  398.87  5122.1  399.43  5135.5  400.13
  5154.0  400.13  5184.0  400.66  5204.1  401.48  5264.3  402.98  5276.1  403.03
#Mann=7,-1,0
  4596.3    0.05       0  4787.9    0.16       0  4813.6    0.05       0
  4817.6    0.16       0  4939.6    0.05       0  5047.0    0.16       0
  5122.1    0.05       0
Bank Sta=4813.6,4817.6
Exp/Cntr=0.3,0.1

Type RM Length L Ch R = 1,508,118,118,118
BEGIN DESCRIPTION:
Mapping XS 66a22c41
END DESCRIPTION:
XS GIS Cut Line= 6
      2731511.80      6815527.44      2731423.82      6815323.01
      2731382.93      6815264.69      2731330.25      6815238.55
      2731297.18      6815237.77      2731060.36      6815213.85
#Sta/Elev= 30
  4615.6  398.46  4664.5  398.36  4669.9  398.99  4722.4  398.86  4740.5  398.28
  4746.0  398.80  4764.1  398.35  4816.6  398.56  4852.8  399.33  4859.7  398.94
  4866.9  399.32  4889.3  399.38  4895.5  398.88  4901.7  399.67  4908.6  398.82
  4948.2  398.98  4956.1  398.45  4982.5  398.85  5018.2  398.58  5042.7  397.69
  5060.8  395.83  5061.0  395.33  5064.5  395.33  5064.8  395.83  5092.9  398.07
  5103.0  397.88  5118.2  398.86  5153.2  399.84  5218.2  400.75  5239.3  401.71
#Mann=5,-1,0
  4615.6    0.05       0  4866.9    0.16       0  4956.1    0.05       0
  5060.8    0.05       0  5064.8    0.05       0
Bank Sta=5060.8,5064.8
Exp/Cntr=0.3,0.1

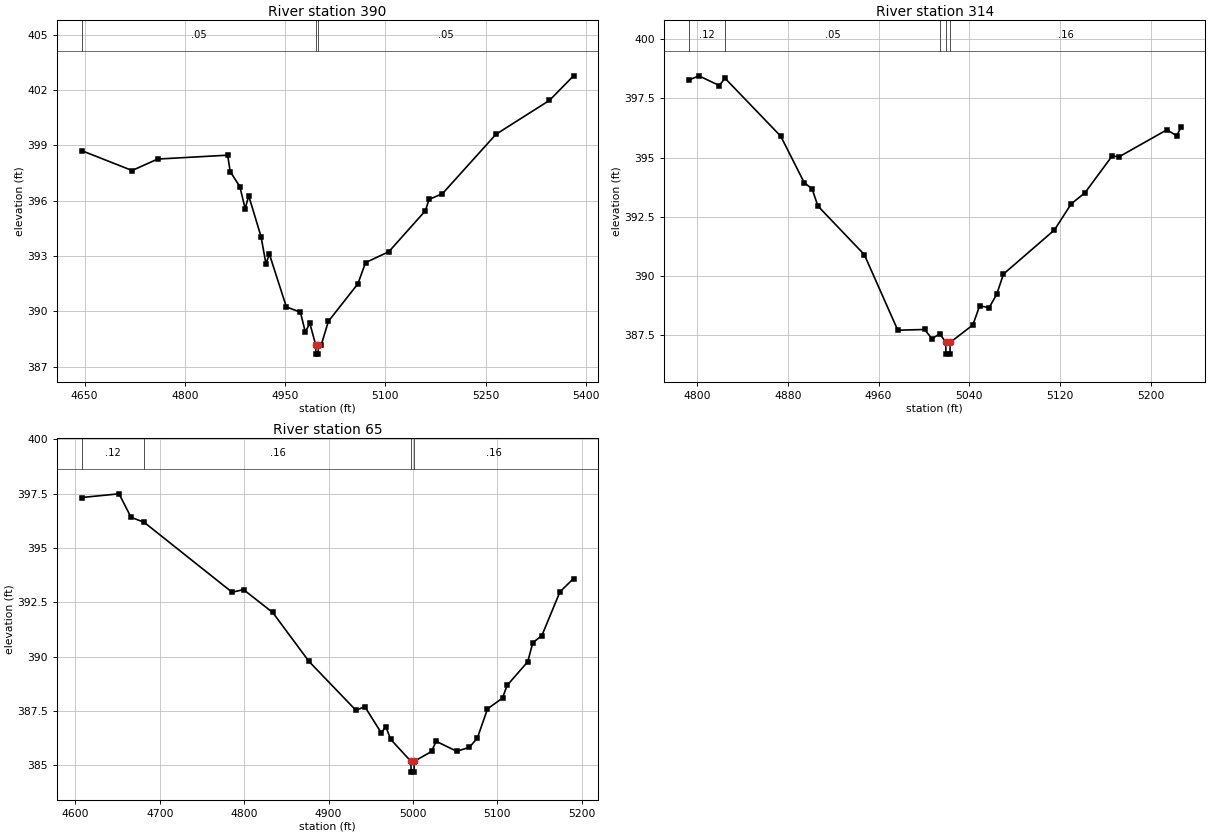
Type RM Length L Ch R = 1,390,76,76,76
BEGIN DESCRIPTION:
South Twin Creek Trib G1389.59
END DESCRIPTION:
XS GIS Cut Line= 6
      2731532.85      6815537.70      2731468.79      6815323.18
      2731441.24      6815244.60      2731408.21      6815210.92
      2731350.37      6815169.73      2731040.03      6815155.53
#Sta/Elev= 30
  4645.4  398.72  4721.0  397.64  4759.3  398.26  4864.0  398.47  4867.8  397.58
  4882.2  396.77  4890.2  395.57  4895.5  396.27  4914.0  394.05  4921.2  392.60
  4926.5  393.10  4951.8  390.25  4972.9  389.96  4980.0  388.90  4987.0  389.35
  4995.7  388.19  4996.0  387.69  4999.5  387.69  4999.7  388.19  5004.0  388.19
  5014.7  389.47  5058.8  391.50  5070.3  392.65  5105.1  393.24  5159.8  395.46
  5165.2  396.07  5185.2  396.38  5265.3  399.60  5345.4  401.44  5381.4  402.77
#Mann=3,-1,0
  4645.4    0.05       0  4995.7    0.05       0  4999.7    0.05       0
Bank Sta=4995.7,4999.7
Exp/Cntr=0.3,0.1

Type RM Length L Ch R = 1,314,249,249,249
BEGIN DESCRIPTION:
Mapping XS a7cd2329
END DESCRIPTION:
XS GIS Cut Line= 3
      2731518.29      6815369.60      2731466.98      6815168.17
      2731340.50      6814980.83
#Sta/Elev= 30
  4792.6  398.27  4801.5  398.45  4819.5  398.04  4824.5  398.35  4873.7  395.90
  4894.4  393.94  4901.3  393.68  4906.5  392.95  4947.4  390.90  4976.9  387.71
  5000.5  387.74  5007.1  387.35  5014.0  387.56  5019.2  387.20  5019.4  386.70
  5022.9  386.70  5023.2  387.20  5043.1  387.93  5049.1  388.74  5057.4  388.66
  5064.1  389.22  5070.1  390.08  5115.0  391.94  5129.8  393.04  5142.1  393.52
  5166.0  395.07  5172.0  395.03  5214.2  396.17  5222.9  395.92  5226.5  396.27
#Mann=5,-1,0
  4792.6    0.12       0  4824.5    0.05       0  5014.0    0.16       0
  5019.2    0.05       0  5023.2    0.16       0
Bank Sta=5019.2,5023.2
Exp/Cntr=0.3,0.1

Type RM Length L Ch R = 1,65,0,0,0
BEGIN DESCRIPTION:
South Twin Creek Trib G165.275
END DESCRIPTION:
XS GIS Cut Line= 3
      2731540.83      6815388.22      2731628.35      6815005.29
      2731451.01      6814936.00
#Sta/Elev= 30
  4607.2  397.32  4651.7  397.49  4665.9  396.41  4681.4  396.18  4785.7  392.96
  4799.2  393.08  4833.8  392.03  4876.7  389.78  4932.6  387.52  4942.9  387.70
  4962.6  386.48  4967.8  386.78  4973.6  386.19  4997.6  385.18  4997.9  384.68
  5001.4  384.68  5001.6  385.18  5022.1  385.63  5027.5  386.10  5051.9  385.64
  5066.9  385.82  5076.4  386.25  5088.4  387.59  5106.2  388.09  5111.6  388.67
  5136.1  389.76  5142.1  390.64  5152.8  390.96  5174.3  392.98  5190.4  393.59
#Mann=4,-1,0
  4607.2    0.12       0  4681.4    0.16       0  4997.6    0.07       0
  5001.6    0.16       0
Bank Sta=4997.6,5001.6
Exp/Cntr=0.3,0.1

Chan Stop Cuts=-1