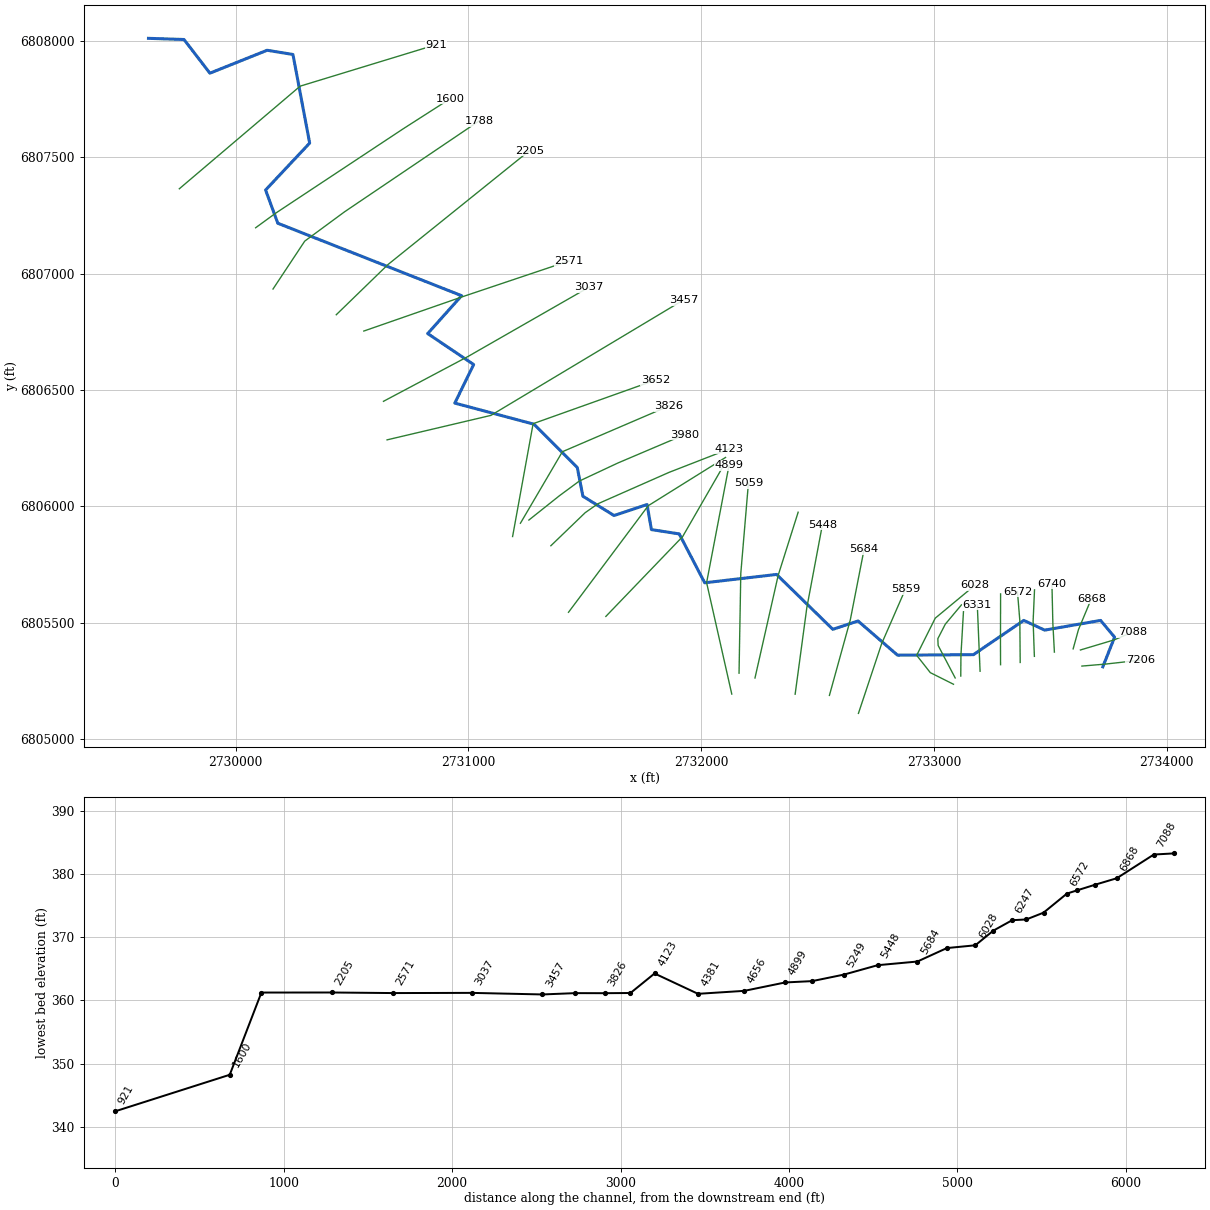
--- South Twin Creek Trib H.prj (project) ---

Proj Title=South Twin Creek Trib H Base Level Engineering
Current Plan=p01
Default Exp/Contr=0.3,0.1
English Units
Geom File=g01
Flow File=f01
Plan File=p01
BEGIN DESCRIPTION:
South Twin Creek Trib H
END DESCRIPTION:

--- South Twin Creek Trib H.p01 (plan) ---

Plan Title=Multiple Run
Short Identifier=Multiple
Geom File=g01
Flow File=f01
Subcritical Flow
K Sum by GR= 0
Std Step Tol= 0.01
Critical Tol= 0.01
Num of Std Step Trials= 20
Max Error Tol= 0.3
Flow Tol Ratio= 0.001
Split Flow NTrial= 30
Split Flow Tol= 0.02
Split Flow Ratio= 0.02
Log Output Level= 0
Friction Slope Method= 1
Unsteady Friction Slope Method= 2
Unsteady Bridges Friction Slope Method= 1
Parabolic Critical Depth
Global Vel Dist=  1 , 1 , 1
Global Log Level= 0
CheckData=True
Encroach Param= -1, 0, 0, 0
BEGIN DESCRIPTION:
Multiple Run
END DESCRIPTION:

--- South Twin Creek Trib H.f01 (steady flow) ---

Flow Title=Multiple
Number of Profiles=7
Profile Names=10-year,25-year,50-year,1pct_min,100-year,1pct_plu,500-year
River Rch & RM= South Twin Creek,Reach-1,7206
     176     217     248     141     282     563     363
River Rch & RM= South Twin Creek,Reach-1,5859
     370     483     572     337     672    1341     927
River Rch & RM= South Twin Creek,Reach-1,4123
     669     907    1102     664    1325    2644    1916
River Rch & RM= South Twin Creek,Reach-1,3457
     946    1304    1602     975    1945    3882    2869
Boundary for River Rch & Prof#=South Twin Creek,Reach-1,1
Up Type=0
Dn Type=3
Dn Slope=0.005
Boundary for River Rch & Prof#=South Twin Creek,Reach-1,2
Up Type=0
Dn Type=3
Dn Slope=0.005
Boundary for River Rch & Prof#=South Twin Creek,Reach-1,3
Up Type=0
Dn Type=3
Dn Slope=0.005
Boundary for River Rch & Prof#=South Twin Creek,Reach-1,4
Up Type=0
Dn Type=3
Dn Slope=0.005
Boundary for River Rch & Prof#=South Twin Creek,Reach-1,5
Up Type=0
Dn Type=3
Dn Slope=0.005
Boundary for River Rch & Prof#=South Twin Creek,Reach-1,6
Up Type=0
Dn Type=3
Dn Slope=0.005
Boundary for River Rch & Prof#=South Twin Creek,Reach-1,7
Up Type=0
Dn Type=3
Dn Slope=0.005

--- South Twin Creek Trib H.g01 (geometry) ---

Geom Title=Existing Conditions

River Reach=South Twin Creek,Reach-1
Reach XY= 30
      2733726.00      6805311.00      2733776.44      6805438.42
      2733716.38      6805510.28      2733476.00      6805468.62
      2733386.50      6805510.40      2733170.03      6805363.17
      2732844.12      6805360.93      2732674.35      6805507.84
      2732565.95      6805472.13      2732324.36      6805707.85
      2732015.57      6805671.94      2731906.08      6805881.93
      2731786.54      6805900.55      2731768.03      6806008.18
      2731626.00      6805961.00      2731492.28      6806043.86
      2731468.14      6806167.17      2731282.20      6806353.21
      2730942.00      6806443.88      2731023.00      6806609.60
      2730825.55      6806742.63      2730971.28      6806905.38
      2730181.59      6807216.61      2730129.12      6807359.36
      2730318.45      6807561.00      2730246.65      6807941.62
      2730135.71      6807959.76      2729889.78      6807861.35
      2729778.54      6808006.00      2729626.00      6808011.00

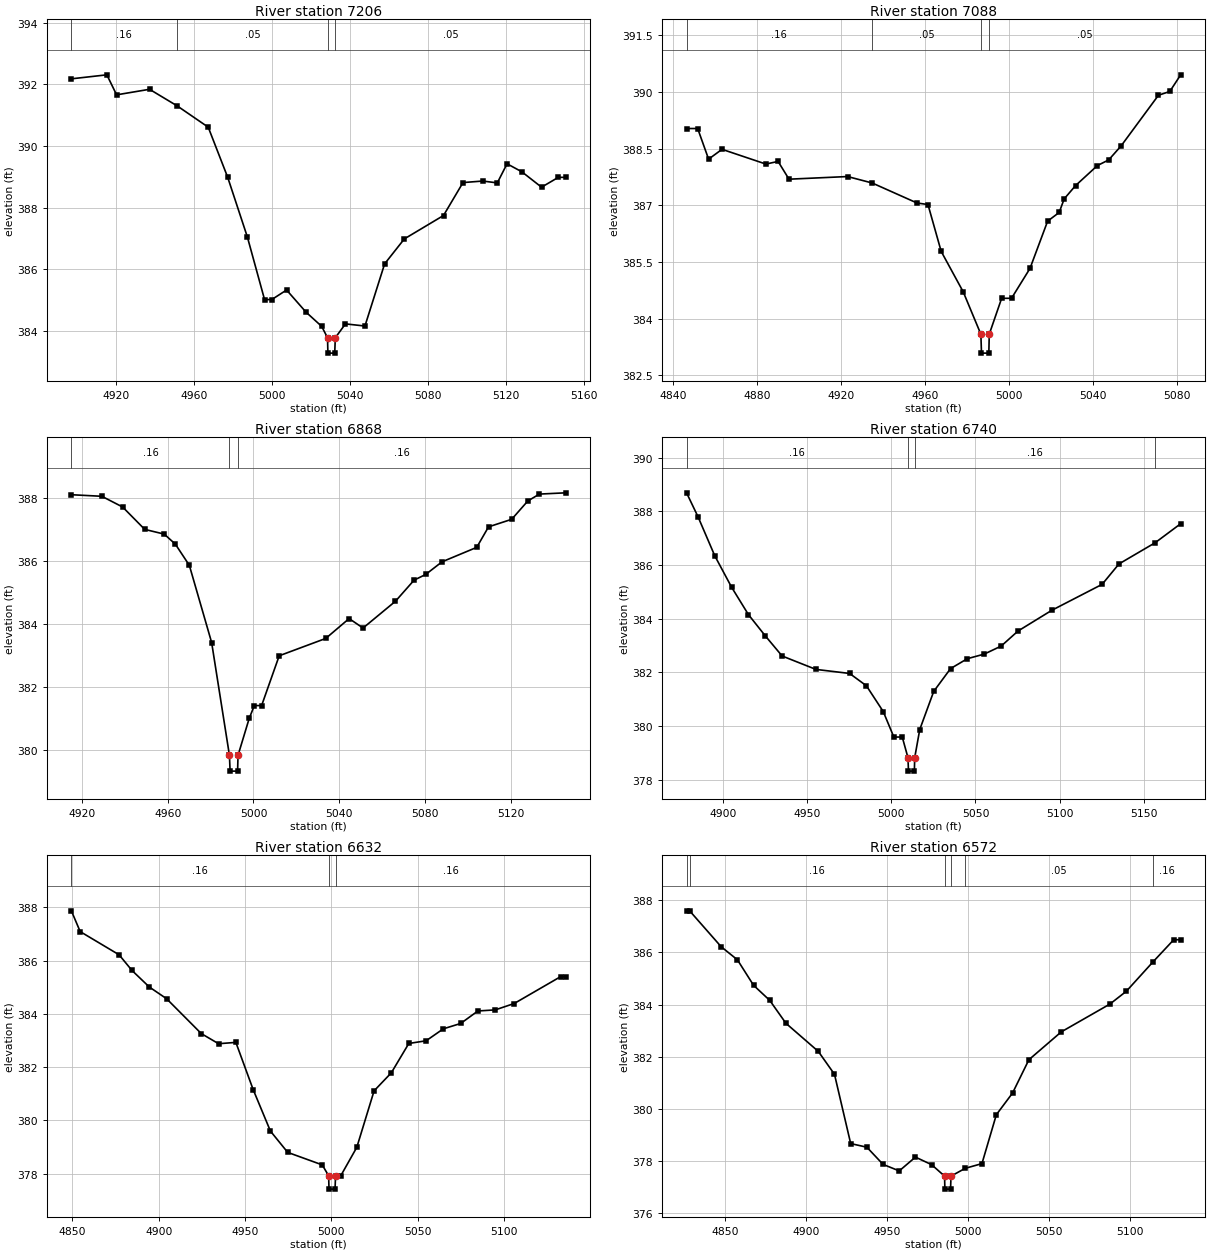
Type RM Length L Ch R = 1,7206,118,118,118
BEGIN DESCRIPTION:
South Twin Creek Trib H7205.985
END DESCRIPTION:
XS GIS Cut Line= 3
      2733636.04      6805314.20      2733738.47      6805322.82
      2733888.23      6805339.64
#Sta/Elev= 30
  4897.2  392.18  4915.4  392.31  4920.4  391.66  4937.3  391.84  4951.5  391.30
  4967.4  390.61  4977.4  388.98  4987.5  387.04  4996.3  385.01  5000.0  385.01
  5007.6  385.32  5017.6  384.60  5025.6  384.14  5028.6  383.77  5028.8  383.27
  5032.3  383.27  5032.6  383.77  5037.8  384.22  5047.8  384.15  5057.9  386.17
  5068.0  386.98  5088.1  387.74  5098.1  388.81  5108.2  388.86  5115.7  388.80
  5120.7  389.42  5128.3  389.16  5138.4  388.66  5147.0  388.98  5150.7  388.98
#Mann=4,-1,0
  4897.2    0.16       0  4951.5    0.05       0  5028.6    0.05       0
  5032.6    0.05       0
Bank Sta=5028.6,5032.6
Exp/Cntr=0.3,0.1

Type RM Length L Ch R = 1,7088,220,220,220
BEGIN DESCRIPTION:
South Twin Creek Trib H7087.68
END DESCRIPTION:
XS GIS Cut Line= 3
      2733629.77      6805383.32      2733774.91      6805426.80
      2733852.12      6805459.58
#Sta/Elev= 30
  4846.5  389.03  4851.8  389.03  4857.0  388.22  4863.4  388.48  4884.3  388.09
  4890.1  388.16  4895.3  387.69  4923.2  387.76  4934.9  387.59  4956.3  387.06
  4961.5  387.02  4967.8  385.78  4978.3  384.71  4986.7  383.59  4987.0  383.09
  4990.5  383.09  4990.7  383.59  4996.6  384.54  5001.3  384.54  5010.1  385.33
  5018.5  386.58  5024.0  386.81  5026.4  387.17  5031.8  387.52  5042.2  388.05
  5047.6  388.20  5053.5  388.57  5071.3  389.91  5076.7  390.01  5081.9  390.45
#Mann=4,-1,0
  4846.5    0.16       0  4934.9    0.05       0  4986.7    0.05       0
  4990.7    0.05       0
Bank Sta=4986.7,4990.7
Exp/Cntr=0.3,0.1

Type RM Length L Ch R = 1,6868,128,128,128
BEGIN DESCRIPTION:
South Twin Creek Trib H6867.71
END DESCRIPTION:
XS GIS Cut Line= 3
      2733598.43      6805388.00      2733621.29      6805470.80
      2733676.97      6805604.15
#Sta/Elev= 29
  4915.1  388.11  4929.3  388.06  4939.0  387.72  4949.3  387.01  4958.4  386.86
  4963.6  386.54  4970.1  385.87  4980.5  383.42  4988.8  379.84  4989.1  379.34
  4992.6  379.34  4992.8  379.84  4998.0  381.01  5000.4  381.42  5003.8  381.42
  5012.0  383.00  5033.7  383.55  5044.6  384.18  5051.1  383.88  5066.2  384.73
  5074.9  385.40  5080.3  385.58  5087.9  385.98  5104.1  386.44  5109.6  387.09
  5120.4  387.33  5127.9  387.91  5133.3  388.13  5145.5  388.17
#Mann=3,-1,0
  4915.1    0.16       0  4988.8    0.07       0  4992.8    0.16       0
Bank Sta=4988.8,4992.8
Exp/Cntr=0.3,0.1

Type RM Length L Ch R = 1,6740,108,108,108
BEGIN DESCRIPTION:
South Twin Creek Trib H6739.83
END DESCRIPTION:
XS GIS Cut Line= 3
      2733517.86      6805374.24      2733511.26      6805498.51
      2733507.27      6805667.72
#Sta/Elev= 29
  4878.3  388.69  4885.1  387.80  4895.1  386.34  4905.1  385.17  4915.1  384.15
  4925.1  383.36  4935.1  382.61  4955.2  382.11  4975.2  381.96  4985.2  381.50
  4995.2  380.54  5001.5  379.59  5006.5  379.59  5009.9  378.82  5010.2  378.32
  5013.7  378.32  5013.9  378.82  5016.9  379.87  5025.2  381.29  5035.2  382.14
  5045.2  382.51  5055.2  382.68  5065.3  382.98  5075.3  383.54  5095.3  384.31
  5125.3  385.28  5135.3  386.04  5156.8  386.83  5172.0  387.54
#Mann=4,-1,0
  4878.3    0.16       0  5009.9    0.07       0  5013.9    0.16       0
  5156.8    0.05       0
Bank Sta=5009.9,5013.9
Exp/Cntr=0.3,0.1

Type RM Length L Ch R = 1,6632,60,60,60
BEGIN DESCRIPTION:
South Twin Creek Trib H6631.58
END DESCRIPTION:
XS GIS Cut Line= 3
      2733431.90      6805355.89      2733426.49      6805507.33
      2733432.51      6805641.65
#Sta/Elev= 30
  4849.5  387.87  4854.6  387.09  4877.1  386.22  4884.6  385.63  4894.6  385.01
  4904.6  384.57  4924.7  383.26  4934.7  382.88  4944.7  382.93  4954.7  381.16
  4964.7  379.60  4974.7  378.80  4994.7  378.33  4998.4  377.92  4998.6  377.42
  5002.1  377.42  5002.4  377.92  5005.4  377.92  5014.7  378.99  5024.7  381.11
  5034.7  381.79  5044.8  382.89  5054.8  382.99  5064.8  383.44  5074.8  383.64
  5084.8  384.11  5094.8  384.15  5105.8  384.39  5132.7  385.40  5135.5  385.40
#Mann=3,-1,0
  4849.5    0.16       0  4998.4    0.07       0  5002.4    0.16       0
Bank Sta=4998.4,5002.4
Exp/Cntr=0.3,0.1

Type RM Length L Ch R = 1,6572,139,139,139
BEGIN DESCRIPTION:
South Twin Creek Trib H6572.22
END DESCRIPTION:
XS GIS Cut Line= 3
      2733370.93      6805329.65      2733369.48      6805508.16
      2733359.15      6805634.52
#Sta/Elev= 30
  4826.2  387.60  4828.1  387.60  4847.6  386.22  4857.6  385.72  4867.6  384.74
  4877.6  384.16  4887.6  383.28  4907.6  382.20  4917.6  381.32  4927.6  378.66
  4937.6  378.52  4947.6  377.86  4957.6  377.61  4967.6  378.14  4977.6  377.85
  4985.6  377.41  4985.8  376.91  4989.3  376.91  4989.6  377.41  4998.4  377.71
  5008.7  377.89  5017.6  379.77  5027.6  380.60  5037.7  381.88  5057.7  382.95
  5087.8  384.02  5097.9  384.51  5114.1  385.62  5127.2  386.49  5131.5  386.49
#Mann=6,-1,0
  4826.2    0.05       0  4828.1    0.16       0  4985.6    0.05       0
  4989.6    0.16       0  4998.4    0.05       0  5114.1    0.16       0
Bank Sta=4985.6,4989.6
Exp/Cntr=0.3,0.1

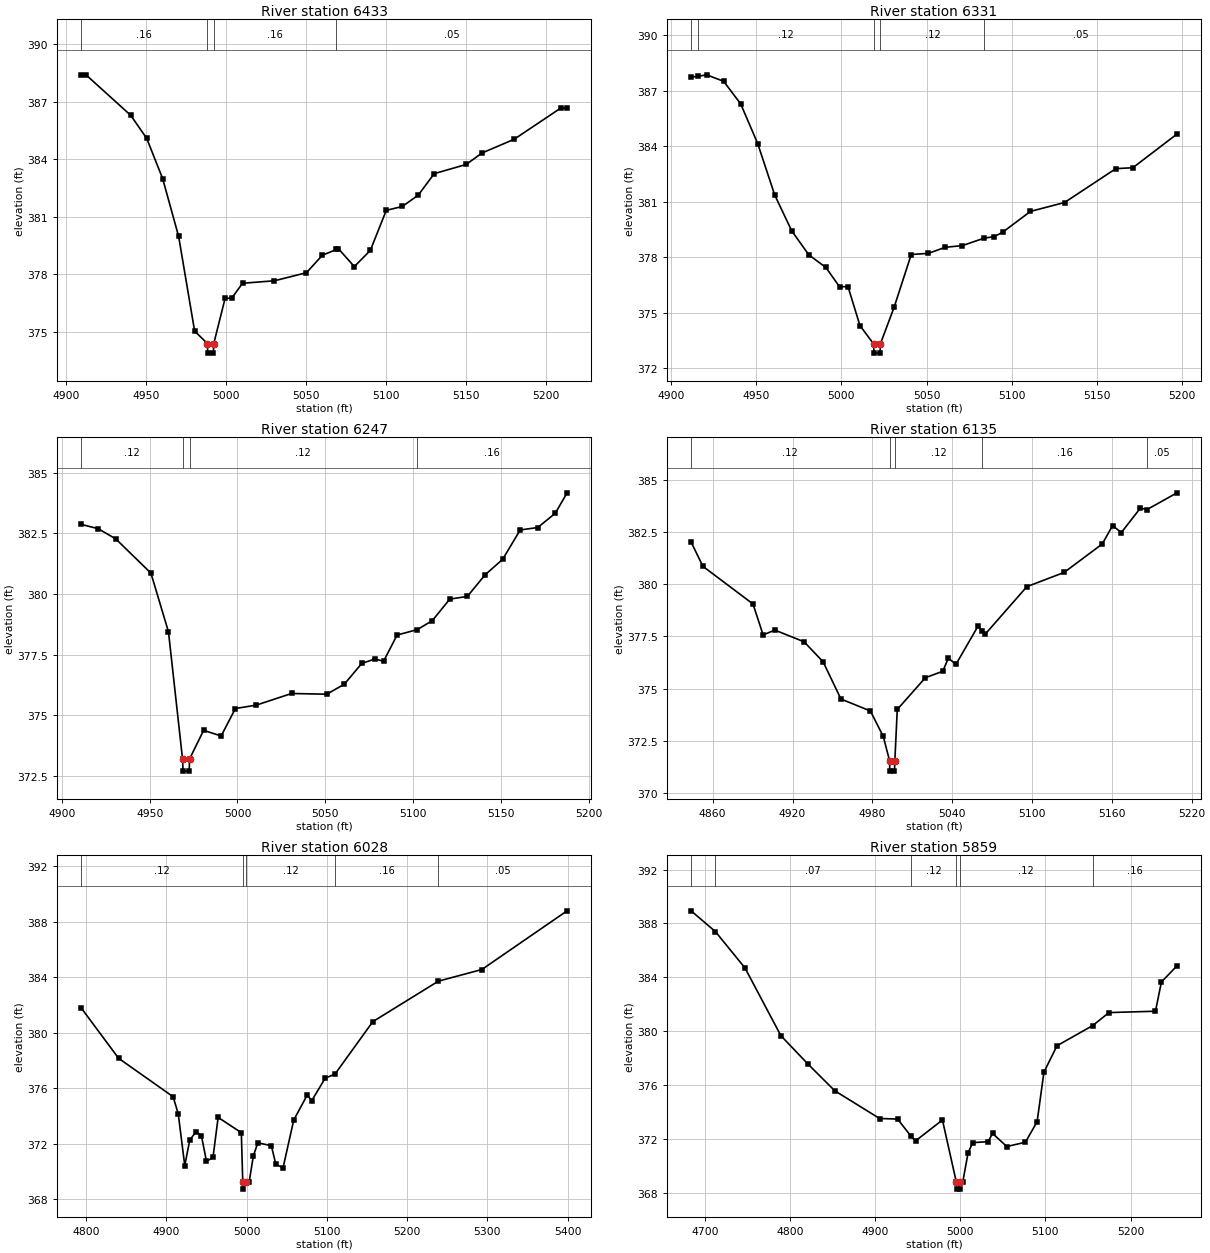
Type RM Length L Ch R = 1,6433,102,102,102
BEGIN DESCRIPTION:
South Twin Creek Trib H6432.56
END DESCRIPTION:
XS GIS Cut Line= 3
      2733286.59      6805320.00      2733286.21      6805414.19
      2733286.78      6805624.20
#Sta/Elev= 30
  4909.3  388.39  4912.3  388.39  4940.3  386.28  4950.3  385.08  4960.3  382.98
  4970.3  379.97  4980.3  375.04  4988.3  374.39  4988.5  373.89  4992.0  373.89
  4992.3  374.39  4999.4  376.75  5003.5  376.75  5010.3  377.53  5030.3  377.66
  5050.3  378.08  5060.3  378.99  5069.1  379.29  5070.3  379.33  5080.3  378.40
  5090.3  379.24  5100.3  381.33  5110.3  381.53  5120.3  382.12  5130.3  383.24
  5150.3  383.72  5160.3  384.32  5180.3  385.03  5209.4  386.65  5213.5  386.65
#Mann=4,-1,0
  4909.3    0.16       0  4988.3    0.07       0  4992.3    0.16       0
  5069.1    0.05       0
Bank Sta=4988.3,4992.3
Exp/Cntr=0.3,0.1

Type RM Length L Ch R = 1,6331,84,84,84
BEGIN DESCRIPTION:
South Twin Creek Trib H6330.87
END DESCRIPTION:
XS GIS Cut Line= 3
      2733198.68      6805291.96      2733194.80      6805381.95
      2733186.69      6805576.90
#Sta/Elev= 30
  4911.8  387.74  4916.0  387.78  4920.9  387.86  4930.9  387.51  4940.9  386.29
  4950.9  384.14  4960.9  381.36  4970.9  379.42  4980.9  378.13  4990.9  377.45
  4998.9  376.41  5003.9  376.41  5010.9  374.31  5018.9  373.32  5019.2  372.82
  5022.7  372.82  5022.9  373.32  5031.0  375.31  5041.0  378.15  5051.0  378.21
  5061.0  378.54  5071.0  378.63  5084.0  379.04  5089.6  379.11  5094.6  379.35
  5111.0  380.48  5131.0  380.96  5161.1  382.79  5171.1  382.84  5197.0  384.66
#Mann=5,-1,0
  4911.8    0.16       0  4916.0    0.12       0  5018.9    0.07       0
  5022.9    0.12       0  5084.0    0.05       0
Bank Sta=5018.9,5022.9
Exp/Cntr=0.3,0.1

Type RM Length L Ch R = 1,6247,112,112,112
BEGIN DESCRIPTION:
South Twin Creek Trib H6246.68
END DESCRIPTION:
XS GIS Cut Line= 3
      2733115.63      6805271.28      2733116.44      6805362.09
      2733127.22      6805547.67
#Sta/Elev= 30
  4911.0  382.87  4920.7  382.69  4930.7  382.27  4950.7  380.86  4960.7  378.44
  4968.7  373.20  4969.0  372.70  4972.5  372.70  4972.7  373.20  4980.7  374.38
  4990.7  374.15  4998.8  375.28  5010.7  375.42  5030.8  375.90  5050.8  375.87
  5060.8  376.28  5070.8  377.14  5078.2  377.32  5083.2  377.23  5090.9  378.31
  5102.3  378.53  5110.9  378.90  5120.9  379.79  5130.9  379.90  5141.0  380.79
  5151.0  381.43  5161.0  382.64  5171.0  382.74  5181.0  383.33  5187.7  384.17
#Mann=4,-1,0
  4911.0    0.12       0  4968.7    0.07       0  4972.7    0.12       0
  5102.3    0.16       0
Bank Sta=4968.7,4972.7
Exp/Cntr=0.3,0.1

Type RM Length L Ch R = 1,6135,107,107,107
BEGIN DESCRIPTION:
South Twin Creek Trib H6134.88
END DESCRIPTION:
XS GIS Cut Line= 5
      2733091.71      6805263.14      2733018.41      6805402.73
      2733017.14      6805431.79      2733049.20      6805494.20
      2733118.63      6805577.16
#Sta/Elev= 30
  4843.8  382.01  4852.7  380.85  4890.3  379.05  4897.9  377.57  4906.7  377.80
  4928.7  377.24  4943.0  376.28  4956.4  374.50  4978.5  373.93  4988.2  372.71
  4992.9  371.55  4993.1  371.05  4996.6  371.05  4996.9  371.55  4998.7  374.00
  5019.8  375.52  5032.9  375.83  5037.1  376.46  5042.8  376.16  5059.3  377.98
  5062.5  377.78  5065.0  377.62  5096.1  379.88  5124.1  380.56  5152.7  381.92
  5160.5  382.80  5167.1  382.47  5181.4  383.64  5186.4  383.57  5208.9  384.37
#Mann=5,-1,0
  4843.8    0.12       0  4992.9    0.07       0  4996.9    0.12       0
  5062.5    0.16       0  5186.4    0.05       0
Bank Sta=4992.9,4996.9
Exp/Cntr=0.3,0.1

Type RM Length L Ch R = 1,6028,169,169,169
BEGIN DESCRIPTION:
South Twin Creek Trib H6028.282
END DESCRIPTION:
XS GIS Cut Line= 5
      2733084.40      6805236.02      2732984.76      6805286.00
      2732926.29      6805360.40      2733005.95      6805519.94
      2733176.02      6805661.02
#Sta/Elev= 30
  4793.9  381.79  4840.5  378.16  4908.4  375.39  4914.8  374.16  4922.9  370.43
  4929.2  372.28  4937.2  372.88  4943.7  372.57  4950.0  370.73  4958.1  371.01
  4964.5  373.90  4993.4  372.80  4995.2  369.23  4995.5  368.73  4999.2  369.23
  5003.1  369.23  5008.4  371.13  5014.0  372.07  5030.8  371.86  5036.4  370.52
  5045.4  370.27  5058.7  373.71  5075.5  375.51  5081.1  375.10  5097.9  376.73
  5110.1  377.02  5157.2  380.80  5238.9  383.72  5293.1  384.56  5399.3  388.79
#Mann=5,-1,0
  4793.9    0.12       0  4995.2    0.07       0  4999.2    0.12       0
  5110.1    0.16       0  5238.9    0.05       0
Bank Sta=4995.2,4999.2
Exp/Cntr=0.3,0.1

Type RM Length L Ch R = 1,5859,175,175,175
BEGIN DESCRIPTION:
South Twin Creek Trib H5859.298
END DESCRIPTION:
XS GIS Cut Line= 3
      2732675.99      6805110.96      2732776.00      6805411.00
      2732877.70      6805644.23
#Sta/Elev= 30
  4683.9  388.94  4712.4  387.40  4747.2  384.70  4789.3  379.68  4821.0  377.58
  4852.6  375.59  4905.3  373.53  4926.4  373.49  4941.9  372.24  4947.5  371.87
  4979.1  373.42  4995.5  368.79  4995.8  368.29  4999.3  368.29  4999.5  368.79
  5002.9  368.79  5009.1  370.95  5014.6  371.74  5032.6  371.81  5038.0  372.42
  5054.7  371.45  5076.5  371.77  5090.3  373.29  5098.3  376.97  5113.7  378.93
  5155.7  380.43  5174.7  381.39  5229.3  381.49  5236.3  383.66  5254.6  384.86
#Mann=6,-1,0
  4683.9    0.05       0  4712.4    0.07       0  4941.9    0.12       0
  4995.5    0.07       0  4999.5    0.12       0  5155.7    0.16       0
Bank Sta=4995.5,4999.5
Exp/Cntr=0.3,0.1

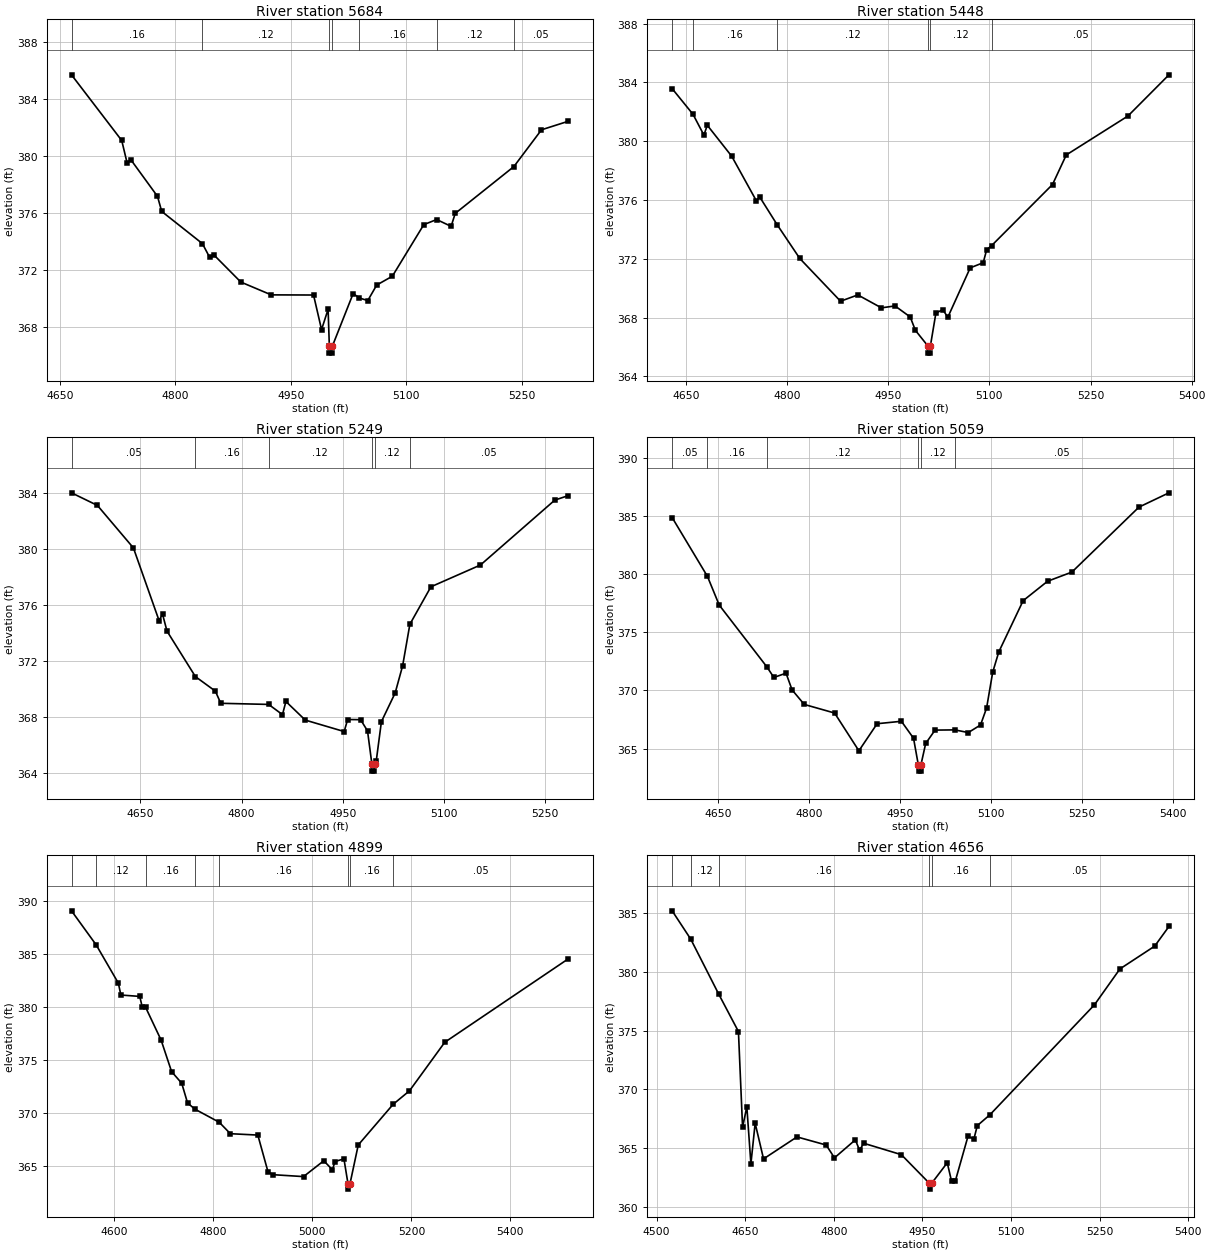
Type RM Length L Ch R = 1,5684,236,236,236
BEGIN DESCRIPTION:
South Twin Creek Trib H5684.2
END DESCRIPTION:
XS GIS Cut Line= 3
      2732551.33      6805188.12      2732641.13      6805512.83
      2732700.19      6805815.12
#Sta/Elev= 30
  4665.3  385.70  4730.5  381.09  4737.4  379.53  4742.6  379.72  4776.9  377.17
  4782.4  376.11  4835.2  373.85  4844.7  372.88  4850.8  373.02  4885.1  371.15
  4924.6  370.25  4979.5  370.24  4989.9  367.81  4998.4  369.24  5000.0  366.66
  5000.2  366.16  5003.7  366.16  5004.0  366.66  5030.9  370.34  5039.1  370.03
  5049.9  369.85  5061.5  370.94  5081.8  371.56  5122.6  375.18  5139.3  375.54
  5158.1  375.06  5163.4  375.97  5239.6  379.26  5275.4  381.84  5310.2  382.44
#Mann=7,-1,0
  4665.3    0.16       0  4835.2    0.12       0  5000.0    0.07       0
  5004.0    0.12       0  5039.1    0.16       0  5139.3    0.12       0
  5239.6    0.05       0
Bank Sta=5000,5004
Exp/Cntr=0.3,0.1

Type RM Length L Ch R = 1,5448,199,199,199
BEGIN DESCRIPTION:
South Twin Creek Trib H5448.24
END DESCRIPTION:
XS GIS Cut Line= 3
      2732404.16      6805193.41      2732454.23      6805564.72
      2732521.10      6805920.72
#Sta/Elev= 30
  4629.4  383.57  4660.4  381.82  4676.5  380.41  4681.5  381.08  4717.8  378.97
  4754.3  375.94  4759.3  376.20  4785.2  374.31  4818.7  372.02  4879.2  369.11
  4904.8  369.54  4939.8  368.66  4960.0  368.79  4982.5  368.04  4990.2  367.13
  5008.5  366.08  5008.7  365.58  5012.2  365.58  5012.5  366.08  5020.6  368.30
  5030.8  368.54  5038.3  368.02  5071.5  371.38  5090.8  371.73  5095.9  372.61
  5103.4  372.90  5193.6  377.05  5214.0  379.06  5305.5  381.71  5366.3  384.51
#Mann=6,-1,0
  4629.4    0.05       0  4660.4    0.16       0  4785.2    0.12       0
  5008.5    0.07       0  5012.5    0.12       0  5103.4    0.05       0
Bank Sta=5008.5,5012.5
Exp/Cntr=0.3,0.1

Type RM Length L Ch R = 1,5249,190,190,190
BEGIN DESCRIPTION:
South Twin Creek Trib H5249.22
END DESCRIPTION:
XS GIS Cut Line= 3
      2732231.55      6805262.93      2732331.45      6805704.70
      2732417.01      6805975.17
#Sta/Elev= 30
  4547.8  384.00  4586.2  383.10  4639.6  380.06  4677.6  374.87  4682.8  375.32
  4689.4  374.11  4731.5  370.86  4761.1  369.82  4769.1  368.95  4840.1  368.87
  4860.6  368.14  4865.7  369.08  4894.4  367.75  4952.1  366.93  4957.2  367.79
  4976.4  367.78  4986.7  366.98  4993.2  364.60  4993.5  364.10  4997.0  364.10
  4997.2  364.60  4999.7  364.85  5007.3  367.64  5027.7  369.69  5038.8  371.64
  5049.5  374.60  5080.7  377.28  5154.2  378.84  5264.4  383.48  5284.4  383.80
#Mann=6,-1,0
  4547.8    0.05       0  4731.5    0.16       0  4840.1    0.12       0
  4993.2    0.07       0  4997.2    0.12       0  5049.5    0.05       0
Bank Sta=4993.2,4997.2
Exp/Cntr=0.3,0.1

Type RM Length L Ch R = 1,5059,160,160,160
BEGIN DESCRIPTION:
South Twin Creek Trib H5059.02
END DESCRIPTION:
XS GIS Cut Line= 3
      2732163.08      6805283.56      2732170.64      6805712.34
      2732203.42      6806100.21
#Sta/Elev= 30
  4575.0  384.88  4633.1  379.82  4652.5  377.35  4731.0  372.03  4742.5  371.12
  4762.5  371.49  4772.5  370.05  4792.5  368.80  4842.5  368.06  4882.5  364.81
  4912.5  367.14  4952.5  367.35  4972.5  365.89  4980.5  363.56  4980.8  363.06
  4984.3  363.06  4984.5  363.56  4992.5  365.44  5007.9  366.59  5040.3  366.61
  5062.7  366.38  5082.8  367.03  5092.8  368.49  5102.9  371.58  5112.9  373.32
  5153.0  377.73  5193.2  379.40  5233.3  380.19  5343.7  385.78  5393.1  387.01
#Mann=6,-1,0
  4575.0    0.05       0  4633.1    0.16       0  4731.0    0.12       0
  4980.5    0.07       0  4984.5    0.12       0  5040.3    0.05       0
Bank Sta=4980.5,4984.5
Exp/Cntr=0.3,0.1

Type RM Length L Ch R = 1,4899,243,243,243
BEGIN DESCRIPTION:
South Twin Creek Trib H4898.697
END DESCRIPTION:
XS GIS Cut Line= 3
      2732131.86      6805193.90      2732023.77      6805672.52
      2732119.99      6806176.03
#Sta/Elev= 30
  4513.6  389.06  4563.6  385.84  4608.2  382.25  4613.3  381.13  4651.4  381.00
  4656.5  380.00  4663.4  379.96  4694.6  376.88  4715.7  373.92  4736.2  372.82
  4748.0  370.96  4763.3  370.37  4811.9  369.15  4834.4  368.07  4889.9  367.94
  4910.5  364.47  4920.7  364.21  4982.2  364.03  5023.1  365.52  5040.6  364.67
  5045.7  365.45  5063.8  365.70  5072.0  363.35  5072.2  362.85  5076.0  363.35
  5092.7  367.01  5163.2  370.84  5196.2  372.11  5267.4  376.68  5516.9  384.54
#Mann=8,-1,0
  4513.6   0.035       0  4563.6    0.12       0  4663.4    0.16       0
  4763.3    0.12       0  4811.9    0.16       0  5072.0    0.07       0
  5076.0    0.16       0  5163.2    0.05       0
Bank Sta=5072,5076
Exp/Cntr=0.3,0.1

Type RM Length L Ch R = 1,4656,275,275,275
BEGIN DESCRIPTION:
South Twin Creek Trib H4656.093
END DESCRIPTION:
XS GIS Cut Line= 3
      2731590.88      6805527.50      2731921.07      6805870.82
      2732103.00      6806186.86
#Sta/Elev= 30
  4526.5  385.18  4558.0  382.77  4605.2  378.11  4638.7  374.92  4645.7  366.77
  4652.9  368.53  4659.8  363.67  4667.0  367.12  4681.2  364.09  4737.8  365.96
  4787.2  365.27  4801.3  364.18  4836.6  365.71  4843.8  364.82  4850.7  365.42
  4914.5  364.45  4961.9  362.02  4962.2  361.52  4965.9  362.02  4992.2  363.76
  4999.4  362.21  5005.8  362.20  5027.3  366.01  5037.3  365.78  5043.1  366.92
  5064.4  367.84  5241.4  377.19  5284.5  380.24  5343.4  382.18  5367.5  383.85
#Mann=6,-1,0
  4526.5    0.16       0  4558.0    0.12       0  4605.2    0.16       0
  4961.9    0.07       0  4965.9    0.16       0  5064.4    0.05       0
Bank Sta=4961.9,4965.9
Exp/Cntr=0.3,0.1

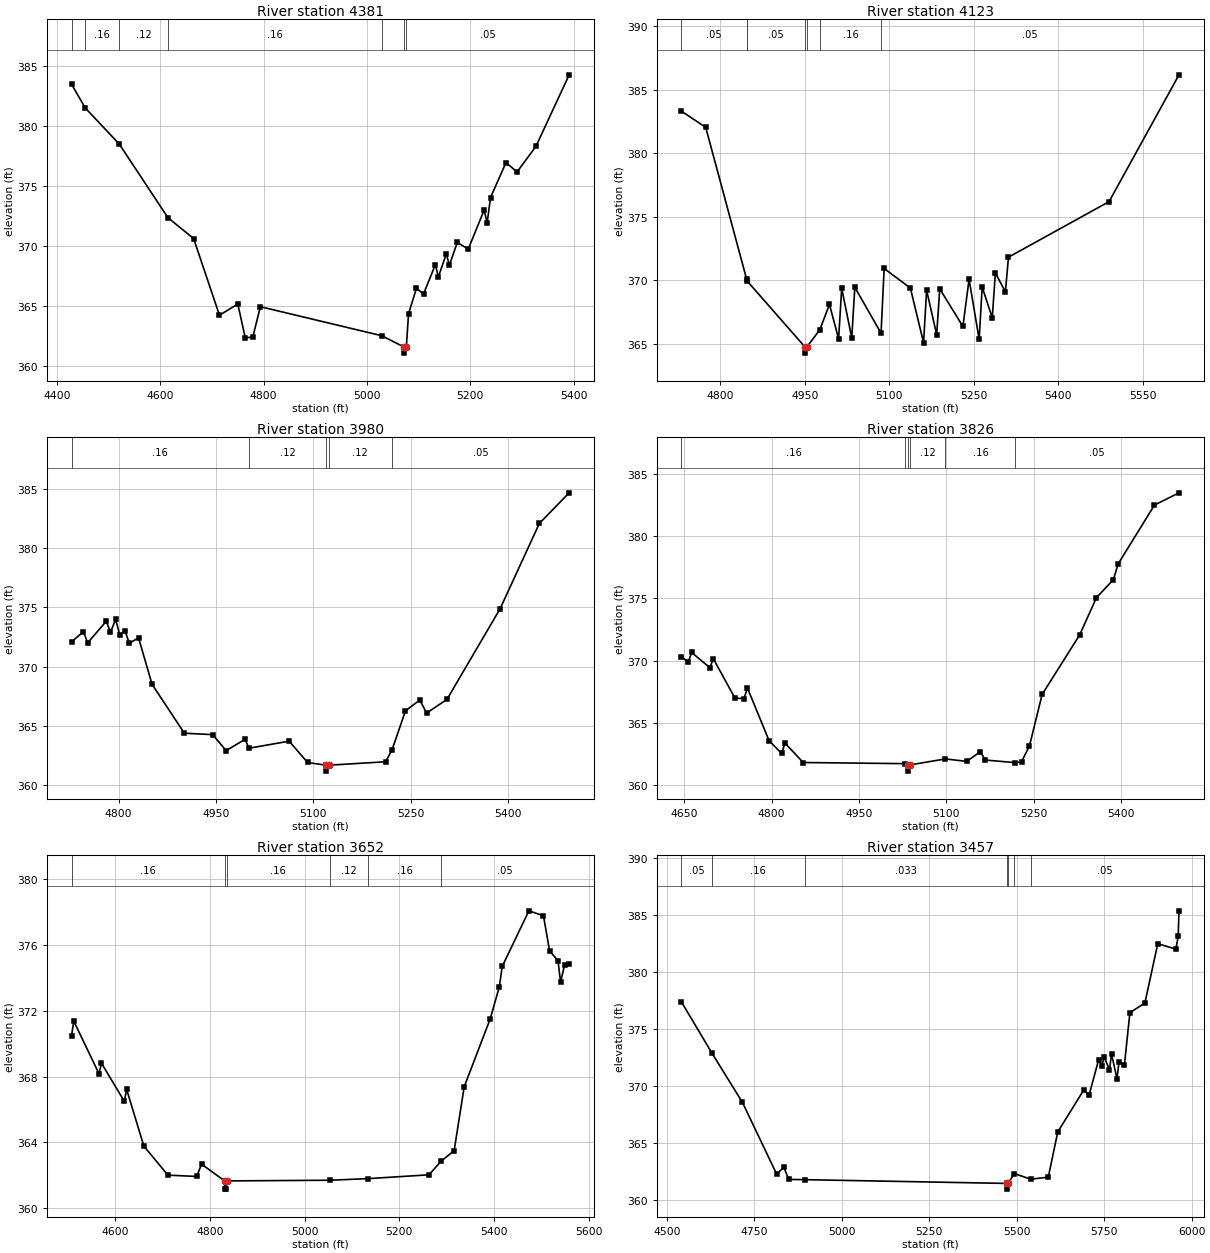
Type RM Length L Ch R = 1,4381,258,258,258
BEGIN DESCRIPTION:
South Twin Creek Trib H4380.553
END DESCRIPTION:
XS GIS Cut Line= 3
      2731430.51      6805545.35      2731772.99      6806003.12
      2732105.12      6806210.39
#Sta/Elev= 30
  4428.3  383.47  4454.8  381.49  4520.6  378.48  4614.9  372.34  4664.6  370.60
  4714.6  364.21  4750.1  365.14  4764.6  362.32  4779.2  362.40  4793.8  364.92
  5028.8  362.50  5072.3  361.55  5072.5  361.05  5076.3  361.55  5080.6  364.33
  5095.9  366.45  5109.6  365.98  5132.5  368.42  5138.4  367.41  5153.7  369.33
  5159.6  368.37  5175.0  370.28  5196.2  369.72  5226.9  372.97  5232.8  371.92
  5239.3  374.02  5269.3  376.94  5290.6  376.15  5327.1  378.28  5391.5  384.25
#Mann=7,-1,0
  4428.3    0.12       0  4454.8    0.16       0  4520.6    0.12       0
  4614.9    0.16       0  5028.8    0.05       0  5072.3    0.07       0
  5076.3    0.05       0
Bank Sta=5072.3,5076.3
Exp/Cntr=0.3,0.1

Type RM Length L Ch R = 1,4123,143,143,143
BEGIN DESCRIPTION:
South Twin Creek Trib H4122.71
END DESCRIPTION:
XS GIS Cut Line= 5
      2731354.81      6805831.22      2731502.22      6805973.24
      2731556.48      6806011.32      2731862.14      6806146.23
      2732121.78      6806247.28
#Sta/Elev= 30
  4730.7  383.31  4773.9  382.04  4846.5  370.10  4847.0  369.97  4949.9  364.77
  4950.1  364.27  4953.9  364.77  4976.5  366.11  4993.7  368.10  5009.9  365.39
  5015.4  369.37  5033.3  365.47  5038.7  369.45  5085.3  365.84  5090.8  370.93
  5137.4  369.39  5160.8  365.09  5166.2  369.22  5184.1  365.72  5189.5  369.33
  5230.7  366.37  5241.6  370.08  5259.5  365.36  5264.9  369.47  5282.8  367.05
  5288.3  370.58  5306.1  369.09  5311.6  371.82  5490.2  376.19  5614.4  386.17
#Mann=7,-1,0
  4730.7    0.05       0  4846.5    0.16       0  4847.0    0.05       0
  4949.9    0.07       0  4953.9    0.05       0  4976.5    0.16       0
  5085.3    0.05       0
Bank Sta=4949.9,4953.9
Exp/Cntr=0.3,0.1

Type RM Length L Ch R = 1,3980,154,154,154
BEGIN DESCRIPTION:
South Twin Creek Trib H3979.69
END DESCRIPTION:
XS GIS Cut Line= 5
      2731260.32      6805941.58      2731392.04      6806046.42
      2731476.97      6806109.03      2731642.43      6806186.52
      2731928.22      6806307.99
#Sta/Elev= 30
  4727.4  372.10  4745.8  372.95  4752.2  372.01  4781.0  373.83  4787.4  372.90
  4795.4  373.99  4801.8  372.65  4809.9  373.03  4816.3  371.97  4830.7  372.43
  4851.5  368.51  4901.3  364.38  4944.9  364.26  4965.7  362.91  4995.0  363.87
  5000.7  363.11  5062.9  363.71  5091.2  361.91  5119.7  361.68  5119.9  361.18
  5123.7  361.68  5211.6  361.97  5221.5  362.99  5242.2  366.27  5264.3  367.18
  5274.8  366.08  5306.2  367.24  5388.0  374.88  5448.6  382.09  5494.5  384.67
#Mann=5,-1,0
  4727.4    0.16       0  5000.7    0.12       0  5119.7    0.07       0
  5123.7    0.12       0  5221.5    0.05       0
Bank Sta=5119.7,5123.7
Exp/Cntr=0.3,0.1

Type RM Length L Ch R = 1,3826,174,174,174
BEGIN DESCRIPTION:
South Twin Creek Trib H3826.35
END DESCRIPTION:
XS GIS Cut Line= 3
      2731223.86      6805927.72      2731404.15      6806235.03
      2731861.93      6806431.63
#Sta/Elev= 30
  4645.2  370.31  4657.1  369.90  4662.9  370.66  4694.2  369.44  4700.0  370.17
  4737.2  367.00  4752.8  366.97  4758.6  367.82  4795.8  363.59  4817.3  362.57
  4823.1  363.40  4854.4  361.84  5029.9  361.75  5034.2  361.65  5034.4  361.15
  5038.2  361.65  5098.6  362.13  5135.1  361.93  5158.7  362.71  5166.8  362.04
  5218.7  361.83  5229.3  361.90  5242.9  363.17  5264.7  367.30  5329.0  372.06
  5358.0  375.06  5387.0  376.50  5395.3  377.77  5457.6  382.48  5499.7  383.46
#Mann=6,-1,0
  4645.2    0.16       0  5029.9    0.12       0  5034.2    0.07       0
  5038.2    0.12       0  5098.6    0.16       0  5218.7    0.05       0
Bank Sta=5034.2,5038.2
Exp/Cntr=0.3,0.1

Type RM Length L Ch R = 1,3652,195,195,195
BEGIN DESCRIPTION:
South Twin Creek Trib H3651.673
END DESCRIPTION:
XS GIS Cut Line= 3
      2731190.28      6805870.62      2731278.46      6806355.57
      2731805.03      6806543.20
#Sta/Elev= 30
  4507.1  370.50  4511.9  371.37  4565.2  368.17  4570.3  368.82  4618.6  366.50
  4623.6  367.22  4659.9  363.78  4710.8  362.01  4771.7  361.93  4781.9  362.68
  4830.7  361.66  4831.0  361.16  4834.5  361.16  4834.7  361.66  5052.8  361.70
  5134.7  361.80  5262.8  362.03  5287.6  362.84  5315.9  363.50  5337.1  367.38
  5392.0  371.50  5411.4  373.46  5417.5  374.70  5473.9  378.08  5504.7  377.78
  5517.6  375.65  5535.5  375.04  5540.8  373.75  5549.4  374.79  5559.0  374.85
#Mann=6,-1,0
  4507.1    0.16       0  4830.7    0.07       0  4834.7    0.16       0
  5052.8    0.12       0  5134.7    0.16       0  5287.6    0.05       0
Bank Sta=4830.7,4834.7
Exp/Cntr=0.3,0.1

Type RM Length L Ch R = 1,3457,420,420,420
BEGIN DESCRIPTION:
South Twin Creek Trib H3456.525
END DESCRIPTION:
XS GIS Cut Line= 3
      2730651.03      6806286.01      2731097.01      6806391.10
      2731923.74      6806886.71
#Sta/Elev= 30
  4541.8  377.38  4629.1  372.88  4716.3  368.56  4814.0  362.27  4834.6  362.87
  4848.5  361.80  4893.9  361.78  5471.4  361.45  5471.7  360.95  5476.0  361.45
  5492.8  362.32  5540.3  361.82  5590.3  362.00  5617.5  365.97  5691.4  369.63
  5706.9  369.19  5734.2  372.29  5743.9  371.76  5749.7  372.58  5765.3  371.42
  5771.1  372.80  5786.7  370.64  5792.5  372.10  5808.0  371.87  5823.6  376.43
  5866.4  377.27  5903.3  382.48  5954.9  382.00  5961.6  383.11  5963.9  385.36
#Mann=7,-1,0
  4541.8    0.05       0  4629.1    0.16       0  4893.9   0.033       0
  5471.4   0.033       0  5476.0   0.033       0  5492.8    0.16       0
  5540.3    0.05       0
Bank Sta=5471.4,5476
Exp/Cntr=0.3,0.1

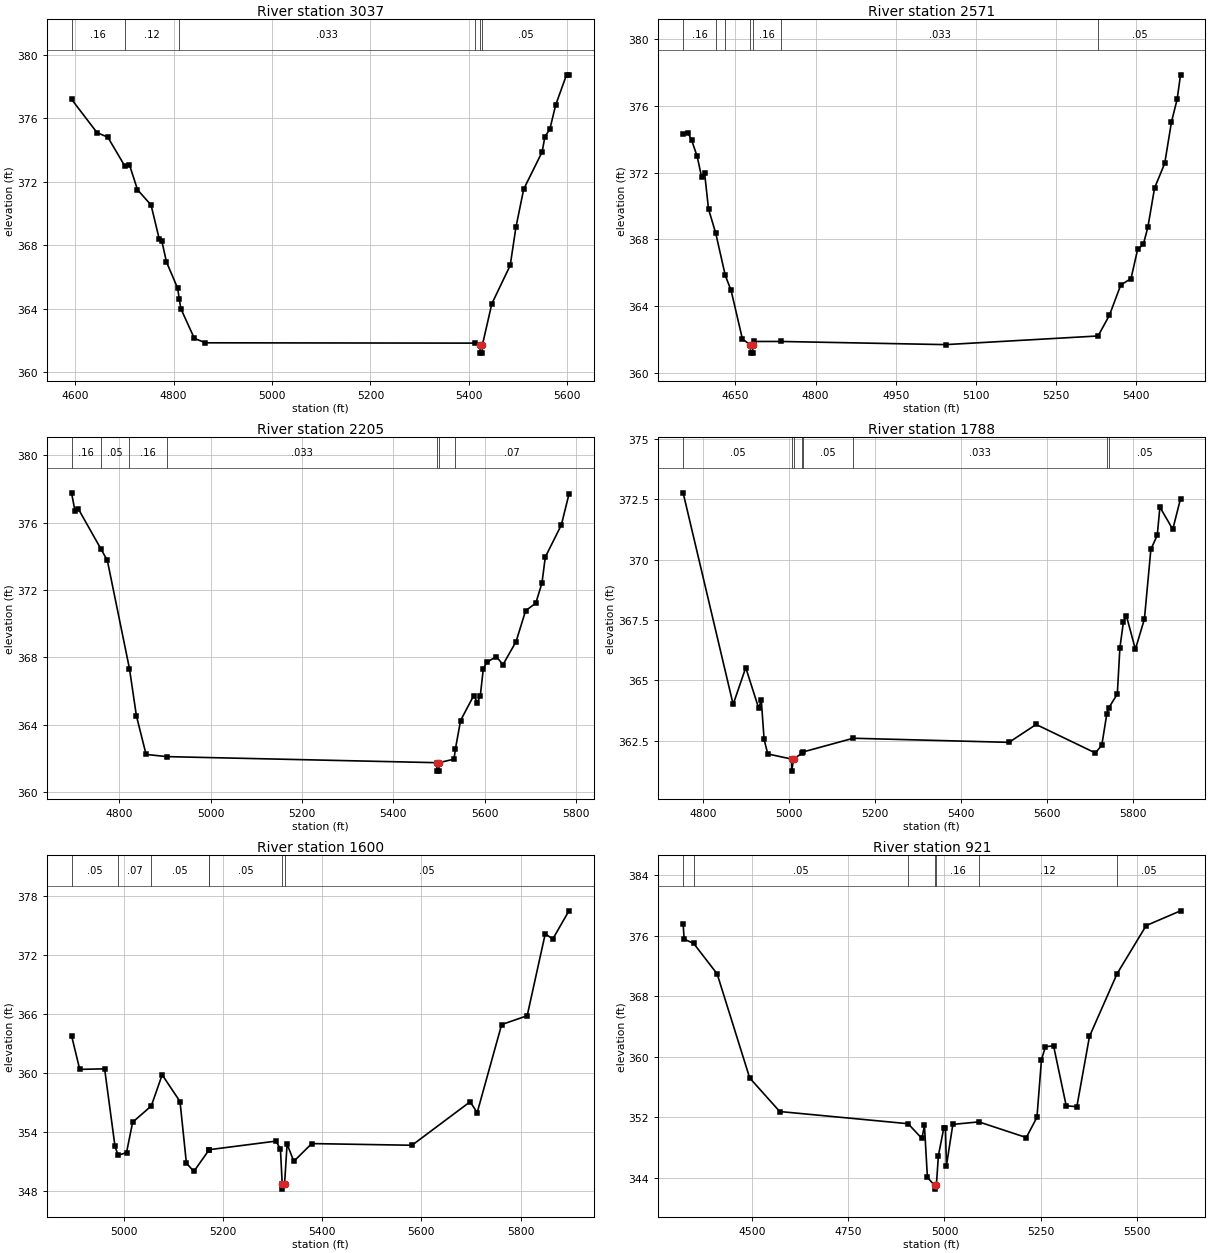
Type RM Length L Ch R = 1,3037,466,466,466
BEGIN DESCRIPTION:
South Twin Creek Trib H3036.67
END DESCRIPTION:
XS GIS Cut Line= 3
      2730635.54      6806451.58      2730999.37      6806644.55
      2731519.55      6806942.50
#Sta/Elev= 30
  4592.4  377.19  4644.2  375.09  4666.2  374.80  4700.8  372.98  4710.2  373.06
  4726.5  371.49  4754.1  370.53  4770.5  368.41  4776.1  368.25  4785.3  366.95
  4808.0  365.30  4811.4  364.63  4814.5  364.01  4842.1  362.13  4864.6  361.85
  5413.3  361.83  5423.0  361.70  5423.3  361.20  5427.3  361.20  5427.6  361.70
  5446.9  364.31  5484.3  366.73  5495.9  369.13  5511.7  371.53  5549.1  373.87
  5554.8  374.83  5564.9  375.31  5576.6  376.82  5598.8  378.73  5603.7  378.73
#Mann=6,-1,0
  4592.4    0.16       0  4700.8    0.12       0  4811.4   0.033       0
  5413.3    0.05       0  5423.0   0.033       0  5427.6    0.05       0
Bank Sta=5423,5427.6
Exp/Cntr=0.3,0.1

Type RM Length L Ch R = 1,2571,366,366,366
BEGIN DESCRIPTION:
South Twin Creek Trib H2571.2
END DESCRIPTION:
XS GIS Cut Line= 3
      2730551.18      6806753.50      2730975.69      6806901.16
      2731432.08      6807054.44
#Sta/Elev= 30
  4552.1  374.33  4561.1  374.39  4567.8  373.97  4578.4  372.97  4586.9  371.71
  4592.2  372.00  4599.6  369.82  4613.0  368.38  4631.0  365.83  4641.9  364.93
  4663.1  362.01  4677.9  361.67  4678.2  361.17  4682.2  361.17  4682.6  361.67
  4685.5  361.87  4735.0  361.87  5043.5  361.68  5328.7  362.20  5350.0  363.45
  5371.1  365.26  5390.3  365.64  5402.7  367.40  5413.3  367.69  5421.8  368.72
  5434.4  371.08  5453.4  372.56  5466.0  375.04  5476.6  376.40  5483.0  377.87
#Mann=7,-1,0
  4552.1    0.16       0  4613.0    0.12       0  4631.0    0.16       0
  4677.9   0.033       0  4682.6    0.16       0  4735.0   0.033       0
  5328.7    0.05       0
Bank Sta=4677.9,4682.6
Exp/Cntr=0.3,0.1

Type RM Length L Ch R = 1,2205,417,417,417
BEGIN DESCRIPTION:
South Twin Creek Trib H2205.41
END DESCRIPTION:
XS GIS Cut Line= 3
      2730432.67      6806823.47      2730654.80      6807039.09
      2731262.05      6807527.88
#Sta/Elev= 30
  4695.3  377.76  4702.9  376.68  4710.1  376.81  4759.7  374.43  4773.7  373.75
  4822.1  367.34  4837.4  364.53  4858.5  362.25  4903.9  362.12  5495.1  361.76
  5495.5  361.26  5499.5  361.26  5499.8  361.76  5532.7  361.97  5535.9  362.59
  5547.1  364.26  5575.9  365.74  5583.8  365.32  5590.3  365.73  5596.9  367.33
  5604.7  367.72  5625.5  368.05  5639.9  367.57  5668.6  368.94  5689.5  370.77
  5711.8  371.22  5725.3  372.41  5732.6  373.95  5767.8  375.86  5784.4  377.68
#Mann=7,-1,0
  4695.3    0.16       0  4759.7    0.05       0  4822.1    0.16       0
  4903.9   0.033       0  5495.1   0.033       0  5499.8   0.033       0
  5535.9    0.07       0
Bank Sta=5495.1,5499.8
Exp/Cntr=0.3,0.1

Type RM Length L Ch R = 1,1788,188,188,188
BEGIN DESCRIPTION:
South Twin Creek Trib H1788.34
END DESCRIPTION:
XS GIS Cut Line= 4
      2730160.97      6806934.02      2730297.29      6807139.80
      2730468.59      6807265.91      2731046.09      6807656.08
#Sta/Elev= 30
  4753.8  372.76  4870.1  364.01  4899.4  365.53  4929.5  363.85  4935.5  364.19
  4942.1  362.56  4950.6  361.96  5005.8  361.75  5006.2  361.25  5010.5  361.75
  5029.5  361.98  5032.0  362.04  5149.4  362.61  5511.5  362.44  5574.5  363.18
  5712.4  362.00  5727.3  362.33  5738.9  363.62  5742.9  363.85  5763.3  364.44
  5769.3  366.35  5777.4  367.41  5784.3  367.68  5805.3  366.29  5826.3  367.54
  5841.3  370.42  5856.2  371.01  5862.3  372.17  5892.2  371.25  5910.3  372.52
#Mann=8,-1,0
  4753.8    0.05       0  5005.8    0.05       0  5010.5    0.05       0
  5029.5   0.033       0  5032.0    0.05       0  5149.4   0.033       0
  5738.9    0.07       0  5742.9    0.05       0
Bank Sta=5005.8,5010.5
Exp/Cntr=0.3,0.1

Type RM Length L Ch R = 1,1600,679,679,679
BEGIN DESCRIPTION:
South Twin Creek Trib H1600.19
END DESCRIPTION:
XS GIS Cut Line= 4
      2730086.37      6807197.18      2730170.96      6807258.92
      2730720.51      6807622.51      2730921.79      6807751.43
#Sta/Elev= 30
  4894.7  363.81  4911.2  360.39  4961.4  360.44  4982.3  352.58  4988.6  351.68
  5005.5  351.94  5017.9  355.03  5055.5  356.68  5077.4  359.84  5113.4  357.12
  5126.2  350.89  5141.2  350.03  5171.9  352.22  5172.2  352.24  5306.7  353.11
  5315.8  352.31  5319.4  348.74  5319.7  348.24  5324.1  348.74  5329.2  352.81
  5342.8  351.06  5378.9  352.86  5581.0  352.69  5698.2  357.10  5712.4  356.00
  5761.7  364.93  5813.2  365.83  5849.6  374.14  5864.8  373.61  5897.4  376.47
#Mann=7,-1,0
  4894.7    0.05       0  4988.6    0.07       0  5055.5    0.05       0
  5171.9    0.07       0  5172.2    0.05       0  5319.4    0.07       0
  5324.1    0.05       0
Bank Sta=5319.4,5324.1
Exp/Cntr=0.3,0.1

Type RM Length L Ch R = 1,921,0,0,0
BEGIN DESCRIPTION:
South Twin Creek Trib H921
END DESCRIPTION:
XS GIS Cut Line= 3
      2729758.53      6807364.73      2730277.61      6807805.55
      2730861.33      6807983.69
#Sta/Elev= 30
  4321.6  377.58  4324.2  375.53  4349.1  374.95  4409.9  370.93  4494.4  357.17
  4572.4  352.73  4905.6  351.12  4941.5  349.17  4948.0  350.90  4955.8  344.02
  4974.2  342.97  4974.6  342.47  4979.0  342.97  4984.3  346.91  4998.3  350.55
  5002.6  350.55  5005.1  345.56  5021.8  351.03  5089.3  351.36  5212.5  349.29
  5240.1  351.97  5251.9  359.61  5262.3  361.31  5283.3  361.41  5316.1  353.49
  5343.7  353.37  5376.5  362.66  5448.1  370.95  5523.7  377.32  5612.9  379.27
#Mann=7,-1,0
  4321.6    0.07       0  4349.1    0.05       0  4905.6    0.16       0
  4974.2    0.07       0  4979.0    0.16       0  5089.3    0.12       0
  5448.1    0.05       0
Bank Sta=4974.2,4979
Exp/Cntr=0.3,0.1

Chan Stop Cuts=-1