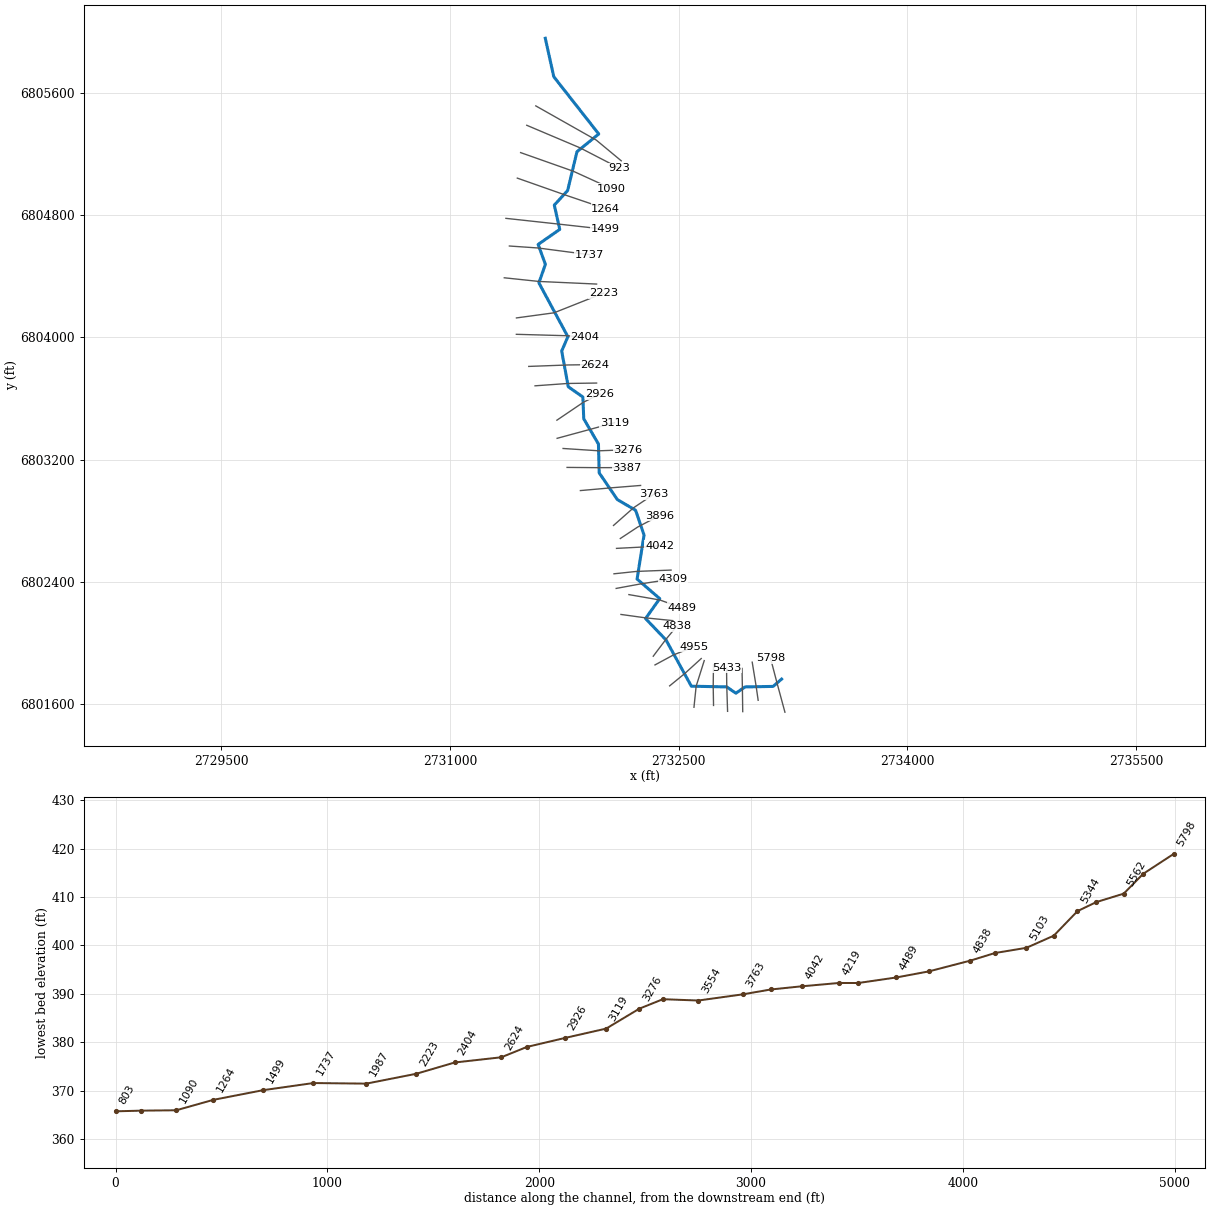
--- South Twin Creek Trib H1.prj (project) ---

Proj Title=South Twin Creek Trib H1 Base Level Engineering
Current Plan=p01
Default Exp/Contr=0.3,0.1
English Units
Geom File=g01
Flow File=f01
Plan File=p01
BEGIN DESCRIPTION:
South Twin Creek Trib H1
END DESCRIPTION:

--- South Twin Creek Trib H1.p01 (plan) ---

Plan Title=Multiple Run
Short Identifier=Multiple
Geom File=g01
Flow File=f01
Subcritical Flow
K Sum by GR= 0
Std Step Tol= 0.01
Critical Tol= 0.01
Num of Std Step Trials= 20
Max Error Tol= 0.3
Flow Tol Ratio= 0.001
Split Flow NTrial= 30
Split Flow Tol= 0.02
Split Flow Ratio= 0.02
Log Output Level= 0
Friction Slope Method= 1
Unsteady Friction Slope Method= 2
Unsteady Bridges Friction Slope Method= 1
Parabolic Critical Depth
Global Vel Dist=  1 , 1 , 1
Global Log Level= 0
CheckData=True
Encroach Param= -1, 0, 0, 0
BEGIN DESCRIPTION:
Multiple Run
END DESCRIPTION:

--- South Twin Creek Trib H1.f01 (steady flow) ---

Flow Title=Multiple
Number of Profiles=7
Profile Names=10-year,25-year,50-year,1pct_min,100-year,1pct_plu,500-year
River Rch & RM= South Twin Creek,Reach-1,5798
     340     440     518     303     605    1208     825
Boundary for River Rch & Prof#=South Twin Creek,Reach-1,1
Up Type=0
Dn Type=3
Dn Slope=0.005
Boundary for River Rch & Prof#=South Twin Creek,Reach-1,2
Up Type=0
Dn Type=3
Dn Slope=0.005
Boundary for River Rch & Prof#=South Twin Creek,Reach-1,3
Up Type=0
Dn Type=3
Dn Slope=0.005
Boundary for River Rch & Prof#=South Twin Creek,Reach-1,4
Up Type=0
Dn Type=3
Dn Slope=0.005
Boundary for River Rch & Prof#=South Twin Creek,Reach-1,5
Up Type=0
Dn Type=3
Dn Slope=0.005
Boundary for River Rch & Prof#=South Twin Creek,Reach-1,6
Up Type=0
Dn Type=3
Dn Slope=0.005
Boundary for River Rch & Prof#=South Twin Creek,Reach-1,7
Up Type=0
Dn Type=3
Dn Slope=0.005

--- South Twin Creek Trib H1.g01 (geometry) ---

Geom Title=Existing Conditions

River Reach=South Twin Creek,Reach-1
Reach XY= 30
      2733176.00      6801761.00      2733120.22      6801712.89
      2732936.44      6801709.62      2732876.00      6801668.56
      2732815.56      6801709.62      2732583.99      6801714.22
      2732417.84      6802017.05      2732283.60      6802157.66
      2732376.60      6802288.29      2732228.00      6802416.30
      2732273.75      6802705.06      2732218.25      6802867.45
      2732098.87      6802937.17      2731979.55      6803112.47
      2731974.64      6803301.35      2731878.25      6803466.93
      2731872.51      6803609.73      2731776.68      6803676.84
      2731733.59      6803911.01      2731774.16      6804004.88
      2731584.05      6804357.68      2731626.62      6804479.24
      2731579.04      6804609.58      2731720.70      6804708.33
      2731685.15      6804867.73      2731772.36      6804962.50
      2731833.75      6805217.45      2731976.61      6805333.71
      2731681.83      6805708.70      2731626.00      6805961.00

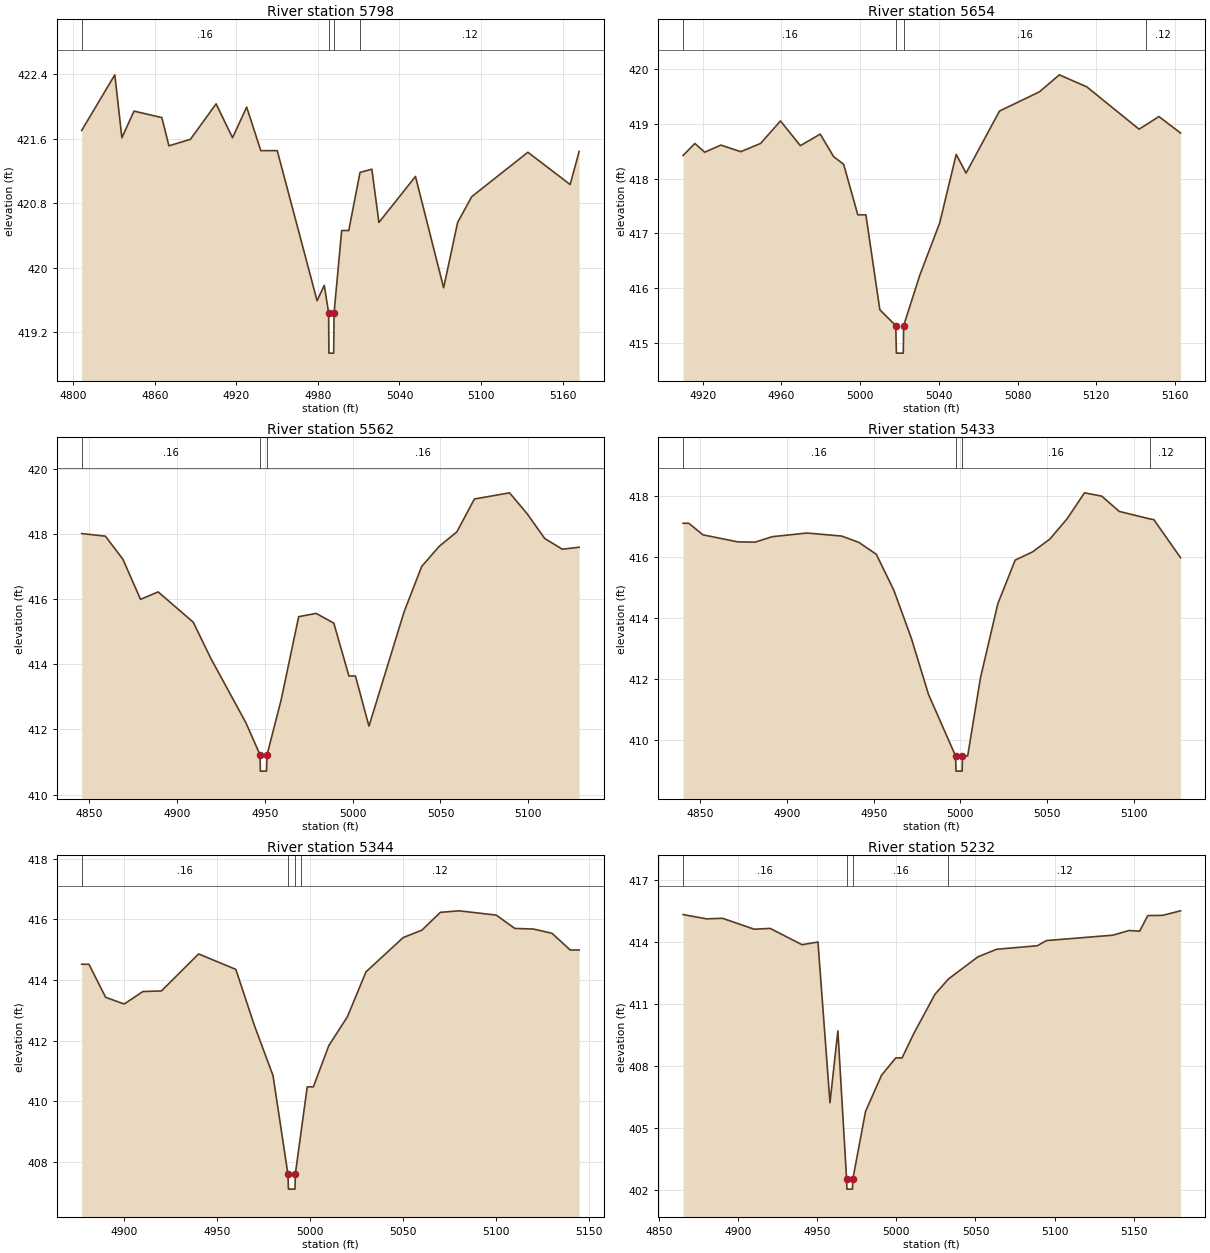
Type RM Length L Ch R = 1,5798,144,144,144
BEGIN DESCRIPTION:
South Twin Creek Trib H15797.998
END DESCRIPTION:
XS GIS Cut Line= 3
      2733197.75      6801543.82      2733147.03      6801730.87
      2733103.32      6801897.43
#Sta/Elev= 30
  4806.2  421.70  4830.6  422.39  4835.8  421.61  4844.7  421.94  4865.2  421.86
  4870.4  421.51  4886.2  421.59  4905.1  422.03  4917.2  421.61  4927.6  421.99
  4938.0  421.45  4950.1  421.45  4979.4  419.59  4984.7  419.78  4987.9  419.44
  4988.1  418.94  4991.6  418.94  4991.9  419.44  4997.5  420.46  5002.7  420.46
  5011.0  421.18  5019.7  421.22  5024.9  420.56  5051.8  421.13  5072.5  419.75
  5082.8  420.56  5093.2  420.88  5134.5  421.43  5165.6  421.03  5172.2  421.44
#Mann=4,-1,0
  4806.2    0.16       0  4987.9    0.07       0  4991.9    0.16       0
  5011.0    0.12       0
Bank Sta=4987.9,4991.9
Exp/Cntr=0.3,0.1

Type RM Length L Ch R = 1,5654,92,92,92
BEGIN DESCRIPTION:
South Twin Creek Trib H15654.3
END DESCRIPTION:
XS GIS Cut Line= 3
      2733022.13      6801622.04      2733008.93      6801713.96
      2732983.15      6801871.81
#Sta/Elev= 30
  4910.0  418.42  4916.0  418.64  4921.0  418.48  4929.2  418.61  4939.3  418.49
  4949.4  418.64  4959.5  419.05  4969.6  418.60  4979.7  418.81  4986.5  418.40
  4991.6  418.26  4998.8  417.34  5002.9  417.34  5010.0  415.61  5018.1  415.32
  5018.4  414.82  5021.9  414.82  5022.1  415.32  5030.3  416.24  5040.4  417.19
  5048.8  418.44  5053.8  418.10  5070.8  419.23  5091.1  419.58  5101.2  419.89
  5115.2  419.67  5141.7  418.90  5145.3  418.98  5151.8  419.13  5162.8  418.83
#Mann=4,-1,0
  4910.0    0.16       0  5018.1    0.07       0  5022.1    0.16       0
  5145.3    0.12       0
Bank Sta=5018.1,5022.1
Exp/Cntr=0.3,0.1

Type RM Length L Ch R = 1,5562,129,129,129
BEGIN DESCRIPTION:
South Twin Creek Trib H15561.75
END DESCRIPTION:
XS GIS Cut Line= 3
      2732920.93      6801547.55      2732918.73      6801703.35
      2732916.46      6801830.61
#Sta/Elev= 29
  4845.8  418.01  4859.3  417.93  4869.3  417.22  4879.3  415.99  4889.3  416.22
  4909.3  415.29  4919.3  414.18  4939.3  412.20  4947.3  411.22  4947.5  410.72
  4951.0  410.72  4951.3  411.22  4959.3  412.90  4969.3  415.46  4979.3  415.56
  4989.3  415.26  4997.9  413.64  5001.6  413.64  5009.3  412.10  5029.3  415.61
  5039.3  417.00  5049.3  417.62  5059.3  418.06  5069.3  419.07  5089.3  419.26
  5099.3  418.62  5109.3  417.86  5119.3  417.53  5128.9  417.59
#Mann=3,-1,0
  4845.8    0.16       0  4947.3    0.07       0  4951.3    0.16       0
Bank Sta=4947.3,4951.3
Exp/Cntr=0.3,0.1

Type RM Length L Ch R = 1,5433,89,89,89
BEGIN DESCRIPTION:
South Twin Creek Trib H15433.4
END DESCRIPTION:
XS GIS Cut Line= 3
      2732821.60      6801549.51      2732816.31      6801711.33
      2732814.83      6801836.42
#Sta/Elev= 30
  4840.0  417.12  4843.3  417.12  4851.5  416.74  4871.5  416.51  4881.5  416.50
  4891.5  416.68  4911.5  416.80  4931.5  416.70  4941.5  416.49  4951.5  416.10
  4961.6  414.92  4971.6  413.36  4981.6  411.50  4997.2  409.48  4997.5  408.98
  5001.0  408.98  5001.2  409.48  5004.2  409.48  5011.6  412.05  5021.6  414.48
  5031.6  415.91  5041.6  416.18  5051.6  416.60  5061.6  417.27  5071.6  418.12
  5081.6  418.01  5091.6  417.51  5109.5  417.26  5111.6  417.24  5127.0  415.99
#Mann=4,-1,0
  4840.0    0.16       0  4997.2    0.07       0  5001.2    0.16       0
  5109.5    0.12       0
Bank Sta=4997.2,5001.2
Exp/Cntr=0.3,0.1

Type RM Length L Ch R = 1,5344,112,112,112
BEGIN DESCRIPTION:
South Twin Creek Trib H15344.23
END DESCRIPTION:
XS GIS Cut Line= 3
      2732729.50      6801588.09      2732727.30      6801712.69
      2732729.08      6801855.56
#Sta/Elev= 30
  4877.0  414.52  4880.9  414.52  4889.9  413.43  4899.9  413.21  4909.9  413.62
  4919.9  413.64  4939.9  414.86  4959.9  414.35  4969.9  412.50  4979.9  410.85
  4987.9  407.61  4988.2  407.11  4991.7  407.11  4991.9  407.61  4995.1  409.05
  4998.3  410.48  5001.6  410.48  5009.9  411.84  5019.9  412.79  5029.9  414.27
  5049.9  415.40  5059.9  415.64  5069.9  416.23  5079.9  416.28  5099.9  416.14
  5109.9  415.70  5119.9  415.68  5129.9  415.54  5139.7  414.99  5144.5  414.99
#Mann=4,-1,0
  4877.0    0.16       0  4987.9    0.07       0  4991.9    0.16       0
  4995.1    0.12       0
Bank Sta=4987.9,4991.9
Exp/Cntr=0.3,0.1

Type RM Length L Ch R = 1,5232,129,129,129
BEGIN DESCRIPTION:
South Twin Creek Trib H15231.94
END DESCRIPTION:
XS GIS Cut Line= 3
      2732601.19      6801576.20      2732615.41      6801713.97
      2732668.45      6801881.89
#Sta/Elev= 30
  4865.1  415.32  4880.0  415.11  4890.0  415.14  4910.1  414.61  4920.2  414.65
  4940.3  413.86  4950.4  413.99  4958.0  406.21  4963.0  409.69  4968.5  402.53
  4968.7  402.03  4972.2  402.03  4972.5  402.53  4980.5  405.79  4990.6  407.54
  4999.6  408.38  5003.6  408.38  5011.0  409.56  5024.4  411.46  5032.9  412.20
  5051.5  413.27  5063.4  413.64  5089.1  413.81  5094.9  414.06  5136.8  414.32
  5147.3  414.55  5153.8  414.51  5159.0  415.27  5168.3  415.28  5179.7  415.50
#Mann=4,-1,0
  4865.1    0.16       0  4968.5    0.07       0  4972.5    0.16       0
  5032.9    0.12       0
Bank Sta=4968.5,4972.5
Exp/Cntr=0.3,0.1

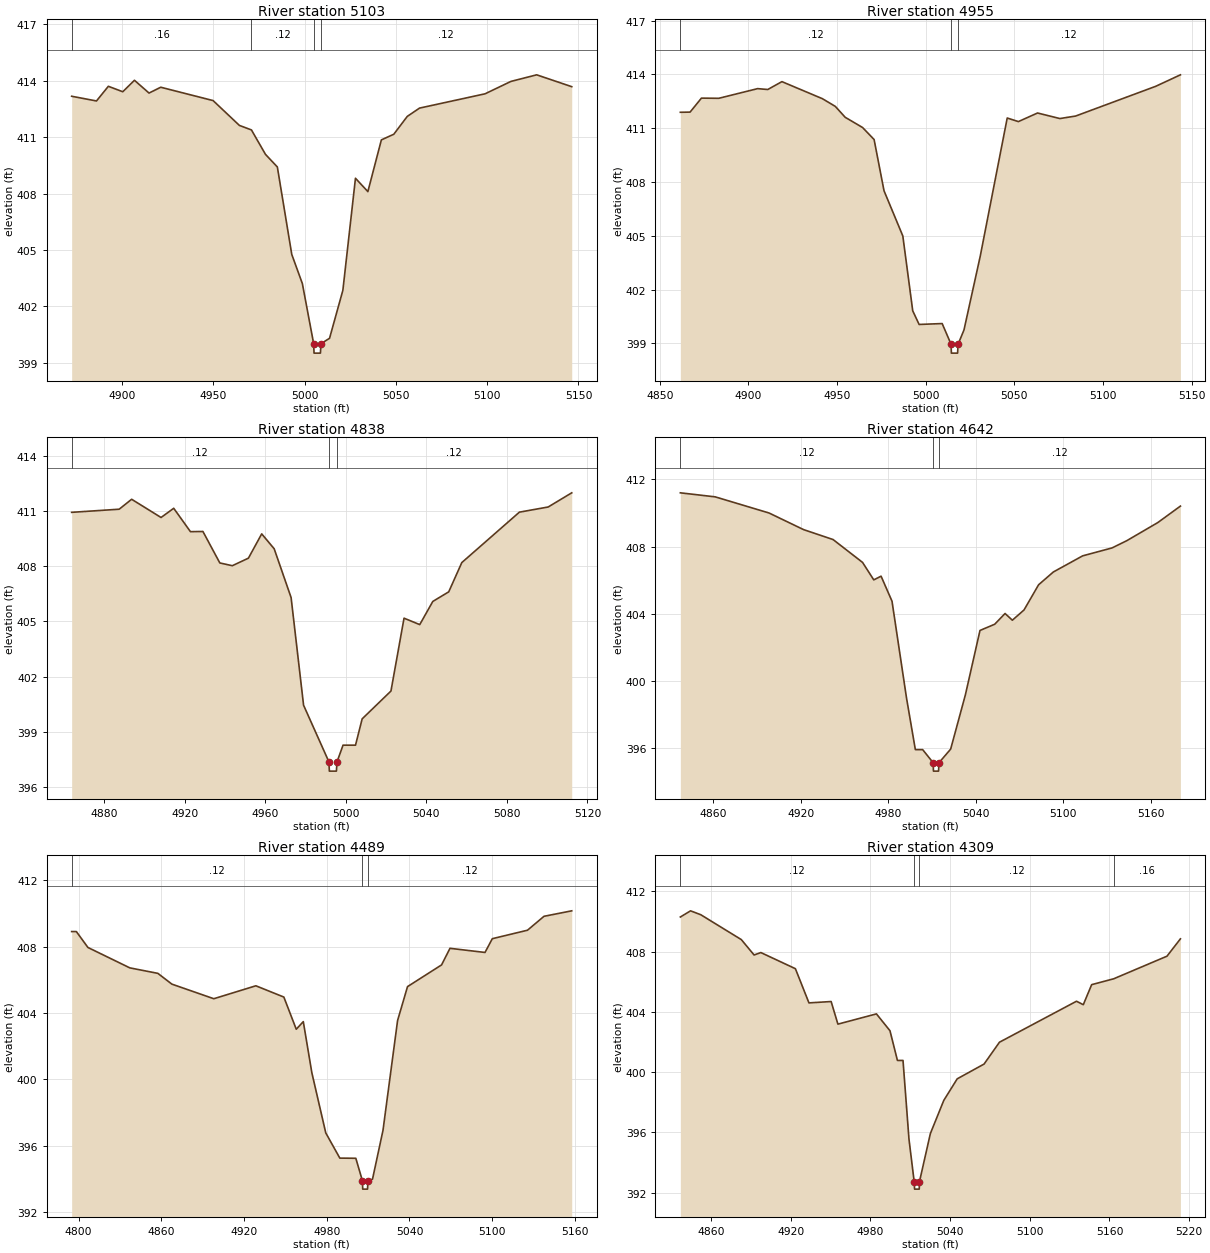
Type RM Length L Ch R = 1,5103,148,148,148
BEGIN DESCRIPTION:
South Twin Creek Trib H15103.34
END DESCRIPTION:
XS GIS Cut Line= 3
      2732441.65      6801716.40      2732539.92      6801796.62
      2732648.85      6801895.54
#Sta/Elev= 30
  4872.3  413.18  4885.9  412.93  4892.4  413.71  4900.3  413.42  4906.7  414.03
  4914.7  413.35  4921.1  413.66  4949.8  412.95  4964.2  411.63  4970.8  411.39
  4978.5  410.09  4985.0  409.42  4992.9  404.77  4998.7  403.22  5004.9  400.02
  5005.1  399.52  5008.6  399.52  5008.9  400.02  5013.6  400.31  5020.9  402.86
  5027.8  408.82  5034.6  408.11  5042.0  410.86  5048.8  411.16  5056.2  412.11
  5062.9  412.55  5098.8  413.31  5113.0  413.97  5127.1  414.32  5146.3  413.69
#Mann=4,-1,0
  4872.3    0.16       0  4970.8    0.12       0  5004.9    0.07       0
  5008.9    0.12       0
Bank Sta=5004.9,5008.9
Exp/Cntr=0.3,0.1

Type RM Length L Ch R = 1,4955,117,117,117
BEGIN DESCRIPTION:
South Twin Creek Trib H14955.43
END DESCRIPTION:
XS GIS Cut Line= 3
      2732345.54      6801853.74      2732467.17      6801919.38
      2732600.98      6801972.29
#Sta/Elev= 30
  4861.6  411.89  4867.1  411.90  4873.5  412.68  4883.3  412.67  4905.2  413.21
  4910.9  413.16  4918.9  413.60  4941.7  412.65  4949.0  412.22  4954.6  411.61
  4964.4  411.04  4970.9  410.37  4976.5  407.51  4987.1  404.99  4992.7  400.81
  4996.3  400.05  5009.3  400.10  5014.3  398.95  5014.5  398.45  5018.0  398.45
  5018.3  398.95  5021.6  399.74  5030.8  403.87  5046.0  411.57  5052.3  411.37
  5063.1  411.85  5075.7  411.54  5084.6  411.68  5129.8  413.34  5143.7  413.98
#Mann=3,-1,0
  4861.6    0.12       0  5014.3    0.07       0  5018.3    0.12       0
Bank Sta=5014.3,5018.3
Exp/Cntr=0.3,0.1

Type RM Length L Ch R = 1,4838,196,196,196
BEGIN DESCRIPTION:
South Twin Creek Trib H14838.45
END DESCRIPTION:
XS GIS Cut Line= 3
      2732334.07      6801910.82      2732416.97      6802021.02
      2732487.59      6802106.02
#Sta/Elev= 30
  4863.8  410.93  4887.4  411.10  4893.6  411.64  4908.2  410.65  4914.5  411.15
  4922.8  409.88  4929.0  409.89  4937.4  408.18  4943.6  408.03  4951.6  408.44
  4958.2  409.76  4964.4  408.95  4972.8  406.30  4979.0  400.45  4991.6  397.37
  4991.8  396.87  4995.3  396.87  4995.6  397.37  4998.6  398.28  5004.8  398.28
  5008.1  399.71  5022.4  401.22  5028.9  405.18  5036.7  404.83  5043.2  406.09
  5051.1  406.61  5057.6  408.20  5086.2  410.94  5100.5  411.22  5112.2  411.99
#Mann=3,-1,0
  4863.8    0.12       0  4991.6    0.07       0  4995.6    0.12       0
Bank Sta=4991.6,4995.6
Exp/Cntr=0.3,0.1

Type RM Length L Ch R = 1,4642,153,153,153
BEGIN DESCRIPTION:
South Twin Creek Trib H14642.07
END DESCRIPTION:
XS GIS Cut Line= 3
      2732122.32      6802184.54      2732282.83      6802162.33
      2732462.66      6802144.05
#Sta/Elev= 30
  4837.5  411.20  4861.4  410.96  4898.3  410.00  4922.0  409.01  4942.2  408.42
  4962.4  407.06  4970.1  406.02  4975.1  406.24  4982.6  404.75  4992.6  398.96
  4998.6  395.92  5003.6  395.92  5010.8  395.14  5011.0  394.64  5014.5  394.64
  5014.8  395.14  5022.8  395.95  5032.9  399.18  5042.9  403.01  5053.0  403.38
  5060.1  404.02  5065.1  403.62  5073.1  404.23  5083.1  405.73  5093.2  406.49
  5113.3  407.45  5133.4  407.92  5143.5  408.35  5164.8  409.43  5180.3  410.41
#Mann=3,-1,0
  4837.5    0.12       0  5010.8    0.07       0  5014.8    0.12       0
Bank Sta=5010.8,5014.8
Exp/Cntr=0.3,0.1

Type RM Length L Ch R = 1,4489,180,180,180
BEGIN DESCRIPTION:
South Twin Creek Trib H14489.21
END DESCRIPTION:
XS GIS Cut Line= 3
      2732174.41      6802314.57      2732377.52      6802279.29
      2732524.90      6802226.49
#Sta/Elev= 30
  4795.0  408.92  4798.4  408.92  4806.8  407.96  4837.2  406.73  4857.5  406.40
  4867.7  405.75  4898.1  404.87  4928.6  405.65  4948.9  404.97  4957.9  403.03
  4963.0  403.49  4969.2  400.41  4979.3  396.78  4989.5  395.26  5001.1  395.25
  5005.9  393.89  5006.1  393.39  5009.6  393.39  5009.9  393.89  5013.2  393.99
  5020.8  396.93  5031.4  403.56  5038.6  405.60  5063.3  406.91  5069.4  407.91
  5094.8  407.66  5100.1  408.49  5125.6  409.00  5137.6  409.84  5157.7  410.17
#Mann=3,-1,0
  4795.0    0.12       0  5005.9    0.07       0  5009.9    0.12       0
Bank Sta=5005.9,5009.9
Exp/Cntr=0.3,0.1

Type RM Length L Ch R = 1,4309,90,90,90
BEGIN DESCRIPTION:
South Twin Creek Trib H14308.84
END DESCRIPTION:
XS GIS Cut Line= 3
      2732090.86      6802355.09      2732251.98      6802384.86
      2732462.02      6802417.39
#Sta/Elev= 30
  4837.0  410.30  4844.7  410.71  4852.4  410.45  4882.9  408.80  4892.5  407.78
  4897.6  407.94  4923.6  406.87  4933.8  404.60  4950.5  404.69  4955.6  403.19
  4984.6  403.87  4994.8  402.75  5000.4  400.78  5004.6  400.78  5009.1  395.55
  5013.0  392.74  5013.3  392.24  5016.8  392.24  5017.0  392.74  5025.2  395.93
  5035.3  398.13  5045.4  399.56  5065.6  400.54  5077.2  401.99  5135.2  404.71
  5140.3  404.48  5146.6  405.81  5163.2  406.20  5203.3  407.70  5213.4  408.85
#Mann=4,-1,0
  4837.0    0.12       0  5013.0    0.07       0  5017.0    0.12       0
  5163.2    0.16       0
Bank Sta=5013,5017
Exp/Cntr=0.3,0.1

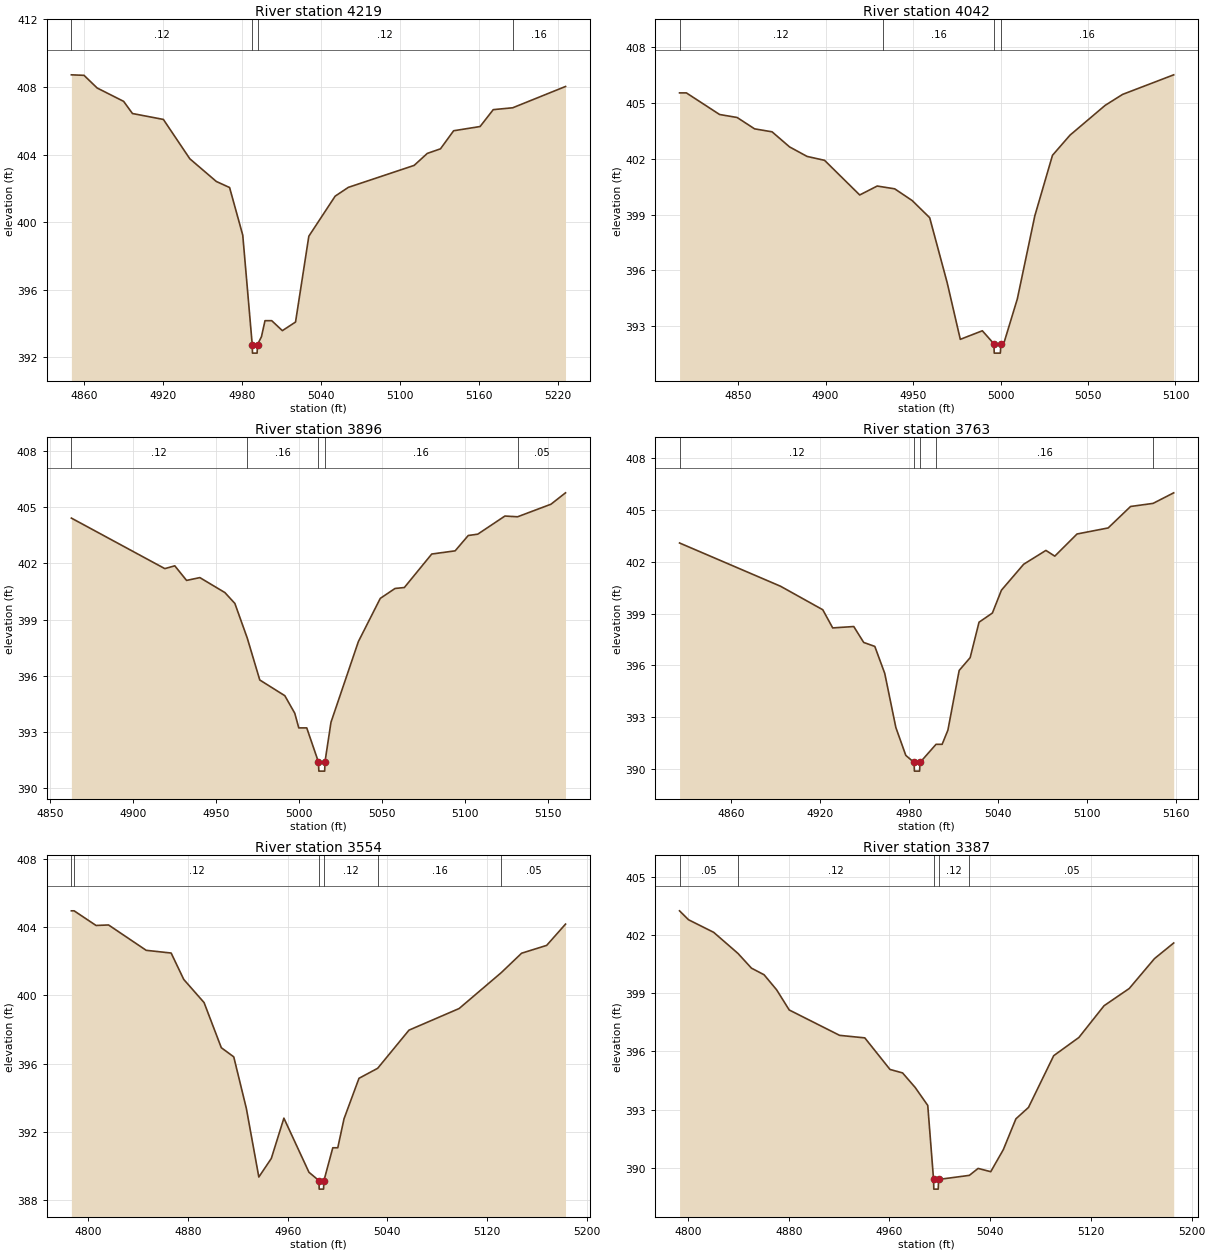
Type RM Length L Ch R = 1,4219,177,177,177
BEGIN DESCRIPTION:
South Twin Creek Trib H14218.76
END DESCRIPTION:
XS GIS Cut Line= 3
      2732076.49      6802450.96      2732224.64      6802466.57
      2732450.90      6802475.36
#Sta/Elev= 30
  4850.5  408.72  4860.1  408.69  4870.1  407.94  4890.2  407.15  4896.9  406.43
  4920.4  406.08  4940.5  403.75  4960.6  402.41  4970.7  402.05  4980.7  399.23
  4987.9  392.75  4988.1  392.25  4991.6  392.25  4991.9  392.75  4994.9  393.22
  4997.6  394.17  5002.7  394.17  5010.8  393.58  5020.8  394.09  5030.9  399.17
  5050.9  401.54  5060.9  402.06  5110.9  403.36  5120.9  404.07  5130.9  404.34
  5140.9  405.41  5161.0  405.66  5171.0  406.66  5185.8  406.77  5225.9  408.03
#Mann=4,-1,0
  4850.5    0.12       0  4987.9    0.07       0  4991.9    0.12       0
  5185.8    0.16       0
Bank Sta=4987.9,4991.9
Exp/Cntr=0.3,0.1

Type RM Length L Ch R = 1,4042,146,146,146
BEGIN DESCRIPTION:
South Twin Creek Trib H14042.08
END DESCRIPTION:
XS GIS Cut Line= 3
      2732093.16      6802617.61      2732278.22      6802627.15
      2732375.13      6802634.63
#Sta/Elev= 30
  4816.5  405.53  4820.4  405.53  4839.4  404.37  4849.4  404.21  4859.4  403.60
  4869.4  403.44  4879.4  402.63  4889.4  402.12  4899.4  401.91  4919.5  400.05
  4929.5  400.53  4932.8  400.48  4939.5  400.38  4949.5  399.75  4959.5  398.83
  4969.5  395.34  4977.0  392.30  4989.6  392.76  4996.2  392.06  4996.4  391.56
  4999.9  391.56  5000.2  392.06  5001.8  392.06  5009.6  394.47  5019.6  398.93
  5029.7  402.18  5039.7  403.26  5059.8  404.86  5069.8  405.45  5099.0  406.50
#Mann=4,-1,0
  4816.5    0.12       0  4932.8    0.16       0  4996.2    0.07       0
  5000.2    0.16       0
Bank Sta=4996.2,5000.2
Exp/Cntr=0.3,0.1

Type RM Length L Ch R = 1,3896,133,133,133
BEGIN DESCRIPTION:
South Twin Creek Trib H13896.48
END DESCRIPTION:
XS GIS Cut Line= 3
      2732118.08      6802682.27      2732232.49      6802757.69
      2732374.91      6802832.06
#Sta/Elev= 30
  4863.0  404.42  4919.3  401.72  4925.3  401.87  4932.4  401.09  4940.4  401.24
  4955.5  400.44  4961.5  399.86  4969.0  398.00  4976.5  395.77  4991.6  394.93
  4997.6  393.99  5000.0  393.21  5004.8  393.21  5011.8  391.40  5012.1  390.90
  5015.6  390.90  5015.8  391.40  5019.4  393.51  5035.9  397.82  5049.1  400.13
  5058.0  400.66  5063.6  400.71  5080.1  402.50  5094.2  402.67  5102.1  403.49
  5107.8  403.56  5124.2  404.53  5131.8  404.49  5151.9  405.16  5160.7  405.77
#Mann=5,-1,0
  4863.0    0.12       0  4969.0    0.16       0  5011.8    0.07       0
  5015.8    0.16       0  5131.8    0.05       0
Bank Sta=5011.8,5015.8
Exp/Cntr=0.3,0.1

Type RM Length L Ch R = 1,3763,209,209,209
BEGIN DESCRIPTION:
South Twin Creek Trib H13763.03
END DESCRIPTION:
XS GIS Cut Line= 3
      2732073.42      6802767.81      2732204.53      6802883.46
      2732336.33      6802971.44
#Sta/Elev= 30
  4825.1  403.08  4893.2  400.58  4921.7  399.22  4928.4  398.17  4942.6  398.25
  4949.3  397.33  4956.8  397.10  4963.5  395.54  4971.0  392.41  4977.7  390.80
  4983.3  390.39  4983.5  389.89  4987.0  389.89  4987.3  390.39  4998.1  391.44
  5002.2  391.44  5006.1  392.26  5013.7  395.71  5021.1  396.45  5027.1  398.50
  5036.1  399.03  5042.2  400.35  5057.2  401.85  5072.2  402.65  5078.2  402.32
  5093.2  403.60  5114.2  403.95  5129.3  405.19  5144.5  405.37  5158.4  405.98
#Mann=5,-1,0
  4825.1    0.12       0  4983.3    0.07       0  4987.3    0.12       0
  4998.1    0.16       0  5144.5    0.05       0
Bank Sta=4983.3,4987.3
Exp/Cntr=0.3,0.1

Type RM Length L Ch R = 1,3554,167,167,167
BEGIN DESCRIPTION:
South Twin Creek Trib H13553.91
END DESCRIPTION:
XS GIS Cut Line= 3
      2731856.28      6802996.49      2732069.06      6803015.35
      2732251.06      6803030.02
#Sta/Elev= 30
  4786.6  404.97  4788.8  404.97  4806.4  404.11  4816.4  404.14  4846.6  402.65
  4866.6  402.49  4876.7  400.94  4893.0  399.58  4906.8  396.93  4916.8  396.39
  4926.9  393.36  4936.9  389.33  4946.9  390.42  4957.0  392.79  4977.1  389.61
  4985.1  389.12  4985.3  388.62  4988.8  388.62  4989.1  389.12  4996.2  391.05
  5000.2  391.05  5005.2  392.75  5017.2  395.13  5032.2  395.72  5057.3  397.96
  5097.5  399.23  5131.3  401.34  5147.6  402.48  5167.7  402.94  5182.8  404.19
#Mann=6,-1,0
  4786.6    0.05       0  4788.8    0.12       0  4985.1    0.07       0
  4989.1    0.12       0  5032.2    0.16       0  5131.3    0.05       0
Bank Sta=4985.1,4989.1
Exp/Cntr=0.3,0.1

Type RM Length L Ch R = 1,3387,111,111,111
BEGIN DESCRIPTION:
South Twin Creek Trib H13386.9
END DESCRIPTION:
XS GIS Cut Line= 3
      2731768.86      6803148.30      2731974.08      6803146.63
      2732161.26      6803147.15
#Sta/Elev= 30
  4793.3  403.26  4800.4  402.80  4820.4  402.15  4839.7  401.06  4850.4  400.30
  4860.4  399.96  4870.4  399.18  4880.4  398.14  4920.4  396.83  4940.4  396.70
  4960.4  395.07  4970.4  394.89  4980.4  394.14  4990.4  393.21  4995.0  389.39
  4995.2  388.89  4998.7  388.89  4999.0  389.39  5023.4  389.60  5030.4  389.96
  5040.4  389.79  5050.4  390.93  5060.4  392.52  5070.4  393.11  5090.4  395.78
  5110.4  396.72  5130.4  398.36  5150.4  399.25  5170.4  400.79  5185.7  401.60
#Mann=5,-1,0
  4793.3    0.05       0  4839.7    0.12       0  4995.0    0.07       0
  4999.0    0.12       0  5023.4    0.05       0
Bank Sta=4995,4999
Exp/Cntr=0.3,0.1

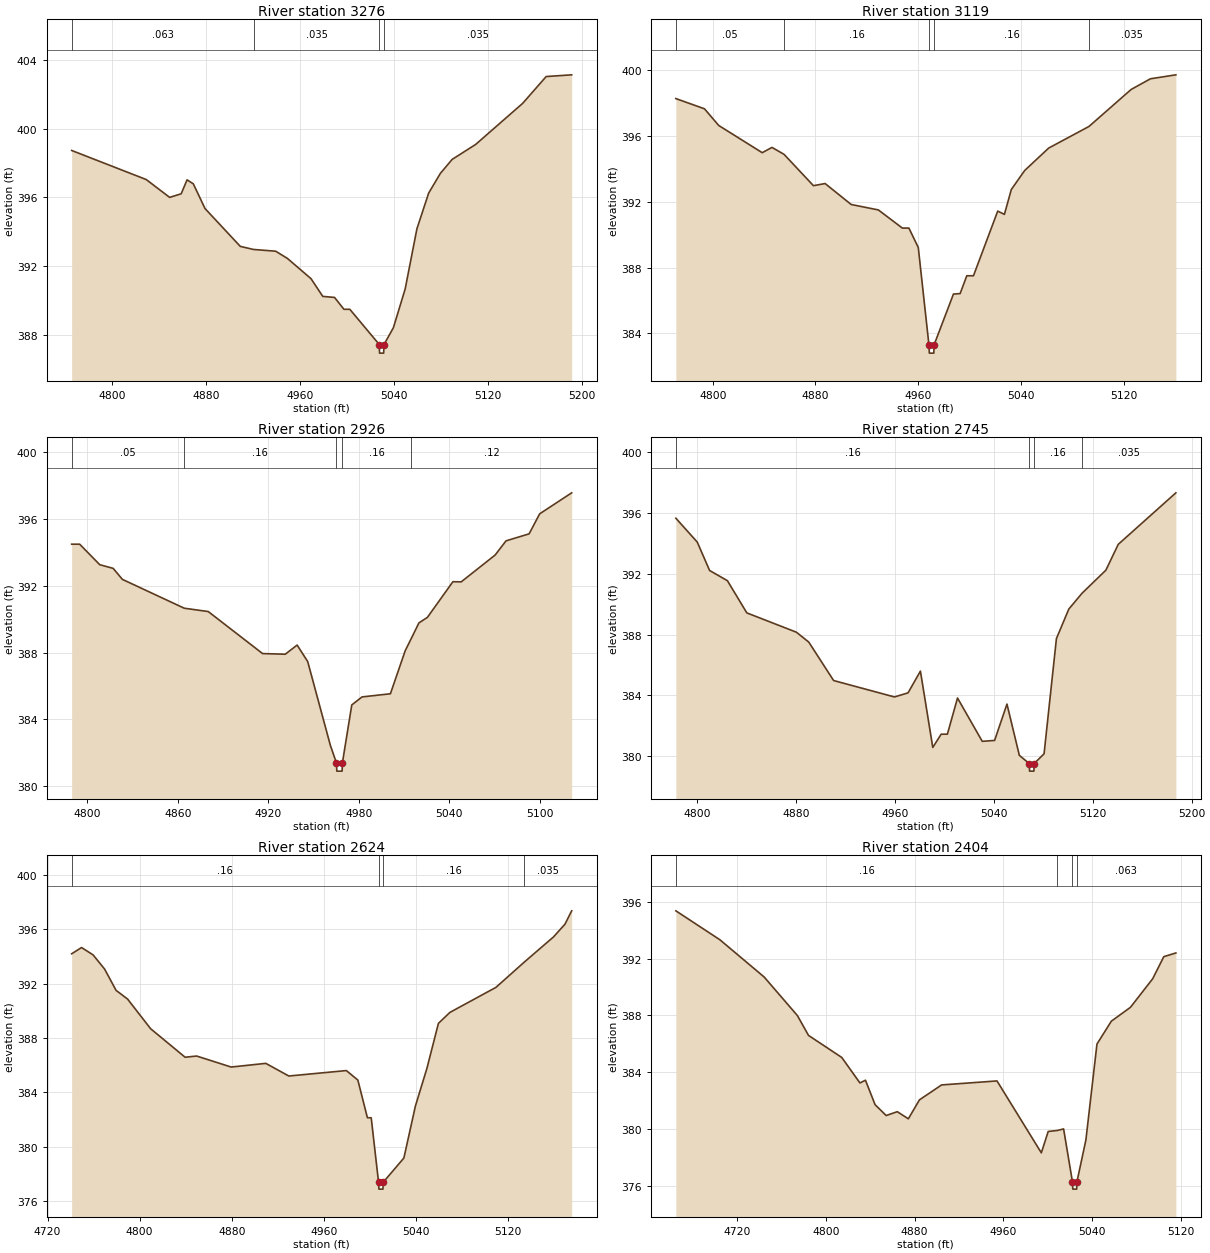
Type RM Length L Ch R = 1,3276,157,157,157
BEGIN DESCRIPTION:
South Twin Creek Trib H13276.39
END DESCRIPTION:
XS GIS Cut Line= 3
      2731742.77      6803272.38      2731977.00      6803257.11
      2732167.64      6803264.19
#Sta/Elev= 30
  4765.9  398.73  4829.3  397.04  4849.3  396.00  4859.1  396.21  4864.1  397.02
  4869.4  396.79  4879.4  395.35  4909.4  393.15  4920.7  392.97  4939.5  392.87
  4949.5  392.45  4969.6  391.27  4979.6  390.24  4989.6  390.18  4997.6  389.49
  5002.6  389.49  5027.7  387.44  5027.9  386.94  5031.4  386.94  5031.7  387.44
  5039.7  388.42  5049.7  390.67  5059.7  394.17  5069.7  396.25  5079.7  397.40
  5089.7  398.21  5109.7  399.08  5149.7  401.47  5169.7  403.03  5191.4  403.13
#Mann=4,-1,0
  4765.9   0.063       0  4920.7   0.035       0  5027.7   0.035       0
  5031.7   0.035       0
Bank Sta=5027.7,5031.7
Exp/Cntr=0.3,0.1

Type RM Length L Ch R = 1,3119,193,193,193
BEGIN DESCRIPTION:
South Twin Creek Trib H13118.7
END DESCRIPTION:
XS GIS Cut Line= 3
      2731703.72      6803339.00      2731924.03      6803398.73
      2732079.64      6803441.35
#Sta/Elev= 30
  4771.2  398.24  4793.5  397.62  4804.6  396.61  4838.5  394.96  4846.1  395.28
  4855.5  394.86  4878.4  392.96  4887.5  393.09  4907.8  391.82  4929.0  391.49
  4947.7  390.39  4952.8  390.39  4960.1  389.21  4968.4  383.31  4968.7  382.81
  4972.2  382.81  4972.4  383.31  4987.5  386.39  4992.7  386.42  4997.9  387.50
  5003.1  387.50  5022.0  391.42  5027.2  391.22  5032.6  392.73  5043.0  393.88
  5061.7  395.24  5093.1  396.55  5125.9  398.79  5141.0  399.44  5160.8  399.68
#Mann=5,-1,0
  4771.2    0.05       0  4855.5    0.16       0  4968.4    0.07       0
  4972.4    0.16       0  5093.1   0.035       0
Bank Sta=4968.4,4972.4
Exp/Cntr=0.3,0.1

Type RM Length L Ch R = 1,2926,181,181,181
BEGIN DESCRIPTION:
South Twin Creek Trib H12926.18
END DESCRIPTION:
XS GIS Cut Line= 3
      2731702.23      6803457.84      2731877.42      6803576.27
      2731985.01      6803629.02
#Sta/Elev= 30
  4789.7  394.50  4795.0  394.50  4808.3  393.27  4817.2  393.05  4823.3  392.39
  4864.3  390.66  4880.2  390.46  4916.2  387.94  4931.2  387.90  4939.1  388.45
  4946.1  387.46  4961.1  382.44  4965.1  381.39  4965.4  380.89  4968.9  380.89
  4969.1  381.39  4975.3  384.86  4982.1  385.34  5000.9  385.53  5010.7  388.11
  5014.7  388.84  5019.8  389.78  5025.4  390.11  5042.3  392.25  5047.8  392.24
  5070.3  393.85  5077.5  394.70  5092.8  395.12  5099.8  396.32  5121.0  397.58
#Mann=5,-1,0
  4789.7    0.05       0  4864.3    0.16       0  4965.1    0.07       0
  4969.1    0.16       0  5014.7    0.12       0
Bank Sta=4965.1,4969.1
Exp/Cntr=0.3,0.1

Type RM Length L Ch R = 1,2745,121,121,121
BEGIN DESCRIPTION:
South Twin Creek Trib H12745.37
END DESCRIPTION:
XS GIS Cut Line= 3
      2731558.73      6803683.07      2731774.53      6803698.54
      2731962.55      6803701.24
#Sta/Elev= 30
  4782.8  395.66  4800.1  394.09  4810.1  392.22  4824.5  391.55  4840.2  389.43
  4880.3  388.16  4890.3  387.51  4910.4  384.98  4959.6  383.90  4970.6  384.17
  4980.6  385.60  4990.6  380.58  4997.4  381.45  5002.4  381.45  5010.6  383.83
  5030.6  380.98  5040.6  381.04  5050.6  383.43  5060.6  380.06  5068.6  379.52
  5068.9  379.02  5072.4  379.02  5072.6  379.52  5080.6  380.16  5090.6  387.74
  5100.6  389.68  5111.4  390.73  5130.6  392.24  5140.6  393.94  5187.2  397.33
#Mann=4,-1,0
  4782.8    0.16       0  5068.6    0.07       0  5072.6    0.16       0
  5111.4   0.035       0
Bank Sta=5068.6,5072.6
Exp/Cntr=0.3,0.1

Type RM Length L Ch R = 1,2624,220,220,220
BEGIN DESCRIPTION:
South Twin Creek Trib H12624.12
END DESCRIPTION:
XS GIS Cut Line= 3
      2731517.45      6803810.25      2731777.56      6803819.83
      2731951.76      6803822.21
#Sta/Elev= 30
  4740.9  394.19  4749.5  394.65  4759.5  394.11  4769.5  393.07  4779.5  391.50
  4789.5  390.86  4809.5  388.68  4839.5  386.58  4849.5  386.67  4879.5  385.86
  4909.6  386.13  4929.6  385.20  4979.6  385.60  4989.6  384.90  4997.9  382.13
  5001.2  382.13  5007.6  377.38  5007.9  376.88  5011.4  376.88  5011.6  377.38
  5029.6  379.17  5039.6  382.99  5049.6  385.76  5059.6  389.07  5069.6  389.88
  5109.6  391.72  5134.1  393.57  5159.6  395.43  5169.6  396.37  5175.4  397.35
#Mann=4,-1,0
  4740.9    0.16       0  5007.6    0.07       0  5011.6    0.16       0
  5134.1   0.035       0
Bank Sta=5007.6,5011.6
Exp/Cntr=0.3,0.1

Type RM Length L Ch R = 1,2404,181,181,181
BEGIN DESCRIPTION:
South Twin Creek Trib H12403.67
END DESCRIPTION:
XS GIS Cut Line= 3
      2731436.31      6804020.66      2731773.35      6804011.27
      2731886.83      6804000.09
#Sta/Elev= 30
  4664.6  395.35  4704.3  393.32  4744.3  390.70  4774.3  387.99  4784.3  386.60
  4814.3  385.05  4830.7  383.26  4835.7  383.45  4844.4  381.73  4854.4  380.97
  4864.4  381.24  4874.4  380.74  4884.4  382.07  4904.4  383.12  4954.4  383.40
  4994.4  378.35  5000.6  379.85  5008.9  379.92  5014.5  380.03  5022.5  376.30
  5022.8  375.80  5026.3  375.80  5026.5  376.30  5034.6  379.25  5044.6  385.99
  5057.6  387.60  5074.8  388.57  5094.9  390.58  5104.9  392.13  5115.8  392.39
#Mann=4,-1,0
  4664.6    0.16       0  5008.9   0.063       0  5022.5    0.07       0
  5026.5   0.063       0
Bank Sta=5022.5,5026.5
Exp/Cntr=0.3,0.1

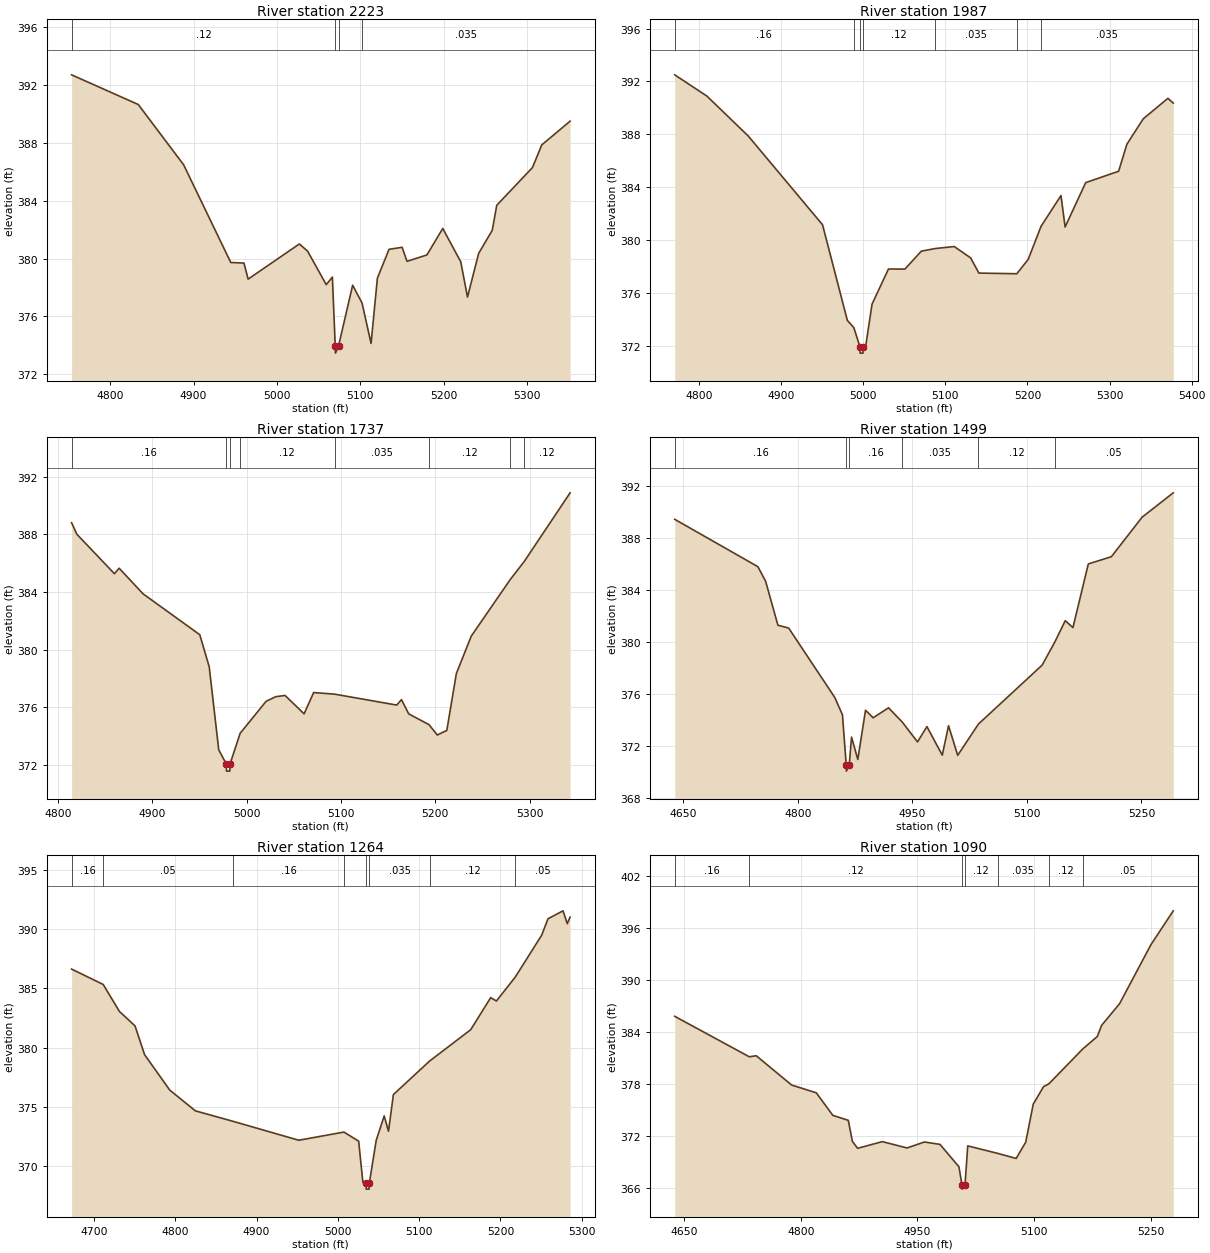
Type RM Length L Ch R = 1,2223,236,236,236
BEGIN DESCRIPTION:
South Twin Creek Trib H12223.41
END DESCRIPTION:
XS GIS Cut Line= 3
      2731436.73      6804128.04      2731683.05      6804161.54
      2732007.94      6804290.40
#Sta/Elev= 30
  4753.6  392.69  4833.6  390.64  4888.0  386.48  4944.6  379.73  4960.4  379.69
  4965.4  378.58  5026.9  381.01  5036.8  380.51  5059.1  378.20  5066.5  378.72
  5069.9  373.97  5070.2  373.47  5073.9  373.97  5090.8  378.16  5102.1  376.93
  5112.9  374.14  5120.5  378.65  5134.5  380.64  5150.2  380.78  5156.0  379.81
  5179.9  380.25  5198.9  382.08  5220.5  379.78  5228.6  377.34  5242.0  380.36
  5258.3  381.95  5263.7  383.68  5306.6  386.29  5317.7  387.85  5351.7  389.49
#Mann=4,-1,0
  4753.6    0.12       0  5069.9    0.07       0  5073.9    0.12       0
  5102.1   0.035       0
Bank Sta=5069.9,5073.9
Exp/Cntr=0.3,0.1

Type RM Length L Ch R = 1,1987,250,250,250
BEGIN DESCRIPTION:
South Twin Creek Trib H11987.26
END DESCRIPTION:
XS GIS Cut Line= 3
      2731357.00      6804391.14      2731585.56      6804367.07
      2731962.45      6804350.06
#Sta/Elev= 30
  4770.5  392.50  4809.7  390.89  4860.0  387.87  4950.5  381.15  4980.7  373.91
  4988.6  373.36  4996.0  371.93  4996.3  371.43  4999.8  371.43  5000.0  371.93
  5003.0  371.93  5010.8  375.14  5030.8  377.80  5050.8  377.79  5070.8  379.15
  5087.9  379.35  5110.9  379.50  5130.9  378.64  5140.9  377.49  5187.1  377.44
  5201.0  378.53  5216.6  381.03  5240.9  383.36  5245.9  380.98  5271.0  384.34
  5311.1  385.20  5321.1  387.24  5341.1  389.17  5371.1  390.72  5377.6  390.36
#Mann=7,-1,0
  4770.5    0.16       0  4988.6    0.12       0  4996.0    0.07       0
  5000.0    0.12       0  5087.9   0.035       0  5187.1    0.05       0
  5216.6   0.035       0
Bank Sta=4996,5000
Exp/Cntr=0.3,0.1

Type RM Length L Ch R = 1,1737,238,238,238
BEGIN DESCRIPTION:
South Twin Creek Trib H11737.39
END DESCRIPTION:
XS GIS Cut Line= 3
      2731390.42      6804599.44      2731578.19      6804586.54
      2731915.62      6804542.53
#Sta/Elev= 30
  4814.5  388.81  4820.1  388.01  4859.9  385.27  4864.9  385.65  4890.3  383.87
  4950.4  381.03  4960.4  378.80  4970.5  373.03  4978.5  372.05  4978.7  371.55
  4982.2  371.55  4982.5  372.05  4993.2  374.18  5020.7  376.40  5030.8  376.72
  5040.8  376.81  5061.0  375.53  5071.1  377.01  5093.3  376.90  5159.2  376.14
  5164.2  376.52  5171.9  375.53  5193.4  374.78  5202.2  374.06  5212.3  374.38
  5222.4  378.33  5238.2  380.93  5279.5  384.86  5294.5  386.13  5343.0  390.89
#Mann=8,-1,0
  4814.5    0.16       0  4978.5    0.07       0  4982.5    0.16       0
  4993.2    0.12       0  5093.3   0.035       0  5193.4    0.12       0
  5279.5    0.05       0  5294.5    0.12       0
Bank Sta=4978.5,4982.5
Exp/Cntr=0.3,0.1

Type RM Length L Ch R = 1,1499,235,235,235
BEGIN DESCRIPTION:
South Twin Creek Trib H11499.17
END DESCRIPTION:
XS GIS Cut Line= 3
      2731367.72      6804780.75      2731727.13      6804741.58
      2732016.51      6804709.42
#Sta/Elev= 30
  4638.9  389.47  4747.8  385.82  4757.9  384.70  4774.0  381.31  4788.1  381.09
  4848.4  375.75  4858.5  374.41  4863.4  370.57  4863.7  370.07  4867.4  370.57
  4870.4  372.69  4878.6  370.97  4888.7  374.76  4898.7  374.18  4918.8  374.95
  4936.8  373.85  4956.8  372.32  4969.1  373.50  4989.2  371.30  4997.4  373.57
  5009.4  371.29  5036.6  373.70  5120.0  378.24  5136.5  380.01  5150.2  381.66
  5160.3  381.13  5180.4  386.03  5210.6  386.59  5250.8  389.63  5291.6  391.51
#Mann=6,-1,0
  4638.9    0.16       0  4863.4   0.035       0  4867.4    0.16       0
  4936.8   0.035       0  5036.6    0.12       0  5136.5    0.05       0
Bank Sta=4863.4,4867.4
Exp/Cntr=0.3,0.1

Type RM Length L Ch R = 1,1264,174,174,174
BEGIN DESCRIPTION:
South Twin Creek Trib H11263.5
END DESCRIPTION:
XS GIS Cut Line= 3
      2731442.45      6805044.42      2731753.83      6804934.87
      2732021.76      6804844.04
#Sta/Elev= 30
  4672.6  386.62  4711.5  385.32  4731.4  383.05  4750.6  381.83  4762.4  379.40
  4793.3  376.42  4824.8  374.67  4870.9  373.79  4952.0  372.19  5007.5  372.88
  5025.6  372.11  5030.8  368.64  5034.7  368.57  5034.9  368.07  5038.4  368.07
  5038.7  368.57  5047.2  372.19  5057.0  374.24  5062.3  372.95  5068.3  376.04
  5112.9  378.87  5163.4  381.51  5187.9  384.21  5195.0  383.93  5218.2  385.95
  5250.7  389.48  5258.4  390.86  5276.9  391.53  5282.1  390.45  5285.6  391.00
#Mann=8,-1,0
  4672.6    0.16       0  4711.5    0.05       0  4870.9    0.16       0
  5007.5   0.035       0  5034.7    0.07       0  5038.7   0.035       0
  5112.9    0.12       0  5218.2    0.05       0
Bank Sta=5034.7,5038.7
Exp/Cntr=0.3,0.1

Type RM Length L Ch R = 1,1090,167,167,167
BEGIN DESCRIPTION:
South Twin Creek Trib H11090.43
END DESCRIPTION:
XS GIS Cut Line= 3
      2731464.17      6805211.65      2731809.02      6805089.86
      2732059.84      6804975.45
#Sta/Elev= 30
  4637.7  385.86  4733.6  381.19  4742.6  381.31  4788.1  377.93  4819.9  377.03
  4841.1  374.43  4861.0  373.86  4866.3  371.43  4873.0  370.63  4904.8  371.40
  4936.6  370.67  4959.0  371.36  4979.0  371.08  5003.4  368.50  5007.2  366.42
  5007.4  365.92  5011.2  366.42  5014.7  370.91  5053.0  370.05  5077.0  369.46
  5089.3  371.34  5099.0  375.73  5112.3  377.75  5119.1  378.07  5163.0  382.12
  5181.4  383.53  5187.0  384.82  5210.0  387.31  5250.5  394.14  5279.1  398.03
#Mann=7,-1,0
  4637.7    0.16       0  4733.6    0.12       0  5007.2    0.07       0
  5011.2    0.12       0  5053.0   0.035       0  5119.1    0.12       0
  5163.0    0.05       0
Bank Sta=5007.2,5011.2
Exp/Cntr=0.3,0.1

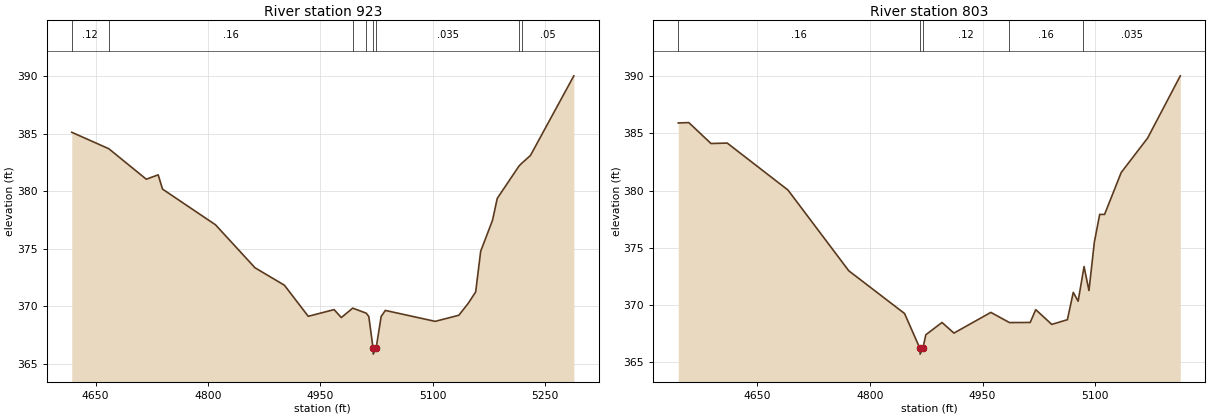
Type RM Length L Ch R = 1,923,120,120,120
BEGIN DESCRIPTION:
South Twin Creek Trib H1923.36
END DESCRIPTION:
XS GIS Cut Line= 3
      2731504.40      6805390.79      2731853.45      6805243.16
      2732112.45      6805109.37
#Sta/Elev= 30
  4618.2  385.13  4667.7  383.70  4717.7  381.05  4733.6  381.43  4739.4  380.19
  4810.1  377.09  4862.9  373.35  4902.2  371.83  4934.0  369.13  4968.5  369.71
  4978.2  369.02  4993.4  369.84  5011.5  369.40  5014.9  369.11  5020.6  366.34
  5020.8  365.84  5024.6  366.34  5031.4  369.12  5037.0  369.64  5103.5  368.69
  5135.1  369.22  5147.8  370.27  5157.6  371.25  5164.3  374.79  5180.1  377.48
  5186.4  379.38  5215.5  382.20  5218.8  382.42  5230.7  383.11  5288.7  390.04
#Mann=8,-1,0
  4618.2    0.12       0  4667.7    0.16       0  4993.4    0.12       0
  5011.5   0.035       0  5020.6    0.07       0  5024.6   0.035       0
  5215.5    0.12       0  5218.8    0.05       0
Bank Sta=5020.6,5024.6
Exp/Cntr=0.3,0.1

Type RM Length L Ch R = 1,803,0,0,0
BEGIN DESCRIPTION:
South Twin Creek Trib H1802.846
END DESCRIPTION:
XS GIS Cut Line= 3
      2731563.71      6805517.81      2731959.94      6805293.95
      2732124.12      6805157.94
#Sta/Elev= 30
  4544.9  385.92  4559.0  385.95  4588.5  384.12  4610.1  384.16  4691.0  380.05
  4771.9  372.99  4846.2  369.25  4866.6  366.20  4866.9  365.70  4870.6  366.20
  4874.4  367.39  4896.0  368.47  4911.9  367.54  4961.0  369.35  4985.8  368.46
  5013.4  368.47  5020.8  369.59  5042.1  368.30  5062.9  368.71  5070.7  371.10
  5077.2  370.33  5084.0  372.94  5085.1  373.36  5091.6  371.26  5098.8  375.50
  5105.9  377.92  5112.4  377.92  5134.5  381.58  5169.7  384.60  5213.2  390.04
#Mann=5,-1,0
  4544.9    0.16       0  4866.6    0.07       0  4870.6    0.12       0
  4985.8    0.16       0  5084.0   0.035       0
Bank Sta=4866.6,4870.6
Exp/Cntr=0.3,0.1

Chan Stop Cuts=-1