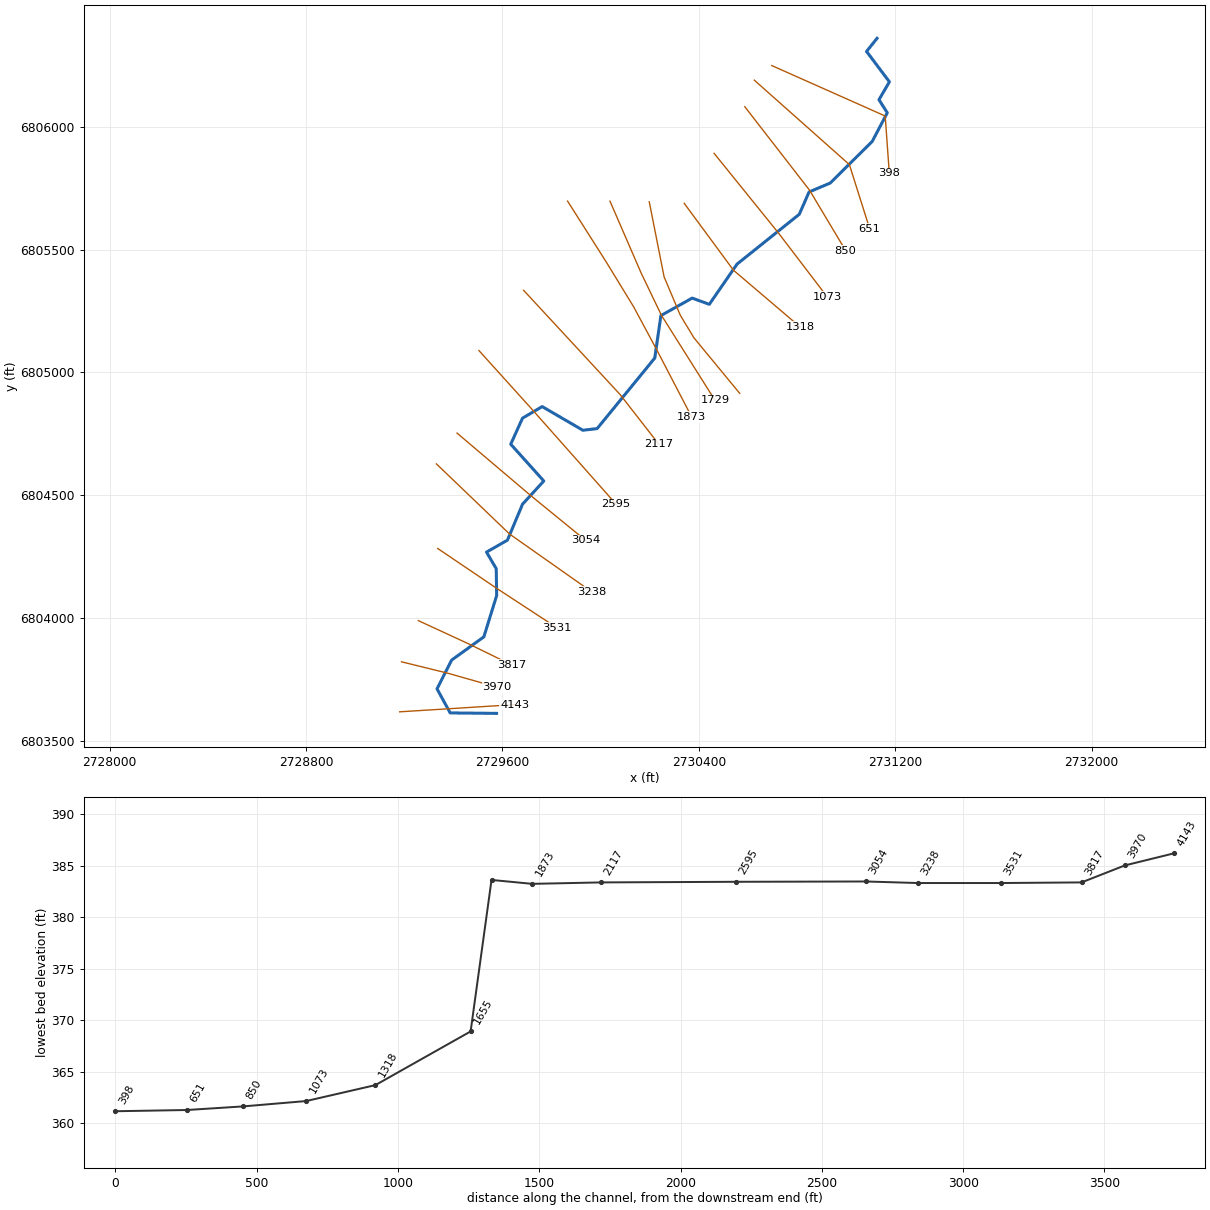
--- South Twin Creek Trib H3.prj (project) ---

Proj Title=South Twin Creek Trib H3 Base Level Engineering
Current Plan=p01
Default Exp/Contr=0.3,0.1
English Units
Geom File=g01
Flow File=f01
Plan File=p01
BEGIN DESCRIPTION:
South Twin Creek Trib H3
END DESCRIPTION:

--- South Twin Creek Trib H3.p01 (plan) ---

Plan Title=Multiple Run
Short Identifier=Multiple
Geom File=g01
Flow File=f01
Subcritical Flow
K Sum by GR= 0
Std Step Tol= 0.01
Critical Tol= 0.01
Num of Std Step Trials= 20
Max Error Tol= 0.3
Flow Tol Ratio= 0.001
Split Flow NTrial= 30
Split Flow Tol= 0.02
Split Flow Ratio= 0.02
Log Output Level= 0
Friction Slope Method= 1
Unsteady Friction Slope Method= 2
Unsteady Bridges Friction Slope Method= 1
Parabolic Critical Depth
Global Vel Dist=  1 , 1 , 1
Global Log Level= 0
CheckData=True
Encroach Param= -1, 0, 0, 0
BEGIN DESCRIPTION:
Multiple Run
END DESCRIPTION:

--- South Twin Creek Trib H3.f01 (steady flow) ---

Flow Title=Multiple
Number of Profiles=7
Profile Names=10-year,25-year,50-year,1pct_min,100-year,1pct_plu,500-year
River Rch & RM= South Twin Creek,Reach-1,4143
     394     514     609     359     716    1428     987
Boundary for River Rch & Prof#=South Twin Creek,Reach-1,1
Up Type=0
Dn Type=3
Dn Slope=0.005
Boundary for River Rch & Prof#=South Twin Creek,Reach-1,2
Up Type=0
Dn Type=3
Dn Slope=0.005
Boundary for River Rch & Prof#=South Twin Creek,Reach-1,3
Up Type=0
Dn Type=3
Dn Slope=0.005
Boundary for River Rch & Prof#=South Twin Creek,Reach-1,4
Up Type=0
Dn Type=3
Dn Slope=0.005
Boundary for River Rch & Prof#=South Twin Creek,Reach-1,5
Up Type=0
Dn Type=3
Dn Slope=0.005
Boundary for River Rch & Prof#=South Twin Creek,Reach-1,6
Up Type=0
Dn Type=3
Dn Slope=0.005
Boundary for River Rch & Prof#=South Twin Creek,Reach-1,7
Up Type=0
Dn Type=3
Dn Slope=0.005

--- South Twin Creek Trib H3.g01 (geometry) ---

Geom Title=Existing Conditions

River Reach=South Twin Creek,Reach-1
Reach XY= 30
      2729576.00      6803611.00      2729387.09      6803612.83
      2729333.48      6803710.97      2729392.62      6803827.70
      2729524.26      6803922.87      2729576.39      6804090.87
      2729574.62      6804200.57      2729535.06      6804268.00
      2729620.34      6804316.61      2729681.86      6804463.30
      2729768.40      6804557.67      2729633.77      6804707.59
      2729681.70      6804813.61      2729761.83      6804860.85
      2729927.74      6804764.31      2729985.70      6804771.18
      2730220.53      6805058.55      2730245.45      6805231.56
      2730372.77      6805302.75      2730442.70      6805277.37
      2730555.61      6805441.16      2730809.36      6805644.30
      2730848.86      6805734.84      2730935.66      6805771.79
      2731106.23      6805940.91      2731167.76      6806057.77
      2731133.83      6806110.92      2731176.36      6806183.80
      2731083.27      6806307.67      2731126.00      6806361.00

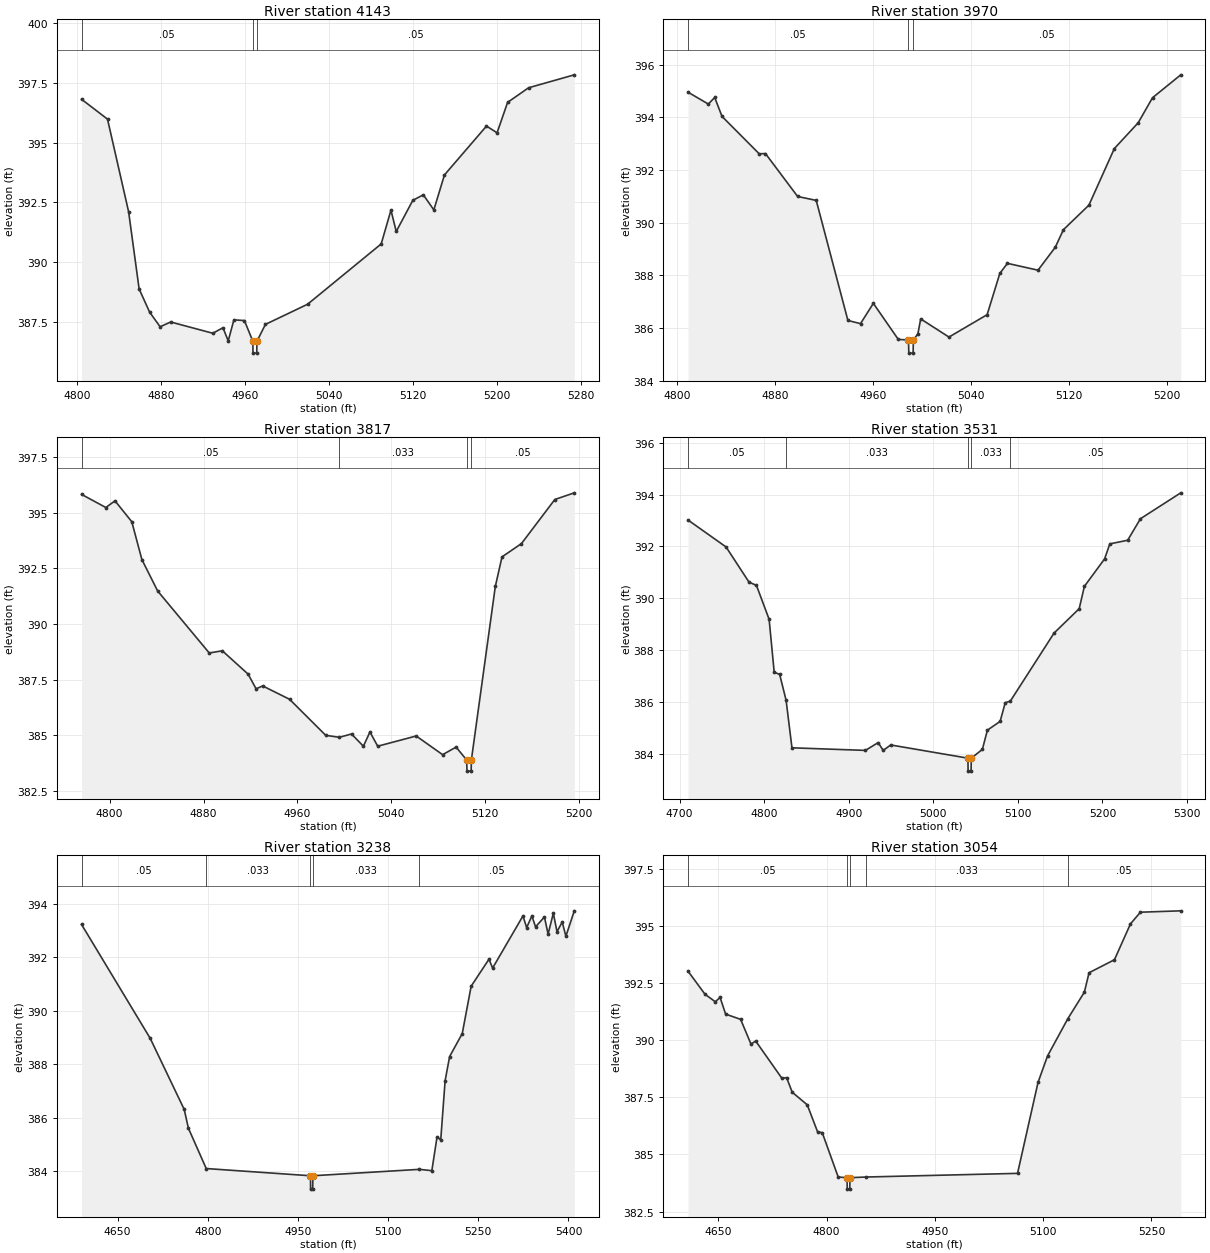
Type RM Length L Ch R = 1,4143,173,173,173
BEGIN DESCRIPTION:
South Twin Creek Trib H34143.016
END DESCRIPTION:
XS GIS Cut Line= 3
      2729181.32      6803617.35      2729376.45      6803629.50
      2729649.40      6803646.72
#Sta/Elev= 30
  4804.5  396.81  4829.2  395.98  4849.3  392.11  4859.3  388.89  4869.3  387.92
  4879.3  387.31  4889.3  387.51  4929.4  387.04  4939.1  387.27  4944.1  386.72
  4949.5  387.60  4959.5  387.57  4967.5  386.71  4967.7  386.21  4971.2  386.21
  4971.5  386.71  4979.5  387.41  5019.6  388.25  5089.7  390.77  5099.0  392.18
  5104.0  391.29  5119.8  392.59  5129.8  392.82  5139.8  392.19  5149.9  393.65
  5189.9  395.69  5200.0  395.41  5210.0  396.68  5230.0  397.29  5273.5  397.83
#Mann=3,-1,0
  4804.5    0.05       0  4967.5    0.05       0  4971.5    0.05       0
Bank Sta=4967.5,4971.5
Exp/Cntr=0.3,0.1

Type RM Length L Ch R = 1,3970,153,153,153
BEGIN DESCRIPTION:
South Twin Creek Trib H33969.87
END DESCRIPTION:
XS GIS Cut Line= 3
      2729189.04      6803821.00      2729375.44      6803775.15
      2729578.27      6803717.57
#Sta/Elev= 30
  4808.8  394.95  4825.4  394.50  4830.6  394.75  4836.6  394.03  4867.0  392.61
  4872.1  392.62  4898.4  390.99  4913.6  390.84  4939.5  386.28  4949.8  386.16
  4960.3  386.93  4980.7  385.56  4989.0  385.54  4989.3  385.04  4992.8  385.04
  4993.0  385.54  4996.7  385.77  4999.0  386.34  5022.1  385.65  5053.3  386.50
  5063.7  388.07  5069.9  388.45  5094.9  388.19  5109.0  389.06  5115.7  389.73
  5136.5  390.66  5157.3  392.81  5176.8  393.79  5188.5  394.74  5211.6  395.61
#Mann=3,-1,0
  4808.8    0.05       0  4989.0    0.05       0  4993.0    0.05       0
Bank Sta=4989,4993
Exp/Cntr=0.3,0.1

Type RM Length L Ch R = 1,3817,286,286,286
BEGIN DESCRIPTION:
South Twin Creek Trib H33817.26
END DESCRIPTION:
XS GIS Cut Line= 3
      2729257.16      6803988.86      2729460.88      6803894.91
      2729636.44      6803808.98
#Sta/Elev= 30
  4776.1  395.83  4796.8  395.24  4804.6  395.54  4818.9  394.60  4827.5  392.90
  4840.9  391.49  4884.9  388.70  4896.0  388.80  4918.0  387.75  4924.8  387.09
  4930.4  387.22  4953.3  386.62  4984.1  385.00  4995.7  384.91  5006.1  385.06
  5016.2  384.51  5021.8  385.15  5028.4  384.51  5061.2  384.97  5083.7  384.13
  5095.2  384.47  5104.2  383.89  5104.5  383.39  5108.0  383.39  5108.2  383.89
  5128.6  391.69  5134.3  393.02  5150.9  393.62  5179.3  395.60  5195.9  395.90
#Mann=4,-1,0
  4776.1    0.05       0  4995.7   0.033       0  5104.2   0.033       0
  5108.2    0.05       0
Bank Sta=5104.2,5108.2
Exp/Cntr=0.3,0.1

Type RM Length L Ch R = 1,3531,293,293,293
BEGIN DESCRIPTION:
South Twin Creek Trib H33530.7
END DESCRIPTION:
XS GIS Cut Line= 3
      2729336.18      6804282.83      2729573.78      6804122.15
      2729821.40      6803960.20
#Sta/Elev= 30
  4710.0  393.02  4755.0  391.98  4782.2  390.62  4790.9  390.50  4805.9  389.19
  4811.9  387.15  4818.4  387.06  4826.0  386.06  4832.9  384.23  4919.8  384.13
  4934.8  384.43  4940.8  384.13  4949.7  384.34  5041.0  383.83  5041.2  383.33
  5044.7  383.33  5045.0  383.83  5058.1  384.17  5064.0  384.91  5079.1  385.25
  5085.1  385.97  5091.1  386.03  5142.9  388.66  5172.6  389.60  5178.7  390.46
  5202.6  391.52  5208.8  392.10  5229.9  392.24  5245.0  393.07  5292.7  394.07
#Mann=5,-1,0
  4710.0    0.05       0  4826.0   0.033       0  5041.0   0.033       0
  5045.0   0.033       0  5091.1    0.05       0
Bank Sta=5041,5045
Exp/Cntr=0.3,0.1

Type RM Length L Ch R = 1,3238,184,184,184
BEGIN DESCRIPTION:
South Twin Creek Trib H33237.85
END DESCRIPTION:
XS GIS Cut Line= 3
      2729331.02      6804627.35      2729628.94      6804341.65
      2729961.74      6804107.49
#Sta/Elev= 30
  4590.0  393.23  4704.2  388.97  4760.8  386.31  4767.7  385.61  4797.4  384.10
  4970.8  383.83  4971.0  383.33  4974.5  383.33  4974.8  383.83  5152.0  384.07
  5172.7  384.02  5181.4  385.29  5187.5  385.17  5194.8  387.39  5202.3  388.29
  5223.3  389.15  5238.1  390.92  5267.7  391.93  5273.8  391.60  5324.3  393.55
  5330.4  393.11  5339.1  393.55  5345.2  393.14  5360.0  393.51  5366.1  392.87
  5374.8  393.65  5380.9  392.96  5389.6  393.32  5395.7  392.79  5409.7  393.74
#Mann=5,-1,0
  4590.0    0.05       0  4797.4   0.033       0  4970.8   0.033       0
  4974.8   0.033       0  5152.0    0.05       0
Bank Sta=4970.8,4974.8
Exp/Cntr=0.3,0.1

Type RM Length L Ch R = 1,3054,459,459,459
BEGIN DESCRIPTION:
South Twin Creek Trib H33053.51
END DESCRIPTION:
XS GIS Cut Line= 3
      2729414.98      6804752.83      2729715.07      6804498.38
      2729939.28      6804315.47
#Sta/Elev= 30
  4607.9  393.02  4631.4  392.01  4645.7  391.68  4652.3  391.87  4660.0  391.14
  4680.8  390.91  4695.1  389.83  4701.7  389.96  4738.0  388.33  4744.5  388.36
  4752.3  387.72  4773.1  387.17  4787.4  385.99  4793.9  385.95  4816.0  384.01
  4828.3  383.98  4828.5  383.48  4832.0  383.48  4832.3  383.98  4854.5  384.01
  5064.5  384.17  5092.9  388.15  5106.1  389.31  5134.2  390.94  5157.1  392.10
  5163.6  392.95  5198.8  393.52  5221.0  395.09  5234.8  395.60  5290.7  395.66
#Mann=5,-1,0
  4607.9    0.05       0  4828.3   0.033       0  4832.3    0.05       0
  4854.5   0.033       0  5134.2    0.05       0
Bank Sta=4828.3,4832.3
Exp/Cntr=0.3,0.1

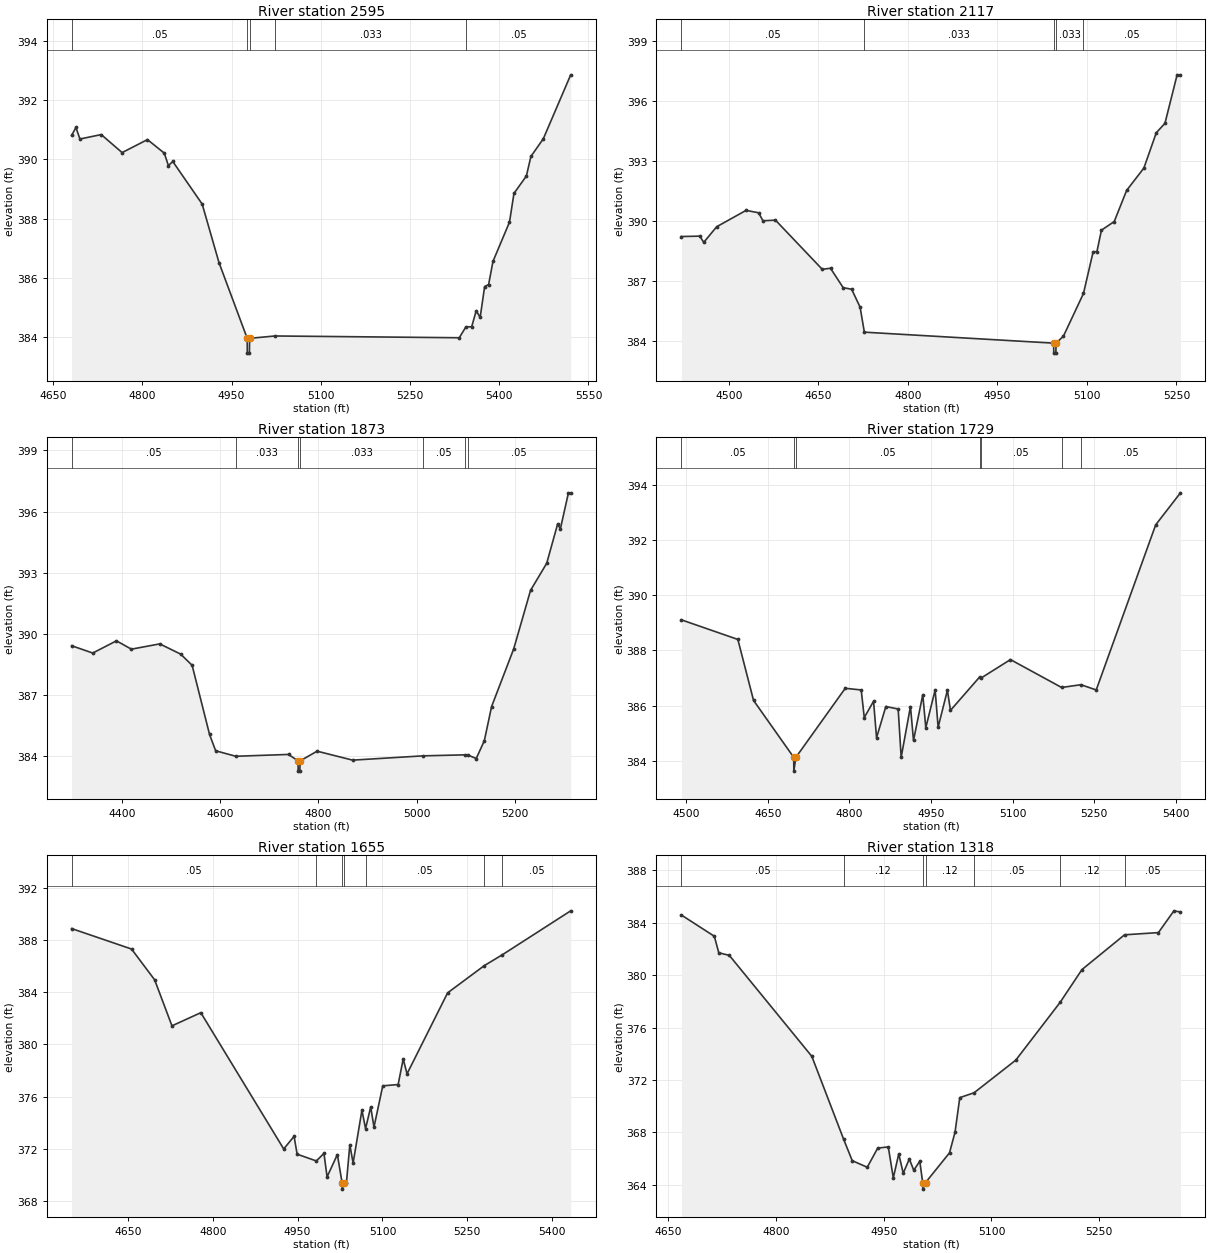
Type RM Length L Ch R = 1,2595,478,478,478
BEGIN DESCRIPTION:
South Twin Creek Trib H32595
END DESCRIPTION:
XS GIS Cut Line= 3
      2729504.16      6805089.14      2729715.53      6804855.14
      2730063.00      6804463.22
#Sta/Elev= 30
  4681.0  390.81  4688.2  391.08  4695.0  390.69  4730.8  390.84  4765.9  390.23
  4808.5  390.67  4836.9  390.21  4843.7  389.79  4851.1  389.93  4900.5  388.49
  4928.8  386.51  4976.2  383.95  4976.4  383.45  4979.9  383.45  4980.2  383.95
  5023.0  384.03  5332.7  383.97  5344.0  384.34  5353.6  384.34  5361.2  384.88
  5367.9  384.66  5375.4  385.70  5382.1  385.77  5389.4  386.55  5417.2  387.88
  5424.7  388.85  5445.6  389.44  5453.2  390.10  5474.1  390.70  5520.1  392.86
#Mann=5,-1,0
  4681.0    0.05       0  4976.2    0.05       0  4980.2    0.05       0
  5023.0   0.033       0  5344.0    0.05       0
Bank Sta=4976.2,4980.2
Exp/Cntr=0.3,0.1

Type RM Length L Ch R = 1,2117,244,244,244
BEGIN DESCRIPTION:
South Twin Creek Trib H32117.15
END DESCRIPTION:
XS GIS Cut Line= 3
      2729686.31      6805334.40      2730078.61      6804910.69
      2730237.84      6804706.59
#Sta/Elev= 30
  4420.5  389.23  4451.2  389.25  4458.0  388.94  4479.6  389.72  4528.9  390.54
  4549.9  390.42  4557.2  390.02  4578.2  390.05  4656.5  387.59  4670.4  387.64
  4691.6  386.67  4705.8  386.59  4720.0  385.69  4727.1  384.44  5044.3  383.89
  5044.5  383.39  5048.0  383.39  5048.3  383.89  5060.7  384.24  5094.3  386.38
  5110.5  388.47  5116.8  388.47  5124.4  389.55  5145.8  389.98  5166.6  391.54
  5195.5  392.66  5216.3  394.43  5230.8  394.90  5251.2  397.33  5256.8  397.33
#Mann=5,-1,0
  4420.5    0.05       0  4727.1   0.033       0  5044.3   0.033       0
  5048.3   0.033       0  5094.3    0.05       0
Bank Sta=5044.3,5048.3
Exp/Cntr=0.3,0.1

Type RM Length L Ch R = 1,1873,144,144,144
BEGIN DESCRIPTION:
South Twin Creek Trib H31872.91
END DESCRIPTION:
XS GIS Cut Line= 5
      2729865.26      6805697.99      2730023.71      6805448.42
      2730134.59      6805267.02      2730228.78      6805091.72
      2730371.14      6804818.18
#Sta/Elev= 30
  4297.7  389.41  4340.7  389.05  4388.9  389.65  4419.4  389.24  4477.0  389.50
  4519.4  389.00  4542.9  388.45  4578.4  385.05  4590.8  384.25  4631.7  383.98
  4739.2  384.07  4758.5  383.75  4758.7  383.25  4762.2  383.25  4762.5  383.75
  4797.2  384.23  4869.5  383.79  5012.5  384.00  5098.7  384.05  5104.1  384.04
  5121.1  383.87  5137.5  384.74  5152.3  386.42  5197.4  389.26  5231.6  392.13
  5264.5  393.46  5286.6  395.38  5292.3  395.15  5308.7  396.92  5313.3  396.92
#Mann=7,-1,0
  4297.7    0.05       0  4631.7   0.033       0  4758.5   0.033       0
  4762.5   0.033       0  5012.5    0.05       0  5098.7   0.033       0
  5104.1    0.05       0
Bank Sta=4758.5,4762.5
Exp/Cntr=0.3,0.1

Type RM Length L Ch R = 1,1729,74,74,74
BEGIN DESCRIPTION:
South Twin Creek Trib H31729.03
END DESCRIPTION:
XS GIS Cut Line= 4
      2730038.09      6805697.66      2730164.41      6805406.26
      2730247.53      6805232.87      2730465.21      6804887.30
#Sta/Elev= 30
  4490.7  389.11  4594.6  388.40  4623.5  386.19  4697.4  384.13  4697.6  383.63
  4701.4  384.13  4792.2  386.63  4821.6  386.57  4827.2  385.57  4844.3  386.16
  4849.8  384.84  4866.9  385.97  4889.6  385.88  4895.1  384.13  4912.2  385.97
  4917.8  384.74  4934.9  386.40  4940.4  385.20  4957.6  386.57  4963.1  385.22
  4980.2  386.56  4985.8  385.83  5039.5  387.04  5041.2  386.99  5096.2  387.67
  5190.3  386.66  5225.9  386.76  5254.0  386.57  5363.4  392.55  5409.0  393.71
#Mann=7,-1,0
  4490.7    0.05       0  4697.4    0.05       0  4701.4    0.05       0
  5039.5    0.07       0  5041.2    0.05       0  5190.3   0.033       0
  5225.9    0.05       0
Bank Sta=4697.4,4701.4
Exp/Cntr=0.3,0.1

Type RM Length L Ch R = 1,1655,337,337,337
BEGIN DESCRIPTION:
South Twin Creek Trib H31655.2
END DESCRIPTION:
XS GIS Cut Line= 5
      2730198.08      6805694.93      2730258.57      6805388.99
      2730324.75      6805232.52      2730380.21      6805140.74
      2730566.54      6804914.73
#Sta/Elev= 30
  4550.7  388.88  4656.6  387.31  4697.4  384.95  4728.0  381.42  4779.0  382.43
  4925.5  371.98  4943.8  372.95  4949.2  371.58  4983.1  371.06  4996.6  371.64
  5002.1  369.84  5020.3  371.55  5028.6  369.40  5028.8  368.90  5032.6  369.40
  5036.3  369.40  5042.3  372.30  5048.1  370.90  5063.7  374.95  5070.1  373.54
  5079.2  375.20  5085.0  373.66  5100.5  376.82  5127.7  376.92  5136.6  378.88
  5143.4  377.74  5215.1  383.95  5280.0  386.04  5311.8  386.87  5432.6  390.24
#Mann=7,-1,0
  4550.7    0.05       0  4983.1    0.07       0  5028.6    0.07       0
  5032.6    0.07       0  5070.1    0.05       0  5280.0    0.07       0
  5311.8    0.05       0
Bank Sta=5028.6,5032.6
Exp/Cntr=0.3,0.1

Type RM Length L Ch R = 1,1318,245,245,245
BEGIN DESCRIPTION:
South Twin Creek Trib H31317.95
END DESCRIPTION:
XS GIS Cut Line= 3
      2730340.61      6805688.70      2730541.13      6805416.33
      2730812.92      6805184.90
#Sta/Elev= 30
  4668.1  384.59  4714.0  382.97  4720.2  381.71  4734.9  381.51  4849.8  373.81
  4894.0  367.50  4906.1  365.85  4927.0  365.35  4941.6  366.81  4956.3  366.90
  4963.3  364.54  4970.9  366.37  4977.1  364.89  4985.6  365.98  4991.8  365.12
  5000.2  365.81  5004.2  364.18  5004.5  363.68  5008.2  364.18  5041.6  366.45
  5049.3  368.03  5055.9  370.66  5075.8  371.03  5133.9  373.52  5195.7  377.93
  5226.1  380.43  5285.4  383.08  5332.6  383.25  5354.2  384.91  5363.3  384.82
#Mann=7,-1,0
  4668.1    0.05       0  4894.0    0.12       0  5004.2    0.07       0
  5008.2    0.12       0  5075.8    0.05       0  5195.7    0.12       0
  5285.4    0.05       0
Bank Sta=5004.2,5008.2
Exp/Cntr=0.3,0.1

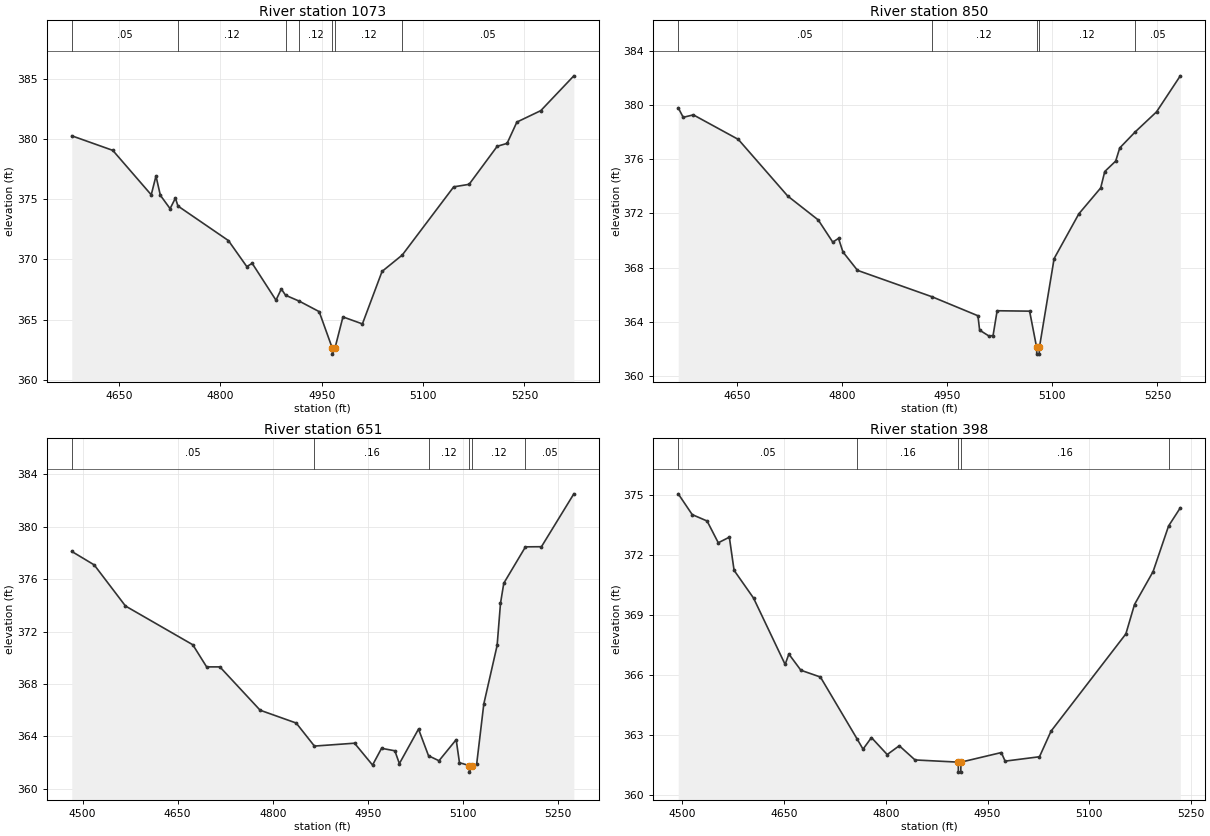
Type RM Length L Ch R = 1,1073,223,223,223
BEGIN DESCRIPTION:
South Twin Creek Trib H31072.88
END DESCRIPTION:
XS GIS Cut Line= 3
      2730462.28      6805892.47      2730725.85      6805566.14
      2730922.07      6805308.91
#Sta/Elev= 30
  4580.1  380.26  4640.8  379.05  4697.7  375.36  4704.7  376.92  4711.2  375.32
  4725.6  374.21  4733.5  375.09  4737.2  374.43  4811.9  371.56  4839.1  369.40
  4847.1  369.67  4882.3  366.61  4890.2  367.54  4896.5  367.02  4917.1  366.52
  4946.2  365.66  4965.6  362.63  4965.9  362.13  4969.6  362.63  4981.4  365.22
  5010.2  364.64  5039.3  369.00  5069.2  370.36  5145.3  376.02  5168.1  376.23
  5209.7  379.39  5224.3  379.63  5238.8  381.40  5274.2  382.35  5323.1  385.24
#Mann=7,-1,0
  4580.1    0.05       0  4737.2    0.12       0  4896.5    0.05       0
  4917.1    0.12       0  4965.6    0.07       0  4969.6    0.12       0
  5069.2    0.05       0
Bank Sta=4965.6,4969.6
Exp/Cntr=0.3,0.1

Type RM Length L Ch R = 1,850,199,199,199
BEGIN DESCRIPTION:
South Twin Creek Trib H3850.29
END DESCRIPTION:
XS GIS Cut Line= 3
      2730587.27      6806082.39      2730851.13      6805742.26
      2730998.11      6805496.31
#Sta/Elev= 30
  4565.7  379.78  4572.8  379.08  4587.3  379.26  4651.5  377.45  4722.1  373.27
  4765.6  371.51  4786.4  369.87  4794.6  370.15  4800.9  369.15  4821.7  367.79
  4928.2  365.84  4993.7  364.44  4996.1  363.38  5009.3  362.95  5015.3  362.98
  5021.1  364.81  5067.5  364.78  5077.5  362.11  5077.7  361.61  5081.2  361.61
  5081.5  362.11  5102.5  368.66  5137.8  371.96  5169.0  373.87  5174.8  375.08
  5190.4  375.85  5196.2  376.82  5218.4  378.01  5248.7  379.48  5282.7  382.14
#Mann=5,-1,0
  4565.7    0.05       0  4928.2    0.12       0  5077.5    0.07       0
  5081.5    0.12       0  5218.4    0.05       0
Bank Sta=5077.5,5081.5
Exp/Cntr=0.3,0.1

Type RM Length L Ch R = 1,651,253,253,253
BEGIN DESCRIPTION:
South Twin Creek Trib H3651.01
END DESCRIPTION:
XS GIS Cut Line= 3
      2730625.88      6806190.70      2731013.40      6805846.52
      2731095.88      6805585.64
#Sta/Elev= 30
  4483.0  378.12  4518.4  377.09  4567.7  373.95  4673.9  370.99  4695.7  369.30
  4716.6  369.30  4780.1  365.99  4837.0  365.01  4865.7  363.25  4929.0  363.47
  4957.4  361.80  4971.6  363.08  4992.6  362.89  4999.7  361.91  5029.9  364.55
  5045.7  362.51  5062.2  362.13  5089.3  363.74  5094.5  361.98  5110.0  361.76
  5110.2  361.26  5114.0  361.76  5121.6  361.86  5132.9  366.47  5153.9  370.94
  5159.2  374.15  5164.4  375.69  5198.6  378.47  5223.8  378.48  5274.9  382.52
#Mann=6,-1,0
  4483.0    0.05       0  4865.7    0.16       0  5045.7    0.12       0
  5110.0    0.07       0  5114.0    0.12       0  5198.6    0.05       0
Bank Sta=5110,5114
Exp/Cntr=0.3,0.1

Type RM Length L Ch R = 1,398,0,0,0
BEGIN DESCRIPTION:
South Twin Creek Trib H3398.245
END DESCRIPTION:
XS GIS Cut Line= 3
      2730697.21      6806250.08      2731159.24      6806044.49
      2731176.00      6805810.99
#Sta/Elev= 30
  4494.3  375.07  4514.9  374.03  4536.8  373.71  4553.3  372.62  4569.6  372.90
  4576.6  371.24  4605.3  369.85  4651.8  366.53  4657.3  367.05  4675.0  366.24
  4703.8  365.90  4757.7  362.81  4766.6  362.29  4779.0  362.87  4802.2  362.02
  4820.0  362.46  4843.2  361.75  4906.9  361.64  4907.1  361.14  4910.6  361.14
  4910.9  361.64  4970.4  362.12  4975.9  361.69  5026.6  361.91  5043.6  363.19
  5153.9  368.06  5166.6  369.53  5194.0  371.18  5216.8  373.46  5234.1  374.37
#Mann=5,-1,0
  4494.3    0.05       0  4757.7    0.16       0  4906.9    0.07       0
  4910.9    0.16       0  5216.8    0.05       0
Bank Sta=4906.9,4910.9
Exp/Cntr=0.3,0.1

Chan Stop Cuts=-1