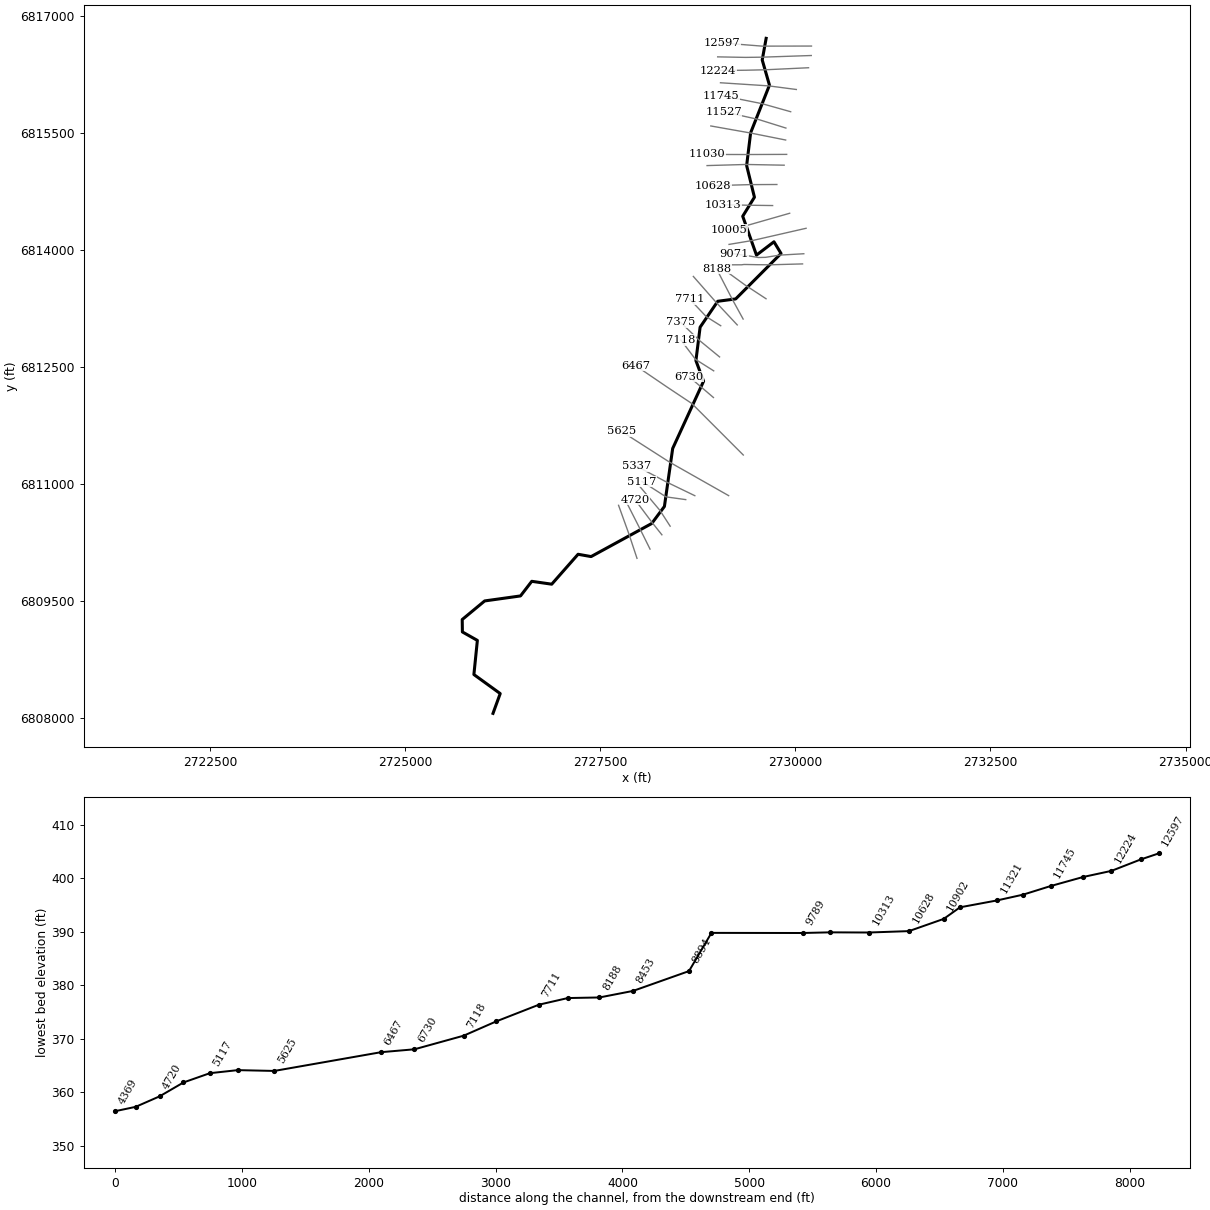
--- South Twin Creek Trib I.prj (project) ---

Proj Title=South Twin Creek Trib I Base Level Engineering
Current Plan=p01
Default Exp/Contr=0.3,0.1
English Units
Geom File=g01
Flow File=f01
Plan File=p01
BEGIN DESCRIPTION:
South Twin Creek Trib I
END DESCRIPTION:

--- South Twin Creek Trib I.p01 (plan) ---

Plan Title=Multiple Run
Short Identifier=Multiple
Geom File=g01
Flow File=f01
Subcritical Flow
K Sum by GR= 0
Std Step Tol= 0.01
Critical Tol= 0.01
Num of Std Step Trials= 20
Max Error Tol= 0.3
Flow Tol Ratio= 0.001
Split Flow NTrial= 30
Split Flow Tol= 0.02
Split Flow Ratio= 0.02
Log Output Level= 0
Friction Slope Method= 1
Unsteady Friction Slope Method= 2
Unsteady Bridges Friction Slope Method= 1
Parabolic Critical Depth
Global Vel Dist=  1 , 1 , 1
Global Log Level= 0
CheckData=True
Encroach Param= -1, 0, 0, 0
BEGIN DESCRIPTION:
Multiple Run
END DESCRIPTION:

--- South Twin Creek Trib I.f01 (steady flow) ---

Flow Title=Multiple
Number of Profiles=7
Profile Names=10-year,25-year,50-year,1pct_min,100-year,1pct_plu,500-year
River Rch & RM= South Twin Creek,Reach-1,12597
     306     391     455     264     527    1051     702
River Rch & RM= South Twin Creek,Reach-1,6467
     510     672     801     473     944    1884    1311
River Rch & RM= South Twin Creek,Reach-1,1698
     866    1182    1440     870    1736    3463    2519
Boundary for River Rch & Prof#=South Twin Creek,Reach-1,1
Up Type=0
Dn Type=3
Dn Slope=0.005
Boundary for River Rch & Prof#=South Twin Creek,Reach-1,2
Up Type=0
Dn Type=3
Dn Slope=0.005
Boundary for River Rch & Prof#=South Twin Creek,Reach-1,3
Up Type=0
Dn Type=3
Dn Slope=0.005
Boundary for River Rch & Prof#=South Twin Creek,Reach-1,4
Up Type=0
Dn Type=3
Dn Slope=0.005
Boundary for River Rch & Prof#=South Twin Creek,Reach-1,5
Up Type=0
Dn Type=3
Dn Slope=0.005
Boundary for River Rch & Prof#=South Twin Creek,Reach-1,6
Up Type=0
Dn Type=3
Dn Slope=0.005
Boundary for River Rch & Prof#=South Twin Creek,Reach-1,7
Up Type=0
Dn Type=3
Dn Slope=0.005

--- South Twin Creek Trib I.g01 (geometry) ---

Geom Title=Existing Conditions

River Reach=South Twin Creek,Reach-1
Reach XY= 30
      2729626.00      6816711.00      2729575.83      6816433.68
      2729668.47      6816110.99      2729427.20      6815500.50
      2729376.07      6815081.03      2729475.90      6814675.04
      2729325.79      6814431.06      2729502.17      6813933.18
      2729726.22      6814104.02      2729816.89      6813954.27
      2729235.70      6813371.75      2729005.93      6813341.72
      2728779.75      6813009.45      2728726.07      6812581.03
      2728824.20      6812317.11      2728428.36      6811455.48
      2728322.39      6810712.50      2728159.54      6810493.87
      2727382.93      6810070.22      2727216.00      6810099.77
      2726878.47      6809716.45      2726622.57      6809753.21
      2726478.54      6809566.01      2726019.27      6809501.86
      2725731.45      6809263.45      2725733.69      6809104.52
      2725925.56      6808996.13      2725881.09      6808558.70
      2726218.31      6808314.67      2726126.00      6808061.00

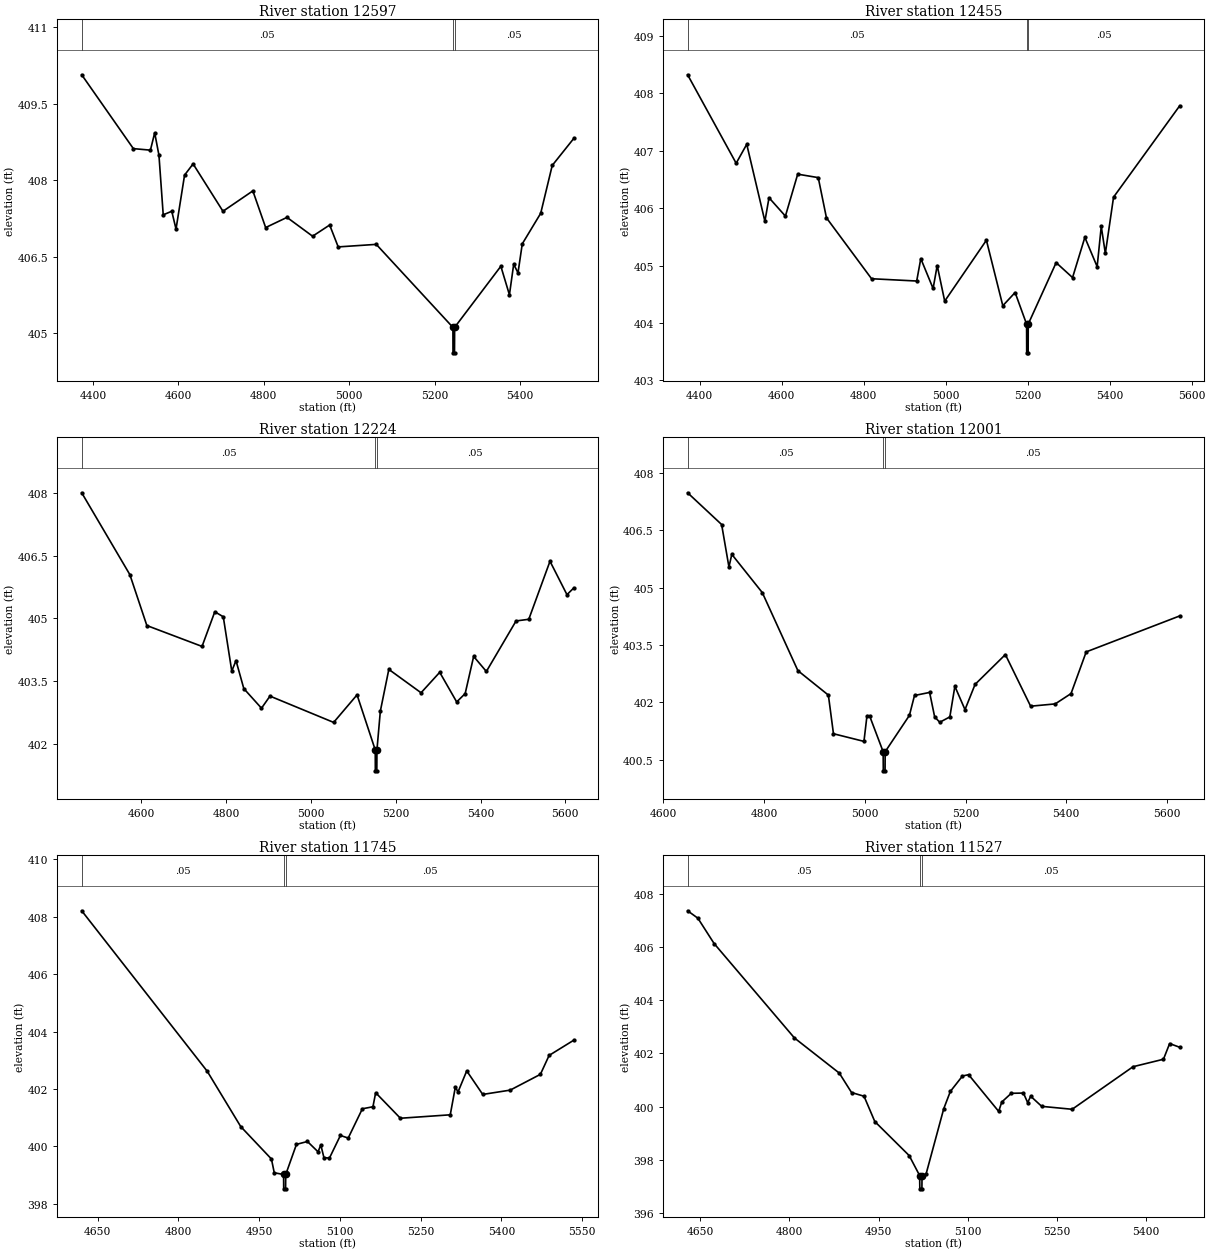
Type RM Length L Ch R = 1,12597,142,142,142
BEGIN DESCRIPTION:
South Twin Creek Trib I12596.857
END DESCRIPTION:
XS GIS Cut Line= 3
      2730207.04      6816612.18      2729576.00      6816611.00
      2729055.68      6816652.27
#Sta/Elev= 30
  4373.3  410.07  4494.3  408.62  4534.3  408.59  4544.3  408.93  4554.3  408.49
  4564.3  407.32  4584.3  407.39  4594.3  407.04  4614.3  408.10  4634.3  408.32
  4704.3  407.39  4774.3  407.79  4804.3  407.07  4854.3  407.27  4914.3  406.90
  4954.3  407.12  4974.3  406.69  5063.5  406.74  5243.1  405.11  5243.3  404.61
  5246.8  404.61  5247.1  405.11  5355.4  406.31  5375.5  405.75  5385.5  406.35
  5395.6  406.18  5405.6  406.75  5448.8  407.35  5475.8  408.29  5526.3  408.82
#Mann=3,-1,0
  4373.3    0.05       0  5243.1    0.05       0  5247.1    0.05       0
Bank Sta=5243.1,5247.1
Exp/Cntr=0.3,0.1

Type RM Length L Ch R = 1,12455,231,231,231
BEGIN DESCRIPTION:
South Twin Creek Trib I12454.89
END DESCRIPTION:
XS GIS Cut Line= 4
      2730204.37      6816490.90      2729574.52      6816469.62
      2729361.41      6816466.78      2729004.71      6816473.57
#Sta/Elev= 30
  4370.8  408.32  4489.2  406.78  4515.0  407.11  4559.3  405.77  4569.3  406.18
  4609.3  405.86  4639.3  406.59  4689.4  406.53  4709.4  405.83  4819.4  404.77
  4929.5  404.73  4939.5  405.12  4969.5  404.60  4979.5  405.00  4997.8  404.38
  5099.5  405.44  5139.5  404.30  5169.5  404.53  5197.5  403.98  5197.8  403.48
  5201.3  403.48  5201.5  403.98  5269.6  405.05  5309.6  404.79  5339.6  405.49
  5369.6  404.98  5379.6  405.68  5389.6  405.21  5409.6  406.19  5570.9  407.78
#Mann=3,-1,0
  4370.8    0.05       0  5197.5    0.05       0  5201.5    0.05       0
Bank Sta=5197.5,5201.5
Exp/Cntr=0.3,0.1

Type RM Length L Ch R = 1,12224,223,223,223
BEGIN DESCRIPTION:
South Twin Creek Trib I12224.225
END DESCRIPTION:
XS GIS Cut Line= 4
      2730169.41      6816334.22      2729624.24      6816308.43
      2729368.94      6816302.44      2729009.91      6816298.34
#Sta/Elev= 30
  4459.7  408.01  4573.2  406.05  4613.3  404.83  4743.4  404.33  4773.5  405.16
  4793.5  405.04  4813.5  403.74  4823.5  403.99  4841.9  403.32  4883.6  402.85
  4903.6  403.14  5053.7  402.51  5108.9  403.17  5151.8  401.85  5152.0  401.35
  5155.5  401.35  5155.8  401.85  5163.8  402.78  5183.8  403.78  5259.8  403.22
  5303.8  403.71  5343.8  403.00  5363.8  403.20  5383.8  404.09  5413.8  403.73
  5483.8  404.94  5513.8  404.98  5563.8  406.37  5603.8  405.57  5619.9  405.73
#Mann=3,-1,0
  4459.7    0.05       0  5151.8    0.05       0  5155.8    0.05       0
Bank Sta=5151.8,5155.8
Exp/Cntr=0.3,0.1

Type RM Length L Ch R = 1,12001,256,256,256
BEGIN DESCRIPTION:
South Twin Creek Trib I12001.13
END DESCRIPTION:
XS GIS Cut Line= 3
      2730012.95      6816055.45      2729659.03      6816101.70
      2729040.85      6816141.73
#Sta/Elev= 30
  4648.6  407.48  4716.1  406.65  4730.6  405.54  4736.3  405.87  4796.8  404.87
  4867.4  402.83  4927.9  402.19  4938.0  401.18  4998.5  400.98  5004.5  401.65
  5009.6  401.65  5036.6  400.71  5036.9  400.21  5040.4  400.21  5040.6  400.71
  5088.7  401.66  5098.8  402.18  5128.8  402.26  5138.8  401.62  5148.9  401.48
  5168.9  401.62  5178.9  402.42  5199.0  401.81  5219.0  402.47  5279.1  403.25
  5329.2  401.90  5378.0  401.96  5409.4  402.23  5439.5  403.32  5625.0  404.26
#Mann=3,-1,0
  4648.6    0.05       0  5036.6    0.05       0  5040.6    0.05       0
Bank Sta=5036.6,5040.6
Exp/Cntr=0.3,0.1

Type RM Length L Ch R = 1,11745,218,218,218
BEGIN DESCRIPTION:
South Twin Creek Trib I11744.82
END DESCRIPTION:
XS GIS Cut Line= 3
      2729940.24      6815770.60      2729573.96      6815873.70
      2729051.04      6815978.34
#Sta/Elev= 30
  4620.5  408.21  4853.5  402.62  4915.8  400.69  4972.8  399.56  4978.1  399.08
  4995.4  399.02  4995.6  398.52  4999.1  398.52  4999.4  399.02  5019.3  400.07
  5039.7  400.17  5059.4  399.81  5064.5  400.05  5070.3  399.61  5080.5  399.59
  5100.9  400.38  5115.4  400.29  5141.7  401.31  5161.3  401.38  5166.4  401.87
  5212.3  400.98  5304.9  401.10  5314.3  402.06  5319.4  401.90  5335.5  402.63
  5365.2  401.81  5416.2  401.96  5472.3  402.51  5488.5  403.17  5534.3  403.70
#Mann=3,-1,0
  4620.5    0.05       0  4995.4    0.05       0  4999.4    0.05       0
Bank Sta=4995.4,4999.4
Exp/Cntr=0.3,0.1

Type RM Length L Ch R = 1,11527,206,206,206
BEGIN DESCRIPTION:
South Twin Creek Trib I11527.4
END DESCRIPTION:
XS GIS Cut Line= 3
      2729879.05      6815561.34      2729523.55      6815672.50
      2729079.48      6815770.82
#Sta/Elev= 30
  4628.9  407.36  4646.2  407.08  4673.4  406.13  4808.5  402.58  4883.9  401.26
  4904.5  400.53  4925.5  400.39  4943.6  399.44  5001.4  398.16  5019.0  397.41
  5019.3  396.91  5022.8  396.91  5023.0  397.41  5029.6  397.45  5059.5  399.92
  5070.6  400.57  5091.0  401.15  5101.3  401.20  5151.9  399.82  5157.0  400.17
  5173.0  400.50  5193.5  400.51  5200.6  400.15  5205.7  400.39  5224.2  400.01
  5275.4  399.90  5377.8  401.50  5428.9  401.78  5439.3  402.37  5456.2  402.23
#Mann=3,-1,0
  4628.9    0.05       0  5019.0    0.05       0  5023.0    0.05       0
Bank Sta=5019,5023
Exp/Cntr=0.3,0.1

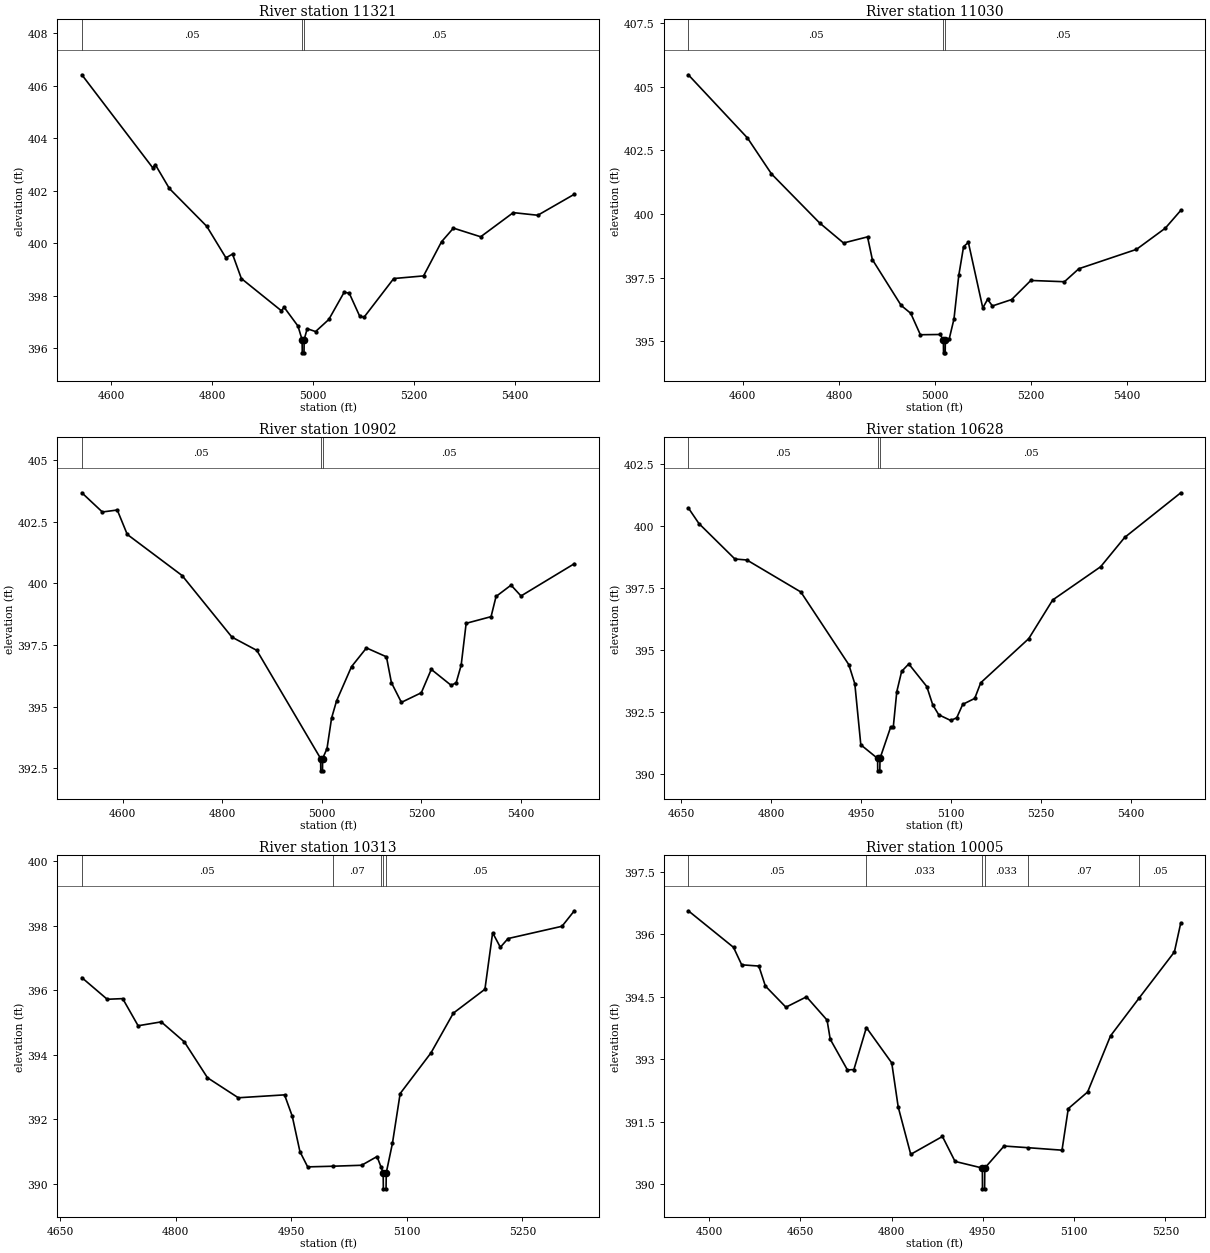
Type RM Length L Ch R = 1,11321,291,291,291
BEGIN DESCRIPTION:
South Twin Creek Trib I11321.37
END DESCRIPTION:
XS GIS Cut Line= 3
      2729876.02      6815408.01      2729421.78      6815498.66
      2728916.85      6815588.14
#Sta/Elev= 30
  4541.9  406.42  4682.3  402.88  4687.4  403.00  4715.3  402.09  4789.4  400.65
  4827.4  399.45  4840.5  399.59  4858.0  398.66  4937.5  397.43  4942.6  397.57
  4970.2  396.85  4978.4  396.33  4978.7  395.83  4982.2  395.83  4982.4  396.33
  4988.5  396.75  5005.1  396.64  5031.3  397.10  5061.8  398.14  5071.9  398.10
  5092.2  397.24  5100.9  397.18  5160.0  398.66  5219.1  398.76  5254.7  400.06
  5278.3  400.58  5332.3  400.25  5396.9  401.17  5445.5  401.07  5517.9  401.87
#Mann=3,-1,0
  4541.9    0.05       0  4978.4    0.05       0  4982.4    0.05       0
Bank Sta=4978.4,4982.4
Exp/Cntr=0.3,0.1

Type RM Length L Ch R = 1,11030,128,128,128
BEGIN DESCRIPTION:
South Twin Creek Trib I11029.6
END DESCRIPTION:
XS GIS Cut Line= 3
      2729889.17      6815223.89      2729368.72      6815222.07
      2728863.67      6815223.21
#Sta/Elev= 30
  4486.4  405.46  4609.6  402.98  4659.6  401.57  4759.6  399.65  4809.6  398.86
  4859.6  399.10  4869.6  398.21  4929.6  396.41  4949.6  396.10  4969.6  395.26
  5010.7  395.27  5017.6  395.05  5017.8  394.55  5021.3  394.55  5021.6  395.05
  5029.6  395.09  5039.6  395.88  5049.6  397.59  5059.6  398.72  5069.6  398.88
  5099.6  396.31  5109.6  396.65  5119.6  396.39  5159.6  396.64  5199.6  397.39
  5269.6  397.34  5299.6  397.85  5419.6  398.61  5479.6  399.44  5511.9  400.14
#Mann=3,-1,0
  4486.4    0.05       0  5017.6    0.05       0  5021.6    0.05       0
Bank Sta=5017.6,5021.6
Exp/Cntr=0.3,0.1

Type RM Length L Ch R = 1,10902,274,274,274
BEGIN DESCRIPTION:
South Twin Creek Trib I10902.19
END DESCRIPTION:
XS GIS Cut Line= 3
      2729857.12      6815085.46      2729369.50      6815094.80
      2728869.01      6815080.48
#Sta/Elev= 30
  4518.4  403.68  4559.5  402.90  4589.5  402.98  4609.5  401.99  4719.6  400.32
  4819.6  397.82  4869.6  397.28  4997.6  392.89  4997.9  392.39  5001.4  392.39
  5001.6  392.89  5010.4  393.29  5019.6  394.53  5029.6  395.23  5059.6  396.62
  5089.6  397.38  5129.7  397.02  5139.7  395.97  5159.7  395.17  5199.7  395.56
  5219.7  396.51  5259.7  395.86  5269.7  395.97  5279.7  396.68  5289.7  398.38
  5339.7  398.65  5349.7  399.47  5379.8  399.93  5399.8  399.49  5506.8  400.80
#Mann=3,-1,0
  4518.4    0.05       0  4997.6    0.05       0  5001.6    0.05       0
Bank Sta=4997.6,5001.6
Exp/Cntr=0.3,0.1

Type RM Length L Ch R = 1,10628,315,315,315
BEGIN DESCRIPTION:
South Twin Creek Trib I10627.86
END DESCRIPTION:
XS GIS Cut Line= 3
      2729763.69      6814838.00      2729421.87      6814836.48
      2728942.48      6814823.07
#Sta/Elev= 30
  4662.1  400.71  4679.8  400.08  4739.8  398.65  4759.8  398.61  4849.8  397.32
  4929.8  394.39  4939.8  393.62  4949.8  391.16  4977.8  390.61  4978.0  390.11
  4981.5  390.11  4981.8  390.61  4999.4  391.86  5003.9  391.86  5009.8  393.30
  5017.9  394.12  5029.8  394.42  5059.8  393.51  5069.8  392.77  5079.8  392.37
  5099.8  392.14  5109.8  392.25  5119.8  392.79  5139.8  393.03  5149.8  393.66
  5229.9  395.44  5269.9  397.00  5349.9  398.34  5389.9  399.52  5483.5  401.32
#Mann=3,-1,0
  4662.1    0.05       0  4977.8    0.05       0  4981.8    0.05       0
Bank Sta=4977.8,4981.8
Exp/Cntr=0.3,0.1

Type RM Length L Ch R = 1,10313,308,308,308
BEGIN DESCRIPTION:
South Twin Creek Trib I10312.68
END DESCRIPTION:
XS GIS Cut Line= 3
      2729708.95      6814568.29      2729379.54      6814572.69
      2729070.04      6814579.24
#Sta/Elev= 30
  4678.4  396.39  4711.3  395.72  4731.4  395.74  4751.4  394.90  4781.4  395.02
  4811.4  394.40  4841.4  393.29  4881.4  392.67  4941.4  392.76  4951.4  392.10
  4961.4  391.00  4971.4  390.53  5003.8  390.55  5041.4  390.58  5061.4  390.85
  5066.5  390.53  5069.4  390.35  5069.6  389.85  5073.1  389.85  5073.4  390.35
  5081.4  391.26  5091.4  392.80  5131.4  394.06  5160.4  395.29  5201.4  396.03
  5211.4  397.78  5221.4  397.33  5231.4  397.60  5301.4  397.98  5317.4  398.46
#Mann=5,-1,0
  4678.4    0.05       0  5003.8    0.07       0  5066.5    0.05       0
  5069.4    0.05       0  5073.4    0.05       0
Bank Sta=5069.4,5073.4
Exp/Cntr=0.3,0.1

Type RM Length L Ch R = 1,10005,216,216,216
BEGIN DESCRIPTION:
South Twin Creek Trib I10004.96
END DESCRIPTION:
XS GIS Cut Line= 3
      2729927.42      6814469.51      2729413.35      6814322.37
      2729145.78      6814260.69
#Sta/Elev= 30
  4466.0  396.57  4540.3  395.69  4553.7  395.27  4581.9  395.24  4592.6  394.76
  4626.4  394.25  4660.2  394.50  4694.0  393.94  4699.2  393.48  4727.5  392.74
  4738.1  392.75  4758.6  393.76  4800.3  392.91  4810.9  391.85  4831.5  390.71
  4883.6  391.14  4904.3  390.54  4949.2  390.38  4949.4  389.88  4952.9  389.88
  4953.2  390.38  4984.9  390.91  5024.1  390.87  5080.1  390.81  5090.4  391.81
  5122.2  392.21  5159.8  393.56  5206.8  394.47  5264.8  395.58  5275.3  396.28
#Mann=6,-1,0
  4466.0    0.05       0  4758.6   0.033       0  4949.2   0.033       0
  4953.2   0.033       0  5024.1    0.07       0  5206.8    0.05       0
Bank Sta=4949.2,4953.2
Exp/Cntr=0.3,0.1

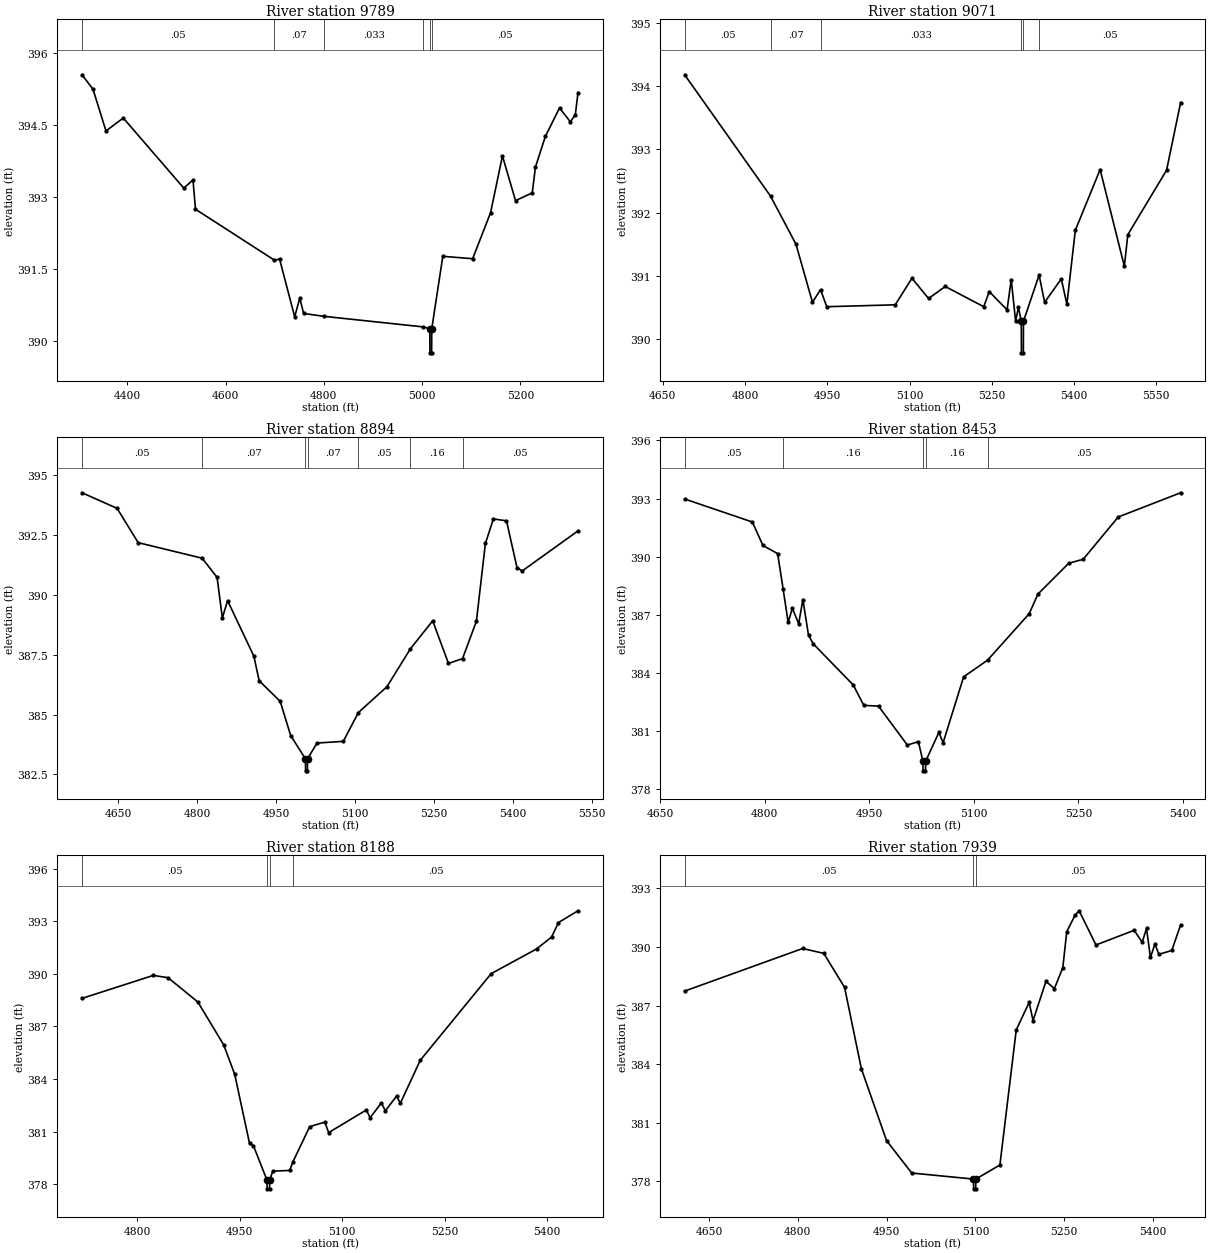
Type RM Length L Ch R = 1,9789,718,718,718
BEGIN DESCRIPTION:
South Twin Creek Trib I9789.42
END DESCRIPTION:
XS GIS Cut Line= 3
      2730137.77      6814277.02      2729462.14      6814122.63
      2729150.65      6814070.36
#Sta/Elev= 30
  4308.1  395.55  4330.4  395.25  4356.8  394.38  4392.0  394.65  4515.1  393.19
  4533.8  393.36  4538.9  392.75  4699.4  391.69  4710.0  391.71  4740.7  390.51
  4751.0  390.90  4758.9  390.58  4800.4  390.52  5002.3  390.30  5015.5  390.26
  5015.8  389.76  5019.3  389.76  5019.5  390.26  5042.0  391.77  5102.7  391.72
  5139.2  392.68  5163.3  393.86  5189.9  392.93  5223.9  393.09  5230.5  393.63
  5250.7  394.27  5279.5  394.86  5301.4  394.57  5311.6  394.72  5317.0  395.18
#Mann=6,-1,0
  4308.1    0.05       0  4699.4    0.07       0  4800.4   0.033       0
  5002.3    0.05       0  5015.5   0.033       0  5019.5    0.05       0
Bank Sta=5015.5,5019.5
Exp/Cntr=0.3,0.1

Type RM Length L Ch R = 1,9071,177,177,177
BEGIN DESCRIPTION:
South Twin Creek Trib I9070.68
END DESCRIPTION:
XS GIS Cut Line= 6
      2730108.71      6813950.77      2729797.40      6813933.07
      2729618.69      6813904.63      2729526.12      6813902.46
      2729400.64      6813923.76      2729210.65      6813950.43
#Sta/Elev= 30
  4689.9  394.18  4846.5  392.26  4892.9  391.50  4923.0  390.58  4937.7  390.78
  4949.1  390.51  5074.0  390.54  5104.4  390.96  5134.8  390.64  5165.1  390.83
  5235.4  390.51  5245.4  390.75  5277.9  390.46  5285.5  390.94  5293.5  390.28
  5298.6  390.50  5303.8  390.28  5304.1  389.78  5307.6  389.78  5307.8  390.28
  5336.3  391.01  5346.4  390.58  5376.8  390.95  5387.0  390.55  5402.4  391.72
  5447.6  392.68  5491.8  391.15  5498.1  391.65  5568.8  392.67  5594.4  393.74
#Mann=6,-1,0
  4689.9    0.05       0  4846.5    0.07       0  4937.7   0.033       0
  5303.8   0.033       0  5307.8   0.033       0  5336.3    0.05       0
Bank Sta=5303.8,5307.8
Exp/Cntr=0.3,0.1

Type RM Length L Ch R = 1,8894,441,441,441
BEGIN DESCRIPTION:
South Twin Creek Trib I8894.32
END DESCRIPTION:
XS GIS Cut Line= 6
      2730092.66      6813820.51      2729673.87      6813808.95
      2729515.04      6813810.42      2729342.95      6813813.31
      2729310.71      6813809.09      2729150.03      6813808.76
#Sta/Elev= 30
  4581.1  394.25  4647.8  393.60  4687.8  392.17  4809.6  391.52  4837.9  390.72
  4847.9  389.03  4857.9  389.75  4907.9  387.43  4917.9  386.41  4957.9  385.55
  4977.9  384.12  5005.9  383.15  5006.2  382.65  5009.7  382.65  5009.9  383.15
  5027.9  383.81  5077.9  383.88  5106.5  385.08  5160.9  386.16  5205.5  387.74
  5247.9  388.91  5277.9  387.13  5304.6  387.33  5331.0  388.89  5348.1  392.14
  5363.4  393.16  5388.2  393.08  5408.2  391.13  5418.2  390.99  5524.2  392.66
#Mann=7,-1,0
  4581.1    0.05       0  4809.6    0.07       0  5005.9    0.07       0
  5009.9    0.07       0  5106.5    0.05       0  5205.5    0.16       0
  5304.6    0.05       0
Bank Sta=5005.9,5009.9
Exp/Cntr=0.3,0.1

Type RM Length L Ch R = 1,8453,265,265,265
BEGIN DESCRIPTION:
South Twin Creek Trib I8452.83
END DESCRIPTION:
XS GIS Cut Line= 3
      2729624.53      6813374.13      2729353.84      6813551.80
      2729040.35      6813779.93
#Sta/Elev= 30
  4685.1  392.98  4782.3  391.79  4797.4  390.58  4818.5  390.16  4826.3  388.35
  4833.6  386.61  4839.6  387.34  4848.7  386.54  4854.7  387.79  4862.8  385.95
  4869.7  385.50  4927.0  383.38  4942.1  382.33  4963.2  382.29  5004.6  380.28
  5020.4  380.46  5026.9  379.45  5027.1  378.95  5030.6  378.95  5030.9  379.45
  5049.8  380.93  5055.9  380.40  5085.3  383.80  5119.6  384.66  5179.4  387.06
  5191.9  388.07  5236.0  389.66  5256.9  389.87  5307.1  392.05  5396.6  393.30
#Mann=5,-1,0
  4685.1    0.05       0  4826.3    0.16       0  5026.9    0.07       0
  5030.9    0.16       0  5119.6    0.05       0
Bank Sta=5026.9,5030.9
Exp/Cntr=0.3,0.1

Type RM Length L Ch R = 1,8188,249,249,249
BEGIN DESCRIPTION:
South Twin Creek Trib I8187.73
END DESCRIPTION:
XS GIS Cut Line= 3
      2729331.03      6813114.00      2729194.72      6813361.90
      2728991.24      6813756.41
#Sta/Elev= 30
  4718.8  388.60  4823.2  389.91  4845.0  389.78  4888.6  388.39  4926.5  385.94
  4942.5  384.27  4964.3  380.32  4970.0  380.19  4989.8  378.23  4990.1  377.73
  4993.6  377.73  4993.8  378.23  4998.3  378.74  5023.2  378.78  5027.6  379.25
  5052.4  381.28  5074.6  381.54  5080.2  380.94  5135.4  382.23  5141.0  381.79
  5157.6  382.64  5163.2  382.18  5179.7  383.02  5185.3  382.62  5214.5  385.07
  5318.3  390.01  5384.8  391.42  5406.9  392.10  5417.0  392.93  5445.6  393.60
#Mann=4,-1,0
  4718.8    0.05       0  4989.8    0.07       0  4993.8    0.05       0
  5027.6    0.05       0
Bank Sta=4989.8,4993.8
Exp/Cntr=0.3,0.1

Type RM Length L Ch R = 1,7939,228,228,228
BEGIN DESCRIPTION:
South Twin Creek Trib I7939.25
END DESCRIPTION:
XS GIS Cut Line= 3
      2729255.60      6813038.62      2728986.03      6813326.70
      2728693.34      6813659.72
#Sta/Elev= 30
  4608.8  387.74  4808.2  389.92  4843.9  389.67  4879.0  387.93  4907.4  383.76
  4949.9  380.09  4992.4  378.43  5096.7  378.12  5097.0  377.62  5100.5  377.62
  5100.7  378.12  5141.4  378.84  5169.0  385.75  5190.8  387.16  5197.4  386.23
  5219.2  388.24  5233.5  387.87  5247.7  388.94  5254.3  390.78  5268.6  391.64
  5275.3  391.85  5303.7  390.10  5368.2  390.85  5381.8  390.24  5389.1  390.95
  5395.7  389.46  5403.3  390.15  5410.0  389.62  5431.8  389.82  5446.7  391.13
#Mann=3,-1,0
  4608.8    0.05       0  5096.7    0.05       0  5100.7    0.05       0
Bank Sta=5096.7,5100.7
Exp/Cntr=0.3,0.1

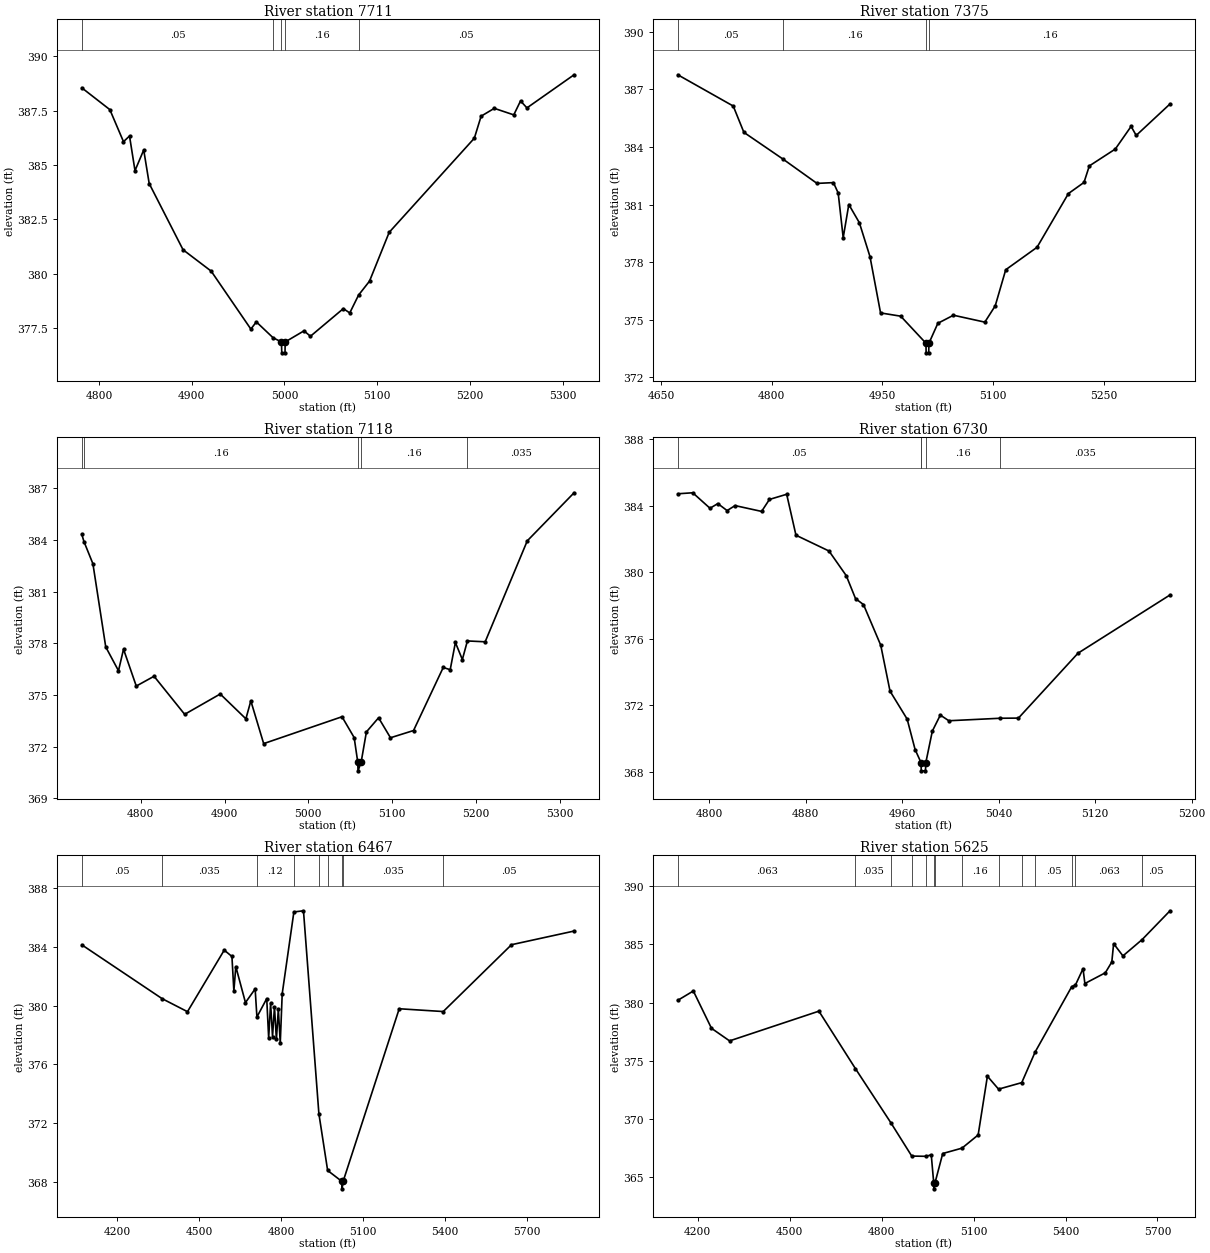
Type RM Length L Ch R = 1,7711,336,336,336
BEGIN DESCRIPTION:
South Twin Creek Trib I7617.09
END DESCRIPTION:
XS GIS Cut Line= 3
      2729044.03      6813028.36      2728859.04      6813144.45
      2728644.30      6813371.07
#Sta/Elev= 30
  4781.6  388.54  4811.8  387.54  4826.5  386.07  4833.0  386.33  4838.9  384.74
  4848.3  385.69  4854.2  384.15  4890.7  381.11  4921.0  380.13  4963.8  377.47
  4969.7  377.80  4987.8  377.07  4996.8  376.88  4997.1  376.38  5000.6  376.38
  5000.8  376.88  5021.1  377.39  5028.0  377.14  5063.5  378.41  5070.4  378.21
  5079.9  379.03  5091.7  379.67  5112.9  381.91  5204.7  386.23  5212.0  387.24
  5226.2  387.60  5247.2  387.30  5254.5  387.94  5261.4  387.62  5312.2  389.14
#Mann=5,-1,0
  4781.6    0.05       0  4987.8    0.16       0  4996.8    0.07       0
  5000.8    0.16       0  5079.9    0.05       0
Bank Sta=4996.8,5000.8
Exp/Cntr=0.3,0.1

Type RM Length L Ch R = 1,7375,257,257,257
BEGIN DESCRIPTION:
South Twin Creek Trib I7233.85
END DESCRIPTION:
XS GIS Cut Line= 3
      2729029.27      6812628.52      2728776.20      6812835.92
      2728530.87      6813070.45
#Sta/Elev= 30
  4672.8  387.76  4747.9  386.13  4762.3  384.76  4815.5  383.36  4861.3  382.10
  4883.6  382.14  4890.0  381.60  4896.8  379.27  4904.4  381.00  4918.7  380.05
  4933.1  378.28  4947.4  375.35  4974.7  375.18  5008.9  373.77  5009.1  373.27
  5012.6  373.27  5012.9  373.77  5025.0  374.81  5046.1  375.23  5088.6  374.87
  5102.7  375.72  5116.9  377.60  5159.3  378.77  5201.8  381.57  5222.9  382.15
  5230.1  383.01  5265.3  383.89  5286.7  385.07  5293.6  384.60  5339.4  386.24
#Mann=4,-1,0
  4672.8    0.05       0  4815.5    0.16       0  5008.9    0.07       0
  5012.9    0.16       0
Bank Sta=5008.9,5012.9
Exp/Cntr=0.3,0.1

Type RM Length L Ch R = 1,7118,388,388,388
BEGIN DESCRIPTION:
Mapping XS 55df5f1d
END DESCRIPTION:
XS GIS Cut Line= 3
      2728954.02      6812450.14      2728721.22      6812597.07
      2728533.09      6812845.48
#Sta/Elev= 30
  4729.9  384.32  4732.4  383.91  4743.1  382.62  4758.4  377.79  4773.6  376.41
  4779.6  377.66  4794.8  375.52  4816.0  376.09  4852.5  373.88  4894.9  375.06
  4925.5  373.62  4931.4  374.66  4946.7  372.18  5040.1  373.74  5054.6  372.53
  5058.9  371.10  5059.2  370.60  5062.9  371.10  5069.2  372.86  5083.7  373.68
  5097.9  372.52  5125.4  372.94  5160.8  376.60  5169.1  376.47  5175.3  378.05
  5183.6  377.06  5189.6  378.14  5210.8  378.09  5261.0  383.95  5316.8  386.74
#Mann=5,-1,0
  4729.9    0.05       0  4732.4    0.16       0  5058.9    0.07       0
  5062.9    0.16       0  5189.6   0.035       0
Bank Sta=5058.9,5062.9
Exp/Cntr=0.3,0.1

Type RM Length L Ch R = 1,6730,263,263,263
BEGIN DESCRIPTION:
South Twin Creek Trib I6750.46
END DESCRIPTION:
XS GIS Cut Line= 3
      2728950.83      6812108.32      2728778.88      6812255.28
      2728640.22      6812373.17
#Sta/Elev= 30
  4773.8  384.71  4786.2  384.77  4800.5  383.84  4807.0  384.12  4814.7  383.70
  4821.3  384.00  4843.3  383.65  4849.8  384.37  4864.1  384.68  4871.8  382.22
  4899.2  381.27  4913.5  379.79  4921.2  378.41  4927.8  378.05  4942.1  375.61
  4949.8  372.85  4964.0  371.17  4970.6  369.34  4975.3  368.59  4975.5  368.56
  4975.7  368.06  4979.2  368.06  4979.5  368.56  4984.9  370.45  4991.5  371.41
  4998.6  371.07  5041.0  371.22  5056.3  371.23  5105.7  375.13  5182.0  378.63
#Mann=5,-1,0
  4773.8    0.05       0  4975.3    0.16       0  4975.5    0.07       0
  4979.5    0.16       0  5041.0   0.035       0
Bank Sta=4975.5,4979.5
Exp/Cntr=0.3,0.1

Type RM Length L Ch R = 1,6467,842,842,842
BEGIN DESCRIPTION:
South Twin Creek Trib I6467.04
END DESCRIPTION:
XS GIS Cut Line= 4
      2729333.13      6811371.67      2728673.66      6812031.58
      2728357.00      6812242.37      2727954.27      6812516.47
#Sta/Elev= 30
  4070.5  384.13  4363.9  380.47  4456.9  379.58  4591.3  383.77  4619.5  383.34
  4626.6  380.99  4633.7  382.65  4669.0  380.20  4704.4  381.13  4710.9  379.22
  4746.8  380.47  4753.9  377.79  4761.0  380.14  4768.0  377.89  4775.1  379.91
  4782.2  377.69  4789.2  379.76  4796.3  377.45  4803.4  380.80  4846.1  386.37
  4881.2  386.45  4937.6  372.63  4969.6  368.77  5022.1  368.02  5022.3  367.52
  5026.1  368.02  5231.4  379.78  5392.4  379.59  5642.1  384.14  5871.0  385.07
#Mann=9,-1,0
  4070.5    0.05       0  4363.9   0.035       0  4710.9    0.12       0
  4846.1   0.035       0  4937.6    0.05       0  4969.6   0.035       0
  5022.1   0.035       0  5026.1   0.035       0  5392.4    0.05       0
Bank Sta=5022.1,5026.1
Exp/Cntr=0.3,0.1

Type RM Length L Ch R = 1,5625,288,288,288
BEGIN DESCRIPTION:
South Twin Creek Trib I5625.29
END DESCRIPTION:
XS GIS Cut Line= 3
      2729145.42      6810851.15      2728388.36      6811280.23
      2727768.79      6811676.95
#Sta/Elev= 30
  4135.1  380.19  4185.8  380.99  4245.0  377.79  4304.1  376.71  4595.5  379.26
  4714.4  374.34  4829.7  369.71  4898.4  366.83  4945.1  366.81  4962.0  366.94
  4970.1  364.52  4970.4  364.02  4974.1  364.52  4999.5  367.05  5062.3  367.51
  5115.0  368.64  5145.2  373.68  5181.6  372.57  5257.3  373.13  5301.0  375.76
  5420.3  381.36  5432.4  381.50  5457.2  382.90  5463.2  381.63  5529.9  382.55
  5551.1  383.48  5557.0  385.05  5587.4  384.00  5650.0  385.40  5741.0  387.87
#Mann=14,-1,0
  4135.1   0.063       0  4714.4   0.035       0  4829.7    0.12       0
  4898.4   0.035       0  4945.1    0.12       0  4970.1    0.07       0
  4974.1    0.12       0  5062.3    0.16       0  5181.6    0.07       0
  5257.3   0.063       0  5301.0    0.05       0  5420.3    0.07       0
  5432.4   0.063       0  5650.0    0.05       0
Bank Sta=4970.1,4974.1
Exp/Cntr=0.3,0.1

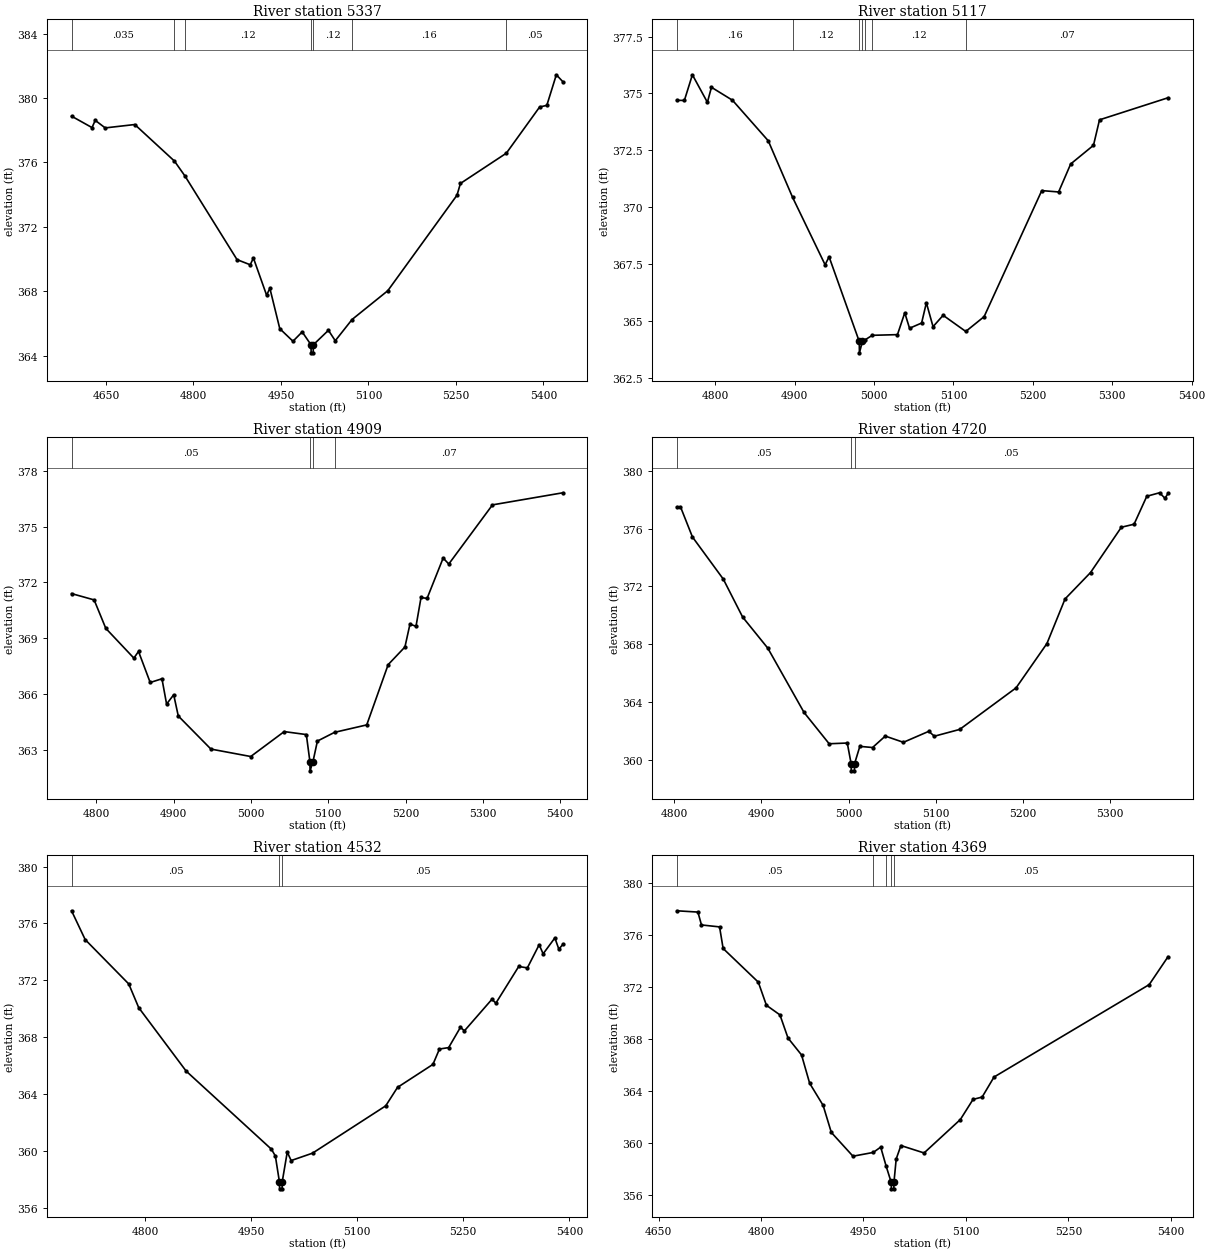
Type RM Length L Ch R = 1,5337,220,220,220
BEGIN DESCRIPTION:
South Twin Creek Trib I5337.1
END DESCRIPTION:
XS GIS Cut Line= 3
      2728712.06      6810850.49      2728340.20      6811030.13
      2727960.81      6811231.08
#Sta/Elev= 30
  4591.0  378.87  4626.1  378.16  4631.6  378.61  4648.7  378.14  4699.4  378.35
  4767.4  376.08  4785.5  375.15  4874.7  369.96  4897.3  369.64  4902.8  370.06
  4925.4  367.75  4931.0  368.18  4948.0  365.67  4970.6  364.89  4986.4  365.47
  5001.5  364.67  5001.8  364.17  5005.3  364.17  5005.5  364.67  5031.4  365.57
  5043.1  364.92  5071.9  366.24  5133.2  368.03  5251.8  373.96  5257.7  374.69
  5336.4  376.57  5393.5  379.44  5405.8  379.54  5422.1  381.44  5433.3  381.01
#Mann=7,-1,0
  4591.0   0.035       0  4767.4    0.16       0  4785.5    0.12       0
  5001.5    0.07       0  5005.5    0.12       0  5071.9    0.16       0
  5336.4    0.05       0
Bank Sta=5001.5,5005.5
Exp/Cntr=0.3,0.1

Type RM Length L Ch R = 1,5117,208,208,208
BEGIN DESCRIPTION:
South Twin Creek Trib I5117.42
END DESCRIPTION:
XS GIS Cut Line= 3
      2728595.55      6810800.16      2728342.93      6810835.37
      2728036.94      6811031.66
#Sta/Elev= 30
  4751.6  374.70  4761.2  374.69  4771.3  375.82  4790.2  374.61  4795.3  375.27
  4821.8  374.70  4866.8  372.92  4897.5  370.43  4938.4  367.47  4943.4  367.82
  4981.4  364.10  4981.6  363.60  4985.4  364.10  4989.1  364.18  4997.8  364.37
  5029.5  364.40  5038.7  365.36  5044.7  364.68  5059.9  364.91  5065.9  365.80
  5074.3  364.75  5087.0  365.25  5115.5  364.54  5138.6  365.19  5211.2  370.73
  5232.4  370.67  5247.6  371.90  5276.3  372.72  5283.9  373.84  5370.2  374.81
#Mann=7,-1,0
  4751.6    0.16       0  4897.5    0.12       0  4981.4    0.07       0
  4985.4    0.12       0  4989.1    0.16       0  4997.8    0.12       0
  5115.5    0.07       0
Bank Sta=4981.4,4985.4
Exp/Cntr=0.3,0.1

Type RM Length L Ch R = 1,4909,189,189,189
BEGIN DESCRIPTION:
South Twin Creek Trib I4909.17
END DESCRIPTION:
XS GIS Cut Line= 3
      2728395.84      6810459.93      2728266.15      6810660.39
      2728010.96      6810963.91
#Sta/Elev= 30
  4768.1  371.40  4797.3  371.06  4812.4  369.53  4848.7  367.93  4854.7  368.29
  4869.8  366.62  4885.0  366.82  4891.0  365.46  4900.2  365.96  4906.1  364.82
  4948.3  363.04  4999.8  362.64  5043.1  363.98  5071.7  363.82  5076.3  362.37
  5076.5  361.87  5080.3  362.37  5086.0  363.47  5108.2  363.94  5149.8  364.34
  5177.5  367.58  5199.2  368.53  5205.7  369.76  5213.5  369.64  5220.0  371.19
  5227.8  371.14  5248.6  373.31  5255.9  372.99  5312.4  376.17  5403.4  376.82
#Mann=4,-1,0
  4768.1    0.05       0  5076.3    0.05       0  5080.3    0.05       0
  5108.2    0.07       0
Bank Sta=5076.3,5080.3
Exp/Cntr=0.3,0.1

Type RM Length L Ch R = 1,4720,188,188,188
BEGIN DESCRIPTION:
South Twin Creek Trib I4719.78
END DESCRIPTION:
XS GIS Cut Line= 3
      2728289.99      6810349.21      2728163.10      6810508.61
      2727947.51      6810796.99
#Sta/Elev= 30
  4802.8  377.50  4807.1  377.50  4820.8  375.42  4856.2  372.51  4878.4  369.89
  4907.3  367.74  4948.9  363.30  4977.7  361.14  4998.5  361.19  5002.9  359.77
  5003.1  359.27  5006.6  359.27  5006.9  359.77  5012.9  360.96  5027.5  360.88
  5042.1  361.67  5062.9  361.24  5092.1  362.00  5098.4  361.66  5127.5  362.13
  5192.2  365.00  5227.6  368.06  5248.4  371.14  5277.6  372.96  5313.0  376.09
  5327.6  376.30  5342.2  378.23  5356.8  378.47  5363.1  378.09  5366.6  378.43
#Mann=3,-1,0
  4802.8    0.05       0  5002.9    0.05       0  5006.9    0.05       0
Bank Sta=5002.9,5006.9
Exp/Cntr=0.3,0.1

Type RM Length L Ch R = 1,4532,163,163,163
BEGIN DESCRIPTION:
South Twin Creek Trib I4532.48
END DESCRIPTION:
XS GIS Cut Line= 3
      2728138.16      6810165.90      2727999.27      6810445.79
      2727826.17      6810786.60
#Sta/Elev= 30
  4696.1  376.89  4715.4  374.86  4777.0  371.74  4791.1  370.07  4858.1  365.61
  4978.7  360.11  4984.3  359.63  4990.0  357.82  4990.3  357.32  4993.8  357.32
  4994.0  357.82  5001.1  359.91  5006.6  359.31  5036.8  359.83  5140.3  363.16
  5157.0  364.46  5207.1  366.08  5216.3  367.16  5229.3  367.26  5246.0  368.69
  5251.6  368.44  5290.5  370.66  5296.1  370.39  5328.4  372.97  5340.6  372.87
  5357.3  374.50  5362.9  373.86  5379.5  374.98  5385.1  374.19  5390.8  374.52
#Mann=3,-1,0
  4696.1    0.05       0  4990.0    0.05       0  4994.0    0.05       0
Bank Sta=4990,4994
Exp/Cntr=0.3,0.1

Type RM Length L Ch R = 1,4369,268,268,268
BEGIN DESCRIPTION:
South Twin Creek Trib I4369.02
END DESCRIPTION:
XS GIS Cut Line= 3
      2727971.11      6810047.64      2727866.68      6810362.15
      2727734.94      6810727.00
#Sta/Elev= 30
  4676.7  377.89  4707.7  377.79  4712.9  376.80  4739.4  376.65  4744.6  374.99
  4796.1  372.40  4808.0  370.62  4827.8  369.88  4839.6  368.10  4859.4  366.80
  4871.3  364.62  4891.0  362.92  4903.0  360.84  4934.7  359.01  4964.4  359.30
  4975.3  359.71  4983.4  358.22  4990.7  357.00  4991.0  356.50  4994.5  356.50
  4994.7  357.00  4998.0  358.80  5004.9  359.83  5038.8  359.26  5091.9  361.83
  5110.5  363.38  5123.8  363.56  5141.2  365.10  5368.4  372.21  5396.0  374.36
#Mann=5,-1,0
  4676.7    0.05       0  4964.4    0.12       0  4983.4    0.05       0
  4990.7    0.05       0  4994.7    0.05       0
Bank Sta=4990.7,4994.7
Exp/Cntr=0.3,0.1