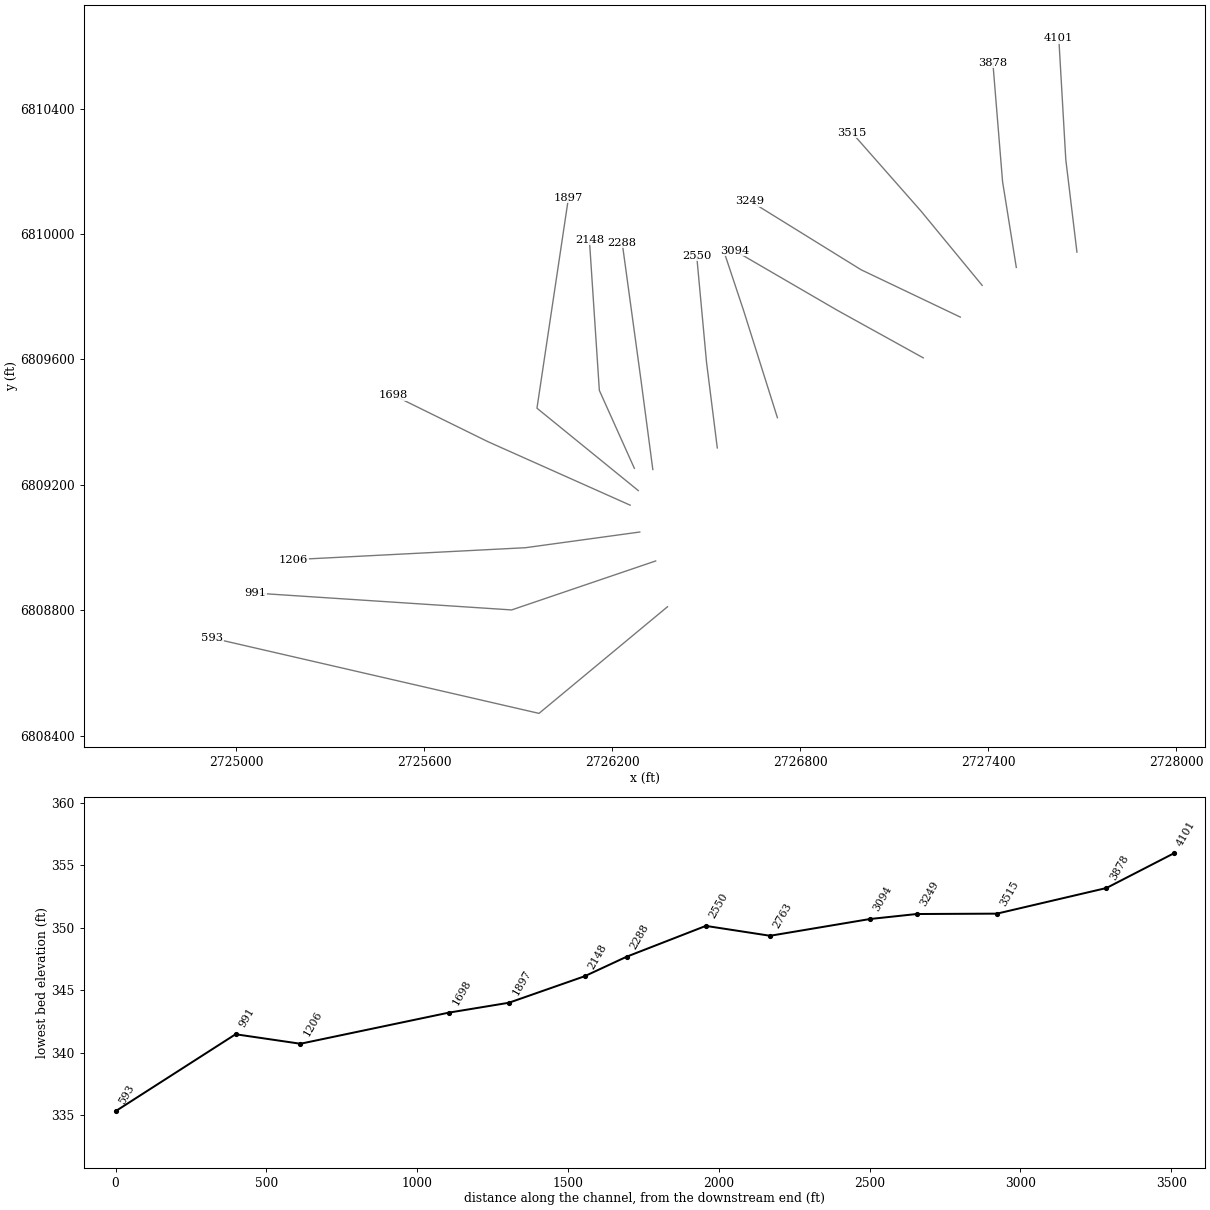
HEC-RAS study South Twin Creek Trib I.prj: South Twin Creek Trib I Base Level Engineering

--- South Twin Creek Trib I.g01 (geometry) --- (continued)

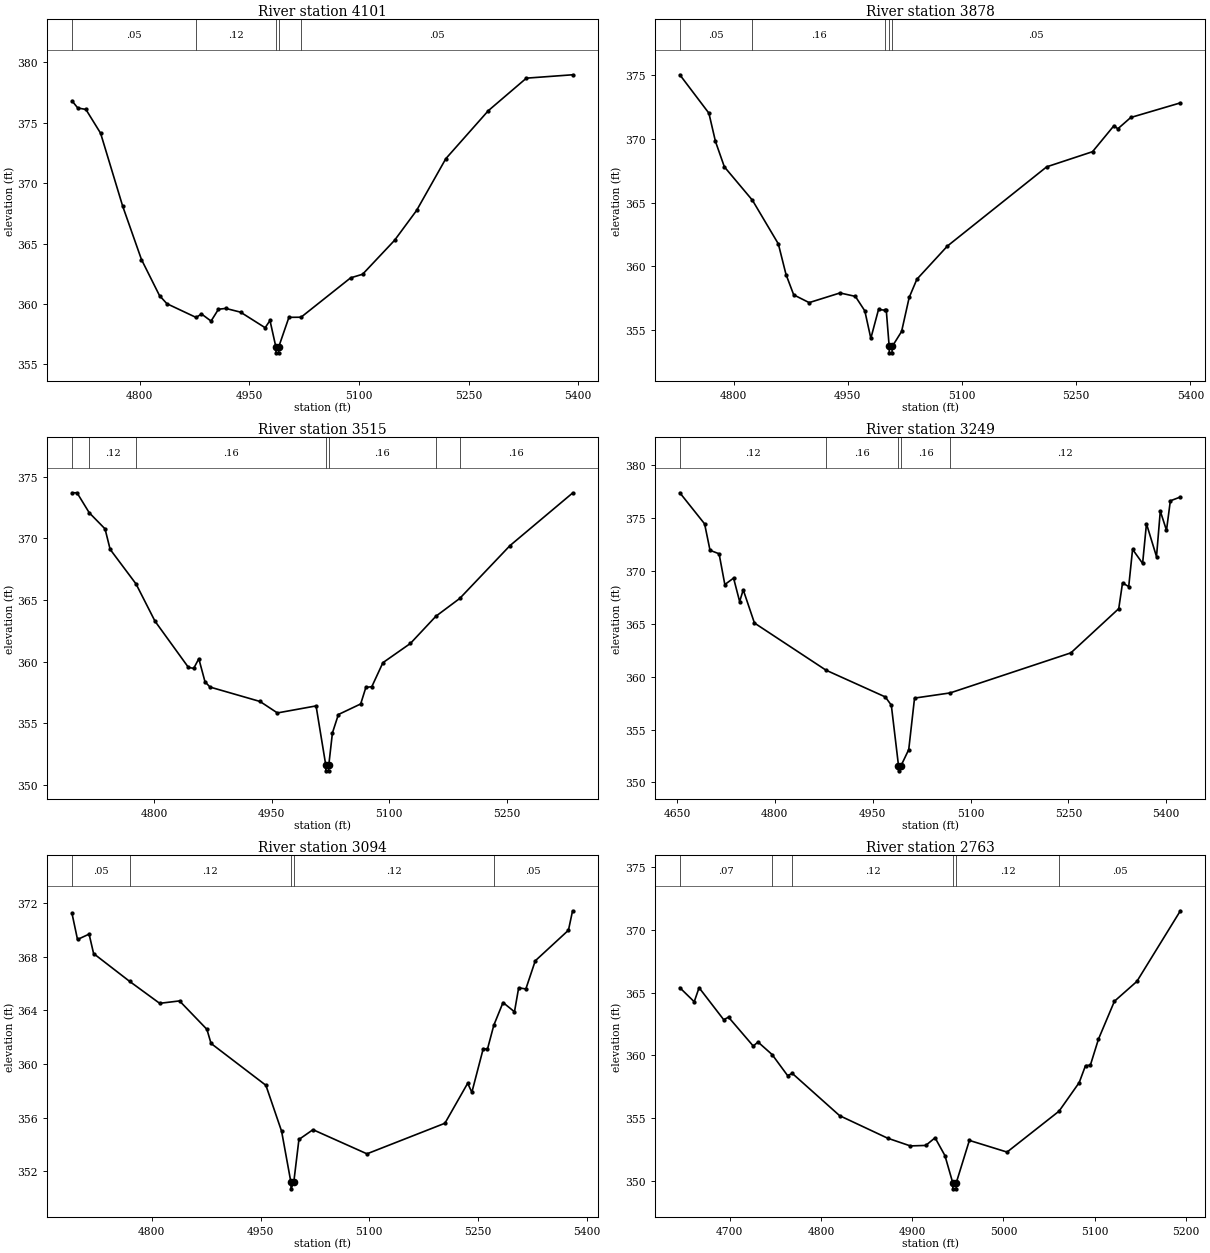
Type RM Length L Ch R = 1,4101,223,223,223
BEGIN DESCRIPTION:
South Twin Creek Trib I4101.2
END DESCRIPTION:
XS GIS Cut Line= 3
      2727682.42      6809942.17      2727646.83      6810237.52
      2727624.55      6810624.09
#Sta/Elev= 30
  4707.5  376.82  4715.4  376.23  4726.5  376.11  4746.6  374.14  4776.8  368.10
  4802.5  363.68  4827.2  360.69  4837.3  360.02  4877.3  358.88  4884.6  359.17
  4897.7  358.58  4907.8  359.56  4917.8  359.63  4938.0  359.32  4971.7  358.03
  4978.3  358.63  4986.3  356.45  4986.6  355.95  4990.1  355.95  4990.3  356.45
  5004.2  358.89  5020.8  358.90  5088.6  362.16  5105.0  362.46  5148.7  365.27
  5178.8  367.74  5218.8  372.03  5277.0  376.01  5329.0  378.70  5392.2  378.98
#Mann=5,-1,0
  4707.5    0.05       0  4877.3    0.12       0  4986.3    0.07       0
  4990.3    0.12       0  5020.8    0.05       0
Bank Sta=4986.3,4990.3
Exp/Cntr=0.3,0.1

Type RM Length L Ch R = 1,3878,363,363,363
BEGIN DESCRIPTION:
South Twin Creek Trib I3877.66
END DESCRIPTION:
XS GIS Cut Line= 3
      2727488.96      6809893.25      2727445.06      6810167.53
      2727414.15      6810546.00
#Sta/Elev= 30
  4729.3  375.05  4767.5  372.03  4776.1  369.81  4787.8  367.81  4824.7  365.18
  4858.7  361.75  4868.8  359.34  4878.9  357.74  4899.2  357.13  4939.7  357.89
  4959.9  357.62  4972.3  356.48  4980.2  354.32  4990.3  356.59  4999.2  356.53
  5000.5  356.52  5004.3  353.68  5004.5  353.18  5008.0  353.18  5008.3  353.68
  5020.6  354.86  5030.6  357.54  5040.7  358.97  5080.8  361.58  5211.2  367.81
  5271.4  369.00  5299.6  371.05  5304.6  370.80  5321.6  371.69  5386.8  372.84
#Mann=5,-1,0
  4729.3    0.05       0  4824.7    0.16       0  4999.2    0.05       0
  5004.3    0.05       0  5008.3    0.05       0
Bank Sta=5004.3,5008.3
Exp/Cntr=0.3,0.1

Type RM Length L Ch R = 1,3515,266,266,266
BEGIN DESCRIPTION:
South Twin Creek Trib I3515
END DESCRIPTION:
XS GIS Cut Line= 3
      2727380.01      6809836.11      2727184.79      6810073.12
      2726965.01      6810322.55
#Sta/Elev= 30
  4694.8  373.70  4701.2  373.70  4716.8  372.08  4737.0  370.77  4743.5  369.11
  4776.6  366.30  4800.8  363.28  4843.6  359.52  4850.3  359.45  4856.8  360.23
  4864.7  358.36  4871.1  357.93  4935.0  356.76  4957.2  355.83  5006.6  356.40
  5018.9  351.63  5019.1  351.13  5022.6  351.13  5022.9  351.63  5027.5  354.21
  5035.1  355.70  5063.6  356.56  5070.2  357.90  5077.8  357.96  5092.0  359.91
  5127.1  361.47  5159.7  363.68  5190.1  365.12  5254.3  369.41  5334.3  373.68
#Mann=7,-1,0
  4694.8    0.05       0  4716.8    0.12       0  4776.6    0.16       0
  5018.9    0.07       0  5022.9    0.16       0  5159.7    0.05       0
  5190.1    0.16       0
Bank Sta=5018.9,5022.9
Exp/Cntr=0.3,0.1

Type RM Length L Ch R = 1,3249,155,155,155
BEGIN DESCRIPTION:
South Twin Creek Trib I3249.37
END DESCRIPTION:
XS GIS Cut Line= 3
      2727310.33      6809734.90      2726993.60      6809885.95
      2726639.55      6810105.11
#Sta/Elev= 30
  4654.3  377.40  4692.3  374.46  4700.6  371.96  4714.5  371.63  4723.3  368.72
  4736.7  369.33  4746.0  367.11  4751.5  368.22  4768.7  365.08  4878.4  360.62
  4969.3  358.09  4978.5  357.31  4989.5  351.60  4989.7  351.10  4993.5  351.60
  5005.2  353.11  5014.1  357.98  5068.7  358.47  5253.8  362.26  5327.1  366.44
  5332.9  368.87  5342.4  368.53  5348.3  372.05  5363.7  370.72  5369.6  374.47
  5385.0  371.36  5390.8  375.67  5400.3  373.85  5406.2  376.64  5421.6  377.00
#Mann=5,-1,0
  4654.3    0.12       0  4878.4    0.16       0  4989.5    0.07       0
  4993.5    0.16       0  5068.7    0.12       0
Bank Sta=4989.5,4993.5
Exp/Cntr=0.3,0.1

Type RM Length L Ch R = 1,3094,331,331,331
BEGIN DESCRIPTION:
South Twin Creek Trib I3093.59
END DESCRIPTION:
XS GIS Cut Line= 3
      2727192.10      6809604.83      2726917.21      6809756.88
      2726591.49      6809946.23
#Sta/Elev= 30
  4689.8  371.23  4697.4  369.29  4713.4  369.69  4719.6  368.24  4769.5  366.16
  4810.8  364.53  4838.2  364.71  4876.0  362.59  4881.7  361.54  4957.4  358.42
  4979.1  354.99  4991.9  351.20  4992.1  350.70  4995.9  351.20  5003.0  354.38
  5022.4  355.11  5096.9  353.31  5204.5  355.59  5235.9  358.57  5241.7  357.90
  5257.4  361.15  5263.2  361.11  5272.0  362.90  5284.7  364.59  5300.5  363.90
  5306.3  365.69  5316.2  365.60  5329.2  367.70  5375.0  369.98  5380.7  371.43
#Mann=5,-1,0
  4689.8    0.05       0  4769.5    0.12       0  4991.9    0.07       0
  4995.9    0.12       0  5272.0    0.05       0
Bank Sta=4991.9,4995.9
Exp/Cntr=0.3,0.1

Type RM Length L Ch R = 1,2763,213,213,213
BEGIN DESCRIPTION:
South Twin Creek Trib I2762.54
END DESCRIPTION:
XS GIS Cut Line= 3
      2726726.70      6809413.90      2726618.73      6809755.96
      2726558.69      6809936.23
#Sta/Elev= 30
  4645.3  365.39  4661.1  364.27  4666.4  365.39  4693.4  362.84  4698.7  363.04
  4725.8  360.74  4731.0  361.06  4746.5  360.06  4763.4  358.39  4768.6  358.56
  4820.5  355.19  4873.0  353.40  4898.0  352.78  4914.9  352.82  4925.1  353.43
  4935.9  352.01  4944.4  349.86  4944.6  349.36  4948.1  349.36  4948.4  349.86
  4962.7  353.22  5004.0  352.29  5061.0  355.55  5083.1  357.83  5090.0  359.18
  5095.3  359.21  5104.2  361.29  5121.7  364.31  5146.3  365.89  5194.0  371.52
#Mann=6,-1,0
  4645.3    0.07       0  4746.5    0.05       0  4768.6    0.12       0
  4944.4    0.07       0  4948.4    0.12       0  5061.0    0.05       0
Bank Sta=4944.4,4948.4
Exp/Cntr=0.3,0.1

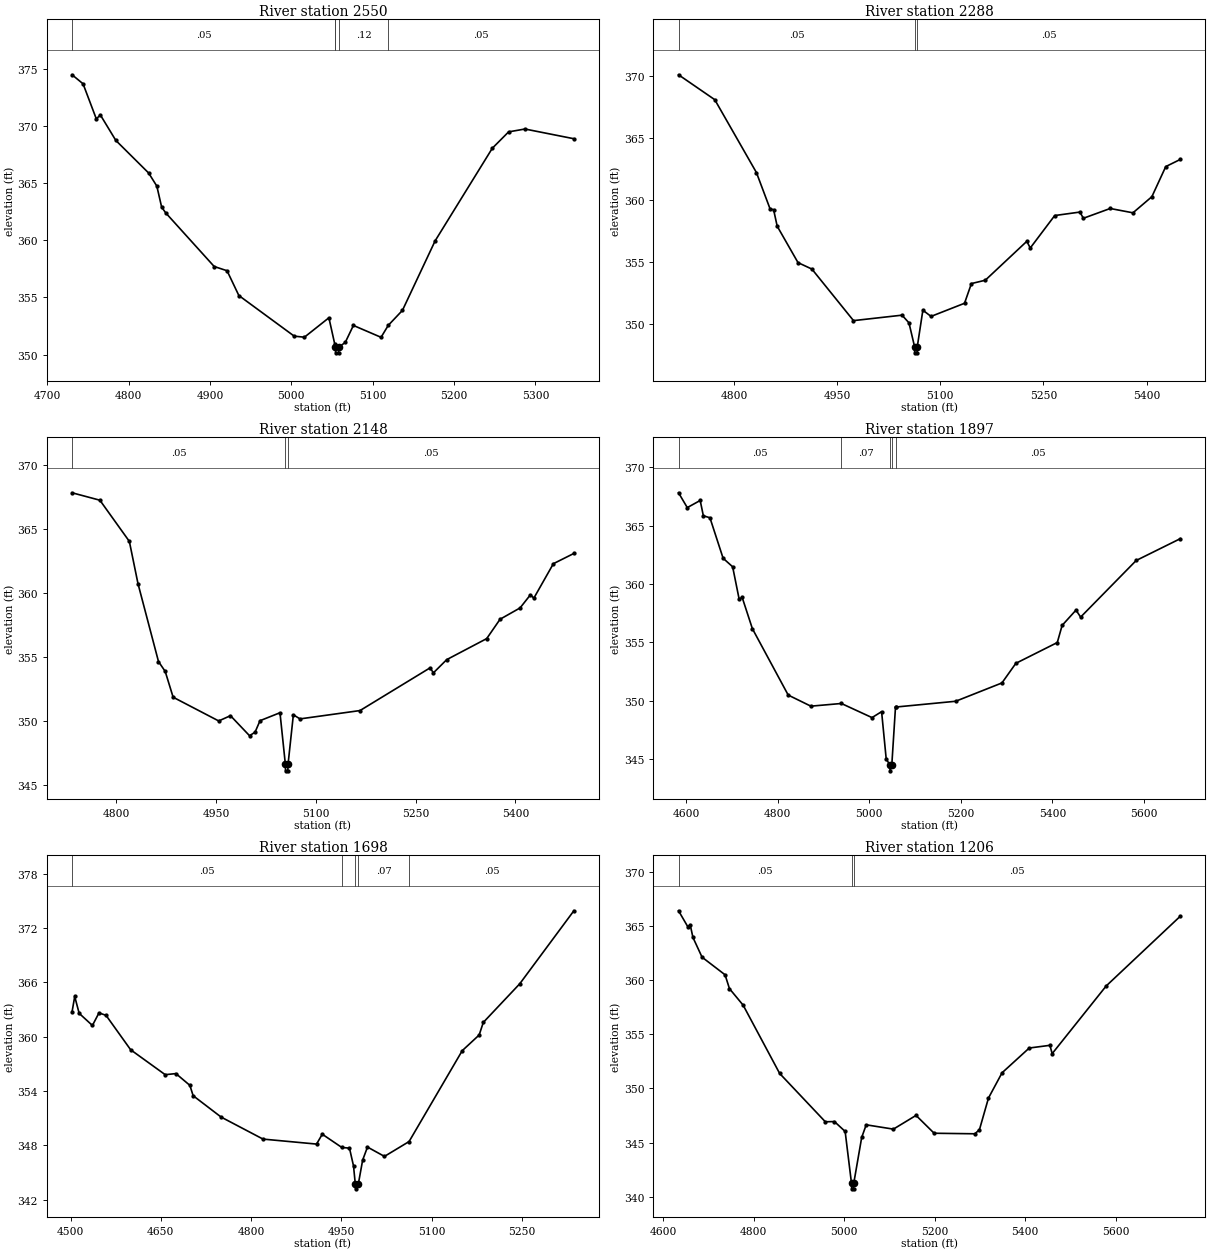
Type RM Length L Ch R = 1,2550,262,262,262
BEGIN DESCRIPTION:
South Twin Creek Trib I2550.15
END DESCRIPTION:
XS GIS Cut Line= 3
      2726534.86      6809317.62      2726500.55      6809590.41
      2726469.07      6809930.81
#Sta/Elev= 30
  4730.5  374.50  4744.0  373.71  4760.3  370.64  4765.3  370.98  4784.3  368.75
  4824.6  365.90  4834.7  364.75  4840.6  362.91  4845.7  362.40  4905.2  357.71
  4921.0  357.34  4935.5  355.17  5003.6  351.61  5016.1  351.52  5046.2  353.22
  5053.4  350.91  5054.2  350.65  5054.5  350.15  5058.0  350.15  5058.2  350.65
  5066.3  351.06  5076.3  352.55  5110.3  351.51  5119.2  352.56  5136.6  353.87
  5176.8  359.96  5247.1  368.07  5267.1  369.50  5287.2  369.75  5347.3  368.90
#Mann=5,-1,0
  4730.5    0.05       0  5053.4    0.12       0  5054.2    0.05       0
  5058.2    0.12       0  5119.2    0.05       0
Bank Sta=5054.2,5058.2
Exp/Cntr=0.3,0.1

Type RM Length L Ch R = 1,2288,140,140,140
BEGIN DESCRIPTION:
South Twin Creek Trib I2288.21
END DESCRIPTION:
XS GIS Cut Line= 3
      2726329.13      6809248.72      2726291.64      6809531.85
      2726231.36      6809972.05
#Sta/Elev= 30
  4719.2  370.13  4771.9  368.12  4832.5  362.24  4852.4  359.30  4857.5  359.24
  4862.7  357.91  4893.0  354.97  4913.2  354.45  4973.7  350.29  5044.3  350.73
  5054.4  350.11  5062.5  348.19  5062.7  347.69  5066.2  347.69  5066.5  348.19
  5074.6  351.13  5086.5  350.63  5135.2  351.69  5145.2  353.28  5165.4  353.55
  5225.8  356.69  5230.8  356.15  5266.4  358.77  5303.0  359.05  5308.1  358.55
  5347.1  359.34  5380.2  358.99  5407.7  360.29  5427.9  362.72  5449.1  363.30
#Mann=3,-1,0
  4719.2    0.05       0  5062.5    0.05       0  5066.5    0.05       0
Bank Sta=5062.5,5066.5
Exp/Cntr=0.3,0.1

Type RM Length L Ch R = 1,2148,251,251,251
BEGIN DESCRIPTION:
South Twin Creek Trib I2148.33
END DESCRIPTION:
XS GIS Cut Line= 3
      2726270.24      6809252.49      2726158.54      6809501.03
      2726126.73      6809981.69
#Sta/Elev= 30
  4733.6  367.80  4775.4  367.22  4819.7  364.01  4832.7  360.71  4863.5  354.64
  4873.6  353.87  4885.5  351.86  4954.0  350.01  4971.7  350.42  5000.3  348.86
  5008.6  349.13  5016.1  350.03  5046.1  350.65  5054.2  346.62  5054.4  346.12
  5057.9  346.12  5058.2  346.62  5066.2  350.49  5076.2  350.17  5166.4  350.82
  5271.7  354.15  5276.7  353.76  5296.7  354.79  5356.8  356.43  5376.9  357.94
  5406.9  358.82  5422.6  359.85  5427.6  359.58  5457.0  362.27  5487.8  363.07
#Mann=3,-1,0
  4733.6    0.05       0  5054.2    0.05       0  5058.2    0.05       0
Bank Sta=5054.2,5058.2
Exp/Cntr=0.3,0.1

Type RM Length L Ch R = 1,1897,199,199,199
BEGIN DESCRIPTION:
South Twin Creek Trib I1896.694
END DESCRIPTION:
XS GIS Cut Line= 3
      2726282.74      6809181.50      2725959.46      6809444.26
      2726060.17      6810116.36
#Sta/Elev= 30
  4583.4  367.82  4602.5  366.55  4630.7  367.16  4637.6  365.85  4652.0  365.68
  4680.8  362.21  4701.6  361.48  4715.9  358.69  4722.4  358.86  4744.7  356.18
  4823.0  350.49  4872.5  349.54  4939.1  349.77  5006.1  348.56  5027.0  349.07
  5037.1  345.01  5045.3  344.50  5045.5  344.00  5049.3  344.50  5057.4  349.48
  5059.2  349.47  5188.8  349.96  5289.9  351.53  5320.3  353.21  5410.8  354.99
  5421.4  356.46  5451.7  357.77  5461.8  357.17  5583.2  362.02  5679.6  363.89
#Mann=5,-1,0
  4583.4    0.05       0  4939.1    0.07       0  5045.3    0.07       0
  5049.3    0.07       0  5059.2    0.05       0
Bank Sta=5045.3,5049.3
Exp/Cntr=0.3,0.1

Type RM Length L Ch R = 1,1698,492,492,492
BEGIN DESCRIPTION:
South Twin Creek Trib I1697.752
END DESCRIPTION:
XS GIS Cut Line= 3
      2726256.82      6809134.98      2725802.60      6809337.69
      2725501.00      6809486.00
#Sta/Elev= 30
  4502.6  362.75  4507.0  364.44  4514.4  362.58  4536.4  361.24  4547.3  362.63
  4559.0  362.36  4599.9  358.56  4657.3  355.81  4675.1  355.93  4698.3  354.63
  4703.7  353.49  4750.2  351.13  4819.8  348.70  4908.7  348.15  4918.2  349.24
  4950.6  347.78  4963.4  347.70  4970.1  345.74  4973.1  343.71  4973.5  343.21
  4978.0  343.71  4985.3  346.39  4993.3  347.82  5021.5  346.79  5062.4  348.43
  5150.7  358.46  5178.8  360.19  5185.7  361.58  5246.2  365.84  5336.1  373.90
#Mann=5,-1,0
  4502.6    0.05       0  4950.6    0.07       0  4973.1    0.07       0
  4978.0    0.07       0  5062.4    0.05       0
Bank Sta=4973.1,4978
Exp/Cntr=0.3,0.1

Type RM Length L Ch R = 1,1206,215,215,215
BEGIN DESCRIPTION:
South Twin Creek Trib I1206.3
END DESCRIPTION:
XS GIS Cut Line= 3
      2726287.54      6809049.36      2725922.56      6808999.28
      2725182.34      6808961.22
#Sta/Elev= 30
  4633.7  366.43  4654.4  364.94  4659.5  365.14  4665.5  363.97  4685.7  362.14
  4736.6  360.51  4746.3  359.23  4776.6  357.70  4857.3  351.39  4958.3  346.92
  4978.4  346.94  5002.1  346.03  5016.2  341.22  5016.6  340.72  5020.8  340.72
  5021.1  341.22  5038.7  345.47  5048.7  346.64  5108.8  346.24  5158.9  347.51
  5198.9  345.86  5289.0  345.81  5299.1  346.19  5319.1  349.12  5349.1  351.45
  5409.2  353.74  5454.9  353.99  5459.9  353.22  5579.4  359.48  5743.3  365.93
#Mann=3,-1,0
  4633.7    0.05       0  5016.2    0.05       0  5021.1    0.05       0
Bank Sta=5016.2,5021.1
Exp/Cntr=0.3,0.1

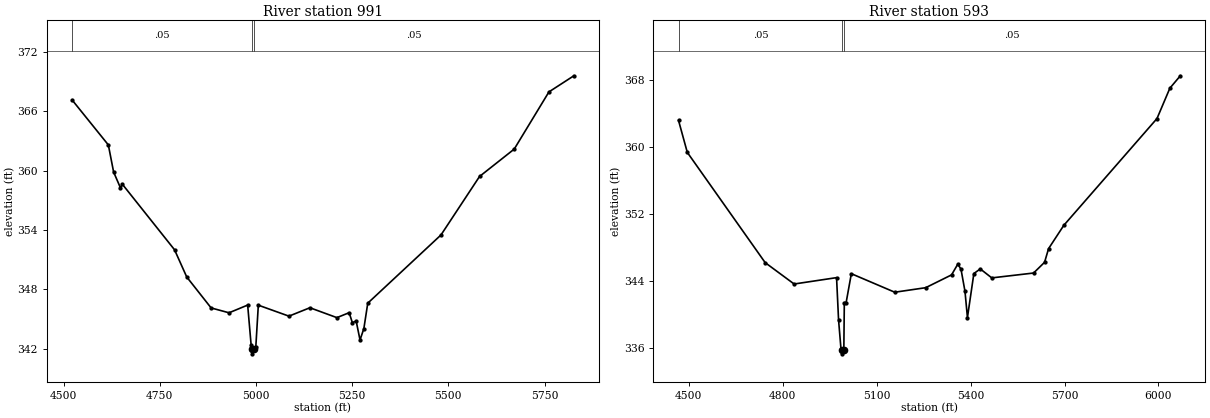
Type RM Length L Ch R = 1,991,398,398,398
BEGIN DESCRIPTION:
South Twin Creek Trib I991.15
END DESCRIPTION:
XS GIS Cut Line= 3
      2726338.24      6808957.03      2725878.67      6808800.83
      2725061.32      6808854.49
#Sta/Elev= 30
  4521.8  367.15  4616.1  362.60  4629.8  359.86  4647.5  358.27  4652.7  358.62
  4788.2  352.00  4819.9  349.25  4883.3  346.12  4929.9  345.63  4978.3  346.41
  4987.4  342.33  4990.2  341.98  4990.5  341.48  4995.1  341.98  4999.4  342.13
  5006.0  346.40  5085.6  345.29  5140.1  346.14  5210.3  345.14  5242.1  345.64
  5250.4  344.64  5260.4  344.79  5270.4  342.88  5280.4  344.04  5290.5  346.60
  5480.9  353.50  5581.1  359.41  5671.3  362.18  5761.5  367.96  5826.3  369.59
#Mann=3,-1,0
  4521.8    0.05       0  4990.2    0.05       0  4995.1    0.05       0
Bank Sta=4990.2,4995.1
Exp/Cntr=0.3,0.1

Type RM Length L Ch R = 1,593,0,0,0
BEGIN DESCRIPTION:
South Twin Creek Trib I592.993
END DESCRIPTION:
XS GIS Cut Line= 3
      2726376.01      6808811.01      2725965.92      6808470.86
      2724923.42      6808711.01
#Sta/Elev= 30
  4467.2  363.16  4495.2  359.35  4743.9  346.20  4836.4  343.65  4971.9  344.41
  4978.3  339.36  4986.2  335.82  4990.2  335.82  4990.6  335.32  4995.1  335.82
  4996.7  341.44  5002.5  341.44  5019.1  344.88  5157.8  342.67  5256.5  343.21
  5339.2  344.74  5359.1  346.02  5369.3  345.42  5382.0  342.79  5389.9  339.65
  5410.4  344.90  5430.9  345.45  5467.6  344.38  5601.1  344.96  5636.2  346.24
  5649.0  347.87  5697.7  350.65  5995.3  363.39  6036.4  367.01  6069.8  368.49
#Mann=3,-1,0
  4467.2    0.05       0  4990.2    0.05       0  4995.1    0.05       0
Bank Sta=4990.2,4995.1
Exp/Cntr=0.3,0.1

Chan Stop Cuts=-1