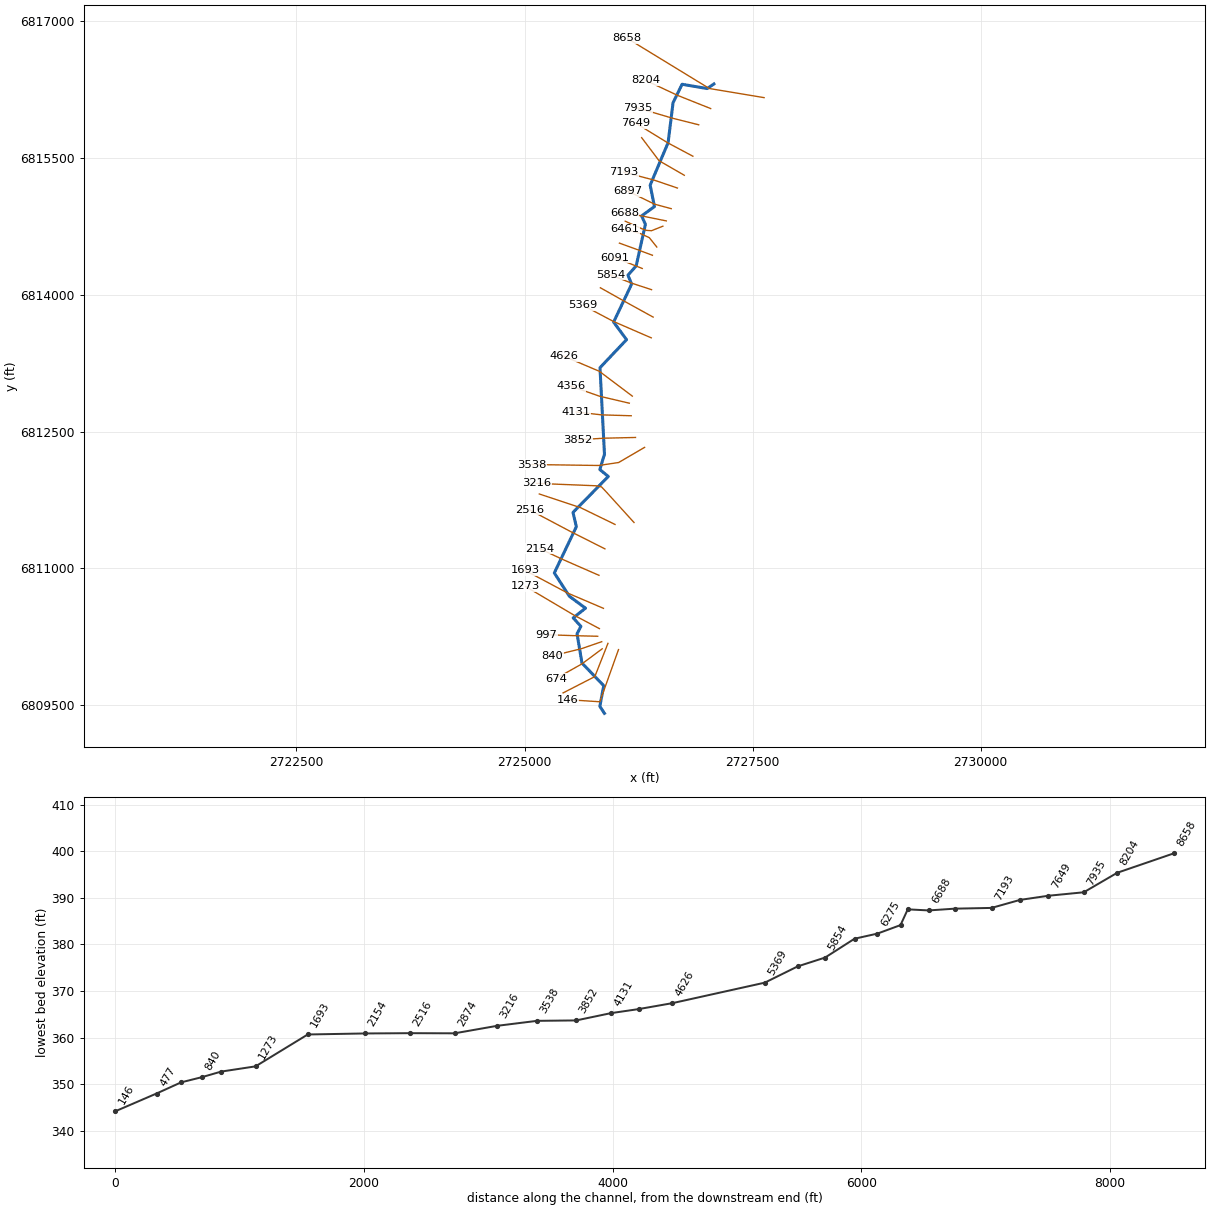
--- South Twin Creek Trib I1.prj (project) ---

Proj Title=South Twin Creek Trib I1 Base Level Engineering
Current Plan=p01
Default Exp/Contr=0.3,0.1
English Units
Geom File=g01
Flow File=f01
Plan File=p01
BEGIN DESCRIPTION:
South Twin Creek Trib I1
END DESCRIPTION:

--- South Twin Creek Trib I1.p01 (plan) ---

Plan Title=Multiple Run
Short Identifier=Multiple
Geom File=g01
Flow File=f01
Subcritical Flow
K Sum by GR= 0
Std Step Tol= 0.01
Critical Tol= 0.01
Num of Std Step Trials= 20
Max Error Tol= 0.3
Flow Tol Ratio= 0.001
Split Flow NTrial= 30
Split Flow Tol= 0.02
Split Flow Ratio= 0.02
Log Output Level= 0
Friction Slope Method= 1
Unsteady Friction Slope Method= 2
Unsteady Bridges Friction Slope Method= 1
Parabolic Critical Depth
Global Vel Dist=  1 , 1 , 1
Global Log Level= 0
CheckData=True
Encroach Param= -1, 0, 0, 0
BEGIN DESCRIPTION:
Multiple Run
END DESCRIPTION:

--- South Twin Creek Trib I1.f01 (steady flow) ---

Flow Title=Multiple
Number of Profiles=7
Profile Names=10-year,25-year,50-year,1pct_min,100-year,1pct_plu,500-year
River Rch & RM= South Twin Creek,Reach-1,8658
     323     416     488     284     568    1133     767
River Rch & RM= South Twin Creek,Reach-1,3538
     418     543     641     376     750    1497    1026
Boundary for River Rch & Prof#=South Twin Creek,Reach-1,1
Up Type=0
Dn Type=3
Dn Slope=0.005
Boundary for River Rch & Prof#=South Twin Creek,Reach-1,2
Up Type=0
Dn Type=3
Dn Slope=0.005
Boundary for River Rch & Prof#=South Twin Creek,Reach-1,3
Up Type=0
Dn Type=3
Dn Slope=0.005
Boundary for River Rch & Prof#=South Twin Creek,Reach-1,4
Up Type=0
Dn Type=3
Dn Slope=0.005
Boundary for River Rch & Prof#=South Twin Creek,Reach-1,5
Up Type=0
Dn Type=3
Dn Slope=0.005
Boundary for River Rch & Prof#=South Twin Creek,Reach-1,6
Up Type=0
Dn Type=3
Dn Slope=0.005
Boundary for River Rch & Prof#=South Twin Creek,Reach-1,7
Up Type=0
Dn Type=3
Dn Slope=0.005

--- South Twin Creek Trib I1.g01 (geometry) ---

Geom Title=Existing Conditions

River Reach=South Twin Creek,Reach-1
Reach XY= 30
      2727076.00      6816311.00      2727003.15      6816260.39
      2726727.22      6816307.57      2726628.38      6816105.47
      2726573.76      6815666.93      2726377.37      6815201.33
      2726424.34      6814966.44      2726283.72      6814864.66
      2726325.18      6814771.71      2726223.81      6814316.44
      2726133.83      6814214.40      2726174.16      6814117.13
      2725976.72      6813700.29      2726118.42      6813507.65
      2725827.20      6813200.50      2725876.45      6812251.72
      2725825.65      6812083.75      2725918.22      6812007.94
      2725531.30      6811613.67      2725568.19      6811457.59
      2725326.55      6810950.36      2725492.50      6810693.95
      2725668.49      6810564.16      2725533.54      6810457.85
      2725618.15      6810364.41      2725575.71      6810283.84
      2725629.54      6809962.46      2725868.21      6809714.42
      2725825.69      6809488.15      2725876.00      6809411.00

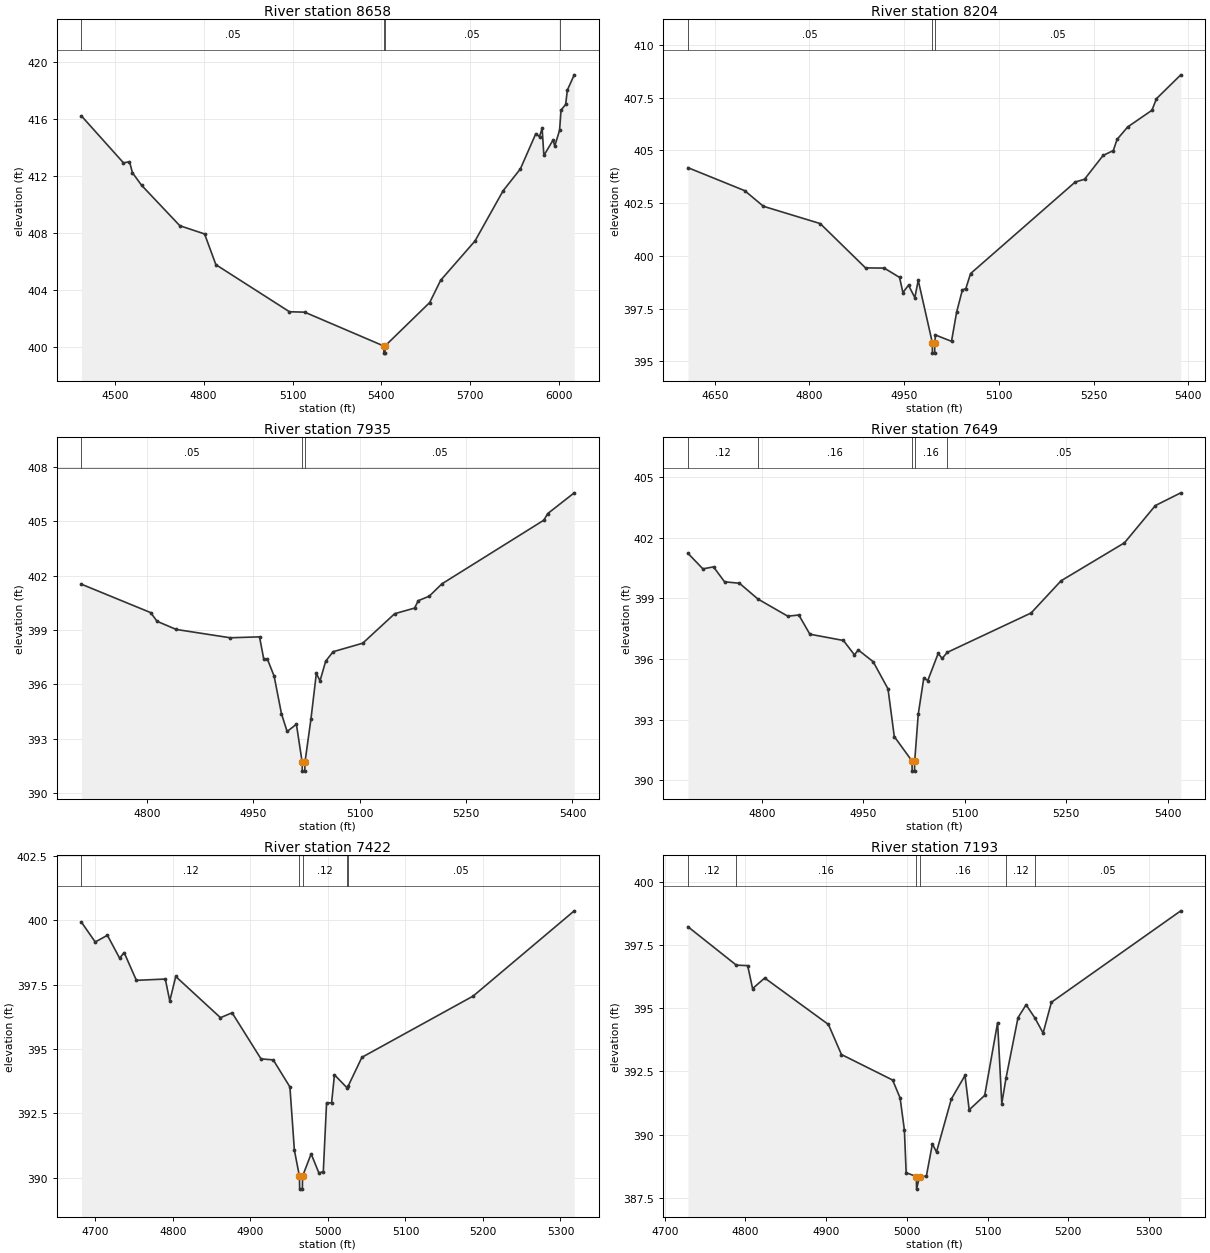
Type RM Length L Ch R = 1,8658,454,454,454
BEGIN DESCRIPTION:
South Twin Creek Trib I18658.006
END DESCRIPTION:
XS GIS Cut Line= 3
      2727625.99      6816161.00      2727026.00      6816261.00
      2726126.01      6816810.99
#Sta/Elev= 30
  4387.7  416.23  4529.6  412.93  4549.9  413.01  4560.0  412.23  4590.4  411.36
  4719.7  408.51  4803.3  407.93  4841.4  405.77  5089.7  402.46  5141.1  402.43
  5408.1  400.05  5408.4  399.55  5411.9  399.55  5412.1  400.05  5563.0  403.11
  5599.8  404.67  5715.9  407.44  5810.7  410.97  5868.8  412.50  5921.0  414.98
  5933.5  414.77  5942.3  415.37  5948.2  413.45  5979.1  414.53  5984.9  414.11
  6001.2  415.22  6006.2  416.64  6021.7  417.04  6027.5  418.05  6050.7  419.12
#Mann=4,-1,0
  4387.7    0.05       0  5408.1    0.05       0  5412.1    0.05       0
  6001.2   0.063       0
Bank Sta=5408.1,5412.1
Exp/Cntr=0.3,0.1

Type RM Length L Ch R = 1,8204,269,269,269
BEGIN DESCRIPTION:
South Twin Creek Trib I18203.5
END DESCRIPTION:
XS GIS Cut Line= 3
      2727040.57      6816041.14      2726675.50      6816186.74
      2726324.69      6816351.72
#Sta/Elev= 30
  4607.5  404.18  4697.4  403.09  4727.0  402.35  4817.0  401.53  4888.8  399.43
  4918.4  399.42  4942.7  398.98  4948.0  398.26  4956.9  398.61  4966.9  398.02
  4972.3  398.84  4994.6  395.89  4994.8  395.39  4998.3  395.39  4998.6  395.89
  4999.5  396.25  5025.0  395.95  5033.1  397.33  5042.2  398.38  5047.7  398.45
  5055.2  399.16  5221.0  403.50  5235.7  403.63  5265.2  404.76  5281.3  404.99
  5287.3  405.52  5304.1  406.11  5342.5  406.90  5349.7  407.45  5388.2  408.58
#Mann=3,-1,0
  4607.5    0.05       0  4994.6    0.05       0  4998.6    0.05       0
Bank Sta=4994.6,4998.6
Exp/Cntr=0.3,0.1

Type RM Length L Ch R = 1,7935,286,286,286
BEGIN DESCRIPTION:
South Twin Creek Trib I17935.2
END DESCRIPTION:
XS GIS Cut Line= 3
      2726909.43      6815863.18      2726625.53      6815934.46
      2726240.05      6816048.13
#Sta/Elev= 30
  4707.9  401.53  4805.5  399.96  4814.5  399.48  4841.5  399.03  4917.6  398.57
  4958.9  398.62  4964.9  397.39  4970.1  397.38  4979.5  396.45  4989.8  394.38
  4997.8  393.39  5010.9  393.79  5019.0  391.70  5019.2  391.20  5022.7  391.20
  5023.0  391.70  5031.4  394.08  5039.0  396.60  5044.2  396.19  5052.2  397.28
  5062.7  397.80  5104.4  398.27  5149.4  399.90  5177.4  400.21  5182.7  400.62
  5198.2  400.87  5216.0  401.55  5359.7  405.07  5365.0  405.43  5402.5  406.58
#Mann=3,-1,0
  4707.9    0.05       0  5019.0    0.05       0  5023.0    0.05       0
Bank Sta=5019,5023
Exp/Cntr=0.3,0.1

Type RM Length L Ch R = 1,7649,227,227,227
BEGIN DESCRIPTION:
South Twin Creek Trib I17648.51
END DESCRIPTION:
XS GIS Cut Line= 3
      2726845.48      6815518.78      2726571.55      6815664.78
      2726215.10      6815883.29
#Sta/Elev= 30
  4691.0  401.22  4713.1  400.45  4728.8  400.55  4745.1  399.81  4767.1  399.74
  4794.4  398.96  4838.6  398.11  4854.9  398.17  4871.2  397.22  4920.8  396.91
  4937.1  396.20  4942.8  396.44  4964.8  395.86  4986.7  394.52  4996.0  392.16
  5022.2  390.95  5022.4  390.45  5025.9  390.45  5026.2  390.95  5031.4  393.26
  5039.6  395.05  5045.5  394.93  5060.9  396.27  5066.8  396.02  5074.2  396.32
  5198.3  398.27  5242.5  399.86  5336.3  401.74  5381.9  403.58  5419.5  404.21
#Mann=5,-1,0
  4691.0    0.12       0  4794.4    0.16       0  5022.2    0.07       0
  5026.2    0.16       0  5074.2    0.05       0
Bank Sta=5022.2,5026.2
Exp/Cntr=0.3,0.1

Type RM Length L Ch R = 1,7422,229,229,229
BEGIN DESCRIPTION:
South Twin Creek Trib I17422.1
END DESCRIPTION:
XS GIS Cut Line= 3
      2726751.40      6815310.01      2726473.86      6815470.19
      2726284.20      6815722.27
#Sta/Elev= 30
  4681.9  399.93  4699.7  399.16  4715.4  399.42  4731.2  398.53  4737.0  398.75
  4752.8  397.67  4790.1  397.72  4795.9  396.87  4803.6  397.82  4861.3  396.22
  4876.3  396.41  4913.6  394.62  4929.4  394.58  4950.9  393.53  4956.7  391.07
  4963.2  390.06  4963.5  389.56  4967.0  389.56  4967.2  390.06  4978.3  390.93
  4988.3  390.19  4994.0  390.24  4998.2  392.91  5004.7  392.91  5008.4  394.00
  5024.8  393.49  5026.2  393.57  5043.8  394.68  5187.4  397.06  5317.8  400.37
#Mann=5,-1,0
  4681.9    0.12       0  4963.2    0.07       0  4967.2    0.12       0
  5024.8    0.16       0  5026.2    0.05       0
Bank Sta=4963.2,4967.2
Exp/Cntr=0.3,0.1

Type RM Length L Ch R = 1,7193,296,296,296
BEGIN DESCRIPTION:
South Twin Creek Trib I17193.34
END DESCRIPTION:
XS GIS Cut Line= 3
      2726676.06      6815169.90      2726419.29      6815257.43
      2726090.90      6815343.27
#Sta/Elev= 30
  4728.8  398.23  4788.7  396.71  4802.8  396.69  4808.9  395.78  4823.9  396.20
  4902.9  394.36  4919.0  393.17  4982.4  392.16  4991.7  391.45  4997.0  390.18
  4999.2  388.49  5011.8  388.34  5012.1  387.84  5015.8  388.34  5024.2  388.35
  5031.7  389.63  5036.8  389.31  5055.2  391.41  5072.1  392.34  5077.3  390.98
  5096.5  391.55  5112.5  394.43  5117.7  391.23  5122.9  392.23  5137.8  394.63
  5147.8  395.14  5158.7  394.62  5168.9  394.02  5179.2  395.24  5339.5  398.86
#Mann=6,-1,0
  4728.8    0.12       0  4788.7    0.16       0  5011.8    0.07       0
  5015.8    0.16       0  5122.9    0.12       0  5158.7    0.05       0
Bank Sta=5011.8,5015.8
Exp/Cntr=0.3,0.1

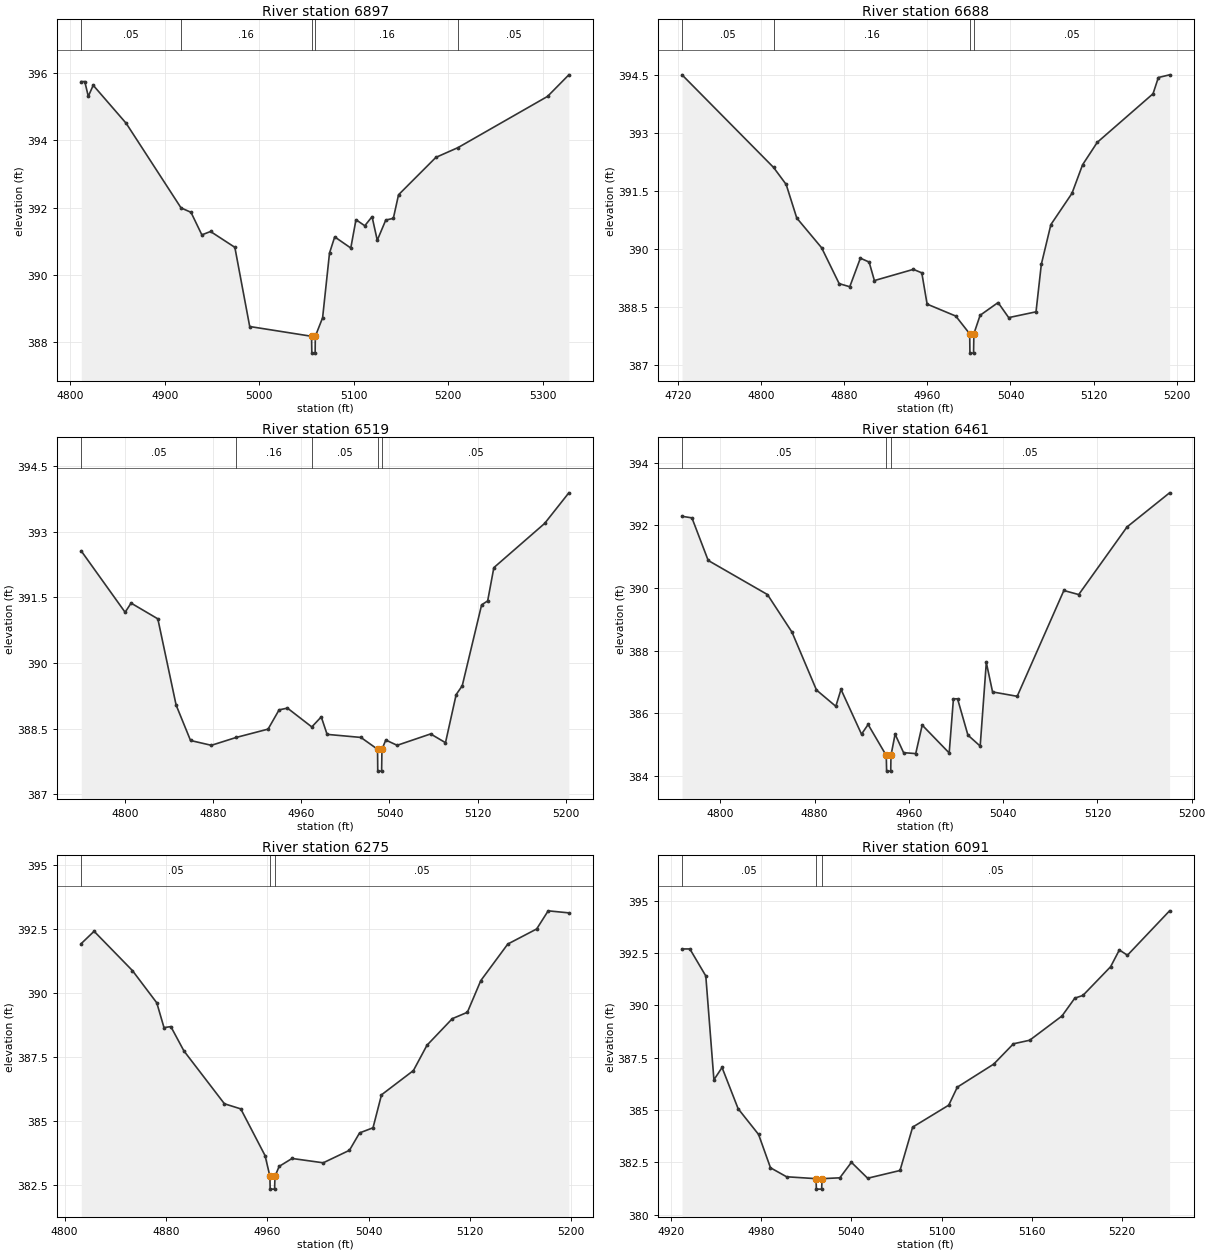
Type RM Length L Ch R = 1,6897,209,209,209
BEGIN DESCRIPTION:
South Twin Creek Trib I16897.37
END DESCRIPTION:
XS GIS Cut Line= 3
      2726608.04      6814944.04      2726425.84      6814992.83
      2726132.14      6815136.54
#Sta/Elev= 30
  4811.8  395.74  4815.5  395.74  4819.2  395.30  4824.4  395.63  4859.3  394.50
  4917.3  391.99  4927.8  391.86  4939.3  391.19  4948.5  391.29  4974.2  390.82
  4989.9  388.47  5055.3  388.18  5055.6  387.68  5059.1  387.68  5059.3  388.18
  5067.0  388.73  5074.3  390.65  5079.8  391.13  5096.8  390.80  5102.3  391.64
  5111.6  391.46  5119.3  391.73  5124.8  391.03  5133.8  391.63  5141.8  391.68
  5147.3  392.38  5186.8  393.49  5210.2  393.78  5304.9  395.30  5327.4  395.94
#Mann=5,-1,0
  4811.8    0.05       0  4917.3    0.16       0  5055.3    0.07       0
  5059.3    0.16       0  5210.2    0.05       0
Bank Sta=5055.3,5059.3
Exp/Cntr=0.3,0.1

Type RM Length L Ch R = 1,6688,169,169,169
BEGIN DESCRIPTION:
South Twin Creek Trib I16687.69
END DESCRIPTION:
XS GIS Cut Line= 3
      2726554.20      6814809.66      2726280.88      6814864.97
      2726093.61      6814898.47
#Sta/Elev= 30
  4724.0  394.51  4812.1  392.11  4824.2  391.67  4834.4  390.80  4858.3  390.03
  4875.2  389.10  4885.4  389.02  4895.6  389.76  4904.0  389.66  4909.1  389.18
  4946.6  389.47  4954.7  389.38  4959.8  388.57  4987.4  388.26  5000.8  387.80
  5001.0  387.30  5004.5  387.30  5004.8  387.80  5010.8  388.28  5028.1  388.61
  5038.3  388.22  5064.6  388.37  5069.7  389.60  5078.9  390.63  5099.2  391.44
  5109.4  392.18  5123.5  392.76  5177.2  394.02  5182.3  394.44  5193.1  394.51
#Mann=4,-1,0
  4724.0    0.05       0  4812.1    0.16       0  5000.8    0.07       0
  5004.8    0.05       0
Bank Sta=5000.8,5004.8
Exp/Cntr=0.3,0.1

Type RM Length L Ch R = 1,6519,58,58,58
BEGIN DESCRIPTION:
South Twin Creek Trib I16518.87
END DESCRIPTION:
XS GIS Cut Line= 5
      2726516.06      6814751.43      2726391.28      6814701.95
      2726335.13      6814706.05      2726287.87      6814723.35
      2726103.88      6814806.33
#Sta/Elev= 30
  4760.2  392.56  4800.0  391.16  4805.4  391.37  4829.7  391.01  4846.3  389.04
  4859.4  388.23  4878.3  388.12  4900.9  388.30  4929.8  388.49  4939.8  388.93
  4947.4  388.97  4969.5  388.54  4978.1  388.77  4983.4  388.37  5014.1  388.30
  5029.2  388.03  5029.4  387.53  5032.9  387.53  5033.2  388.03  5036.7  388.24
  5047.0  388.12  5077.4  388.38  5090.9  388.18  5100.6  389.28  5106.1  389.48
  5123.7  391.33  5129.2  391.42  5134.8  392.18  5180.9  393.19  5202.9  393.89
#Mann=5,-1,0
  4760.2    0.05       0  4900.9    0.16       0  4969.5    0.05       0
  5029.2    0.05       0  5033.2    0.05       0
Bank Sta=5029.2,5033.2
Exp/Cntr=0.3,0.1

Type RM Length L Ch R = 1,6461,186,186,186
BEGIN DESCRIPTION:
South Twin Creek Trib I16460.99
END DESCRIPTION:
XS GIS Cut Line= 5
      2726449.65      6814523.66      2726368.26      6814625.65
      2726274.44      6814668.92      2726181.89      6814697.06
      2726100.84      6814715.67
#Sta/Elev= 30
  4767.5  392.29  4775.9  392.24  4789.7  390.88  4840.0  389.79  4860.8  388.59
  4881.6  386.74  4898.0  386.22  4902.4  386.76  4919.8  385.33  4925.4  385.64
  4940.8  384.65  4941.1  384.15  4944.6  384.15  4944.8  384.65  4948.3  385.33
  4955.5  384.74  4965.8  384.71  4971.3  385.62  4994.2  384.73  4997.8  386.46
  5001.3  386.46  5010.1  385.30  5020.5  384.95  5025.7  387.62  5031.0  386.68
  5051.9  386.54  5091.5  389.92  5104.1  389.79  5145.1  391.95  5181.2  393.04
#Mann=3,-1,0
  4767.5    0.05       0  4940.8    0.05       0  4944.8    0.05       0
Bank Sta=4940.8,4944.8
Exp/Cntr=0.3,0.1

Type RM Length L Ch R = 1,6275,184,184,184
BEGIN DESCRIPTION:
South Twin Creek Trib I16274.98
END DESCRIPTION:
XS GIS Cut Line= 3
      2726401.87      6814433.00      2726224.86      6814499.20
      2726040.65      6814565.89
#Sta/Elev= 30
  4813.2  391.93  4823.3  392.41  4853.6  390.87  4872.8  389.61  4878.5  388.64
  4883.9  388.68  4894.2  387.73  4926.2  385.66  4939.1  385.46  4958.3  383.63
  4962.1  382.82  4962.3  382.32  4965.8  382.32  4966.1  382.82  4969.4  383.21
  4979.6  383.52  5004.2  383.35  5024.9  383.84  5032.9  384.52  5043.5  384.72
  5050.2  386.01  5075.4  386.96  5086.1  387.95  5106.1  388.99  5118.0  389.24
  5128.6  390.48  5149.9  391.91  5172.7  392.50  5181.8  393.21  5198.1  393.13
#Mann=3,-1,0
  4813.2    0.05       0  4962.1    0.05       0  4966.1    0.05       0
Bank Sta=4962.1,4966.1
Exp/Cntr=0.3,0.1

Type RM Length L Ch R = 1,6091,237,237,237
BEGIN DESCRIPTION:
South Twin Creek Trib I16091.07
END DESCRIPTION:
XS GIS Cut Line= 3
      2726290.66      6814288.14      2726221.06      6814315.76
      2725989.64      6814408.25
#Sta/Elev= 30
  4927.5  392.69  4932.7  392.69  4943.3  391.40  4948.7  386.44  4954.1  387.03
  4964.8  385.06  4978.4  383.83  4986.3  382.24  4997.0  381.81  5016.6  381.72
  5016.8  381.22  5020.3  381.22  5020.6  381.72  5032.4  381.76  5040.1  382.50
  5050.9  381.74  5072.4  382.11  5080.8  384.18  5104.8  385.23  5110.5  386.09
  5134.7  387.19  5147.8  388.16  5158.6  388.33  5180.1  389.49  5188.6  390.34
  5194.0  390.47  5212.4  391.84  5218.2  392.64  5223.6  392.39  5251.6  394.51
#Mann=3,-1,0
  4927.5    0.05       0  5016.6    0.05       0  5020.6    0.05       0
Bank Sta=5016.6,5020.6
Exp/Cntr=0.3,0.1

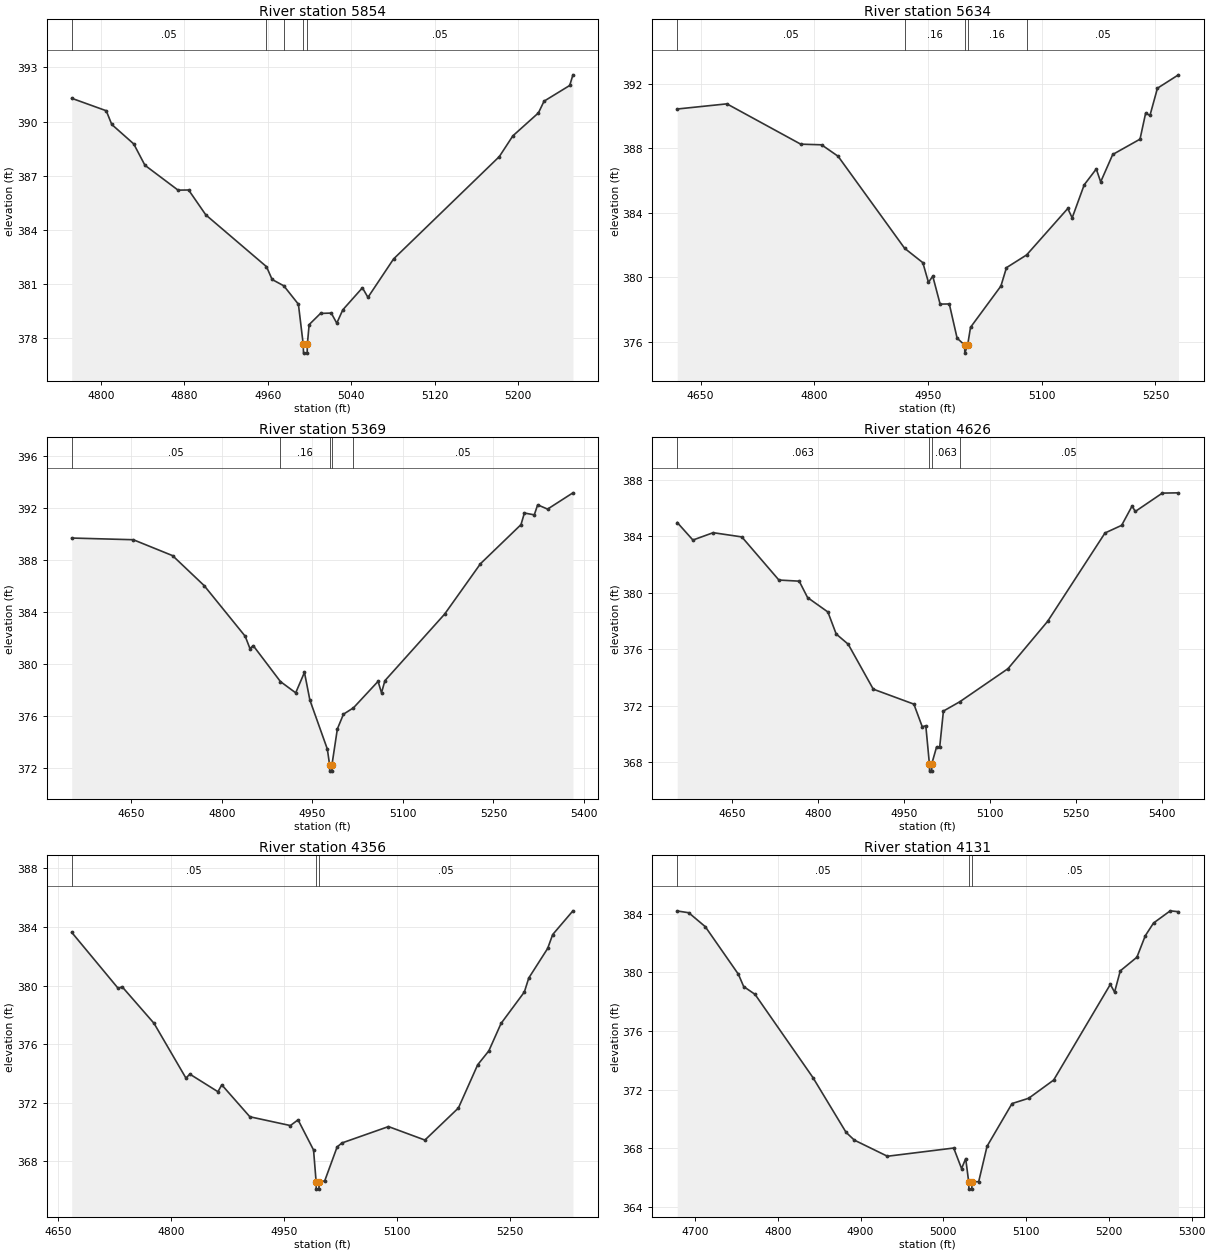
Type RM Length L Ch R = 1,5854,220,220,220
BEGIN DESCRIPTION:
South Twin Creek Trib I15853.63
END DESCRIPTION:
XS GIS Cut Line= 3
      2726392.52      6814055.67      2726174.00      6814127.41
      2725940.21      6814217.95
#Sta/Elev= 30
  4772.0  391.29  4805.1  390.60  4810.4  389.84  4831.5  388.76  4842.2  387.58
  4874.0  386.20  4884.1  386.21  4900.6  384.83  4958.8  381.96  4964.2  381.25
  4975.4  380.90  4989.4  379.88  4994.0  377.67  4994.3  377.17  4997.8  377.17
  4998.0  377.67  4999.7  378.75  5010.6  379.37  5020.9  379.39  5026.2  378.83
  5032.0  379.57  5050.8  380.79  5056.1  380.26  5080.7  382.39  5182.1  388.06
  5195.1  389.21  5219.6  390.48  5225.0  391.13  5249.6  392.00  5252.7  392.59
#Mann=5,-1,0
  4772.0    0.05       0  4958.8    0.16       0  4975.4    0.05       0
  4994.0    0.05       0  4998.0    0.05       0
Bank Sta=4994,4998
Exp/Cntr=0.3,0.1

Type RM Length L Ch R = 1,5634,265,265,265
BEGIN DESCRIPTION:
South Twin Creek Trib I15634.29
END DESCRIPTION:
XS GIS Cut Line= 3
      2726409.71      6813755.15      2726070.81      6813942.08
      2725831.84      6814076.47
#Sta/Elev= 30
  4619.2  390.42  4684.7  390.74  4782.1  388.24  4809.6  388.20  4831.4  387.49
  4919.2  381.78  4943.2  380.89  4950.6  379.67  4956.3  380.05  4966.0  378.32
  4978.1  378.33  4988.4  376.21  4998.3  375.78  4998.6  375.28  5002.3  375.78
  5006.1  376.88  5046.2  379.44  5053.5  380.58  5080.1  381.37  5134.4  384.25
  5140.2  383.67  5156.1  385.72  5172.0  386.70  5177.8  385.90  5193.7  387.60
  5229.7  388.55  5237.1  390.16  5242.8  390.02  5252.7  391.71  5280.4  392.54
#Mann=5,-1,0
  4619.2    0.05       0  4919.2    0.16       0  4998.3    0.07       0
  5002.3    0.16       0  5080.1    0.05       0
Bank Sta=4998.3,5002.3
Exp/Cntr=0.3,0.1

Type RM Length L Ch R = 1,5369,743,743,743
BEGIN DESCRIPTION:
South Twin Creek Trib I15369.48
END DESCRIPTION:
XS GIS Cut Line= 3
      2726389.51      6813527.50      2725975.10      6813707.45
      2725640.56      6813883.85
#Sta/Elev= 30
  4551.6  389.67  4653.6  389.54  4718.6  388.32  4770.9  386.02  4838.9  382.13
  4846.7  381.19  4852.2  381.41  4897.3  378.65  4922.5  377.79  4937.0  379.36
  4946.0  377.23  4974.9  373.47  4978.6  372.28  4978.9  371.78  4982.4  371.78
  4982.6  372.28  4991.5  375.02  5001.6  376.15  5018.2  376.64  5058.9  378.67
  5064.6  377.79  5070.2  378.72  5169.1  383.83  5228.5  387.70  5295.6  390.70
  5301.2  391.59  5317.6  391.45  5323.2  392.22  5339.6  391.89  5381.6  393.14
#Mann=5,-1,0
  4551.6    0.05       0  4897.3    0.16       0  4978.6    0.07       0
  4982.6    0.16       0  5018.2    0.05       0
Bank Sta=4978.6,4982.6
Exp/Cntr=0.3,0.1

Type RM Length L Ch R = 1,4626,270,270,270
BEGIN DESCRIPTION:
South Twin Creek Trib I14625.92
END DESCRIPTION:
XS GIS Cut Line= 3
      2726181.71      6812888.79      2725820.25      6813160.92
      2725432.65      6813325.92
#Sta/Elev= 30
  4554.3  384.97  4581.6  383.73  4617.0  384.25  4666.9  383.95  4731.5  380.90
  4766.9  380.82  4781.5  379.66  4816.9  378.64  4831.4  377.08  4852.3  376.36
  4896.0  373.18  4966.8  372.12  4981.4  370.52  4987.6  370.59  4993.9  367.88
  4994.2  367.38  4997.7  367.38  4997.9  367.88  5006.3  369.08  5011.8  369.08
  5018.3  371.63  5046.9  372.29  5130.9  374.63  5200.0  377.98  5300.0  384.23
  5329.0  384.77  5347.2  386.14  5352.7  385.75  5399.9  387.05  5428.0  387.07
#Mann=4,-1,0
  4554.3   0.063       0  4993.9   0.063       0  4997.9   0.063       0
  5046.9    0.05       0
Bank Sta=4993.9,4997.9
Exp/Cntr=0.3,0.1

Type RM Length L Ch R = 1,4356,225,225,225
BEGIN DESCRIPTION:
South Twin Creek Trib I14356.13
END DESCRIPTION:
XS GIS Cut Line= 3
      2726148.69      6812811.31      2725821.58      6812888.10
      2725510.60      6812997.61
#Sta/Elev= 30
  4668.5  383.64  4730.3  379.81  4735.4  379.93  4777.8  377.43  4820.2  373.69
  4825.4  373.96  4862.7  372.76  4867.8  373.23  4905.1  371.05  4958.9  370.45
  4969.1  370.84  4989.7  368.78  4993.1  366.61  4993.3  366.11  4996.8  366.11
  4997.1  366.61  5004.5  366.67  5021.0  368.99  5027.3  369.26  5089.2  370.38
  5137.6  369.46  5182.1  371.65  5207.7  374.60  5222.5  375.55  5238.7  377.42
  5269.7  379.57  5275.5  380.52  5300.6  382.54  5307.3  383.49  5334.2  385.11
#Mann=3,-1,0
  4668.5    0.05       0  4993.1    0.05       0  4997.1    0.05       0
Bank Sta=4993.1,4997.1
Exp/Cntr=0.3,0.1

Type RM Length L Ch R = 1,4131,279,279,279
BEGIN DESCRIPTION:
South Twin Creek Trib I14131.22
END DESCRIPTION:
XS GIS Cut Line= 3
      2726169.91      6812673.54      2725846.25      6812683.30
      2725566.13      6812714.86
#Sta/Elev= 30
  4678.4  384.18  4692.3  384.06  4712.3  383.11  4752.3  379.87  4758.7  379.03
  4772.4  378.50  4842.4  372.83  4882.4  369.10  4892.4  368.57  4932.4  367.47
  5012.5  368.03  5022.0  366.63  5027.0  367.31  5030.6  365.73  5030.9  365.23
  5034.4  365.23  5034.6  365.73  5042.7  365.74  5052.8  368.15  5083.0  371.06
  5103.1  371.42  5133.3  372.66  5201.8  379.18  5206.9  378.65  5213.8  380.10
  5233.9  381.03  5244.0  382.49  5254.0  383.36  5274.2  384.19  5284.1  384.13
#Mann=3,-1,0
  4678.4    0.05       0  5030.6    0.05       0  5034.6    0.05       0
Bank Sta=5030.6,5034.6
Exp/Cntr=0.3,0.1

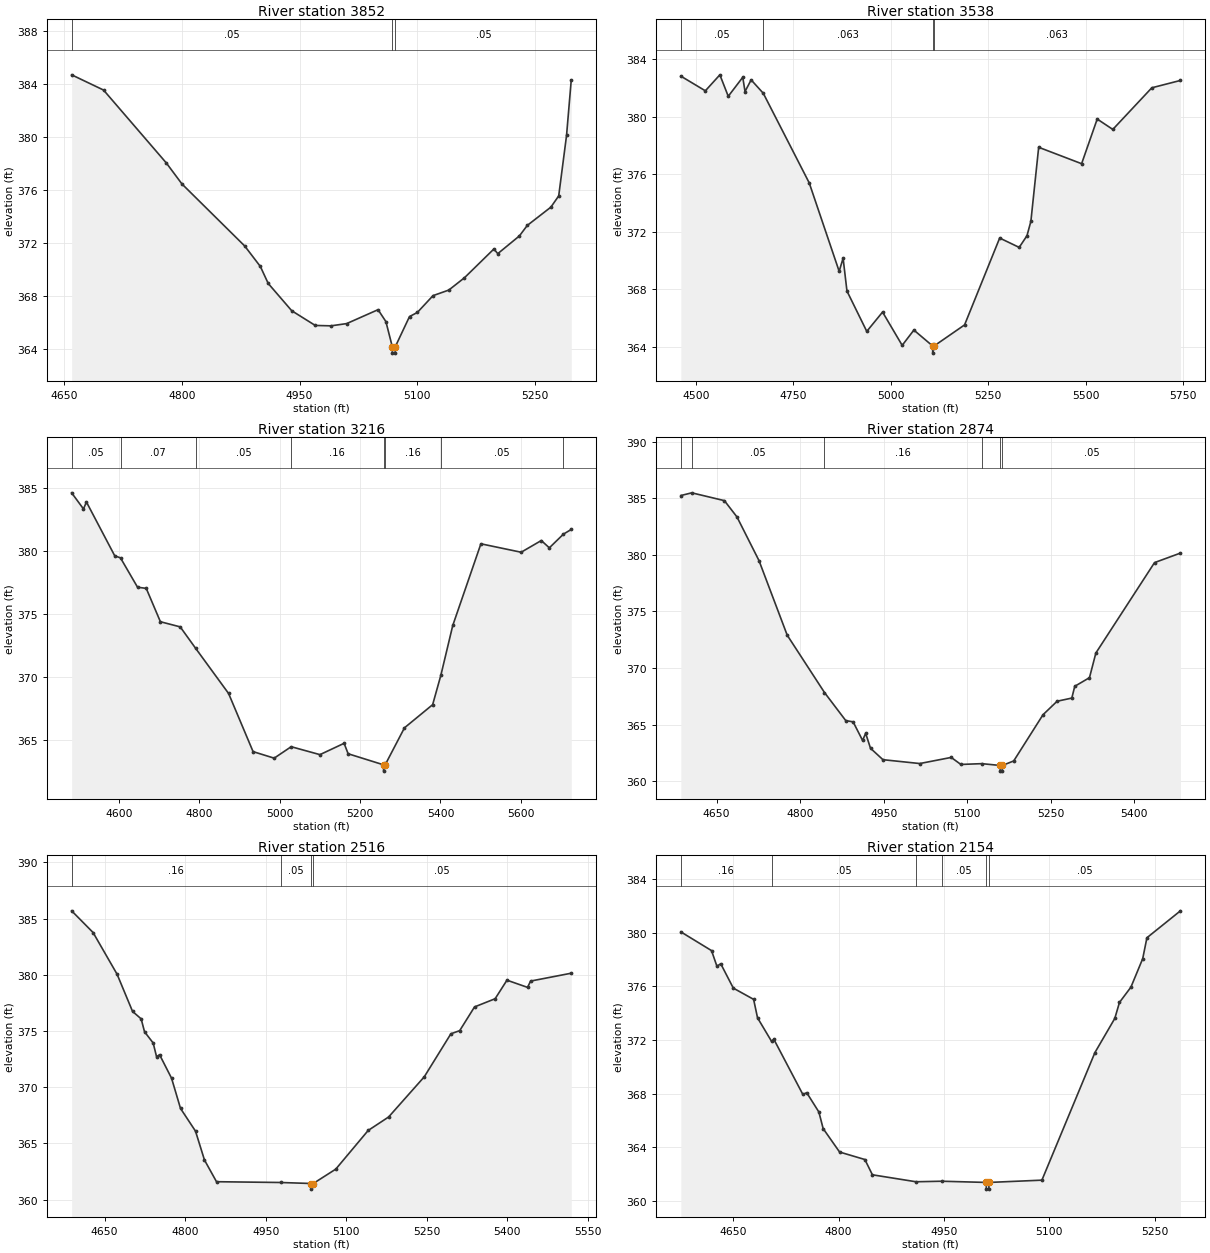
Type RM Length L Ch R = 1,3852,314,314,314
BEGIN DESCRIPTION:
South Twin Creek Trib I13852.11
END DESCRIPTION:
XS GIS Cut Line= 3
      2726216.65      6812435.64      2725878.68      6812427.75
      2725580.04      6812410.42
#Sta/Elev= 30
  4659.3  384.68  4700.0  383.53  4780.0  378.03  4800.0  376.44  4880.0  371.76
  4900.0  370.21  4910.0  368.93  4940.0  366.87  4970.0  365.76  4990.0  365.73
  5010.1  365.90  5050.1  366.95  5060.1  366.05  5068.2  364.17  5068.4  363.67
  5071.9  363.67  5072.2  364.17  5090.2  366.43  5100.2  366.74  5120.2  368.01
  5140.3  368.43  5160.3  369.36  5197.8  371.53  5202.8  371.18  5230.4  372.52
  5240.4  373.31  5270.5  374.69  5280.5  375.54  5290.5  380.10  5296.5  384.29
#Mann=3,-1,0
  4659.3    0.05       0  5068.2    0.05       0  5072.2    0.05       0
Bank Sta=5068.2,5072.2
Exp/Cntr=0.3,0.1

Type RM Length L Ch R = 1,3538,322,322,322
BEGIN DESCRIPTION:
South Twin Creek Trib I13538.25
END DESCRIPTION:
XS GIS Cut Line= 4
      2726316.25      6812327.13      2726031.94      6812161.17
      2725815.09      6812128.40      2725082.58      6812139.02
#Sta/Elev= 30
  4461.8  382.81  4524.7  381.79  4561.9  382.90  4583.4  381.41  4620.6  382.73
  4626.4  381.74  4642.1  382.55  4673.2  381.62  4791.0  375.40  4867.8  369.26
  4877.9  370.17  4887.8  367.89  4938.6  365.09  4979.1  366.43  5029.4  364.12
  5059.4  365.18  5107.4  364.08  5107.7  363.58  5111.4  364.08  5189.4  365.54
  5279.4  371.57  5329.4  370.92  5349.4  371.73  5359.4  372.73  5379.4  377.87
  5489.5  376.73  5529.5  379.83  5569.5  379.11  5669.5  382.00  5742.9  382.51
#Mann=4,-1,0
  4461.8    0.05       0  4673.2   0.063       0  5107.4   0.063       0
  5111.4   0.063       0
Bank Sta=5107.4,5111.4
Exp/Cntr=0.3,0.1

Type RM Length L Ch R = 1,3216,342,342,342
BEGIN DESCRIPTION:
South Twin Creek Trib I13216.38
END DESCRIPTION:
XS GIS Cut Line= 5
      2726200.19      6811503.59      2725895.36      6811839.33
      2725844.10      6811893.55      2725784.99      6811906.03
      2725131.53      6811932.34
#Sta/Elev= 30
  4482.8  384.62  4512.2  383.34  4519.6  383.89  4589.9  379.62  4604.3  379.45
  4646.7  377.12  4668.3  377.03  4703.5  374.38  4752.8  373.97  4791.3  372.26
  4873.1  368.68  4934.0  364.06  4986.5  363.54  5028.8  364.45  5100.3  363.82
  5160.4  364.72  5170.4  363.89  5258.5  363.01  5258.7  362.51  5262.5  363.01
  5310.5  365.95  5380.6  367.79  5400.9  370.11  5430.6  374.08  5500.6  380.57
  5600.7  379.90  5650.8  380.83  5670.8  380.25  5705.9  381.34  5725.3  381.71
#Mann=8,-1,0
  4482.8    0.05       0  4604.3    0.07       0  4791.3    0.05       0
  5028.8    0.16       0  5258.5    0.05       0  5262.5    0.16       0
  5400.9    0.05       0  5705.9   0.063       0
Bank Sta=5258.5,5262.5
Exp/Cntr=0.3,0.1

Type RM Length L Ch R = 1,2874,358,358,358
BEGIN DESCRIPTION:
South Twin Creek Trib I12874.3
END DESCRIPTION:
XS GIS Cut Line= 3
      2725992.23      6811482.22      2725615.19      6811665.65
      2725161.89      6811816.08
#Sta/Elev= 30
  4585.8  385.23  4605.4  385.47  4664.0  384.78  4686.6  383.34  4726.1  379.49
  4776.8  372.90  4843.7  367.84  4881.9  365.36  4895.1  365.25  4912.1  363.61
  4917.6  364.24  4926.3  362.92  4948.6  361.91  5014.8  361.57  5071.2  362.11
  5088.5  361.49  5126.2  361.56  5159.0  361.40  5159.2  360.90  5162.7  360.90
  5163.0  361.40  5183.4  361.80  5236.0  365.88  5261.3  367.07  5287.7  367.35
  5293.0  368.39  5319.4  369.15  5330.9  371.33  5436.2  379.31  5482.7  380.15
#Mann=6,-1,0
  4585.8    0.07       0  4605.4    0.05       0  4843.7    0.16       0
  5126.2    0.05       0  5159.0    0.07       0  5163.0    0.05       0
Bank Sta=5159,5163
Exp/Cntr=0.3,0.1

Type RM Length L Ch R = 1,2516,362,362,362
BEGIN DESCRIPTION:
South Twin Creek Trib I12516.45
END DESCRIPTION:
XS GIS Cut Line= 3
      2725881.60      6811214.66      2725506.62      6811403.35
      2725055.54      6811642.20
#Sta/Elev= 30
  4588.8  385.69  4628.7  383.76  4673.4  380.05  4702.2  376.74  4718.2  376.08
  4724.5  374.93  4740.6  373.93  4746.9  372.71  4752.5  372.89  4774.8  370.80
  4791.5  368.11  4819.4  366.09  4836.1  363.52  4858.5  361.59  4978.0  361.52
  5034.6  361.43  5034.8  360.93  5038.6  361.43  5080.6  362.71  5140.9  366.15
  5179.0  367.35  5245.3  370.92  5294.9  374.75  5311.3  375.03  5338.9  377.14
  5377.3  377.87  5399.3  379.52  5437.6  378.88  5443.3  379.44  5519.0  380.14
#Mann=4,-1,0
  4588.8    0.16       0  4978.0    0.05       0  5034.6    0.05       0
  5038.6    0.05       0
Bank Sta=5034.6,5038.6
Exp/Cntr=0.3,0.1

Type RM Length L Ch R = 1,2154,461,461,461
BEGIN DESCRIPTION:
South Twin Creek Trib I12154.39
END DESCRIPTION:
XS GIS Cut Line= 3
      2725816.03      6810924.53      2725421.57      6811097.18
      2725167.34      6811215.95
#Sta/Elev= 30
  4575.4  380.08  4619.1  378.68  4626.8  377.51  4632.2  377.70  4650.1  375.88
  4679.0  375.04  4684.6  373.66  4704.6  371.90  4707.8  372.06  4749.1  367.94
  4754.6  368.07  4771.9  366.63  4778.0  365.39  4801.4  363.64  4837.4  363.08
  4848.1  361.94  4910.2  361.42  4946.7  361.46  5010.1  361.37  5010.4  360.87
  5013.9  360.87  5014.1  361.37  5089.4  361.54  5164.9  371.07  5193.2  373.62
  5199.8  374.81  5216.1  375.95  5232.9  378.08  5238.9  379.64  5286.6  381.65
#Mann=6,-1,0
  4575.4    0.16       0  4704.6    0.05       0  4910.2    0.16       0
  4946.7    0.05       0  5010.1    0.05       0  5014.1    0.05       0
Bank Sta=5010.1,5014.1
Exp/Cntr=0.3,0.1

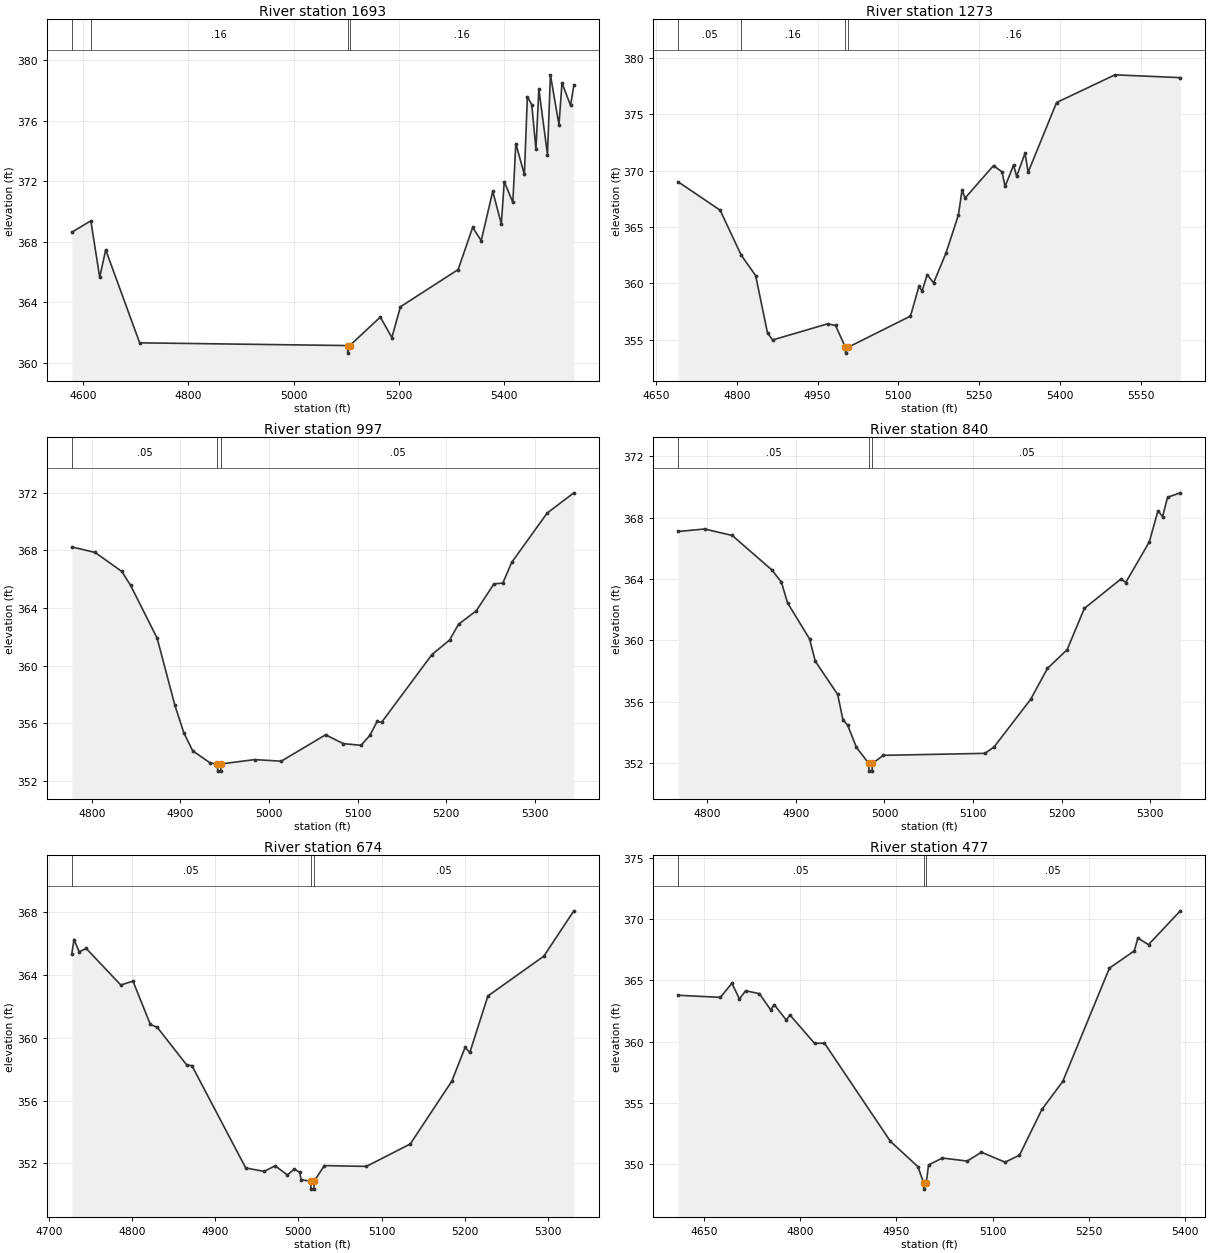
Type RM Length L Ch R = 1,1693,420,420,420
BEGIN DESCRIPTION:
South Twin Creek Trib I11692.81
END DESCRIPTION:
XS GIS Cut Line= 3
      2725864.89      6810562.53      2725472.78      6810730.02
      2725005.28      6810978.88
#Sta/Elev= 30
  4577.8  368.63  4614.1  369.39  4631.0  365.66  4642.4  367.47  4707.1  361.33
  5103.1  361.15  5103.3  360.65  5107.1  361.15  5165.3  363.03  5187.3  361.68
  5203.6  363.71  5313.5  366.17  5341.1  368.95  5357.4  368.08  5379.4  371.34
  5395.7  369.18  5401.3  371.98  5417.6  370.61  5423.3  374.49  5439.6  372.45
  5445.3  377.58  5453.7  377.06  5461.6  374.12  5467.2  378.08  5483.6  373.76
  5489.2  379.03  5505.5  375.72  5511.2  378.50  5527.5  377.01  5533.8  378.33
#Mann=4,-1,0
  4577.8    0.12       0  4614.1    0.16       0  5103.1    0.07       0
  5107.1    0.16       0
Bank Sta=5103.1,5107.1
Exp/Cntr=0.3,0.1

Type RM Length L Ch R = 1,1273,276,276,276
BEGIN DESCRIPTION:
South Twin Creek Trib I11273.32
END DESCRIPTION:
XS GIS Cut Line= 3
      2725820.79      6810340.19      2725543.88      6810486.98
      2725011.57      6810801.89
#Sta/Elev= 30
  4691.5  369.01  4769.2  366.50  4808.2  362.52  4835.2  360.68  4857.2  355.59
  4866.7  354.97  4968.6  356.40  4983.5  356.26  5001.9  354.30  5002.1  353.80
  5005.9  354.30  5122.6  357.09  5138.3  359.74  5144.1  359.31  5153.5  360.77
  5165.5  360.04  5188.4  362.68  5211.6  366.08  5218.2  368.27  5224.0  367.58
  5276.7  370.46  5292.4  369.90  5298.2  368.61  5313.8  370.49  5319.6  369.51
  5335.2  371.56  5341.0  369.87  5393.7  376.06  5502.1  378.52  5623.4  378.27
#Mann=4,-1,0
  4691.5    0.05       0  4808.2    0.16       0  5001.9    0.07       0
  5005.9    0.16       0
Bank Sta=5001.9,5005.9
Exp/Cntr=0.3,0.1

Type RM Length L Ch R = 1,997,157,157,157
BEGIN DESCRIPTION:
South Twin Creek Trib I1997.04
END DESCRIPTION:
XS GIS Cut Line= 3
      2725802.41      6810256.27      2725578.05      6810261.86
      2725235.88      6810273.36
#Sta/Elev= 30
  4777.4  368.24  4803.8  367.85  4833.8  366.54  4843.8  365.57  4873.8  361.90
  4893.8  357.25  4903.9  355.34  4913.9  354.09  4933.9  353.24  4941.9  353.18
  4942.1  352.68  4945.6  352.68  4945.9  353.18  4983.9  353.48  5013.9  353.37
  5063.9  355.20  5083.9  354.59  5103.9  354.47  5113.9  355.16  5122.1  356.13
  5127.1  356.06  5184.0  360.77  5204.0  361.78  5214.0  362.87  5234.0  363.80
  5254.0  365.67  5264.0  365.73  5274.0  367.16  5314.1  370.59  5344.2  371.99
#Mann=3,-1,0
  4777.4    0.05       0  4941.9    0.05       0  4945.9    0.05       0
Bank Sta=4941.9,4945.9
Exp/Cntr=0.3,0.1

Type RM Length L Ch R = 1,840,166,166,166
BEGIN DESCRIPTION:
South Twin Creek Trib I1840.38
END DESCRIPTION:
XS GIS Cut Line= 3
      2725846.12      6810196.69      2725623.63      6810120.05
      2725302.00      6810041.11
#Sta/Elev= 30
  4767.3  367.10  4797.0  367.26  4828.2  366.84  4873.2  364.58  4883.8  363.78
  4890.6  362.45  4915.5  360.09  4921.9  358.64  4947.2  356.47  4953.1  354.83
  4958.4  354.47  4968.4  353.02  4982.3  351.97  4982.5  351.47  4986.0  351.47
  4986.3  351.97  4998.7  352.50  5113.4  352.63  5123.7  353.05  5164.9  356.15
  5183.9  358.17  5206.1  359.39  5225.5  362.08  5267.0  364.01  5272.2  363.77
  5298.8  366.42  5308.6  368.45  5313.8  368.07  5319.4  369.33  5333.8  369.62
#Mann=3,-1,0
  4767.3    0.05       0  4982.3    0.05       0  4986.3    0.05       0
Bank Sta=4982.3,4986.3
Exp/Cntr=0.3,0.1

Type RM Length L Ch R = 1,674,197,197,197
BEGIN DESCRIPTION:
South Twin Creek Trib I1674.34
END DESCRIPTION:
XS GIS Cut Line= 3
      2725851.56      6810118.86      2725629.35      6809953.50
      2725344.56      6809793.18
#Sta/Elev= 30
  4727.5  365.35  4730.2  366.27  4736.5  365.49  4744.9  365.70  4786.5  363.37
  4801.1  363.62  4822.0  360.86  4830.4  360.67  4865.8  358.27  4872.0  358.23
  4936.7  351.71  4958.8  351.49  4972.1  351.85  4986.8  351.26  4995.1  351.64
  5001.4  351.44  5003.5  350.96  5014.9  350.86  5015.2  350.36  5018.7  350.36
  5018.9  350.86  5031.3  351.86  5081.9  351.81  5134.6  353.24  5184.5  357.24
  5200.5  359.39  5206.2  359.07  5227.9  362.67  5295.2  365.21  5331.3  368.10
#Mann=3,-1,0
  4727.5    0.05       0  5014.9    0.05       0  5018.9    0.05       0
Bank Sta=5014.9,5018.9
Exp/Cntr=0.3,0.1

Type RM Length L Ch R = 1,477,331,331,331
BEGIN DESCRIPTION:
South Twin Creek Trib I1477.21
END DESCRIPTION:
XS GIS Cut Line= 3
      2725914.51      6810178.78      2725770.47      6809813.92
      2725422.91      6809635.37
#Sta/Elev= 30
  4609.8  363.79  4675.6  363.62  4693.4  364.77  4705.3  363.49  4714.9  364.16
  4736.4  363.92  4754.0  362.60  4759.4  363.03  4778.4  361.76  4783.8  362.19
  4822.4  359.87  4837.9  359.88  4940.7  351.87  4983.7  349.80  4992.5  348.47
  4992.7  347.97  4996.5  348.47  5000.2  349.94  5021.7  350.51  5060.4  350.26
  5082.6  350.98  5119.5  350.17  5142.0  350.74  5177.0  354.48  5209.5  356.76
  5282.3  366.01  5321.0  367.41  5326.6  368.46  5343.2  367.92  5392.8  370.68
#Mann=3,-1,0
  4609.8    0.05       0  4992.5    0.05       0  4996.5    0.05       0
Bank Sta=4992.5,4996.5
Exp/Cntr=0.3,0.1

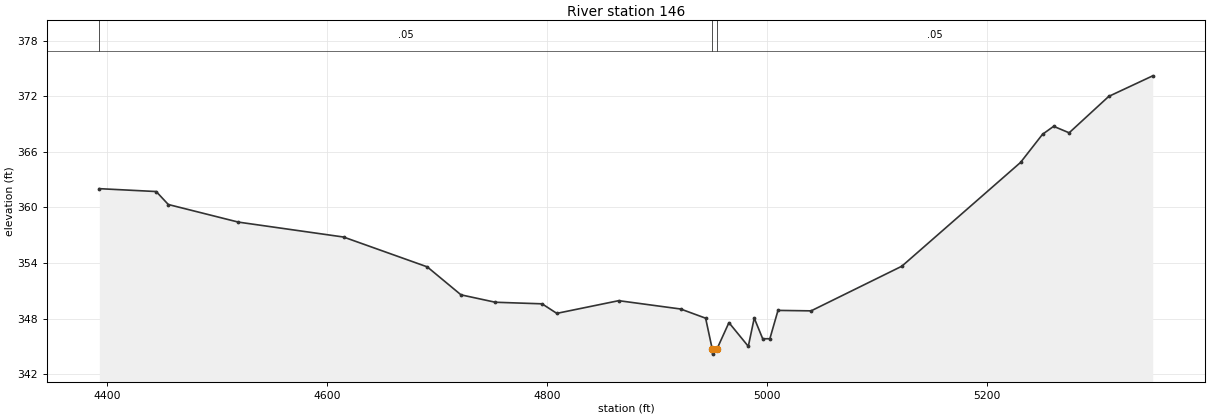
Type RM Length L Ch R = 1,146,0,0,0
BEGIN DESCRIPTION:
South Twin Creek Trib I1146.064
END DESCRIPTION:
XS GIS Cut Line= 3
      2726030.06      6810110.03      2725825.81      6809538.22
      2725476.05      6809561.00
#Sta/Elev= 30
  4392.8  362.02  4444.5  361.71  4455.5  360.31  4519.2  358.41  4614.8  356.80
  4690.9  353.58  4721.6  350.56  4752.8  349.76  4795.3  349.59  4808.7  348.56
  4865.0  349.93  4921.3  349.03  4944.0  348.04  4950.1  344.66  4950.3  344.16
  4954.1  344.66  4965.2  347.56  4982.8  345.00  4988.2  348.05  4995.9  345.82
  5002.4  345.82  5009.8  348.88  5039.9  348.83  5122.4  353.65  5230.3  364.85
  5250.3  367.89  5260.4  368.75  5274.5  368.05  5310.5  371.98  5350.5  374.20
#Mann=3,-1,0
  4392.8    0.05       0  4950.1    0.05       0  4954.1    0.05       0
Bank Sta=4950.1,4954.1
Exp/Cntr=0.3,0.1

Chan Stop Cuts=-1