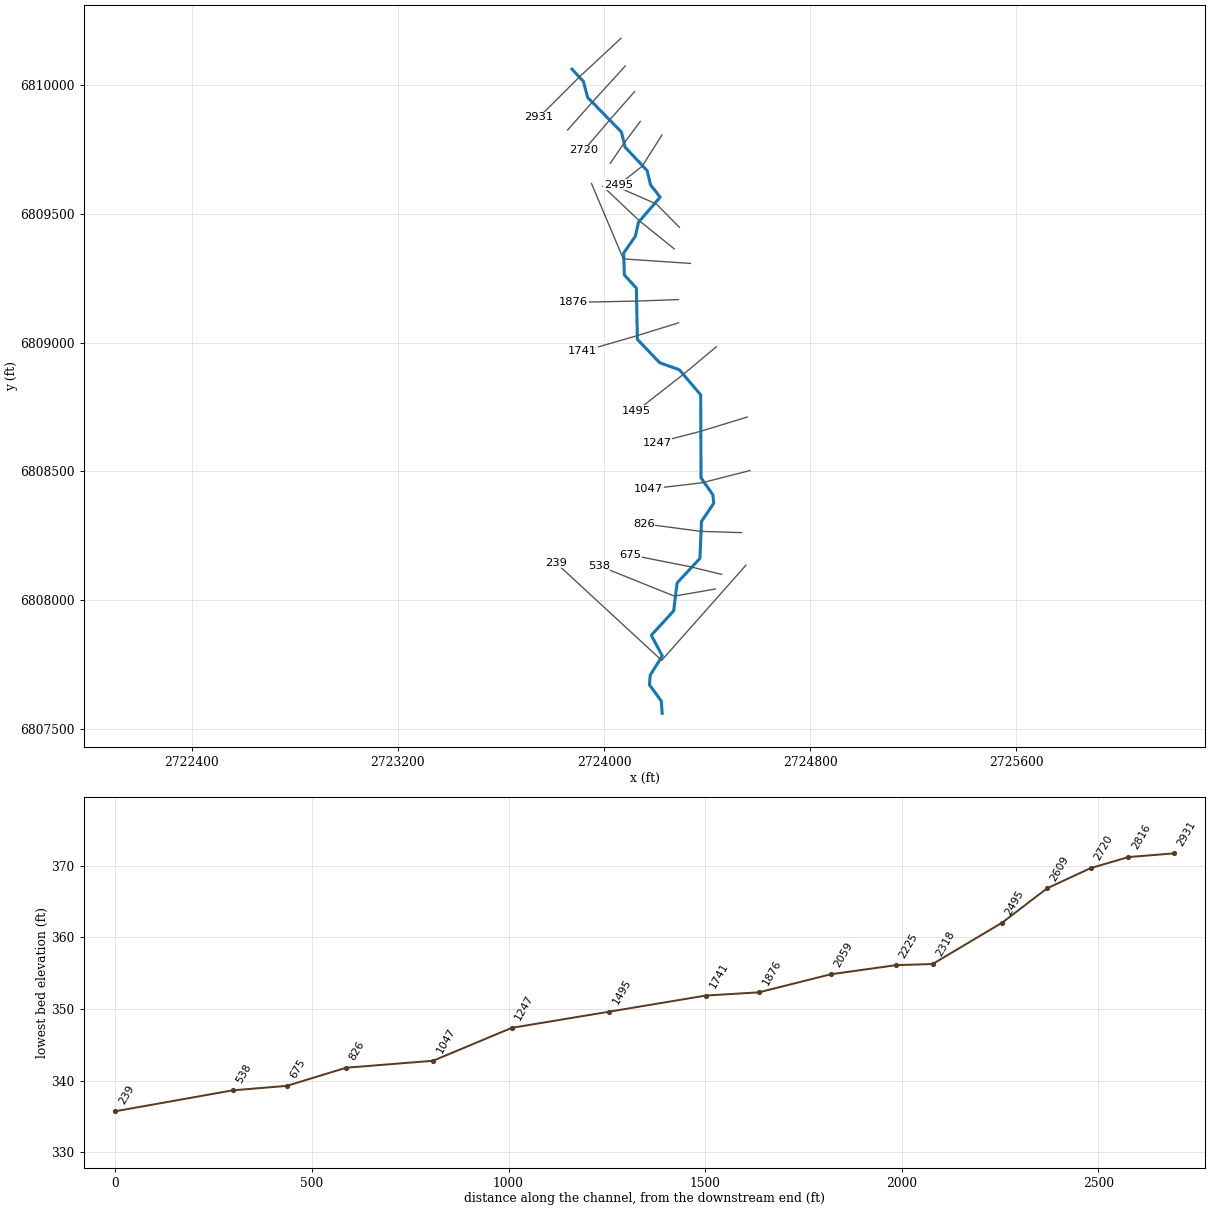
--- South Twin Creek Trib J.prj (project) ---

Proj Title=South Twin Creek Trib J Base Level Engineering
Current Plan=p01
Default Exp/Contr=0.3,0.1
English Units
Geom File=g01
Flow File=f01
Plan File=p01
BEGIN DESCRIPTION:
South Twin Creek Trib J
END DESCRIPTION:

--- South Twin Creek Trib J.p01 (plan) ---

Plan Title=Multiple Run
Short Identifier=Multiple
Geom File=g01
Flow File=f01
Subcritical Flow
K Sum by GR= 0
Std Step Tol= 0.01
Critical Tol= 0.01
Num of Std Step Trials= 20
Max Error Tol= 0.3
Flow Tol Ratio= 0.001
Split Flow NTrial= 30
Split Flow Tol= 0.02
Split Flow Ratio= 0.02
Log Output Level= 0
Friction Slope Method= 1
Unsteady Friction Slope Method= 2
Unsteady Bridges Friction Slope Method= 1
Parabolic Critical Depth
Global Vel Dist=  1 , 1 , 1
Global Log Level= 0
CheckData=True
Encroach Param= -1, 0, 0, 0
BEGIN DESCRIPTION:
Multiple Run
END DESCRIPTION:

--- South Twin Creek Trib J.f01 (steady flow) ---

Flow Title=Multiple
Number of Profiles=7
Profile Names=10-year,25-year,50-year,1pct_min,100-year,1pct_plu,500-year
River Rch & RM= South Twin Creek,Reach-1,2931
     167     207     237     136     271     541     352
River Rch & RM= South Twin Creek,Reach-1,1876
     253     322     374     216     432     862     575
Boundary for River Rch & Prof#=South Twin Creek,Reach-1,1
Up Type=0
Dn Type=3
Dn Slope=0.005
Boundary for River Rch & Prof#=South Twin Creek,Reach-1,2
Up Type=0
Dn Type=3
Dn Slope=0.005
Boundary for River Rch & Prof#=South Twin Creek,Reach-1,3
Up Type=0
Dn Type=3
Dn Slope=0.005
Boundary for River Rch & Prof#=South Twin Creek,Reach-1,4
Up Type=0
Dn Type=3
Dn Slope=0.005
Boundary for River Rch & Prof#=South Twin Creek,Reach-1,5
Up Type=0
Dn Type=3
Dn Slope=0.005
Boundary for River Rch & Prof#=South Twin Creek,Reach-1,6
Up Type=0
Dn Type=3
Dn Slope=0.005
Boundary for River Rch & Prof#=South Twin Creek,Reach-1,7
Up Type=0
Dn Type=3
Dn Slope=0.005

--- South Twin Creek Trib J.g01 (geometry) ---

Geom Title=Existing Conditions

River Reach=South Twin Creek,Reach-1
Reach XY= 30
      2723876.00      6810061.00      2723920.29      6810013.35
      2723936.70      6809951.29      2724067.84      6809817.05
      2724081.87      6809758.72      2724167.86      6809667.04
      2724180.46      6809612.65      2724218.16      6809564.23
      2724134.18      6809467.06      2724121.78      6809412.75
      2724076.52      6809347.05      2724079.19      6809262.40
      2724126.00      6809211.00      2724129.52      6809012.45
      2724216.30      6808921.77      2724292.71      6808894.36
      2724375.47      6808797.15      2724376.70      6808474.91
      2724422.63      6808409.26      2724425.91      6808376.39
      2724378.41      6808305.48      2724372.44      6808162.47
      2724283.88      6808067.16      2724270.45      6807958.57
      2724183.83      6807864.40      2724226.28      6807783.84
      2724179.39      6807709.28      2724176.63      6807671.67
      2724222.31      6807609.51      2724226.00      6807561.00

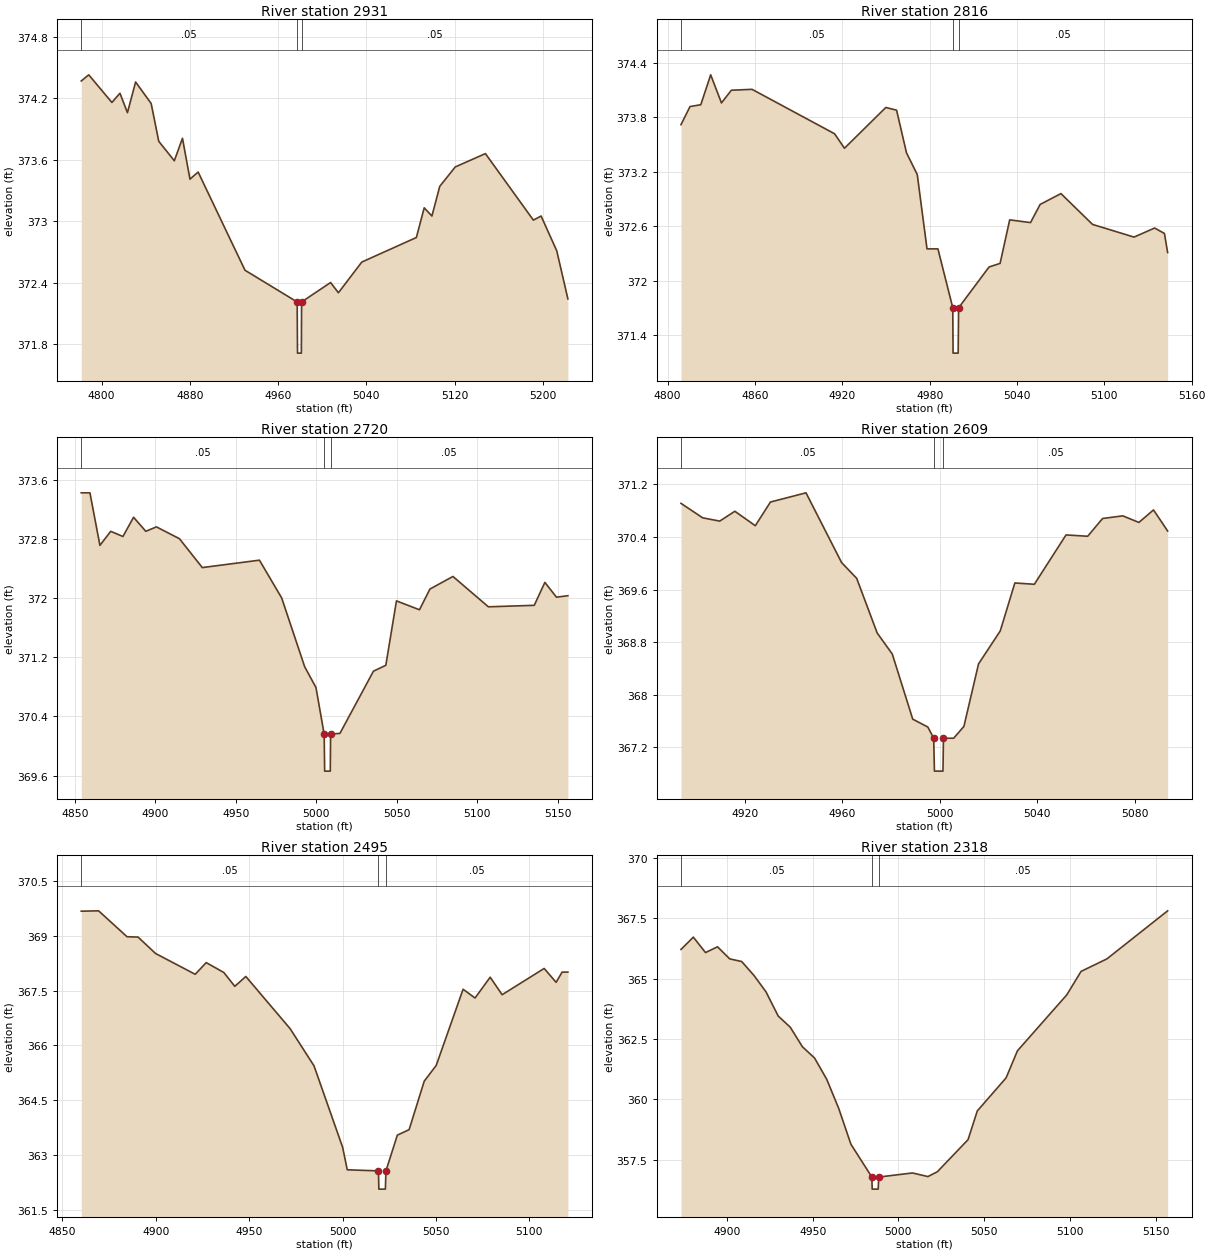
Type RM Length L Ch R = 1,2931,115,115,115
BEGIN DESCRIPTION:
South Twin Creek Trib J2930.904
END DESCRIPTION:
XS GIS Cut Line= 3
      2724065.91      6810180.65      2723905.85      6810031.91
      2723748.06      6809874.61
#Sta/Elev= 30
  4781.5  374.37  4788.3  374.43  4809.3  374.16  4816.6  374.25  4823.4  374.06
  4830.8  374.36  4844.9  374.15  4851.8  373.78  4865.9  373.59  4873.3  373.81
  4880.1  373.41  4887.5  373.48  4930.0  372.52  4977.3  372.21  4977.6  371.71
  4981.1  371.71  4981.3  372.21  5007.6  372.40  5014.7  372.30  5035.9  372.60
  5085.4  372.84  5092.5  373.13  5099.5  373.05  5106.6  373.34  5120.7  373.53
  5148.0  373.66  5191.5  373.01  5198.5  373.05  5212.7  372.71  5222.8  372.24
#Mann=3,-1,0
  4781.5    0.05       0  4977.3    0.05       0  4981.3    0.05       0
Bank Sta=4977.3,4981.3
Exp/Cntr=0.3,0.1

Type RM Length L Ch R = 1,2816,96,96,96
BEGIN DESCRIPTION:
South Twin Creek Trib J2816.19
END DESCRIPTION:
XS GIS Cut Line= 3
      2724082.76      6810073.25      2723953.68      6809931.68
      2723859.01      6809824.89
#Sta/Elev= 30
  4809.2  373.72  4815.4  373.92  4822.8  373.94  4829.6  374.27  4837.0  373.96
  4843.8  374.10  4858.0  374.11  4914.7  373.62  4921.5  373.46  4949.9  373.91
  4957.3  373.88  4964.1  373.41  4971.5  373.17  4978.2  372.35  4985.7  372.35
  4995.9  371.70  4996.1  371.20  4999.6  371.20  4999.9  371.70  5020.8  372.15
  5028.4  372.19  5035.0  372.67  5049.3  372.64  5055.9  372.84  5070.2  372.96
  5091.9  372.62  5120.4  372.48  5134.6  372.58  5141.3  372.52  5143.5  372.31
#Mann=3,-1,0
  4809.2    0.05       0  4995.9    0.05       0  4999.9    0.05       0
Bank Sta=4995.9,4999.9
Exp/Cntr=0.3,0.1

Type RM Length L Ch R = 1,2720,111,111,111
BEGIN DESCRIPTION:
South Twin Creek Trib J2719.63
END DESCRIPTION:
XS GIS Cut Line= 3
      2724119.25      6809974.08      2724021.74      6809863.30
      2723921.33      6809745.59
#Sta/Elev= 30
  4854.0  373.42  4859.4  373.42  4865.6  372.71  4872.3  372.90  4879.9  372.83
  4886.5  373.09  4894.1  372.90  4900.7  372.96  4915.0  372.80  4929.2  372.41
  4964.7  372.51  4978.5  372.00  4992.8  371.07  4999.8  370.79  5004.9  370.16
  5005.2  369.66  5008.7  369.66  5008.9  370.16  5014.7  370.17  5035.5  371.01
  5043.2  371.09  5049.8  371.96  5064.1  371.84  5070.6  372.12  5084.9  372.29
  5106.9  371.88  5135.4  371.90  5142.0  372.21  5149.2  372.01  5156.3  372.03
#Mann=3,-1,0
  4854.0    0.05       0  5004.9    0.05       0  5008.9    0.05       0
Bank Sta=5004.9,5008.9
Exp/Cntr=0.3,0.1

Type RM Length L Ch R = 1,2609,114,114,114
BEGIN DESCRIPTION:
South Twin Creek Trib J2608.72
END DESCRIPTION:
XS GIS Cut Line= 3
      2724140.95      6809858.10      2724075.72      6809770.87
      2724024.66      6809695.81
#Sta/Elev= 30
  4893.8  370.91  4902.7  370.69  4909.7  370.64  4915.9  370.79  4924.3  370.57
  4930.5  370.93  4945.1  371.07  4959.7  370.01  4965.9  369.77  4974.3  368.94
  4980.5  368.62  4988.9  367.63  4995.1  367.51  4997.5  367.34  4997.8  366.84
  5001.3  366.84  5001.5  367.34  5005.7  367.34  5009.9  367.52  5015.9  368.47
  5024.8  368.97  5030.8  369.70  5038.8  369.68  5051.8  370.43  5060.7  370.41
  5066.8  370.68  5075.1  370.72  5081.7  370.62  5087.7  370.81  5093.5  370.49
#Mann=3,-1,0
  4893.8    0.05       0  4997.5    0.05       0  5001.5    0.05       0
Bank Sta=4997.5,5001.5
Exp/Cntr=0.3,0.1

Type RM Length L Ch R = 1,2495,177,177,177
BEGIN DESCRIPTION:
South Twin Creek Trib J2494.51
END DESCRIPTION:
XS GIS Cut Line= 3
      2724224.89      6809805.49      2724148.32      6809684.24
      2724056.23      6809611.93
#Sta/Elev= 30
  4860.1  369.68  4869.4  369.69  4884.6  368.98  4890.5  368.97  4899.9  368.52
  4921.1  367.95  4927.0  368.27  4936.4  368.00  4942.3  367.62  4948.2  367.89
  4971.9  366.46  4984.7  365.44  5000.0  363.21  5002.5  362.59  5019.2  362.56
  5019.4  362.06  5022.9  362.06  5023.2  362.56  5029.3  363.54  5035.6  363.69
  5043.7  365.02  5050.1  365.45  5064.5  367.54  5070.9  367.30  5079.0  367.87
  5085.4  367.39  5107.9  368.11  5114.3  367.73  5117.5  368.01  5120.6  368.01
#Mann=3,-1,0
  4860.1    0.05       0  5019.2    0.05       0  5023.2    0.05       0
Bank Sta=5019.2,5023.2
Exp/Cntr=0.3,0.1

Type RM Length L Ch R = 1,2318,93,93,93
BEGIN DESCRIPTION:
South Twin Creek Trib J2342.65
END DESCRIPTION:
XS GIS Cut Line= 3
      2724292.62      6809447.45      2724203.51      6809537.66
      2724059.73      6809600.72
#Sta/Elev= 30
  4873.2  366.21  4880.4  366.72  4887.5  366.08  4894.5  366.32  4901.6  365.82
  4908.6  365.71  4915.8  365.13  4922.8  364.45  4929.9  363.45  4936.9  362.99
  4944.0  362.18  4951.1  361.71  4958.2  360.83  4965.2  359.62  4972.3  358.14
  4984.5  356.78  4984.7  356.28  4988.2  356.28  4988.5  356.78  5008.2  356.95
  5017.2  356.80  5022.7  357.00  5040.6  358.33  5046.0  359.52  5062.8  360.89
  5069.4  362.01  5098.2  364.33  5106.5  365.30  5121.6  365.82  5157.0  367.81
#Mann=3,-1,0
  4873.2    0.05       0  4984.5    0.05       0  4988.5    0.05       0
Bank Sta=4984.5,4988.5
Exp/Cntr=0.3,0.1

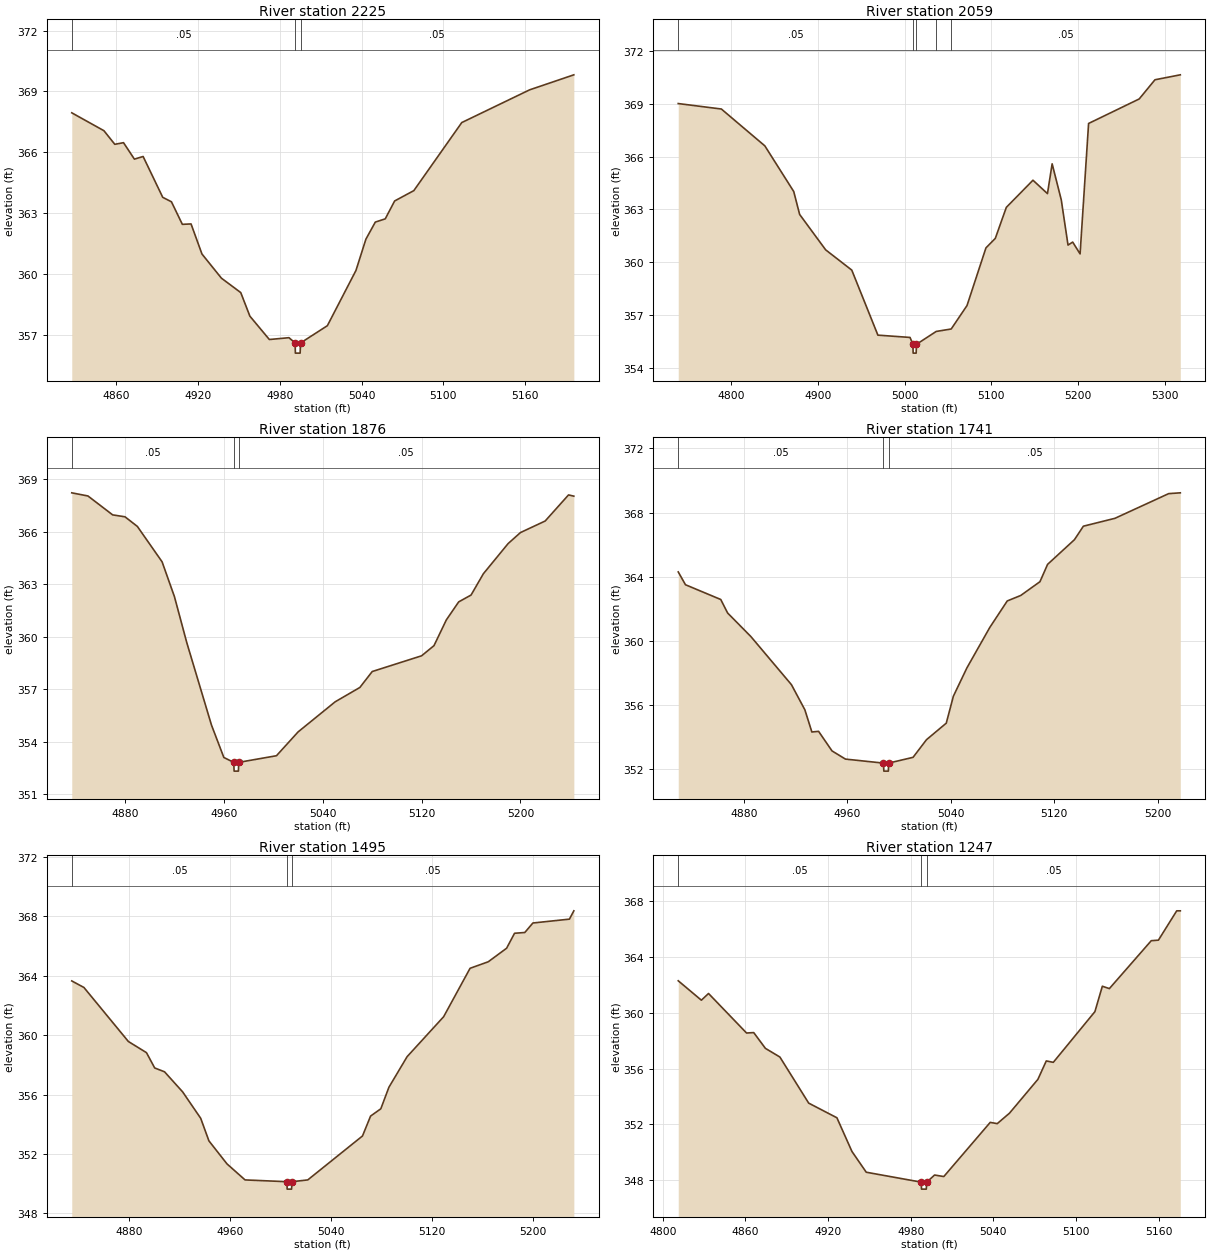
Type RM Length L Ch R = 1,2225,166,166,166
BEGIN DESCRIPTION:
South Twin Creek Trib J2225.23
END DESCRIPTION:
XS GIS Cut Line= 3
      2724272.61      6809363.80      2724136.77      6809473.23
      2723995.61      6809606.69
#Sta/Elev= 30
  4827.2  367.95  4850.8  367.07  4858.8  366.40  4865.2  366.48  4873.2  365.67
  4879.6  365.80  4894.0  363.79  4900.4  363.57  4908.4  362.46  4914.8  362.48
  4922.8  361.00  4937.1  359.81  4951.3  359.10  4958.0  357.94  4972.3  356.79
  4986.7  356.88  4991.2  356.62  4991.4  356.12  4994.9  356.12  4995.2  356.62
  5014.9  357.47  5035.9  360.19  5043.2  361.73  5050.1  362.57  5057.4  362.73
  5064.3  363.61  5078.4  364.12  5113.6  367.47  5163.4  369.08  5195.9  369.82
#Mann=3,-1,0
  4827.2    0.05       0  4991.2    0.05       0  4995.2    0.05       0
Bank Sta=4991.2,4995.2
Exp/Cntr=0.3,0.1

Type RM Length L Ch R = 1,2059,183,183,183
BEGIN DESCRIPTION:
South Twin Creek Trib J2059.03
END DESCRIPTION:
XS GIS Cut Line= 3
      2724335.56      6809307.14      2724075.25      6809324.73
      2723951.54      6809617.35
#Sta/Elev= 30
  4739.1  369.01  4788.8  368.70  4838.9  366.61  4872.2  364.02  4879.0  362.72
  4909.0  360.71  4939.1  359.56  4969.2  355.87  5006.2  355.74  5009.6  355.35
  5009.8  354.85  5013.3  354.85  5013.6  355.35  5036.4  356.08  5053.7  356.22
  5071.9  357.55  5093.7  360.82  5104.5  361.36  5117.2  363.12  5147.9  364.66
  5164.6  363.90  5170.0  365.59  5180.5  363.55  5188.3  360.98  5193.7  361.15
  5202.2  360.48  5212.0  367.88  5270.3  369.27  5288.5  370.36  5317.7  370.64
#Mann=5,-1,0
  4739.1    0.05       0  5009.6    0.05       0  5013.6    0.05       0
  5036.4   0.033       0  5053.7    0.05       0
Bank Sta=5009.6,5013.6
Exp/Cntr=0.3,0.1

Type RM Length L Ch R = 1,1876,135,135,135
BEGIN DESCRIPTION:
South Twin Creek Trib J1876.347
END DESCRIPTION:
XS GIS Cut Line= 3
      2724289.05      6809166.75      2724126.00      6809161.00
      2723882.81      6809155.99
#Sta/Elev= 30
  4836.8  368.23  4849.9  368.05  4869.9  366.97  4879.9  366.86  4889.9  366.31
  4909.9  364.29  4919.9  362.30  4929.9  359.67  4949.9  354.96  4959.9  353.11
  4967.9  352.83  4968.2  352.33  4971.7  352.33  4971.9  352.83  5002.5  353.21
  5020.0  354.57  5050.0  356.29  5070.0  357.11  5080.0  358.02  5120.0  358.92
  5130.0  359.50  5140.0  360.97  5150.0  362.00  5160.0  362.39  5170.0  363.61
  5190.0  365.33  5200.0  365.96  5220.0  366.62  5238.9  368.11  5243.2  368.04
#Mann=3,-1,0
  4836.8    0.05       0  4967.9    0.05       0  4971.9    0.05       0
Bank Sta=4967.9,4971.9
Exp/Cntr=0.3,0.1

Type RM Length L Ch R = 1,1741,246,246,246
BEGIN DESCRIPTION:
South Twin Creek Trib J1741.39
END DESCRIPTION:
XS GIS Cut Line= 3
      2724289.64      6809076.63      2724126.49      6809026.07
      2723917.34      6808965.67
#Sta/Elev= 30
  4829.1  364.30  4834.7  363.50  4862.0  362.58  4867.3  361.74  4885.3  360.27
  4916.7  357.27  4927.1  355.70  4932.5  354.32  4937.7  354.36  4948.1  353.14
  4958.5  352.63  4987.9  352.38  4988.2  351.88  4991.7  351.88  4991.9  352.38
  5010.8  352.74  5021.2  353.84  5036.5  354.87  5042.0  356.55  5052.5  358.32
  5070.2  360.84  5083.7  362.49  5094.1  362.83  5109.0  363.69  5114.9  364.77
  5135.7  366.31  5142.6  367.15  5167.0  367.64  5208.6  369.18  5217.6  369.23
#Mann=3,-1,0
  4829.1    0.05       0  4987.9    0.05       0  4991.9    0.05       0
Bank Sta=4987.9,4991.9
Exp/Cntr=0.3,0.1

Type RM Length L Ch R = 1,1495,248,248,248
BEGIN DESCRIPTION:
South Twin Creek Trib J1494.6
END DESCRIPTION:
XS GIS Cut Line= 3
      2724436.28      6808983.94      2724308.62      6808877.05
      2724126.94      6808734.88
#Sta/Elev= 30
  4834.9  363.65  4844.5  363.21  4879.7  359.57  4894.0  358.82  4900.5  357.79
  4908.3  357.53  4922.6  356.18  4936.9  354.40  4943.4  352.88  4957.7  351.33
  4972.0  350.25  5005.1  350.13  5005.3  349.63  5008.8  349.63  5009.1  350.13
  5021.6  350.25  5064.9  353.21  5071.3  354.55  5079.4  355.04  5085.8  356.49
  5100.2  358.55  5129.1  361.24  5150.0  364.50  5164.4  364.94  5178.9  365.85
  5185.2  366.86  5193.3  366.91  5199.7  367.55  5228.6  367.81  5232.1  368.37
#Mann=3,-1,0
  4834.9    0.05       0  5005.1    0.05       0  5009.1    0.05       0
Bank Sta=5005.1,5009.1
Exp/Cntr=0.3,0.1

Type RM Length L Ch R = 1,1247,200,200,200
BEGIN DESCRIPTION:
South Twin Creek Trib J1247.38
END DESCRIPTION:
XS GIS Cut Line= 3
      2724556.59      6808711.04      2724372.23      6808654.79
      2724205.91      6808611.94
#Sta/Elev= 30
  4811.2  362.29  4828.0  360.90  4833.2  361.38  4860.8  358.55  4866.0  358.58
  4874.5  357.45  4885.0  356.83  4905.9  353.53  4926.4  352.48  4937.3  350.07
  4947.7  348.58  4987.6  347.87  4987.8  347.37  4991.3  347.37  4991.6  347.87
  4997.3  348.38  5004.0  348.27  5037.7  352.15  5042.8  352.06  5051.7  352.81
  5072.3  355.23  5078.4  356.55  5083.5  356.45  5113.7  360.08  5119.1  361.90
  5124.2  361.73  5154.6  365.16  5159.8  365.20  5173.1  367.30  5175.7  367.30
#Mann=3,-1,0
  4811.2    0.05       0  4987.6    0.05       0  4991.6    0.05       0
Bank Sta=4987.6,4991.6
Exp/Cntr=0.3,0.1

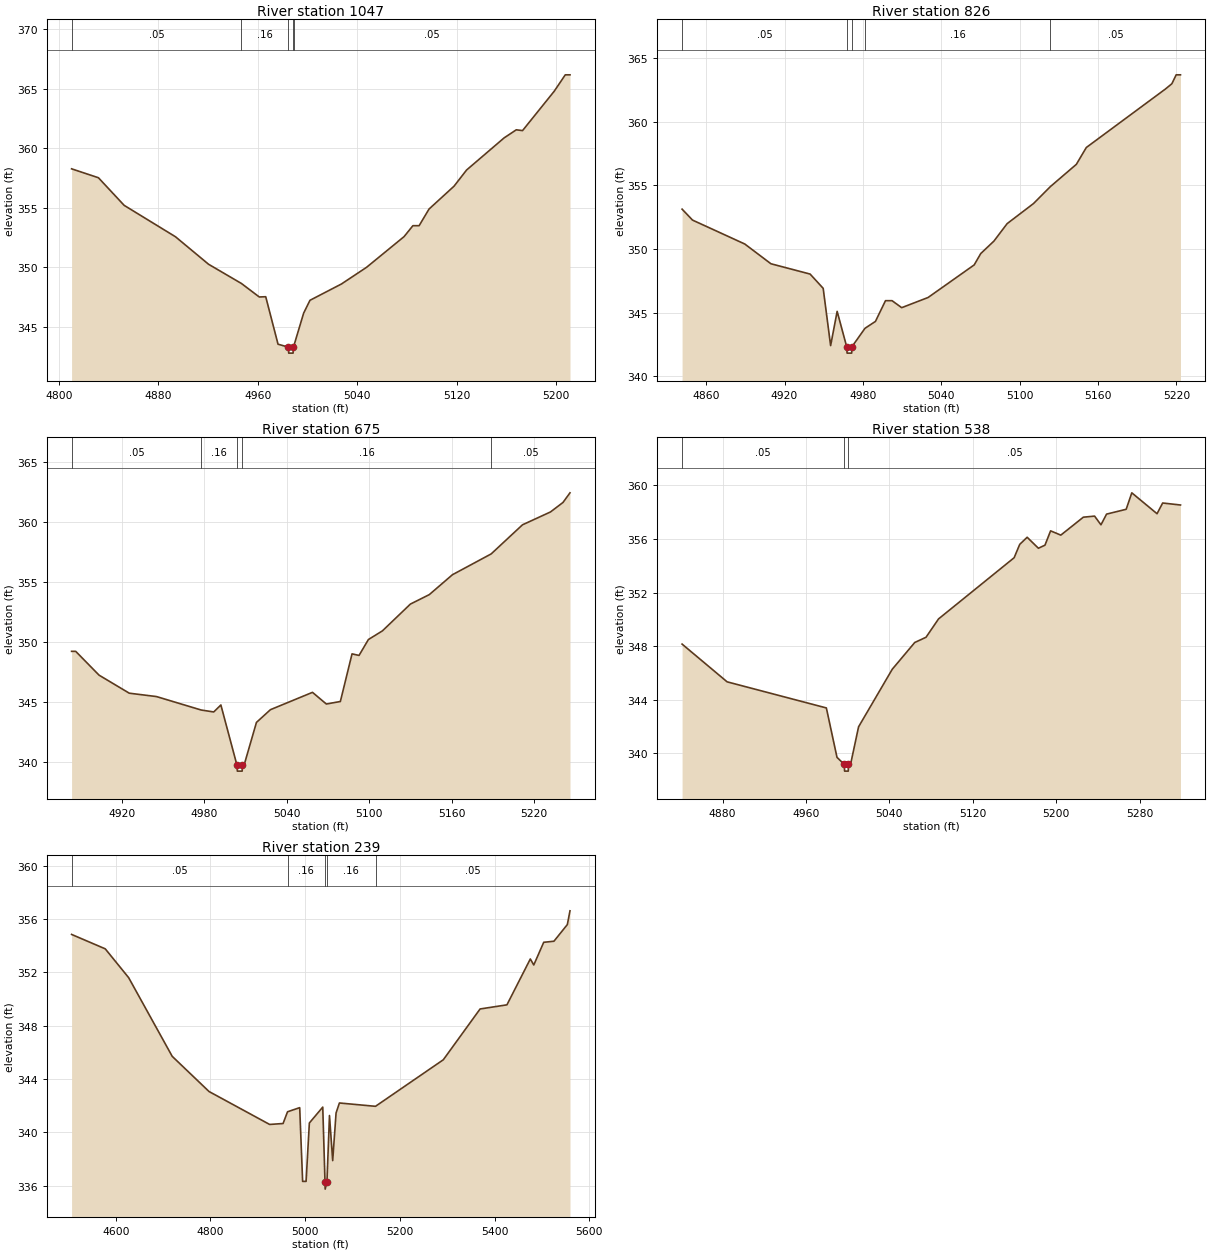
Type RM Length L Ch R = 1,1047,221,221,221
BEGIN DESCRIPTION:
South Twin Creek Trib J1046.59
END DESCRIPTION:
XS GIS Cut Line= 3
      2724566.97      6808503.47      2724380.54      6808455.82
      2724173.38      6808431.51
#Sta/Elev= 30
  4810.3  358.27  4831.9  357.52  4852.6  355.20  4893.9  352.56  4920.5  350.25
  4947.0  348.63  4961.3  347.50  4966.5  347.52  4976.4  343.53  4984.8  343.28
  4985.0  342.78  4988.5  342.78  4988.8  343.28  4989.4  343.49  4997.0  346.14
  5002.1  347.22  5027.4  348.59  5047.6  349.99  5077.8  352.57  5084.9  353.49
  5089.9  353.49  5097.9  354.89  5118.0  356.81  5128.1  358.17  5158.3  360.87
  5168.1  361.55  5173.1  361.48  5198.6  364.79  5207.5  366.17  5211.3  366.17
#Mann=5,-1,0
  4810.3    0.05       0  4947.0    0.16       0  4984.8    0.05       0
  4988.8    0.16       0  4989.4    0.05       0
Bank Sta=4984.8,4988.8
Exp/Cntr=0.3,0.1

Type RM Length L Ch R = 1,826,151,151,151
BEGIN DESCRIPTION:
South Twin Creek Trib J826.17
END DESCRIPTION:
XS GIS Cut Line= 3
      2724533.95      6808262.41      2724375.74      6808267.38
      2724154.48      6808296.86
#Sta/Elev= 30
  4841.6  353.12  4849.6  352.26  4889.6  350.38  4909.6  348.83  4939.6  348.02
  4949.6  346.90  4955.3  342.40  4960.3  345.09  4967.6  342.31  4967.9  341.81
  4971.4  341.81  4971.6  342.31  4981.6  343.76  4989.6  344.30  4997.3  345.93
  5002.3  345.93  5009.7  345.38  5029.9  346.18  5065.2  348.74  5070.2  349.63
  5080.3  350.61  5090.4  351.98  5110.6  353.56  5123.5  354.89  5143.4  356.64
  5151.0  357.96  5211.5  362.55  5216.5  362.97  5219.8  363.67  5223.1  363.67
#Mann=5,-1,0
  4841.6    0.05       0  4967.6    0.07       0  4971.6    0.05       0
  4981.6    0.16       0  5123.5    0.05       0
Bank Sta=4967.6,4971.6
Exp/Cntr=0.3,0.1

Type RM Length L Ch R = 1,675,137,137,137
BEGIN DESCRIPTION:
South Twin Creek Trib J675.48
END DESCRIPTION:
XS GIS Cut Line= 3
      2724456.85      6808100.42      2724334.82      6808130.05
      2724102.03      6808176.20
#Sta/Elev= 30
  4883.3  349.24  4886.3  349.24  4903.3  347.26  4925.3  345.76  4945.1  345.48
  4977.7  344.36  4986.8  344.20  4992.0  344.78  5003.7  339.78  5004.0  339.28
  5007.5  339.28  5007.7  339.78  5008.9  339.78  5017.9  343.33  5028.1  344.39
  5058.7  345.83  5068.8  344.86  5079.0  345.07  5087.5  349.03  5092.6  348.90
  5099.4  350.22  5109.6  350.94  5130.0  353.17  5143.8  353.96  5160.6  355.61
  5188.8  357.34  5211.6  359.76  5232.0  360.83  5241.1  361.62  5246.2  362.42
#Mann=5,-1,0
  4883.3    0.05       0  4977.7    0.16       0  5003.7    0.07       0
  5007.7    0.16       0  5188.8    0.05       0
Bank Sta=5003.7,5007.7
Exp/Cntr=0.3,0.1

Type RM Length L Ch R = 1,538,299,299,299
BEGIN DESCRIPTION:
South Twin Creek Trib J538.13
END DESCRIPTION:
XS GIS Cut Line= 3
      2724432.40      6808043.57      2724273.14      6808016.05
      2723979.52      6808134.16
#Sta/Elev= 30
  4841.2  348.15  4884.4  345.33  4979.6  343.38  4989.8  339.69  4996.8  339.16
  4997.1  338.66  5000.6  338.66  5000.8  339.16  5002.8  339.16  5010.5  341.97
  5042.8  346.27  5064.4  348.27  5075.2  348.66  5087.2  350.03  5159.7  354.60
  5165.1  355.60  5172.2  356.13  5183.0  355.31  5189.3  355.54  5194.7  356.61
  5204.5  356.29  5226.1  357.63  5236.9  357.71  5243.0  357.06  5248.4  357.86
  5267.2  358.22  5272.6  359.45  5296.8  357.89  5302.2  358.69  5319.3  358.54
#Mann=3,-1,0
  4841.2    0.05       0  4996.8    0.05       0  5000.8    0.05       0
Bank Sta=4996.8,5000.8
Exp/Cntr=0.3,0.1

Type RM Length L Ch R = 1,239,0,0,0
BEGIN DESCRIPTION:
South Twin Creek Trib J238.565
END DESCRIPTION:
XS GIS Cut Line= 3
      2724551.03      6808136.03      2724224.00      6807766.72
      2723812.84      6808146.04
#Sta/Elev= 30
  4506.7  354.84  4577.8  353.76  4627.2  351.60  4719.2  345.70  4797.0  343.06
  4925.0  340.59  4953.4  340.66  4962.8  341.54  4988.5  341.85  4994.7  336.32
  5002.0  336.32  5008.9  340.70  5037.2  341.89  5042.0  336.24  5042.3  335.74
  5046.0  336.24  5051.4  341.26  5058.2  337.88  5065.3  341.45  5072.4  342.20
  5148.6  341.95  5291.8  345.44  5369.5  349.25  5426.2  349.56  5475.6  353.00
  5482.9  352.55  5503.9  354.25  5525.5  354.33  5553.8  355.58  5559.4  356.61
#Mann=5,-1,0
  4506.7    0.05       0  4962.8    0.16       0  5042.0    0.07       0
  5046.0    0.16       0  5148.6    0.05       0
Bank Sta=5042,5046
Exp/Cntr=0.3,0.1

Chan Stop Cuts=-1