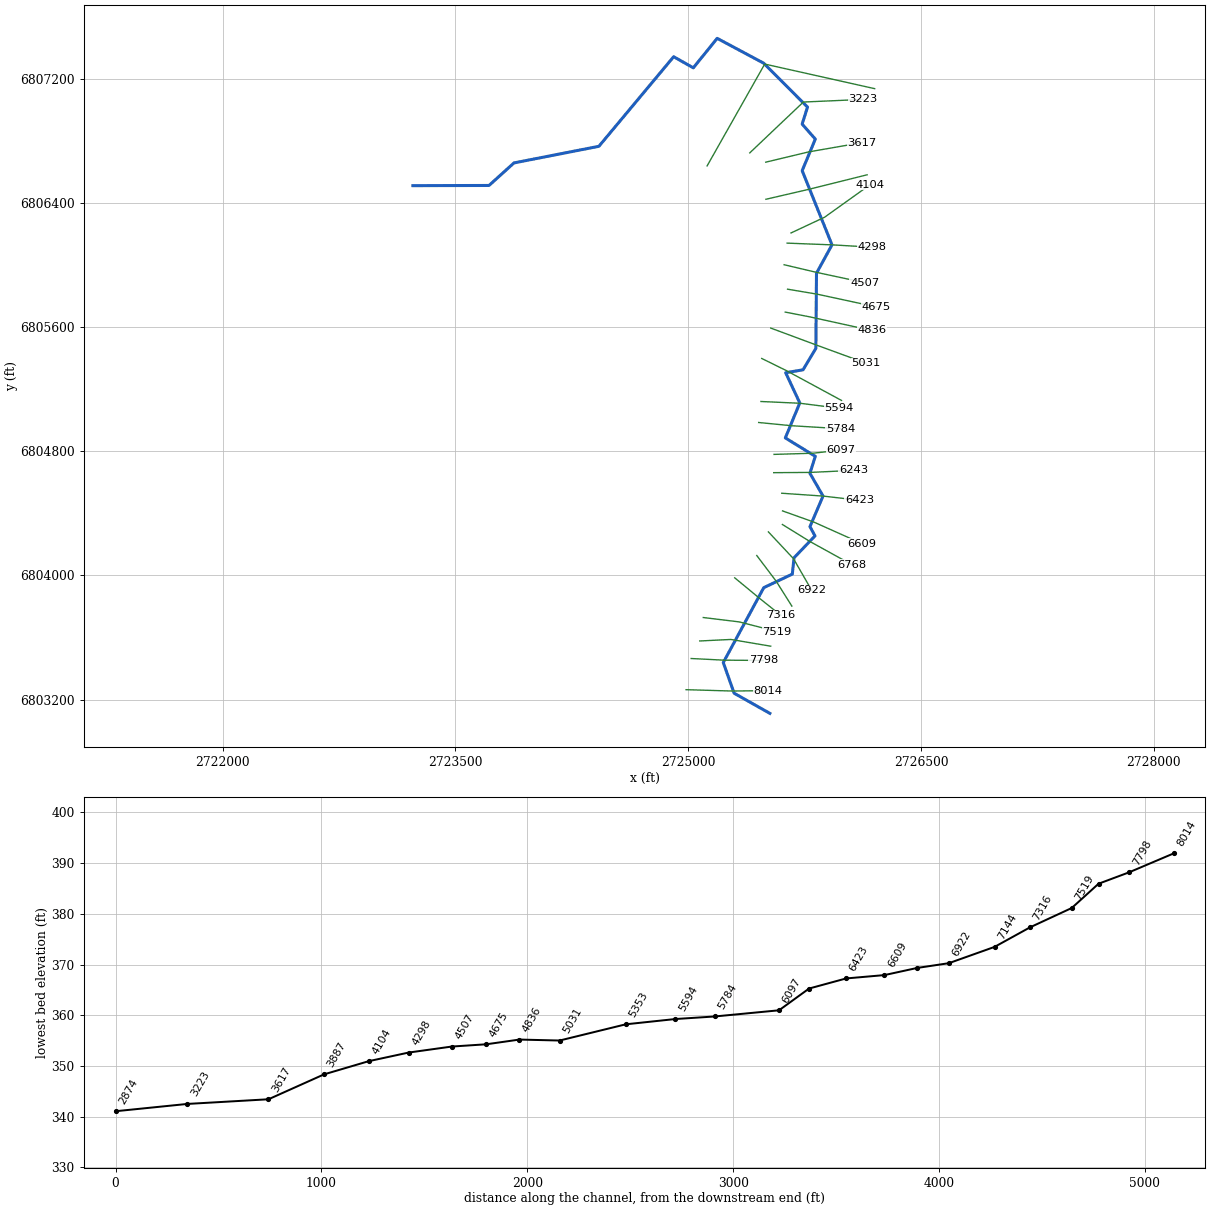
--- South Twin Creek Trib K.prj (project) ---

Proj Title=South Twin Creek Trib K Base Level Engineering
Current Plan=p01
Default Exp/Contr=0.3,0.1
English Units
Geom File=g01
Flow File=f01
Plan File=p01
BEGIN DESCRIPTION:
South Twin Creek Trib K
END DESCRIPTION:

--- South Twin Creek Trib K.p01 (plan) ---

Plan Title=Multiple Run
Short Identifier=Multiple
Geom File=g01
Flow File=f01
Subcritical Flow
K Sum by GR= 0
Std Step Tol= 0.01
Critical Tol= 0.01
Num of Std Step Trials= 20
Max Error Tol= 0.3
Flow Tol Ratio= 0.001
Split Flow NTrial= 30
Split Flow Tol= 0.02
Split Flow Ratio= 0.02
Log Output Level= 0
Friction Slope Method= 1
Unsteady Friction Slope Method= 2
Unsteady Bridges Friction Slope Method= 1
Parabolic Critical Depth
Global Vel Dist=  1 , 1 , 1
Global Log Level= 0
CheckData=True
Encroach Param= -1, 0, 0, 0
BEGIN DESCRIPTION:
Multiple Run
END DESCRIPTION:

--- South Twin Creek Trib K.f01 (steady flow) ---

Flow Title=Multiple
Number of Profiles=7
Profile Names=10-year,25-year,50-year,1pct_min,100-year,1pct_plu,500-year
River Rch & RM= South Twin Creek,Reach-1,8014
     448     590     703     417     831    1659    1159
Boundary for River Rch & Prof#=South Twin Creek,Reach-1,1
Up Type=0
Dn Type=3
Dn Slope=0.005
Boundary for River Rch & Prof#=South Twin Creek,Reach-1,2
Up Type=0
Dn Type=3
Dn Slope=0.005
Boundary for River Rch & Prof#=South Twin Creek,Reach-1,3
Up Type=0
Dn Type=3
Dn Slope=0.005
Boundary for River Rch & Prof#=South Twin Creek,Reach-1,4
Up Type=0
Dn Type=3
Dn Slope=0.005
Boundary for River Rch & Prof#=South Twin Creek,Reach-1,5
Up Type=0
Dn Type=3
Dn Slope=0.005
Boundary for River Rch & Prof#=South Twin Creek,Reach-1,6
Up Type=0
Dn Type=3
Dn Slope=0.005
Boundary for River Rch & Prof#=South Twin Creek,Reach-1,7
Up Type=0
Dn Type=3
Dn Slope=0.005

--- South Twin Creek Trib K.g01 (geometry) ---

Geom Title=Existing Conditions

River Reach=South Twin Creek,Reach-1
Reach XY= 30
      2725526.00      6803111.00      2725295.76      6803240.87
      2725225.72      6803438.24      2725486.63      6803921.05
      2725670.59      6804008.29      2725681.53      6804113.42
      2725816.70      6804254.33      2725784.29      6804314.22
      2725868.47      6804511.01      2725784.07      6804657.69
      2725818.51      6804767.07      2725625.48      6804885.73
      2725718.69      6805110.91      2725627.73      6805305.77
      2725739.68      6805324.51      2725822.26      6805462.55
      2725826.28      6805946.88      2725926.19      6806129.43
      2725734.08      6806607.70      2725818.66      6806811.10
      2725733.85      6806907.59      2725768.50      6807017.05
      2725485.68      6807300.22      2725186.33      6807460.13
      2725032.68      6807269.96      2724906.00      6807341.79
      2724424.50      6806764.61      2723877.46      6806657.46
      2723716.41      6806512.20      2723226.00      6806511.00

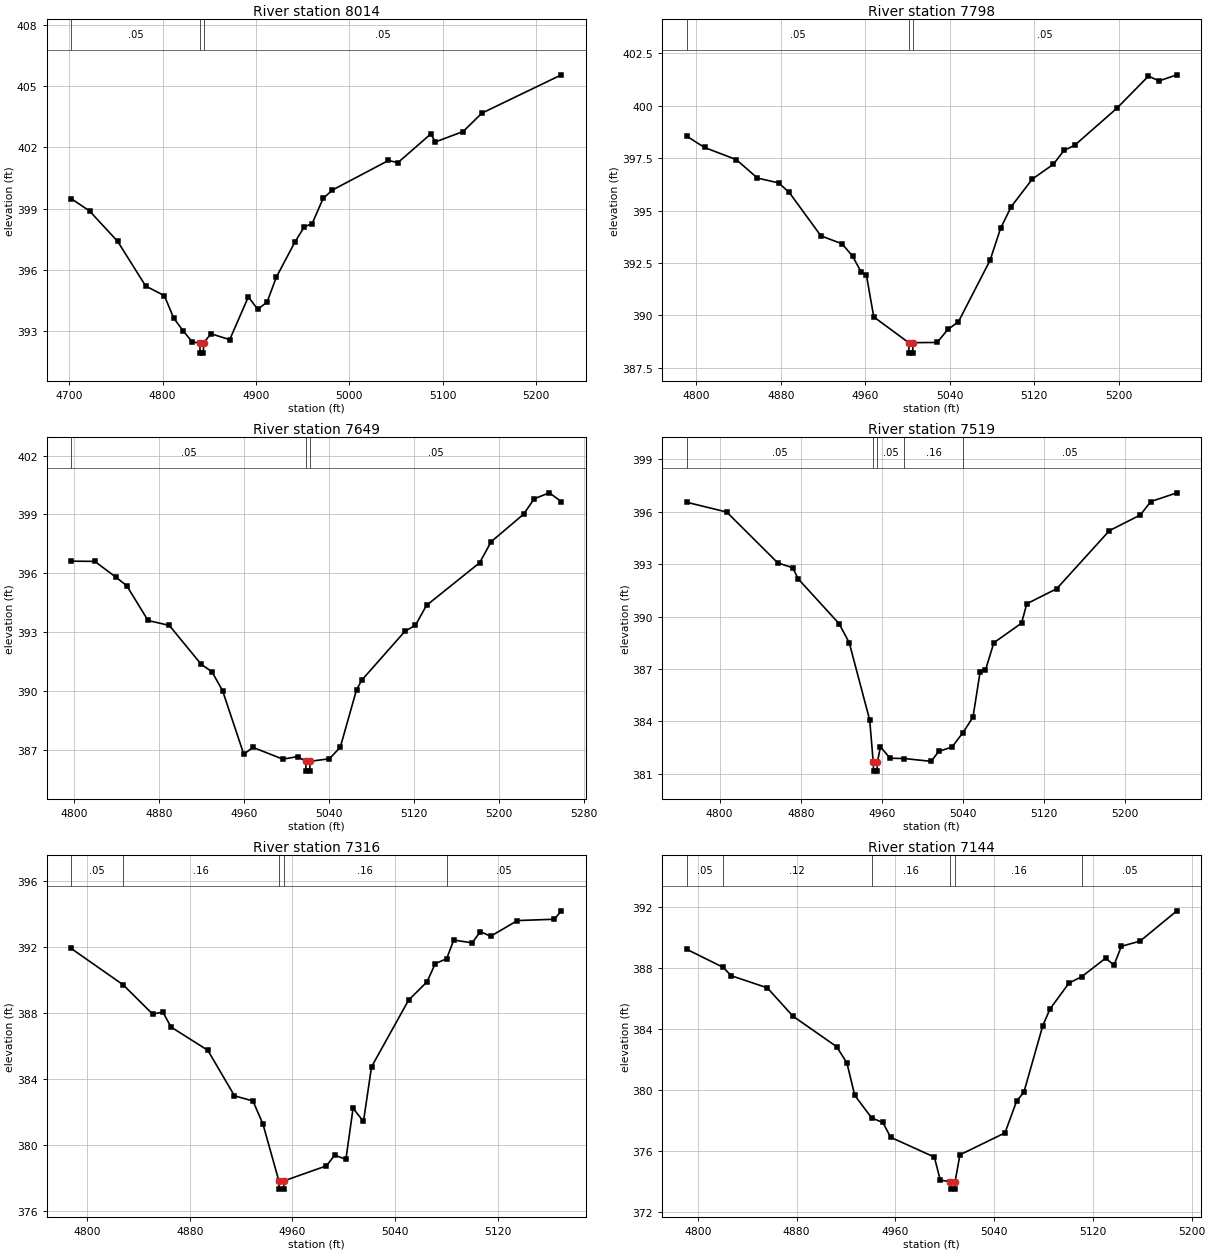
Type RM Length L Ch R = 1,8014,216,216,216
BEGIN DESCRIPTION:
South Twin Creek Trib K8014.233
END DESCRIPTION:
XS GIS Cut Line= 3
      2724986.26      6803263.65      2725284.13      6803254.92
      2725511.21      6803257.71
#Sta/Elev= 30
  4702.0  399.49  4721.7  398.88  4751.8  397.39  4781.8  395.20  4801.8  394.73
  4811.8  393.63  4821.8  393.01  4831.8  392.45  4839.8  392.41  4840.1  391.91
  4843.6  391.91  4843.8  392.41  4851.8  392.86  4871.8  392.57  4891.8  394.67
  4901.8  394.06  4911.8  394.41  4921.8  395.64  4941.8  397.37  4951.8  398.11
  4960.1  398.26  4971.9  399.50  4981.9  399.91  5041.9  401.36  5051.9  401.25
  5087.2  402.66  5092.2  402.27  5121.9  402.78  5141.9  403.68  5227.1  405.56
#Mann=3,-1,0
  4702.0    0.05       0  4839.8    0.05       0  4843.8    0.05       0
Bank Sta=4839.8,4843.8
Exp/Cntr=0.3,0.1

Type RM Length L Ch R = 1,7798,149,149,149
BEGIN DESCRIPTION:
South Twin Creek Trib K7797.61
END DESCRIPTION:
XS GIS Cut Line= 3
      2725019.08      6803464.44      2725231.10      6803453.80
      2725482.91      6803451.94
#Sta/Elev= 30
  4790.9  398.55  4807.8  398.01  4837.9  397.43  4857.9  396.55  4877.9  396.32
  4887.9  395.87  4918.0  393.79  4938.0  393.41  4948.0  392.82  4956.1  392.06
  4961.1  391.91  4968.0  389.92  5001.1  388.69  5001.4  388.19  5004.9  388.19
  5005.1  388.69  5028.1  388.70  5038.1  389.32  5048.1  389.68  5078.1  392.62
  5088.1  394.15  5098.1  395.18  5118.1  396.50  5138.1  397.21  5148.1  397.87
  5158.1  398.11  5198.1  399.88  5228.1  401.42  5238.1  401.19  5255.0  401.48
#Mann=3,-1,0
  4790.9    0.05       0  5001.1    0.05       0  5005.1    0.05       0
Bank Sta=5001.1,5005.1
Exp/Cntr=0.3,0.1

Type RM Length L Ch R = 1,7649,130,130,130
BEGIN DESCRIPTION:
South Twin Creek Trib K7648.63
END DESCRIPTION:
XS GIS Cut Line= 3
      2725073.80      6803577.41      2725274.32      6803587.28
      2725531.13      6803543.94
#Sta/Elev= 30
  4797.5  396.62  4819.7  396.61  4839.7  395.80  4849.8  395.37  4869.8  393.60
  4889.8  393.35  4919.8  391.37  4929.9  390.99  4939.9  390.03  4959.9  386.79
  4968.5  387.14  4996.6  386.54  5010.6  386.67  5018.2  386.43  5018.5  385.93
  5022.0  385.93  5022.2  386.43  5040.5  386.56  5050.7  387.15  5066.0  390.08
  5071.0  390.57  5111.5  393.05  5121.4  393.36  5131.8  394.37  5181.8  396.54
  5192.6  397.61  5223.1  399.01  5233.2  399.80  5247.4  400.10  5258.7  399.65
#Mann=3,-1,0
  4797.5    0.05       0  5018.2    0.05       0  5022.2    0.05       0
Bank Sta=5018.2,5022.2
Exp/Cntr=0.3,0.1

Type RM Length L Ch R = 1,7519,203,203,203
BEGIN DESCRIPTION:
South Twin Creek Trib K7519.31
END DESCRIPTION:
XS GIS Cut Line= 3
      2725096.74      6803728.61      2725329.04      6803700.26
      2725570.93      6803638.37
#Sta/Elev= 30
  4767.5  396.54  4807.0  395.98  4857.4  393.07  4872.1  392.79  4877.6  392.15
  4917.9  389.59  4927.9  388.50  4948.1  384.07  4951.6  381.65  4951.9  381.15
  4955.4  381.15  4955.6  381.65  4958.7  382.54  4968.2  381.89  4982.3  381.87
  5008.7  381.71  5016.3  382.28  5029.3  382.53  5040.2  383.36  5050.0  384.24
  5057.1  386.85  5062.3  386.93  5070.6  388.50  5097.9  389.62  5103.1  390.73
  5132.6  391.59  5184.7  394.92  5215.1  395.81  5225.5  396.58  5251.2  397.08
#Mann=5,-1,0
  4767.5    0.05       0  4951.6    0.07       0  4955.6    0.05       0
  4982.3    0.16       0  5040.2    0.05       0
Bank Sta=4951.6,4955.6
Exp/Cntr=0.3,0.1

Type RM Length L Ch R = 1,7316,172,172,172
BEGIN DESCRIPTION:
South Twin Creek Trib K7316.43
END DESCRIPTION:
XS GIS Cut Line= 3
      2725299.40      6803984.37      2725464.69      6803847.99
      2725596.18      6803743.26
#Sta/Elev= 30
  4787.4  391.91  4827.9  389.71  4851.0  387.93  4858.9  388.06  4865.3  387.15
  4894.0  385.74  4914.8  382.98  4929.2  382.67  4937.0  381.27  4949.4  377.83
  4949.6  377.33  4953.1  377.33  4953.4  377.83  4986.5  378.74  4993.0  379.39
  5001.7  379.13  5007.3  382.23  5015.4  381.43  5021.7  384.74  5050.6  388.78
  5065.0  389.89  5071.4  390.99  5080.3  391.29  5085.8  392.42  5100.2  392.25
  5106.6  392.93  5114.6  392.65  5135.5  393.60  5164.3  393.68  5169.8  394.19
#Mann=5,-1,0
  4787.4    0.05       0  4827.9    0.16       0  4949.4    0.07       0
  4953.4    0.16       0  5080.3    0.05       0
Bank Sta=4949.4,4953.4
Exp/Cntr=0.3,0.1

Type RM Length L Ch R = 1,7144,222,222,222
BEGIN DESCRIPTION:
South Twin Creek Trib K7143.63
END DESCRIPTION:
XS GIS Cut Line= 3
      2725441.59      6804128.02      2725566.81      6803962.07
      2725667.62      6803802.06
#Sta/Elev= 30
  4791.0  389.21  4820.4  388.03  4827.2  387.47  4856.3  386.68  4877.1  384.82
  4912.5  382.82  4920.8  381.75  4927.1  379.63  4940.9  378.14  4949.9  377.85
  4956.2  376.88  4991.6  375.58  4996.4  374.06  5004.4  373.98  5004.7  373.48
  5008.2  373.48  5008.4  373.98  5012.3  375.73  5048.8  377.17  5058.2  379.25
  5064.1  379.84  5079.4  384.20  5085.3  385.30  5100.6  386.99  5111.1  387.42
  5130.2  388.62  5137.1  388.18  5143.0  389.40  5158.3  389.75  5188.0  391.73
#Mann=6,-1,0
  4791.0    0.05       0  4820.4    0.12       0  4940.9    0.16       0
  5004.4    0.07       0  5008.4    0.16       0  5111.1    0.05       0
Bank Sta=5004.4,5008.4
Exp/Cntr=0.3,0.1

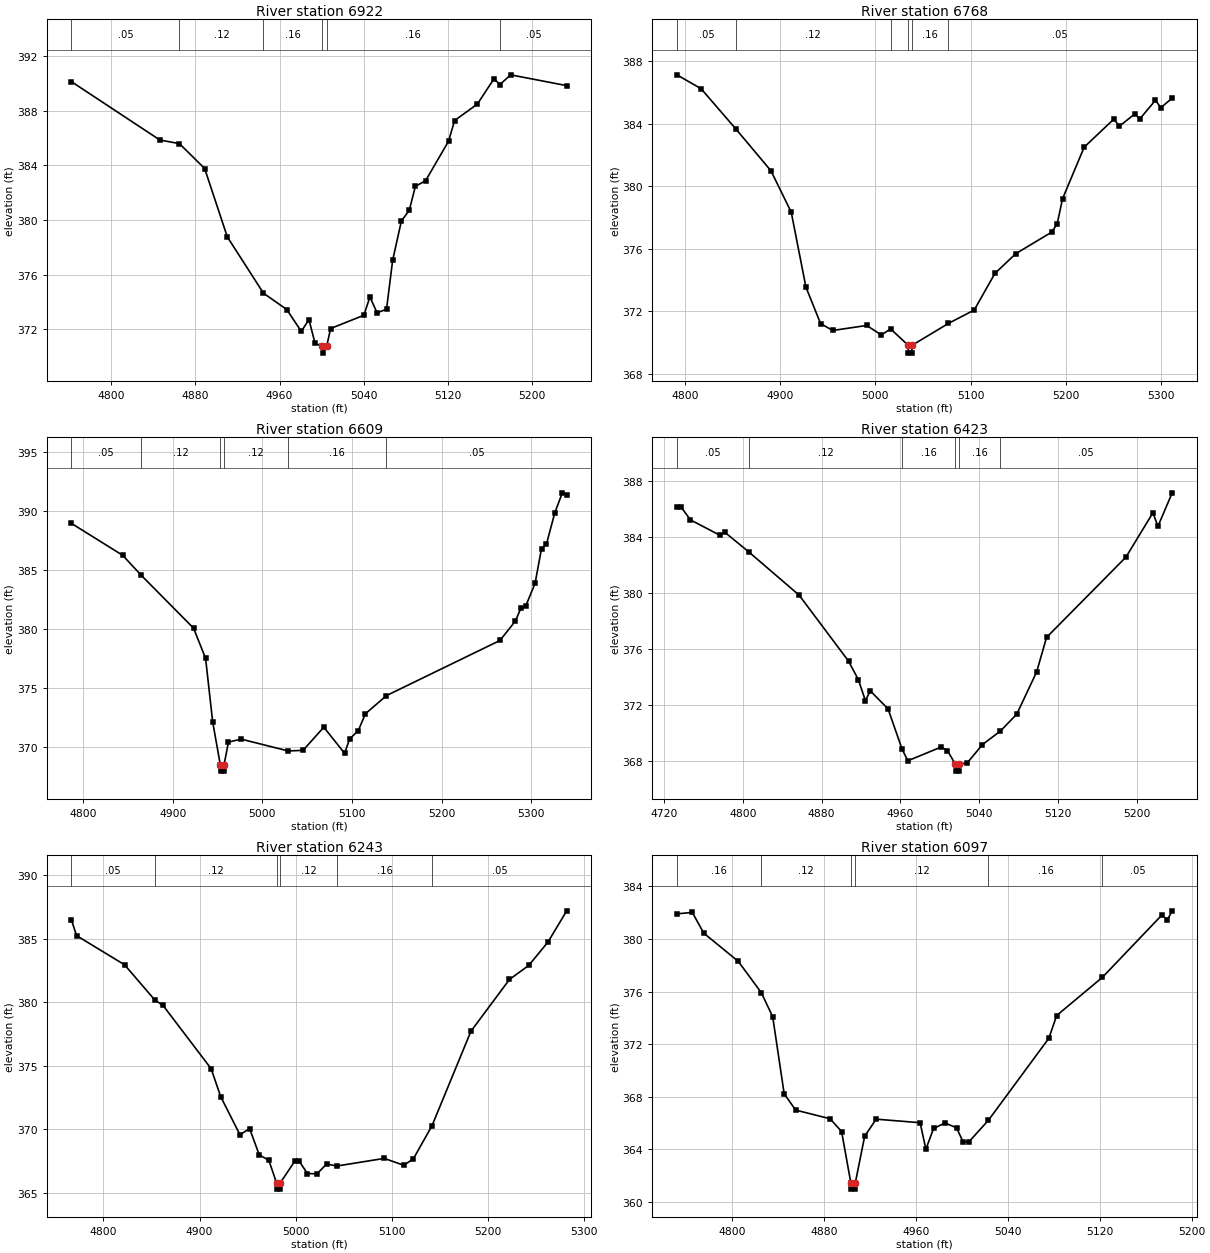
Type RM Length L Ch R = 1,6922,154,154,154
BEGIN DESCRIPTION:
South Twin Creek Trib K6922.42
END DESCRIPTION:
XS GIS Cut Line= 3
      2725516.37      6804280.40      2725678.14      6804107.54
      2725794.77      6803904.85
#Sta/Elev= 30
  4762.2  390.12  4846.3  385.85  4864.8  385.59  4888.8  383.77  4910.3  378.77
  4944.7  374.65  4966.8  373.46  4980.6  371.86  4987.9  372.72  4993.7  370.98
  5000.7  370.77  5001.0  370.27  5004.7  370.77  5008.5  372.07  5040.1  373.04
  5045.8  374.38  5052.6  373.22  5061.6  373.48  5067.4  377.05  5075.7  379.93
  5083.2  380.71  5089.0  382.46  5098.8  382.89  5120.5  385.76  5126.3  387.28
  5147.9  388.48  5163.7  390.33  5169.4  389.91  5179.5  390.62  5232.8  389.83
#Mann=6,-1,0
  4762.2    0.05       0  4864.8    0.12       0  4944.7    0.16       0
  5000.7    0.07       0  5004.7    0.16       0  5169.4    0.05       0
Bank Sta=5000.7,5004.7
Exp/Cntr=0.3,0.1

Type RM Length L Ch R = 1,6768,159,159,159
BEGIN DESCRIPTION:
South Twin Creek Trib K6768.2
END DESCRIPTION:
XS GIS Cut Line= 3
      2725606.87      6804327.79      2725784.05      6804218.29
      2726056.87      6804067.73
#Sta/Elev= 30
  4791.8  387.14  4817.2  386.25  4853.6  383.68  4890.5  381.00  4911.8  378.35
  4927.2  373.56  4942.6  371.22  4955.4  370.78  4991.0  371.10  5006.4  370.49
  5016.1  370.88  5034.6  369.83  5034.8  369.33  5038.3  369.33  5038.6  369.83
  5076.8  371.23  5103.9  372.09  5125.6  374.43  5147.4  375.69  5185.1  377.07
  5190.9  377.59  5196.6  379.21  5219.3  382.51  5250.5  384.31  5256.2  383.85
  5272.3  384.63  5278.0  384.34  5294.1  385.51  5299.8  385.04  5311.7  385.65
#Mann=6,-1,0
  4791.8    0.05       0  4853.6    0.12       0  5016.1    0.16       0
  5034.6    0.07       0  5038.6    0.16       0  5076.8    0.05       0
Bank Sta=5034.6,5038.6
Exp/Cntr=0.3,0.1

Type RM Length L Ch R = 1,6609,186,186,186
BEGIN DESCRIPTION:
South Twin Creek Trib K6608.87
END DESCRIPTION:
XS GIS Cut Line= 3
      2725607.60      6804415.48      2725809.63      6804343.36
      2726118.21      6804205.23
#Sta/Elev= 30
  4786.9  388.91  4844.2  386.20  4864.2  384.56  4923.2  380.03  4936.6  377.47
  4944.5  372.09  4953.1  368.42  4953.3  367.92  4956.8  367.92  4957.1  368.42
  4962.1  370.38  4976.3  370.63  5028.8  369.63  5045.3  369.68  5068.5  371.64
  5091.7  369.43  5097.2  370.63  5107.0  371.36  5114.9  372.78  5138.4  374.32
  5265.0  378.99  5282.3  380.64  5288.2  381.70  5293.7  381.89  5304.2  383.83
  5311.4  386.78  5316.9  387.15  5326.1  389.78  5334.6  391.50  5339.5  391.29
#Mann=6,-1,0
  4786.9    0.05       0  4864.2    0.12       0  4953.1    0.07       0
  4957.1    0.12       0  5028.8    0.16       0  5138.4    0.05       0
Bank Sta=4953.1,4957.1
Exp/Cntr=0.3,0.1

Type RM Length L Ch R = 1,6423,180,180,180
BEGIN DESCRIPTION:
South Twin Creek Trib K6422.78
END DESCRIPTION:
XS GIS Cut Line= 3
      2725602.29      6804529.29      2725869.70      6804510.85
      2726102.62      6804484.03
#Sta/Elev= 30
  4733.2  386.11  4737.6  386.11  4746.9  385.21  4776.5  384.12  4781.5  384.34
  4806.1  382.92  4857.2  379.83  4907.3  375.12  4917.3  373.79  4924.4  372.30
  4929.4  372.99  4947.4  371.71  4961.7  368.82  4967.5  368.00  5001.2  368.98
  5007.6  368.73  5015.7  367.76  5015.9  367.26  5019.4  367.26  5019.7  367.76
  5027.7  367.84  5043.2  369.16  5061.4  370.12  5078.0  371.33  5098.2  374.35
  5108.2  376.81  5188.8  382.55  5216.2  385.72  5221.2  384.74  5235.7  387.14
#Mann=6,-1,0
  4733.2    0.05       0  4806.1    0.12       0  4961.7    0.16       0
  5015.7    0.07       0  5019.7    0.16       0  5061.4    0.05       0
Bank Sta=5015.7,5019.7
Exp/Cntr=0.3,0.1

Type RM Length L Ch R = 1,6243,146,146,146
BEGIN DESCRIPTION:
South Twin Creek Trib K6242.68
END DESCRIPTION:
XS GIS Cut Line= 3
      2725550.66      6804661.86      2725784.51      6804663.42
      2726065.45      6804676.47
#Sta/Elev= 30
  4766.7  386.47  4772.0  385.23  4822.0  382.93  4853.3  380.17  4862.0  379.73
  4912.0  374.75  4922.0  372.54  4942.0  369.55  4952.0  370.04  4962.0  367.97
  4972.0  367.54  4980.0  365.77  4980.3  365.27  4983.8  365.27  4984.0  365.77
  4998.8  367.45  5003.8  367.45  5012.1  366.50  5022.1  366.47  5032.1  367.25
  5042.8  367.09  5092.1  367.69  5112.2  367.15  5122.2  367.64  5141.7  370.26
  5182.2  377.70  5222.3  381.78  5242.3  382.88  5262.3  384.72  5281.8  387.18
#Mann=6,-1,0
  4766.7    0.05       0  4853.3    0.12       0  4980.0    0.07       0
  4984.0    0.12       0  5042.8    0.16       0  5141.7    0.05       0
Bank Sta=4980,4984
Exp/Cntr=0.3,0.1

Type RM Length L Ch R = 1,6097,313,313,313
BEGIN DESCRIPTION:
South Twin Creek Trib K6096.55
END DESCRIPTION:
XS GIS Cut Line= 3
      2725552.62      6804779.49      2725802.51      6804787.06
      2725982.74      6804806.71
#Sta/Elev= 30
  4751.7  381.91  4765.1  382.02  4775.1  380.44  4805.1  378.30  4825.1  375.93
  4835.1  374.09  4845.1  368.23  4855.1  366.99  4885.1  366.33  4895.1  365.36
  4903.1  361.48  4903.4  360.98  4906.9  360.98  4907.1  361.48  4915.2  365.00
  4925.2  366.30  4963.5  366.03  4968.5  364.01  4975.2  365.59  4985.2  366.01
  4995.2  365.64  5000.9  364.58  5006.0  364.58  5023.0  366.22  5075.6  372.45
  5082.4  374.18  5122.3  377.09  5173.8  381.80  5178.9  381.47  5183.0  382.14
#Mann=6,-1,0
  4751.7    0.16       0  4825.1    0.12       0  4903.1    0.07       0
  4907.1    0.12       0  5023.0    0.16       0  5122.3    0.05       0
Bank Sta=4903.1,4907.1
Exp/Cntr=0.3,0.1

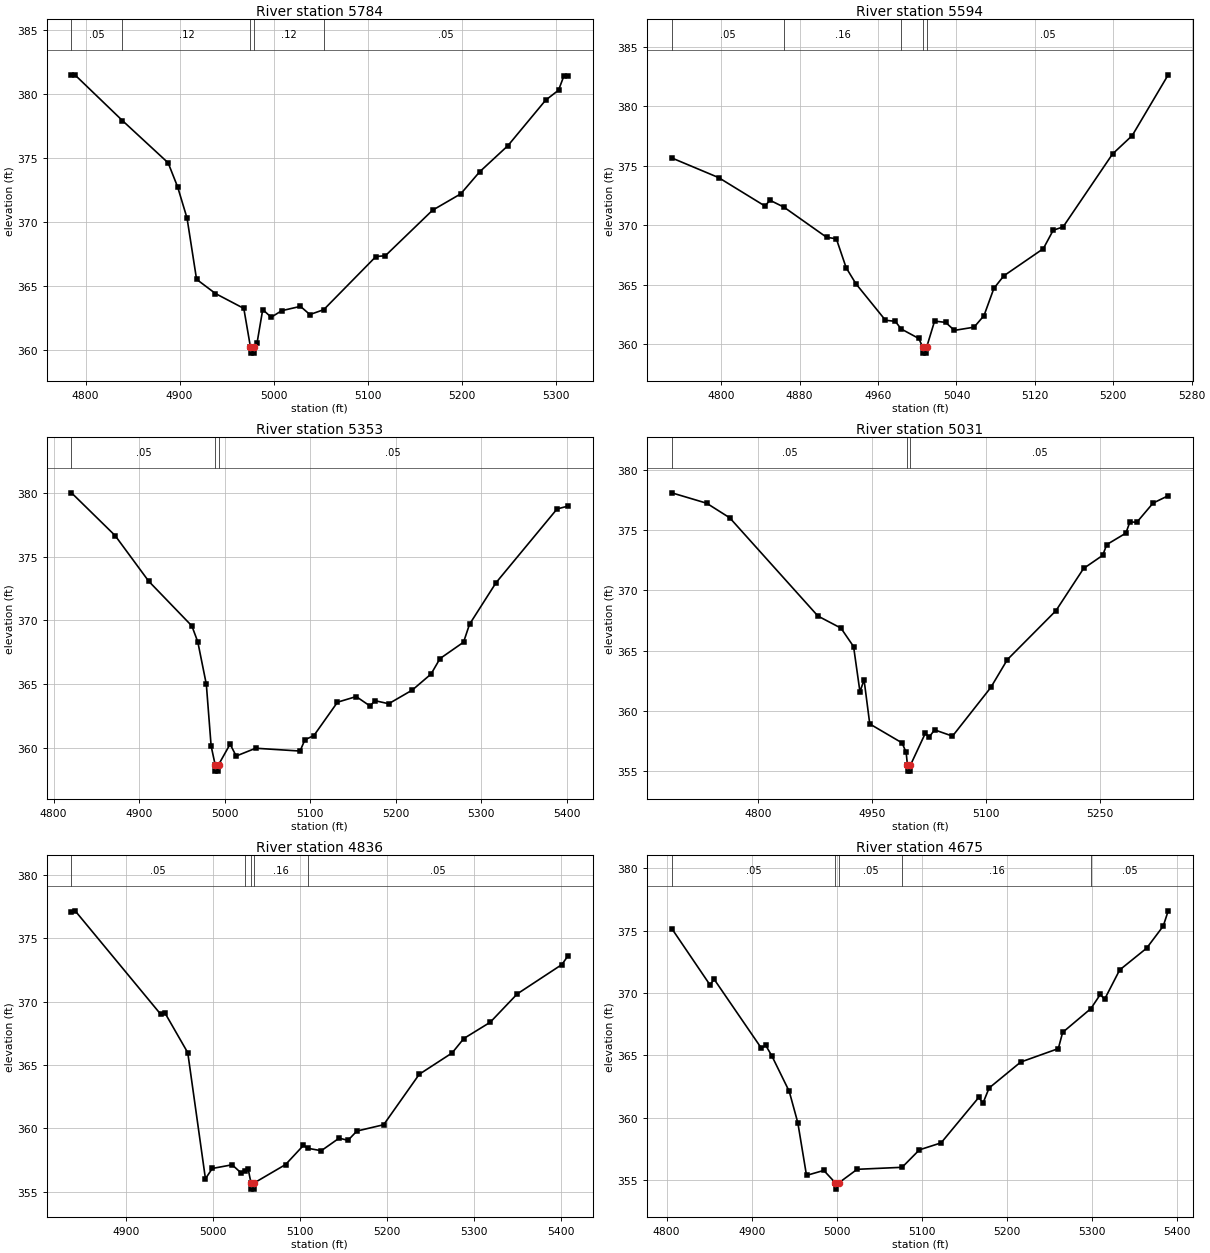
Type RM Length L Ch R = 1,5784,190,190,190
BEGIN DESCRIPTION:
South Twin Creek Trib K5783.89
END DESCRIPTION:
XS GIS Cut Line= 3
      2725453.74      6804985.00      2725668.96      6804964.05
      2725979.66      6804945.33
#Sta/Elev= 30
  4785.1  381.48  4788.7  381.48  4839.2  377.91  4887.8  374.61  4897.9  372.73
  4907.9  370.29  4918.0  365.52  4938.1  364.41  4968.2  363.25  4975.2  360.26
  4975.5  359.76  4979.0  359.76  4979.2  360.26  4982.2  360.52  4988.3  363.16
  4997.3  362.56  5008.4  363.07  5028.4  363.41  5038.4  362.77  5053.1  363.15
  5108.6  367.30  5118.6  367.36  5168.7  370.91  5198.7  372.19  5218.8  373.91
  5248.8  375.95  5288.9  379.50  5302.6  380.28  5308.3  381.39  5312.6  381.39
#Mann=5,-1,0
  4785.1    0.05       0  4839.2    0.12       0  4975.2    0.07       0
  4979.2    0.12       0  5053.1    0.05       0
Bank Sta=4975.2,4979.2
Exp/Cntr=0.3,0.1

Type RM Length L Ch R = 1,5594,241,241,241
BEGIN DESCRIPTION:
South Twin Creek Trib K5593.92
END DESCRIPTION:
XS GIS Cut Line= 3
      2725468.27      6805120.42      2725719.99      6805108.97
      2725972.39      6805076.96
#Sta/Elev= 30
  4749.6  375.65  4797.4  374.00  4844.7  371.61  4849.7  372.10  4864.0  371.52
  4907.5  368.99  4917.5  368.86  4927.5  366.43  4937.5  365.08  4967.6  362.02
  4977.6  361.93  4983.6  361.29  5001.6  360.49  5005.6  359.76  5005.9  359.26
  5009.4  359.26  5009.6  359.76  5017.7  361.95  5029.0  361.84  5037.9  361.17
  5058.0  361.44  5068.1  362.41  5078.2  364.70  5088.3  365.75  5128.6  368.03
  5138.7  369.58  5148.8  369.86  5199.2  375.98  5219.3  377.53  5256.0  382.63
#Mann=5,-1,0
  4749.6    0.05       0  4864.0    0.16       0  4983.6    0.05       0
  5005.6    0.05       0  5009.6    0.05       0
Bank Sta=5005.6,5009.6
Exp/Cntr=0.3,0.1

Type RM Length L Ch R = 1,5353,322,322,322
BEGIN DESCRIPTION:
South Twin Creek Trib K5352.83
END DESCRIPTION:
XS GIS Cut Line= 3
      2725473.51      6805397.64      2725631.24      6805319.91
      2725987.24      6805127.33
#Sta/Elev= 30
  4821.0  379.98  4872.0  376.64  4911.3  373.07  4961.8  369.57  4968.7  368.33
  4978.7  365.01  4984.3  360.19  4989.0  358.72  4989.3  358.22  4992.8  358.22
  4993.0  358.72  5006.5  360.33  5013.6  359.40  5036.4  360.01  5088.3  359.79
  5094.0  360.67  5104.5  361.00  5132.1  363.61  5154.0  364.05  5170.2  363.31
  5175.8  363.73  5192.0  363.49  5219.6  364.56  5241.5  365.81  5252.0  367.02
  5279.5  368.30  5286.5  369.70  5317.6  372.96  5388.9  378.72  5401.6  378.94
#Mann=3,-1,0
  4821.0    0.05       0  4989.0    0.05       0  4993.0    0.05       0
Bank Sta=4989,4993
Exp/Cntr=0.3,0.1

Type RM Length L Ch R = 1,5031,195,195,195
BEGIN DESCRIPTION:
South Twin Creek Trib K5031.49
END DESCRIPTION:
XS GIS Cut Line= 3
      2725531.71      6805593.39      2725827.71      6805483.39
      2726144.78      6805367.40
#Sta/Elev= 30
  4685.9  378.08  4731.8  377.22  4762.2  376.01  4878.3  367.87  4908.6  366.87
  4925.2  365.34  4933.6  361.59  4939.0  362.59  4946.5  358.93  4989.0  357.36
  4994.4  356.57  4996.1  355.52  4996.3  355.02  4999.8  355.02  5000.1  355.52
  5019.5  358.14  5024.8  357.85  5031.8  358.44  5055.4  357.92  5105.8  361.95
  5127.6  364.26  5191.5  368.31  5227.9  371.81  5253.1  372.90  5258.4  373.79
  5283.6  374.74  5288.9  375.67  5298.0  375.64  5319.4  377.23  5339.3  377.84
#Mann=3,-1,0
  4685.9    0.05       0  4996.1    0.05       0  5000.1    0.05       0
Bank Sta=4996.1,5000.1
Exp/Cntr=0.3,0.1

Type RM Length L Ch R = 1,4836,161,161,161
BEGIN DESCRIPTION:
South Twin Creek Trib K4835.96
END DESCRIPTION:
XS GIS Cut Line= 3
      2725624.91      6805696.43      2725783.75      6805665.50
      2726182.82      6805577.86
#Sta/Elev= 30
  4837.4  377.05  4841.6  377.16  4939.8  369.01  4944.9  369.09  4971.0  365.97
  4991.3  356.03  4999.2  356.84  5022.0  357.13  5032.2  356.49  5036.9  356.67
  5040.4  356.80  5043.6  355.71  5043.8  355.21  5047.3  355.21  5047.6  355.71
  5083.4  357.15  5103.9  358.66  5109.1  358.43  5124.4  358.24  5144.9  359.23
  5155.1  359.06  5165.3  359.79  5196.1  360.29  5237.0  364.27  5274.7  365.95
  5288.2  367.09  5318.5  368.37  5349.6  370.61  5400.8  372.92  5407.8  373.60
#Mann=5,-1,0
  4837.4    0.05       0  5036.9    0.16       0  5043.6    0.05       0
  5047.6    0.16       0  5109.1    0.05       0
Bank Sta=5043.6,5047.6
Exp/Cntr=0.3,0.1

Type RM Length L Ch R = 1,4675,168,168,168
BEGIN DESCRIPTION:
South Twin Creek Trib K4674.96
END DESCRIPTION:
XS GIS Cut Line= 3
      2725639.93      6805843.97      2725831.81      6805811.66
      2726211.70      6805729.78
#Sta/Elev= 30
  4806.0  375.18  4850.8  370.67  4855.9  371.10  4911.4  365.57  4916.4  365.81
  4923.7  364.95  4944.0  362.12  4954.1  359.60  4964.3  355.38  4984.6  355.78
  4998.2  354.78  4998.4  354.28  5002.2  354.78  5023.8  355.87  5076.6  356.03
  5096.9  357.43  5122.4  357.99  5166.6  361.63  5171.7  361.19  5178.8  362.39
  5215.9  364.47  5260.1  365.55  5265.2  366.85  5298.4  368.76  5309.4  369.89
  5314.5  369.51  5332.2  371.86  5363.8  373.60  5383.4  375.38  5389.2  376.60
#Mann=5,-1,0
  4806.0    0.05       0  4998.2    0.05       0  5002.2    0.05       0
  5076.6    0.16       0  5298.4    0.05       0
Bank Sta=4998.2,5002.2
Exp/Cntr=0.3,0.1

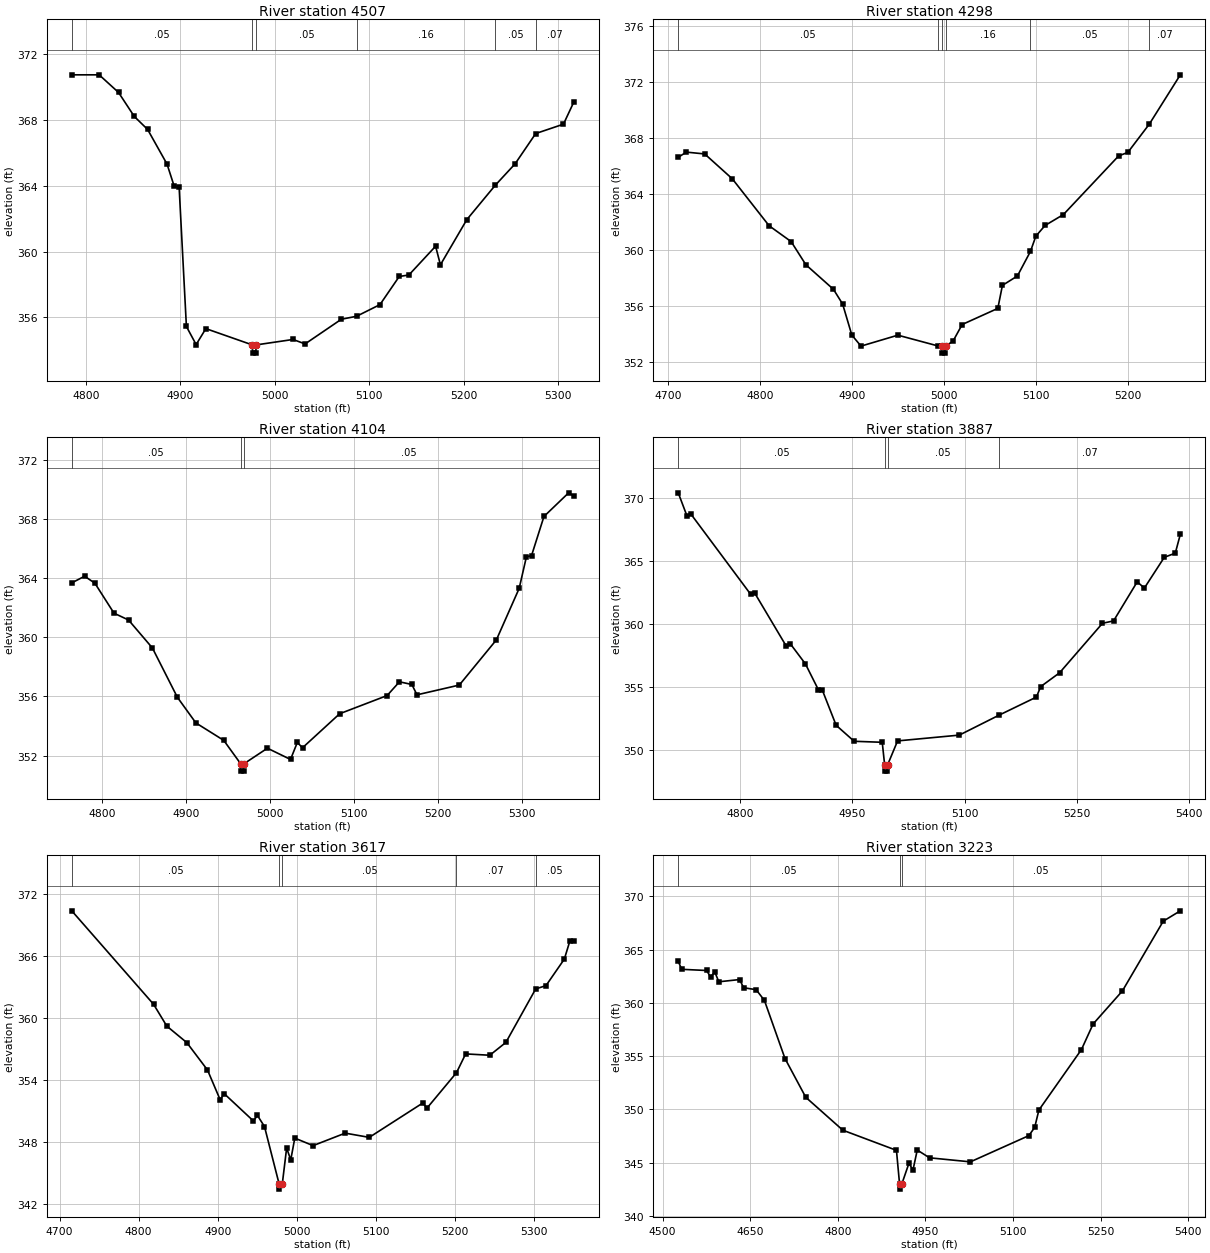
Type RM Length L Ch R = 1,4507,209,209,209
BEGIN DESCRIPTION:
South Twin Creek Trib K4507.05
END DESCRIPTION:
XS GIS Cut Line= 3
      2725617.83      6806001.49      2725826.69      6805952.24
      2726136.80      6805885.95
#Sta/Elev= 30
  4784.9  370.75  4813.9  370.75  4834.4  369.68  4851.1  368.22  4865.2  367.43
  4885.8  365.32  4893.4  363.97  4898.6  363.92  4906.3  355.45  4916.6  354.35
  4926.9  355.32  4976.1  354.33  4976.4  353.83  4979.9  353.83  4980.1  354.33
  5019.2  354.66  5032.0  354.39  5070.4  355.89  5086.5  356.07  5111.3  356.78
  5131.7  358.49  5141.9  358.58  5170.2  360.33  5175.3  359.20  5203.3  361.95
  5233.3  364.03  5254.4  365.34  5276.2  367.18  5305.6  367.75  5316.6  369.10
#Mann=6,-1,0
  4784.9    0.05       0  4976.1    0.05       0  4980.1    0.05       0
  5086.5    0.16       0  5233.3    0.05       0  5276.2    0.07       0
Bank Sta=4976.1,4980.1
Exp/Cntr=0.3,0.1

Type RM Length L Ch R = 1,4298,194,194,194
BEGIN DESCRIPTION:
South Twin Creek Trib K4297.63
END DESCRIPTION:
XS GIS Cut Line= 3
      2725637.21      6806140.70      2725930.84      6806129.37
      2726182.96      6806114.63
#Sta/Elev= 30
  4710.8  366.61  4719.6  366.98  4739.6  366.85  4769.6  365.08  4809.7  361.73
  4833.7  360.60  4849.7  358.95  4879.7  357.20  4889.7  356.15  4899.7  353.94
  4909.7  353.15  4949.8  353.93  4993.6  353.16  4997.7  353.15  4998.0  352.65
  5001.5  352.65  5001.7  353.15  5009.8  353.50  5019.8  354.69  5058.6  355.84
  5063.6  357.48  5079.9  358.15  5094.1  359.90  5100.0  360.99  5110.0  361.75
  5130.0  362.53  5190.1  366.71  5200.1  366.96  5223.5  368.98  5257.2  372.49
#Mann=6,-1,0
  4710.8    0.05       0  4993.6    0.16       0  4997.7    0.07       0
  5001.7    0.16       0  5094.1    0.05       0  5223.5    0.07       0
Bank Sta=4997.7,5001.7
Exp/Cntr=0.3,0.1

Type RM Length L Ch R = 1,4104,217,217,217
BEGIN DESCRIPTION:
South Twin Creek Trib K4104.33
END DESCRIPTION:
XS GIS Cut Line= 3
      2725662.11      6806206.21      2725878.15      6806307.38
      2726170.45      6806516.40
#Sta/Elev= 30
  4763.5  363.68  4778.8  364.13  4791.0  363.66  4813.8  361.63  4831.1  361.17
  4859.5  359.28  4889.3  355.94  4911.3  354.21  4944.5  353.03  4964.6  351.45
  4964.8  350.95  4968.3  350.95  4968.6  351.45  4996.5  352.50  5024.0  351.74
  5032.1  352.89  5038.3  352.53  5082.5  354.83  5139.0  356.06  5153.7  356.99
  5168.5  356.81  5174.6  356.11  5225.0  356.77  5269.2  359.83  5296.3  363.31
  5304.9  365.44  5311.0  365.52  5325.8  368.17  5355.2  369.77  5361.4  369.56
#Mann=3,-1,0
  4763.5    0.05       0  4964.6    0.05       0  4968.6    0.05       0
Bank Sta=4964.6,4968.6
Exp/Cntr=0.3,0.1

Type RM Length L Ch R = 1,3887,270,270,270
BEGIN DESCRIPTION:
South Twin Creek Trib K3886.57
END DESCRIPTION:
XS GIS Cut Line= 3
      2725500.48      6806423.26      2725774.70      6806486.80
      2726152.55      6806580.99
#Sta/Elev= 30
  4717.3  370.45  4728.8  368.64  4733.9  368.79  4814.1  362.39  4819.3  362.51
  4861.9  358.25  4867.1  358.46  4887.2  356.87  4904.6  354.81  4909.8  354.79
  4928.3  351.99  4952.4  350.72  4989.9  350.64  4993.1  348.85  4993.4  348.35
  4996.9  348.35  4997.1  348.85  5010.4  350.75  5092.9  351.21  5145.5  352.78
  5195.9  354.23  5201.6  355.06  5226.9  356.16  5284.2  360.09  5299.0  360.28
  5330.6  363.38  5340.2  362.89  5366.8  365.33  5381.5  365.66  5388.2  367.15
#Mann=4,-1,0
  4717.3    0.05       0  4993.1    0.05       0  4997.1    0.05       0
  5145.5    0.07       0
Bank Sta=4993.1,4997.1
Exp/Cntr=0.3,0.1

Type RM Length L Ch R = 1,3617,394,394,394
BEGIN DESCRIPTION:
South Twin Creek Trib K3617.29
END DESCRIPTION:
XS GIS Cut Line= 3
      2725499.24      6806662.20      2725775.67      6806728.41
      2726120.64      6806788.42
#Sta/Elev= 30
  4715.5  370.38  4818.9  361.33  4835.6  359.22  4860.9  357.62  4887.0  354.97
  4903.0  352.09  4908.1  352.68  4945.0  350.04  4950.1  350.57  4959.0  349.50
  4977.5  343.94  4977.8  343.44  4981.5  343.94  4987.0  347.42  4992.2  346.27
  4997.3  348.38  5020.4  347.65  5061.0  348.86  5091.4  348.45  5159.1  351.78
  5164.2  351.27  5201.6  354.71  5213.2  356.53  5243.7  356.40  5264.0  357.64
  5301.7  362.82  5314.7  363.14  5337.9  365.71  5345.0  367.49  5349.9  367.49
#Mann=5,-1,0
  4715.5    0.05       0  4977.5    0.05       0  4981.5    0.05       0
  5201.6    0.07       0  5301.7    0.05       0
Bank Sta=4977.5,4981.5
Exp/Cntr=0.3,0.1

Type RM Length L Ch R = 1,3223,349,349,349
BEGIN DESCRIPTION:
South Twin Creek Trib K3223.15
END DESCRIPTION:
XS GIS Cut Line= 3
      2725396.37      6806722.12      2725741.70      6807049.73
      2726125.14      6807066.47
#Sta/Elev= 30
  4526.7  363.89  4532.7  363.15  4575.2  363.04  4582.1  362.44  4589.3  362.90
  4596.2  361.98  4631.8  362.19  4638.7  361.42  4660.1  361.24  4674.3  360.23
  4709.5  354.78  4745.1  351.14  4808.6  348.05  4900.4  346.16  4905.7  343.02
  4905.9  342.52  4909.7  343.02  4921.8  344.95  4928.7  344.31  4936.0  346.19
  4957.0  345.46  5027.0  345.08  5127.1  347.54  5137.1  348.31  5144.3  349.94
  5217.2  355.62  5237.2  358.02  5287.3  361.12  5357.3  367.67  5386.5  368.64
#Mann=3,-1,0
  4526.7    0.05       0  4905.7    0.05       0  4909.7    0.05       0
Bank Sta=4905.7,4909.7
Exp/Cntr=0.3,0.1

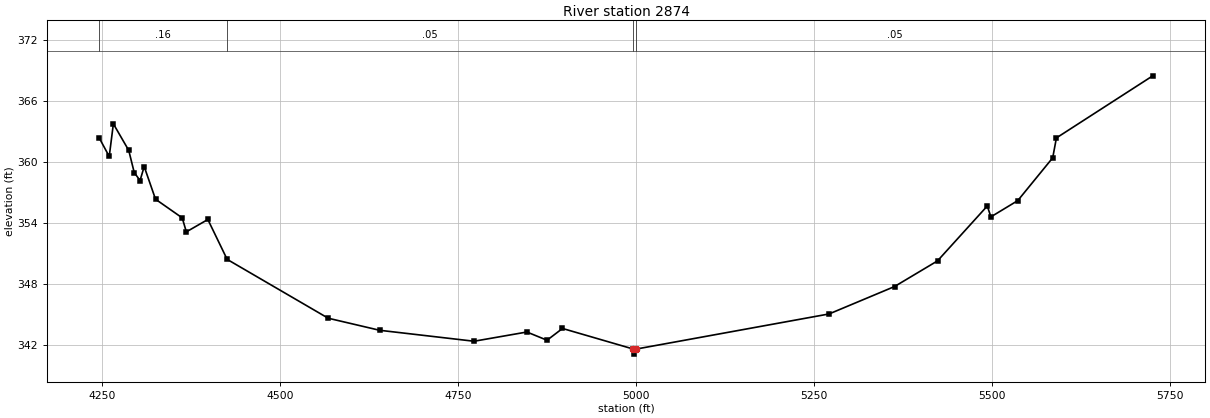
Type RM Length L Ch R = 1,2874,0,0,0
BEGIN DESCRIPTION:
South Twin Creek Trib K2874.151
END DESCRIPTION:
XS GIS Cut Line= 3
      2725121.62      6806638.31      2725492.67      6807294.35
      2726200.99      6807136.00
#Sta/Elev= 30
  4246.3  362.37  4260.2  360.56  4266.0  363.78  4287.6  361.16  4295.3  358.98
  4303.5  358.19  4309.3  359.57  4325.2  356.35  4362.7  354.51  4368.5  353.13
  4398.7  354.35  4425.8  350.42  4567.7  344.62  4640.0  343.43  4772.6  342.35
  4846.8  343.26  4875.1  342.45  4896.8  343.61  4996.3  341.58  4996.6  341.08
  5000.3  341.58  5271.2  345.04  5363.1  347.74  5423.5  350.27  5493.4  355.68
  5498.5  354.61  5536.2  356.21  5585.3  360.43  5590.5  362.39  5725.8  368.51
#Mann=4,-1,0
  4246.3    0.16       0  4425.8    0.05       0  4996.3    0.05       0
  5000.3    0.05       0
Bank Sta=4996.3,5000.3
Exp/Cntr=0.3,0.1

Chan Stop Cuts=-1