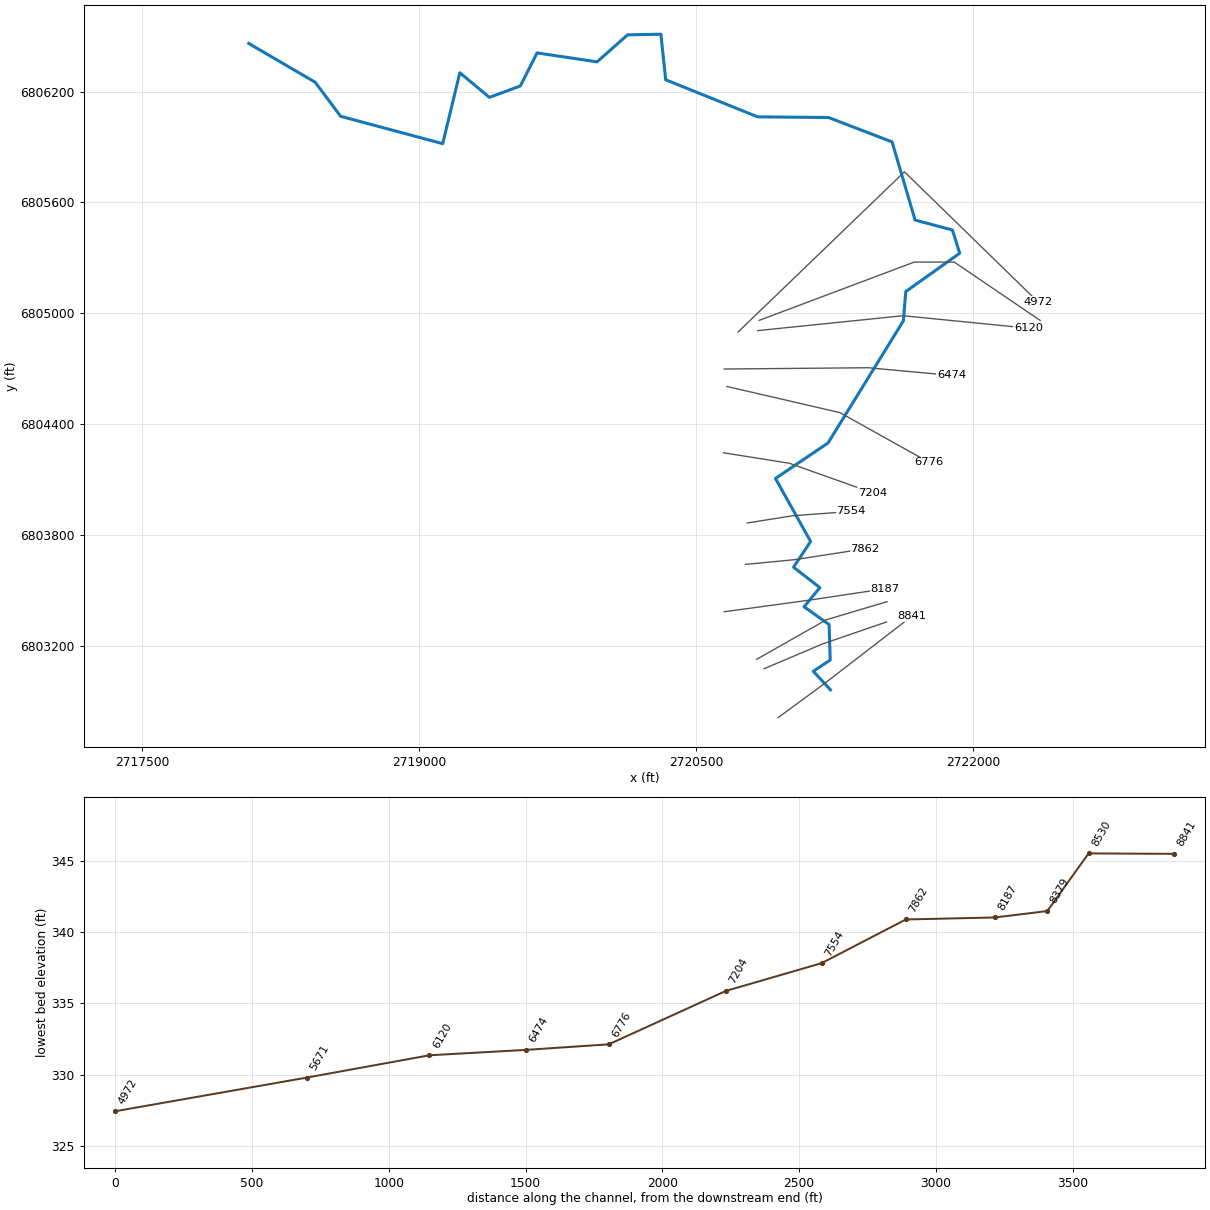
--- South Twin Creek Trib L.prj (project) ---

Proj Title=South Twin Creek Trib L Base Level Engineering
Current Plan=p01
Default Exp/Contr=0.3,0.1
English Units
Geom File=g01
Flow File=f01
Plan File=p01
BEGIN DESCRIPTION:
South Twin Creek Trib L
END DESCRIPTION:

--- South Twin Creek Trib L.p01 (plan) ---

Plan Title=Multiple Run
Short Identifier=Multiple
Geom File=g01
Flow File=f01
Subcritical Flow
K Sum by GR= 0
Std Step Tol= 0.01
Critical Tol= 0.01
Num of Std Step Trials= 20
Max Error Tol= 0.3
Flow Tol Ratio= 0.001
Split Flow NTrial= 30
Split Flow Tol= 0.02
Split Flow Ratio= 0.02
Log Output Level= 0
Friction Slope Method= 1
Unsteady Friction Slope Method= 2
Unsteady Bridges Friction Slope Method= 1
Parabolic Critical Depth
Global Vel Dist=  1 , 1 , 1
Global Log Level= 0
CheckData=True
Encroach Param= -1, 0, 0, 0
BEGIN DESCRIPTION:
Multiple Run
END DESCRIPTION:

--- South Twin Creek Trib L.f01 (steady flow) ---

Flow Title=Multiple
Number of Profiles=7
Profile Names=10-year,25-year,50-year,1pct_min,100-year,1pct_plu,500-year
River Rch & RM= South Twin Creek,Reach-1,8841
     750    1025    1252     760    1515    3024    2217
Boundary for River Rch & Prof#=South Twin Creek,Reach-1,1
Up Type=0
Dn Type=3
Dn Slope=0.005
Boundary for River Rch & Prof#=South Twin Creek,Reach-1,2
Up Type=0
Dn Type=3
Dn Slope=0.005
Boundary for River Rch & Prof#=South Twin Creek,Reach-1,3
Up Type=0
Dn Type=3
Dn Slope=0.005
Boundary for River Rch & Prof#=South Twin Creek,Reach-1,4
Up Type=0
Dn Type=3
Dn Slope=0.005
Boundary for River Rch & Prof#=South Twin Creek,Reach-1,5
Up Type=0
Dn Type=3
Dn Slope=0.005
Boundary for River Rch & Prof#=South Twin Creek,Reach-1,6
Up Type=0
Dn Type=3
Dn Slope=0.005
Boundary for River Rch & Prof#=South Twin Creek,Reach-1,7
Up Type=0
Dn Type=3
Dn Slope=0.005

--- South Twin Creek Trib L.g01 (geometry) ---

Geom Title=Existing Conditions

River Reach=South Twin Creek,Reach-1
Reach XY= 30
      2721226.00      6802961.00      2721132.91      6803061.21
      2721224.56      6803122.33      2721218.28      6803314.66
      2721083.01      6803410.79      2721168.50      6803514.58
      2721025.99      6803624.93      2721118.39      6803764.33
      2720928.07      6804105.53      2721212.53      6804297.43
      2721620.52      6804958.56      2721633.70      6805117.48
      2721925.61      6805324.91      2721886.18      6805450.67
      2721684.00      6805504.61      2721559.37      6805927.71
      2721215.50      6806059.78      2720831.53      6806063.38
      2720333.65      6806264.16      2720307.69      6806510.88
      2720127.47      6806507.47      2719961.94      6806361.15
      2719637.31      6806409.61      2719546.54      6806230.46
      2719379.22      6806168.87      2719219.01      6806302.18
      2719126.36      6805918.20      2718573.54      6806066.46
      2718436.12      6806250.66      2718076.00      6806461.00

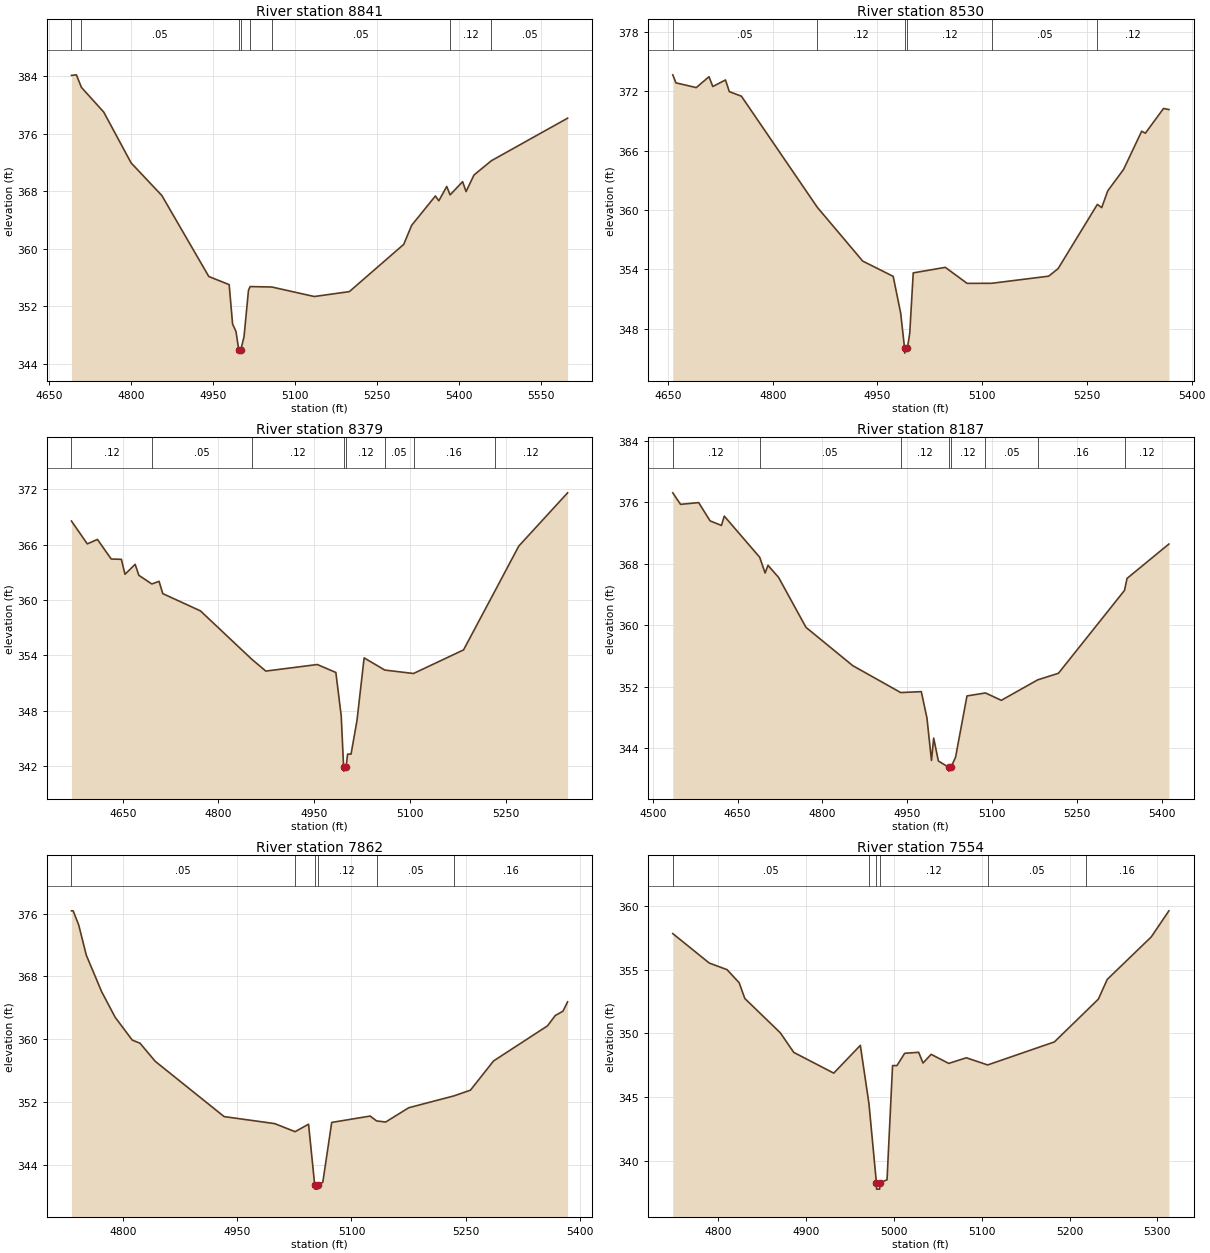
Type RM Length L Ch R = 1,8841,311,311,311
BEGIN DESCRIPTION:
South Twin Creek Trib L8840.571
END DESCRIPTION:
XS GIS Cut Line= 3
      2720943.18      6802811.14      2721192.47      6802994.23
      2721667.25      6803360.44
#Sta/Elev= 30
  4690.7  384.07  4699.7  384.15  4709.0  382.40  4749.8  378.98  4800.0  371.92
  4856.3  367.39  4942.3  356.15  4979.6  355.02  4985.9  349.54  4992.1  348.52
  4997.1  346.01  4997.3  345.51  5001.1  346.01  5006.8  347.78  5015.0  354.24
  5018.0  354.75  5057.8  354.69  5135.5  353.37  5199.8  354.05  5299.4  360.61
  5313.9  363.25  5357.4  367.33  5363.7  366.66  5378.2  368.65  5384.4  367.48
  5407.3  369.32  5413.6  367.94  5428.1  370.24  5459.9  372.22  5599.6  378.13
#Mann=8,-1,0
  4690.7    0.12       0  4709.0    0.05       0  4997.1    0.05       0
  5001.1    0.05       0  5018.0    0.12       0  5057.8    0.05       0
  5384.4    0.12       0  5459.9    0.05       0
Bank Sta=4997.1,5001.1
Exp/Cntr=0.3,0.1

Type RM Length L Ch R = 1,8530,151,151,151
BEGIN DESCRIPTION:
South Twin Creek Trib L8530.34
END DESCRIPTION:
XS GIS Cut Line= 3
      2720865.49      6803074.79      2721184.11      6803209.91
      2721528.86      6803328.32
#Sta/Elev= 30
  4656.8  373.67  4661.3  372.86  4690.4  372.38  4708.7  373.48  4714.1  372.49
  4732.3  373.15  4737.8  371.97  4755.1  371.51  4863.8  360.28  4928.9  354.84
  4972.5  353.30  4983.2  349.59  4988.8  346.04  4989.0  345.54  4992.8  346.04
  4996.2  347.54  5001.2  353.65  5047.2  354.21  5078.4  352.59  5113.7  352.60
  5195.2  353.32  5208.7  354.08  5264.9  360.57  5271.2  360.25  5279.8  361.94
  5302.5  364.11  5328.4  367.97  5333.7  367.77  5359.7  370.27  5367.4  370.16
#Mann=6,-1,0
  4656.8    0.05       0  4863.8    0.12       0  4988.8    0.07       0
  4992.8    0.12       0  5113.7    0.05       0  5264.9    0.12       0
Bank Sta=4988.8,4992.8
Exp/Cntr=0.3,0.1

Type RM Length L Ch R = 1,8379,192,192,192
BEGIN DESCRIPTION:
South Twin Creek Trib L8378.9
END DESCRIPTION:
XS GIS Cut Line= 3
      2720825.72      6803125.83      2721203.15      6803340.24
      2721532.34      6803438.44
#Sta/Elev= 30
  4569.6  368.54  4594.4  366.07  4610.3  366.55  4631.9  364.43  4647.8  364.40
  4653.5  362.78  4669.4  363.86  4675.2  362.67  4695.6  361.73  4706.9  362.02
  4712.7  360.69  4771.8  358.82  4851.9  353.61  4874.2  352.31  4954.9  353.02
  4984.0  352.16  4992.4  347.47  4996.1  341.99  4996.4  341.49  5000.1  341.99
  5002.4  343.33  5007.8  343.33  5017.1  346.96  5028.3  353.74  5060.7  352.42
  5105.7  352.05  5184.1  354.60  5232.7  360.89  5270.7  365.83  5347.2  371.59
#Mann=8,-1,0
  4569.6    0.12       0  4695.6    0.05       0  4851.9    0.12       0
  4996.1    0.07       0  5000.1    0.12       0  5060.7    0.05       0
  5105.7    0.16       0  5232.7    0.12       0
Bank Sta=4996.1,5000.1
Exp/Cntr=0.3,0.1

Type RM Length L Ch R = 1,8187,325,325,325
BEGIN DESCRIPTION:
South Twin Creek Trib L8187.43
END DESCRIPTION:
XS GIS Cut Line= 3
      2720650.59      6803383.70      2721108.77      6803446.28
      2721519.16      6803507.76
#Sta/Elev= 30
  4535.3  377.24  4549.0  375.74  4581.1  375.97  4601.3  373.59  4621.3  373.00
  4626.4  374.21  4689.0  368.86  4698.6  366.81  4703.7  367.81  4722.4  366.24
  4770.9  359.74  4853.6  354.76  4938.4  351.26  4974.8  351.38  4984.8  347.96
  4992.8  342.43  4996.7  345.34  5005.0  342.36  5023.3  341.54  5023.5  341.04
  5027.3  341.54  5035.4  342.85  5055.6  350.82  5088.3  351.21  5116.3  350.25
  5180.6  352.91  5217.4  353.77  5334.2  364.55  5338.7  366.11  5412.7  370.58
#Mann=8,-1,0
  4535.3    0.12       0  4689.0    0.05       0  4938.4    0.12       0
  5023.3    0.07       0  5027.3    0.12       0  5088.3    0.05       0
  5180.6    0.16       0  5334.2    0.12       0
Bank Sta=5023.3,5027.3
Exp/Cntr=0.3,0.1

Type RM Length L Ch R = 1,7862,308,308,308
BEGIN DESCRIPTION:
Mapping XS 5b47690c
END DESCRIPTION:
XS GIS Cut Line= 3
      2720766.55      6803640.27      2721029.18      6803665.40
      2721412.04      6803724.36
#Sta/Elev= 30
  4732.5  376.36  4734.7  376.36  4742.0  374.56  4752.0  370.70  4772.1  366.06
  4789.9  362.79  4812.3  359.89  4822.4  359.50  4842.4  357.19  4932.9  350.14
  4999.2  349.25  5026.0  348.22  5043.7  349.17  5051.8  341.40  5052.1  340.90
  5055.6  340.90  5055.8  341.40  5062.4  341.77  5074.1  349.40  5124.6  350.21
  5133.0  349.59  5144.9  349.45  5175.2  351.27  5234.9  352.79  5256.2  353.51
  5286.5  357.23  5357.4  361.71  5367.5  363.02  5377.6  363.57  5383.7  364.76
#Mann=6,-1,0
  4732.5    0.05       0  5026.0    0.12       0  5051.8    0.05       0
  5055.8    0.12       0  5133.0    0.05       0  5234.9    0.16       0
Bank Sta=5051.8,5055.8
Exp/Cntr=0.3,0.1

Type RM Length L Ch R = 1,7554,350,350,350
BEGIN DESCRIPTION:
Mapping XS d521aea9
END DESCRIPTION:
XS GIS Cut Line= 3
      2720775.01      6803864.34      2721023.36      6803903.87
      2721336.05      6803926.70
#Sta/Elev= 30
  4748.2  357.81  4789.7  355.51  4810.0  354.99  4823.8  353.97  4830.2  352.74
  4870.7  350.05  4886.0  348.52  4931.5  346.90  4961.8  349.07  4971.6  344.52
  4980.1  338.33  4980.3  337.83  4983.8  337.83  4984.1  338.33  4992.2  338.56
  4998.5  347.49  5003.5  347.49  5012.3  348.45  5028.2  348.53  5033.2  347.69
  5042.4  348.37  5062.5  347.66  5082.5  348.10  5106.8  347.54  5182.8  349.34
  5218.3  351.71  5232.9  352.69  5243.0  354.23  5293.1  357.55  5313.2  359.59
#Mann=6,-1,0
  4748.2    0.05       0  4971.6    0.12       0  4980.1    0.07       0
  4984.1    0.12       0  5106.8    0.05       0  5218.3    0.16       0
Bank Sta=4980.1,4984.1
Exp/Cntr=0.3,0.1

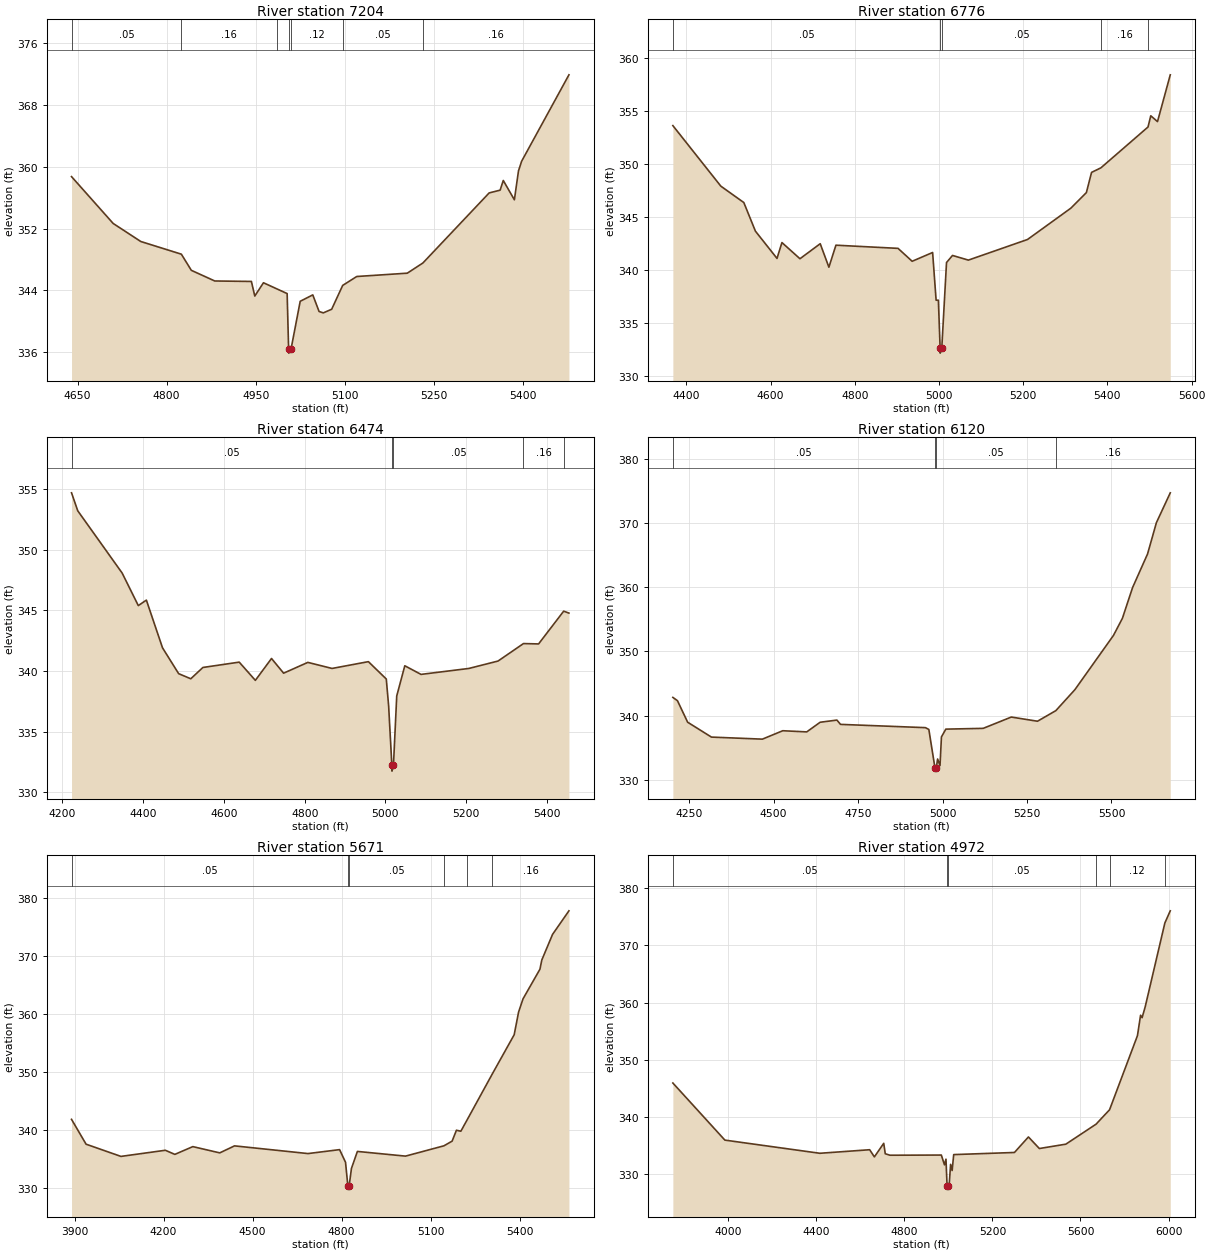
Type RM Length L Ch R = 1,7204,428,428,428
BEGIN DESCRIPTION:
Mapping XS 48585eac
END DESCRIPTION:
XS GIS Cut Line= 3
      2720646.73      6804244.45      2721002.48      6804188.01
      2721452.60      6804028.05
#Sta/Elev= 30
  4639.8  358.73  4709.9  352.67  4756.5  350.33  4824.8  348.69  4841.6  346.60
  4881.1  345.22  4942.8  345.16  4948.5  343.27  4963.1  344.99  4985.9  344.19
  5003.0  343.59  5005.5  336.38  5005.8  335.88  5009.5  336.38  5025.0  342.59
  5046.2  343.42  5056.8  341.27  5063.9  341.09  5078.0  341.56  5096.6  344.65
  5120.3  345.80  5205.4  346.23  5231.7  347.55  5343.3  356.62  5361.8  356.98
  5367.1  358.23  5385.8  355.73  5392.7  359.47  5398.0  360.72  5477.7  371.91
#Mann=7,-1,0
  4639.8    0.05       0  4824.8    0.16       0  4985.9    0.12       0
  5005.5    0.07       0  5009.5    0.12       0  5096.6    0.05       0
  5231.7    0.16       0
Bank Sta=5005.5,5009.5
Exp/Cntr=0.3,0.1

Type RM Length L Ch R = 1,6776,302,302,302
BEGIN DESCRIPTION:
Mapping XS d3f69d30
END DESCRIPTION:
XS GIS Cut Line= 3
      2720665.07      6804603.58      2721277.22      6804461.92
      2721759.94      6804192.59
#Sta/Elev= 30
  4368.1  353.63  4482.0  347.91  4536.6  346.36  4564.1  343.66  4615.4  341.08
  4627.1  342.58  4669.9  341.05  4718.0  342.47  4738.6  340.25  4755.3  342.33
  4902.8  342.03  4936.3  340.81  4984.9  341.64  4993.2  337.13  4998.6  337.13
  5002.7  332.63  5002.9  332.13  5006.7  332.63  5017.9  340.69  5032.1  341.36
  5069.8  340.92  5210.3  342.87  5313.2  345.83  5350.0  347.30  5362.3  349.21
  5384.5  349.64  5496.4  353.50  5502.9  354.56  5518.9  354.01  5549.2  358.43
#Mann=5,-1,0
  4368.1    0.05       0  5002.7    0.05       0  5006.7    0.05       0
  5384.5    0.16       0  5496.4    0.12       0
Bank Sta=5002.7,5006.7
Exp/Cntr=0.3,0.1

Type RM Length L Ch R = 1,6474,354,354,354
BEGIN DESCRIPTION:
Mapping XS a6d76024
END DESCRIPTION:
XS GIS Cut Line= 3
      2720650.58      6804698.02      2721430.23      6804704.99
      2721880.85      6804663.61
#Sta/Elev= 30
  4222.4  354.67  4237.8  353.19  4347.8  348.06  4387.8  345.38  4407.8  345.83
  4447.8  341.90  4487.8  339.77  4517.8  339.35  4547.8  340.28  4637.8  340.72
  4677.8  339.22  4717.8  341.02  4747.8  339.81  4807.8  340.70  4867.8  340.20
  4957.8  340.76  5002.1  339.33  5007.9  337.14  5015.9  332.24  5016.2  331.74
  5019.9  332.24  5028.0  337.93  5048.0  340.42  5088.2  339.71  5206.7  340.20
  5279.0  340.81  5342.0  342.25  5379.4  342.22  5441.6  344.92  5454.6  344.76
#Mann=5,-1,0
  4222.4    0.05       0  5015.9    0.05       0  5019.9    0.05       0
  5342.0    0.16       0  5441.6    0.12       0
Bank Sta=5015.9,5019.9
Exp/Cntr=0.3,0.1

Type RM Length L Ch R = 1,6120,449,449,449
BEGIN DESCRIPTION:
South Twin Creek Trib L6119.89
END DESCRIPTION:
XS GIS Cut Line= 3
      2720832.49      6804906.05      2721618.90      6804986.64
      2722296.93      6804919.26
#Sta/Elev= 30
  4202.1  342.84  4215.7  342.33  4245.8  338.98  4316.2  336.66  4467.0  336.34
  4527.3  337.65  4598.3  337.47  4637.9  338.97  4687.6  339.31  4698.2  338.64
  4949.5  338.13  4959.6  337.85  4977.7  331.86  4977.9  331.36  4981.7  331.86
  4985.5  333.25  4992.6  332.22  4996.9  336.69  5009.8  337.90  5120.4  338.02
  5203.6  339.78  5281.1  339.13  5335.4  340.78  5391.7  344.04  5506.0  352.50
  5532.4  355.16  5562.5  359.95  5606.8  365.18  5632.9  370.04  5674.0  374.70
#Mann=4,-1,0
  4202.1    0.05       0  4977.7    0.05       0  4981.7    0.05       0
  5335.4    0.16       0
Bank Sta=4977.7,4981.7
Exp/Cntr=0.3,0.1

Type RM Length L Ch R = 1,5671,699,699,699
BEGIN DESCRIPTION:
South Twin Creek Trib L5671.15
END DESCRIPTION:
XS GIS Cut Line= 4
      2720840.14      6804961.57      2721679.93      6805277.19
      2721896.12      6805277.01      2722361.66      6804960.98
#Sta/Elev= 30
  3890.0  341.84  3939.0  337.55  4056.5  335.44  4206.1  336.50  4238.1  335.79
  4298.7  337.13  4389.4  336.05  4439.2  337.26  4686.8  335.93  4793.2  336.61
  4813.2  334.43  4821.2  330.29  4821.5  329.79  4825.2  330.29  4833.2  333.37
  4853.2  336.30  5015.3  335.49  5144.8  337.27  5172.4  338.08  5186.9  339.96
  5201.8  339.79  5222.2  341.68  5308.1  349.71  5381.5  356.45  5396.4  360.38
  5411.4  362.66  5468.3  367.77  5474.6  369.36  5510.8  373.78  5566.0  377.85
#Mann=6,-1,0
  3890.0    0.05       0  4821.2    0.05       0  4825.2    0.05       0
  5144.8    0.16       0  5222.2    0.12       0  5308.1    0.16       0
Bank Sta=4821.2,4825.2
Exp/Cntr=0.3,0.1

Type RM Length L Ch R = 1,4972,0,0,0
BEGIN DESCRIPTION:
South Twin Creek Trib L4971.573
END DESCRIPTION:
XS GIS Cut Line= 3
      2720725.13      6804898.03      2721626.43      6805765.73
      2722348.22      6805062.53
#Sta/Elev= 30
  3748.9  345.96  3985.1  335.99  4416.4  333.69  4642.7  334.31  4664.0  333.06
  4706.5  335.43  4713.4  333.61  4734.8  333.35  4968.1  333.38  4982.3  331.67
  4989.2  332.66  4994.2  327.93  4994.5  327.43  4998.2  327.93  5003.2  327.93
  5010.2  331.76  5017.1  330.68  5024.3  333.46  5300.1  333.83  5363.6  336.54
  5413.2  334.52  5533.4  335.28  5670.7  338.77  5732.0  341.29  5858.7  354.23
  5872.9  357.80  5879.8  357.37  5894.0  359.29  5983.1  373.90  6007.7  376.03
#Mann=6,-1,0
  3748.9    0.05       0  4994.2    0.05       0  4998.2    0.05       0
  5670.7    0.16       0  5732.0    0.12       0  5983.1    0.16       0
Bank Sta=4994.2,4998.2
Exp/Cntr=0.3,0.1

Chan Stop Cuts=-1