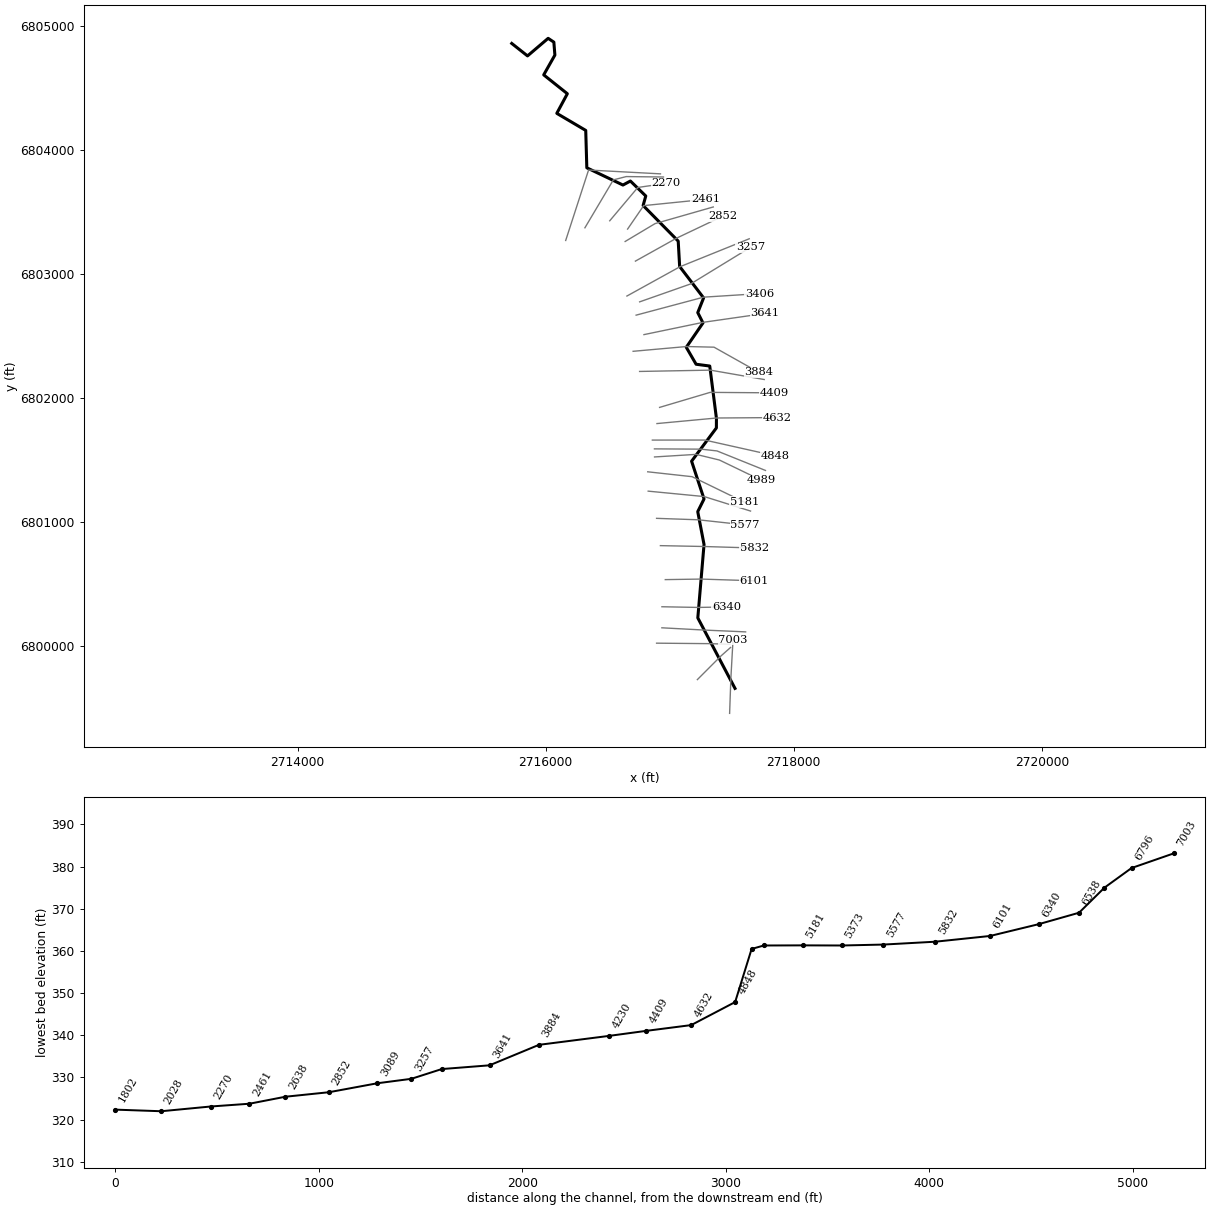
--- South Twin Creek Trib M.prj (project) ---

Proj Title=South Twin Creek Trib M Base Level Engineering
Current Plan=p01
Default Exp/Contr=0.3,0.1
English Units
Geom File=g01
Flow File=f01
Plan File=p01
BEGIN DESCRIPTION:
South Twin Creek Trib M
END DESCRIPTION:

--- South Twin Creek Trib M.p01 (plan) ---

Plan Title=Multiple Run
Short Identifier=Multiple
Geom File=g01
Flow File=f01
Subcritical Flow
K Sum by GR= 0
Std Step Tol= 0.01
Critical Tol= 0.01
Num of Std Step Trials= 20
Max Error Tol= 0.3
Flow Tol Ratio= 0.001
Split Flow NTrial= 30
Split Flow Tol= 0.02
Split Flow Ratio= 0.02
Log Output Level= 0
Friction Slope Method= 1
Unsteady Friction Slope Method= 2
Unsteady Bridges Friction Slope Method= 1
Parabolic Critical Depth
Global Vel Dist=  1 , 1 , 1
Global Log Level= 0
CheckData=True
Encroach Param= -1, 0, 0, 0
BEGIN DESCRIPTION:
Multiple Run
END DESCRIPTION:

--- South Twin Creek Trib M.f01 (steady flow) ---

Flow Title=Multiple
Number of Profiles=7
Profile Names=10-year,25-year,50-year,1pct_min,100-year,1pct_plu,500-year
River Rch & RM= South Twin Creek,Reach-1,7003
     180     223     256     146     292     582     377
River Rch & RM= South Twin Creek,Reach-1,4632
     429     566     675     401     799    1595    1117
Boundary for River Rch & Prof#=South Twin Creek,Reach-1,1
Up Type=0
Dn Type=3
Dn Slope=0.005
Boundary for River Rch & Prof#=South Twin Creek,Reach-1,2
Up Type=0
Dn Type=3
Dn Slope=0.005
Boundary for River Rch & Prof#=South Twin Creek,Reach-1,3
Up Type=0
Dn Type=3
Dn Slope=0.005
Boundary for River Rch & Prof#=South Twin Creek,Reach-1,4
Up Type=0
Dn Type=3
Dn Slope=0.005
Boundary for River Rch & Prof#=South Twin Creek,Reach-1,5
Up Type=0
Dn Type=3
Dn Slope=0.005
Boundary for River Rch & Prof#=South Twin Creek,Reach-1,6
Up Type=0
Dn Type=3
Dn Slope=0.005
Boundary for River Rch & Prof#=South Twin Creek,Reach-1,7
Up Type=0
Dn Type=3
Dn Slope=0.005

--- South Twin Creek Trib M.g01 (geometry) ---

Geom Title=Existing Conditions

River Reach=South Twin Creek,Reach-1
Reach XY= 30
      2717526.00      6799661.00      2717226.20      6800229.26
      2717276.40      6800821.21      2717225.62      6801086.00
      2717276.39      6801188.20      2717176.07      6801492.77
      2717376.00      6801761.00      2717376.36      6801838.42
      2717322.46      6802260.00      2717212.32      6802274.51
      2717133.30      6802411.08      2717267.93      6802607.69
      2717225.80      6802690.80      2717272.87      6802809.37
      2717079.75      6803062.55      2717068.20      6803267.21
      2716785.32      6803554.34      2716806.63      6803631.00
      2716682.67      6803751.70      2716622.78      6803719.29
      2716331.36      6803858.30      2716322.55      6804159.75
      2716089.27      6804297.31      2716174.38      6804455.54
      2715983.76      6804607.58      2716073.86      6804766.97
      2716065.57      6804871.54      2716019.51      6804902.12
      2715853.21      6804760.41      2715726.00      6804861.00

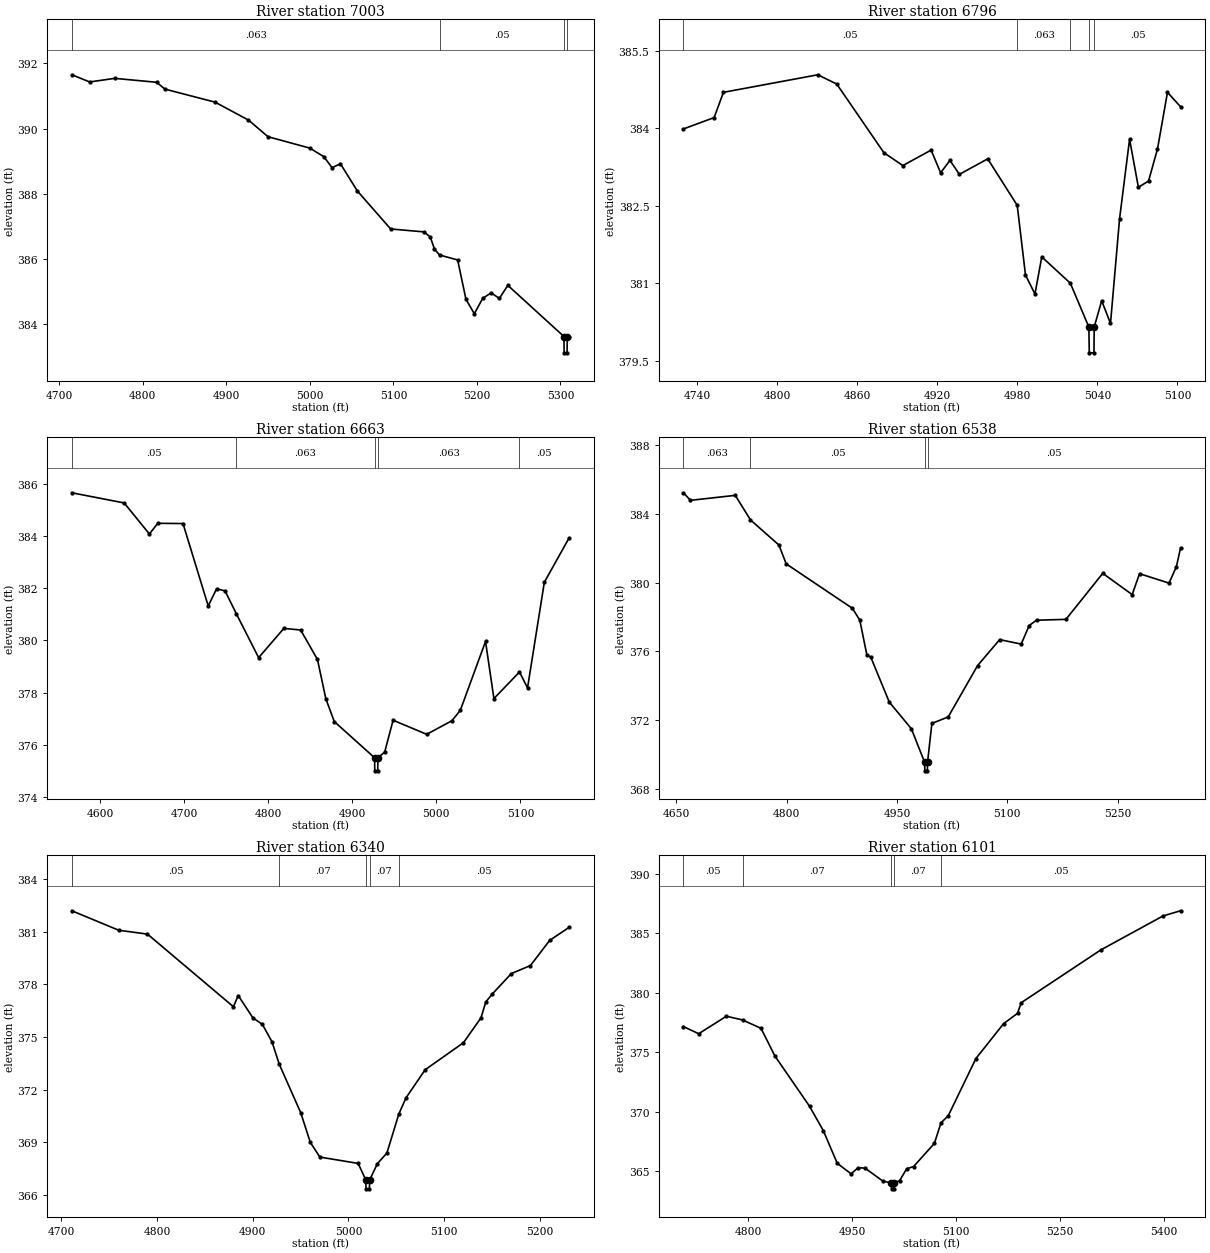
Type RM Length L Ch R = 1,7003,207,207,207
BEGIN DESCRIPTION:
South Twin Creek Trib M7003.091
END DESCRIPTION:
XS GIS Cut Line= 3
      2717482.64      6799459.59      2717492.85      6799744.41
      2717510.10      6800054.13
#Sta/Elev= 30
  4715.0  391.65  4736.4  391.43  4766.4  391.54  4816.5  391.42  4826.5  391.21
  4886.5  390.81  4926.5  390.26  4949.9  389.75  5000.0  389.40  5016.6  389.14
  5026.6  388.80  5036.6  388.92  5056.7  388.09  5096.7  386.92  5136.8  386.83
  5144.2  386.67  5149.2  386.30  5155.3  386.12  5176.9  385.97  5186.9  384.76
  5196.9  384.32  5206.9  384.79  5216.9  384.96  5226.9  384.79  5237.0  385.19
  5304.2  383.62  5304.4  383.12  5307.9  383.12  5308.2  383.62  5310.2  383.62
#Mann=4,-1,0
  4715.0   0.063       0  5155.3    0.05       0  5304.2   0.063       0
  5308.2    0.05       0
Bank Sta=5304.2,5308.2
Exp/Cntr=0.3,0.1

Type RM Length L Ch R = 1,6796,133,133,133
BEGIN DESCRIPTION:
South Twin Creek Trib M6795.77
END DESCRIPTION:
XS GIS Cut Line= 3
      2717222.65      6799731.87      2717413.83      6799923.29
      2717490.21      6799990.84
#Sta/Elev= 30
  4729.8  383.99  4752.8  384.21  4759.8  384.70  4830.5  385.04  4844.7  384.86
  4880.0  383.53  4894.2  383.28  4915.4  383.58  4922.5  383.14  4929.5  383.38
  4936.6  383.11  4957.8  383.41  4979.9  382.51  4986.1  381.16  4993.2  380.79
  4998.3  381.51  5019.7  381.00  5033.6  380.15  5033.9  379.65  5037.4  379.65
  5037.6  380.15  5043.2  380.66  5049.8  380.22  5056.6  382.25  5064.1  383.79
  5070.7  382.86  5078.3  382.98  5085.0  383.60  5092.5  384.70  5102.3  384.42
#Mann=5,-1,0
  4729.8    0.05       0  4979.9   0.063       0  5019.7    0.05       0
  5033.6   0.063       0  5037.6    0.05       0
Bank Sta=5033.6,5037.6
Exp/Cntr=0.3,0.1

Type RM Length L Ch R = 1,6663,125,125,125
BEGIN DESCRIPTION:
South Twin Creek Trib M6663.43
END DESCRIPTION:
XS GIS Cut Line= 3
      2716893.74      6800025.59      2717326.25      6800021.71
      2717485.25      6800016.72
#Sta/Elev= 30
  4566.2  385.66  4628.5  385.27  4658.5  384.08  4668.5  384.49  4698.5  384.48
  4728.5  381.32  4738.5  381.98  4748.5  381.90  4762.0  381.02  4788.5  379.34
  4818.5  380.46  4838.5  380.40  4858.5  379.27  4868.5  377.76  4878.5  376.89
  4926.5  375.50  4926.7  375.00  4930.2  375.00  4930.5  375.50  4938.5  375.72
  4948.5  376.94  4988.5  376.40  5018.5  376.92  5028.5  377.32  5058.5  379.96
  5068.5  377.77  5098.9  378.79  5108.5  378.18  5128.5  382.23  5157.8  383.92
#Mann=5,-1,0
  4566.2    0.05       0  4762.0   0.063       0  4926.5   0.063       0
  4930.5   0.063       0  5098.9    0.05       0
Bank Sta=4926.5,4930.5
Exp/Cntr=0.3,0.1

Type RM Length L Ch R = 1,6538,198,198,198
BEGIN DESCRIPTION:
South Twin Creek Trib M6538.04
END DESCRIPTION:
XS GIS Cut Line= 3
      2716936.42      6800149.53      2717276.65      6800131.40
      2717611.72      6800116.66
#Sta/Elev= 30
  4659.5  385.24  4669.1  384.80  4730.0  385.09  4750.7  383.66  4789.3  382.20
  4799.3  381.10  4889.4  378.51  4899.4  377.82  4909.1  375.77  4914.1  375.69
  4939.5  373.05  4969.5  371.50  4987.5  369.55  4987.8  369.05  4991.3  369.05
  4991.5  369.55  4997.4  371.81  5019.6  372.19  5059.6  375.18  5089.6  376.69
  5118.9  376.43  5129.7  377.51  5139.7  377.82  5179.7  377.87  5229.8  380.55
  5269.8  379.31  5279.8  380.53  5319.9  379.98  5329.9  380.93  5335.6  382.03
#Mann=4,-1,0
  4659.5   0.063       0  4750.7    0.05       0  4987.5    0.05       0
  4991.5    0.05       0
Bank Sta=4987.5,4991.5
Exp/Cntr=0.3,0.1

Type RM Length L Ch R = 1,6340,239,239,239
BEGIN DESCRIPTION:
South Twin Creek Trib M6339.72
END DESCRIPTION:
XS GIS Cut Line= 3
      2716936.97      6800319.25      2717226.85      6800313.82
      2717456.19      6800317.38
#Sta/Elev= 30
  4711.0  382.19  4760.0  381.08  4790.0  380.86  4879.8  376.72  4884.8  377.36
  4900.1  376.09  4910.1  375.71  4920.1  374.72  4927.7  373.44  4950.1  370.68
  4960.1  368.99  4970.1  368.15  5010.1  367.79  5018.1  366.84  5018.3  366.34
  5021.8  366.34  5022.1  366.84  5030.1  367.77  5040.1  368.38  5052.6  370.61
  5060.1  371.53  5080.1  373.13  5120.1  374.67  5138.4  376.09  5143.4  376.99
  5150.1  377.44  5170.1  378.61  5190.1  379.07  5210.1  380.50  5230.3  381.24
#Mann=5,-1,0
  4711.0    0.05       0  4927.7    0.07       0  5018.1    0.07       0
  5022.1    0.07       0  5052.6    0.05       0
Bank Sta=5018.1,5022.1
Exp/Cntr=0.3,0.1

Type RM Length L Ch R = 1,6101,269,269,269
BEGIN DESCRIPTION:
South Twin Creek Trib M6100.73
END DESCRIPTION:
XS GIS Cut Line= 3
      2716964.00      6800537.97      2717252.52      6800542.46
      2717681.14      6800528.55
#Sta/Elev= 30
  4706.9  377.16  4728.9  376.56  4768.9  378.03  4792.6  377.71  4818.9  377.01
  4838.9  374.69  4888.9  370.47  4908.9  368.41  4928.9  365.68  4948.9  364.80
  4958.9  365.31  4968.9  365.28  4994.7  364.19  5006.9  364.04  5007.2  363.54
  5010.7  363.54  5010.9  364.04  5018.9  364.23  5029.0  365.22  5039.0  365.41
  5069.0  367.35  5078.6  369.08  5089.0  369.67  5129.0  374.48  5169.0  377.41
  5189.0  378.27  5194.3  379.16  5309.1  383.59  5399.1  386.45  5424.3  386.88
#Mann=5,-1,0
  4706.9    0.05       0  4792.6    0.07       0  5006.9    0.07       0
  5010.9    0.07       0  5078.6    0.05       0
Bank Sta=5006.9,5010.9
Exp/Cntr=0.3,0.1

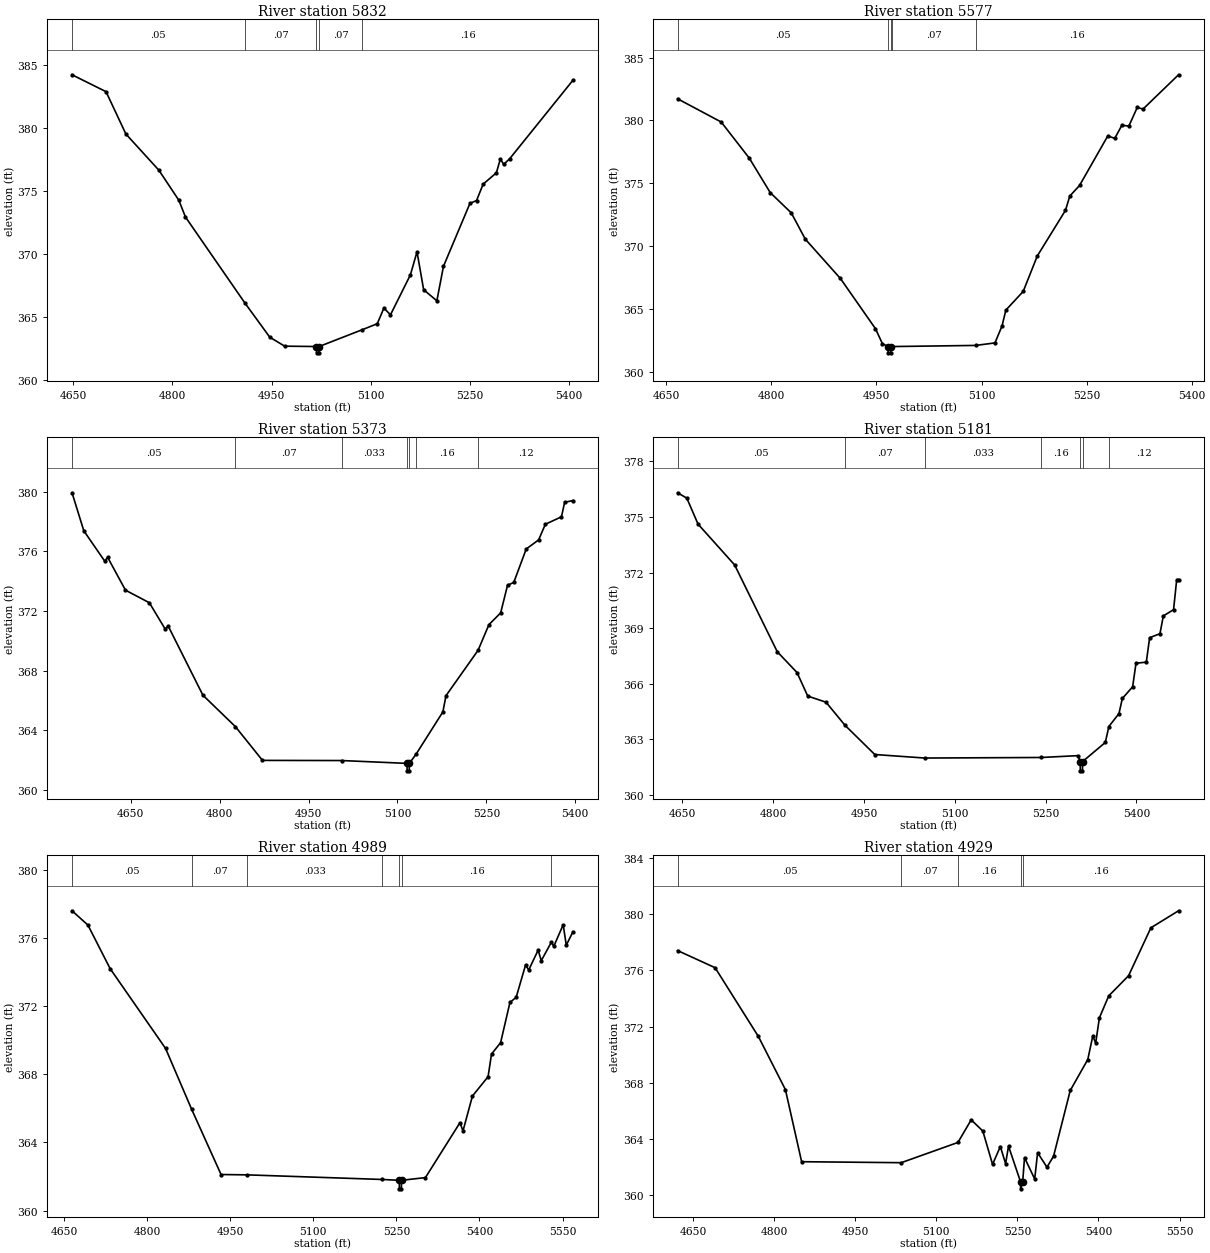
Type RM Length L Ch R = 1,5832,255,255,255
BEGIN DESCRIPTION:
South Twin Creek Trib M5832.41
END DESCRIPTION:
XS GIS Cut Line= 3
      2716924.58      6800811.98      2717277.72      6800804.97
      2717681.73      6800792.69
#Sta/Elev= 30
  4648.2  384.25  4699.6  382.91  4729.6  379.55  4779.6  376.67  4809.7  374.29
  4819.7  372.96  4909.1  366.17  4947.2  363.42  4969.7  362.71  5017.7  362.68
  5017.9  362.18  5021.4  362.18  5021.7  362.68  5087.2  364.02  5109.7  364.49
  5119.7  365.73  5129.7  365.20  5159.8  368.37  5169.8  370.20  5179.8  367.19
  5199.8  366.31  5209.8  369.05  5249.8  374.04  5259.8  374.27  5269.8  375.57
  5289.8  376.47  5295.8  377.57  5300.8  377.14  5309.8  377.58  5405.6  383.82
#Mann=5,-1,0
  4648.2    0.05       0  4909.1    0.07       0  5017.7    0.07       0
  5021.7    0.07       0  5087.2    0.16       0
Bank Sta=5017.7,5021.7
Exp/Cntr=0.3,0.1

Type RM Length L Ch R = 1,5577,204,204,204
BEGIN DESCRIPTION:
South Twin Creek Trib M5577.39
END DESCRIPTION:
XS GIS Cut Line= 3
      2716893.78      6801032.07      2717230.46      6801020.35
      2717606.43      6800979.25
#Sta/Elev= 30
  4666.1  381.72  4728.4  379.87  4768.4  377.00  4798.4  374.25  4828.4  372.64
  4848.4  370.55  4898.5  367.42  4948.5  363.43  4958.5  362.23  4966.5  362.00
  4966.8  361.50  4970.3  361.50  4970.5  362.00  4972.7  362.00  5091.5  362.09
  5119.2  362.29  5129.3  363.65  5134.7  364.90  5159.5  366.39  5179.6  369.21
  5219.8  372.84  5226.0  373.98  5239.9  374.82  5280.2  378.76  5290.2  378.57
  5300.3  379.61  5310.3  379.55  5322.3  381.03  5330.5  380.90  5381.2  383.63
#Mann=5,-1,0
  4666.1    0.05       0  4966.5    0.07       0  4970.5    0.05       0
  4972.7    0.07       0  5091.5    0.16       0
Bank Sta=4966.5,4970.5
Exp/Cntr=0.3,0.1

Type RM Length L Ch R = 1,5373,192,192,192
BEGIN DESCRIPTION:
South Twin Creek Trib M5372.92
END DESCRIPTION:
XS GIS Cut Line= 3
      2716826.19      6801251.31      2717277.62      6801207.61
      2717651.35      6801090.80
#Sta/Elev= 30
  4551.0  379.92  4570.9  377.37  4606.1  375.34  4611.1  375.59  4641.2  373.39
  4681.4  372.55  4708.2  370.78  4713.2  370.99  4771.8  366.35  4826.7  364.24
  4872.3  361.98  5005.9  361.97  5116.1  361.78  5116.3  361.28  5119.8  361.28
  5120.1  361.78  5131.6  362.41  5176.6  365.23  5181.9  366.32  5236.0  369.36
  5254.3  371.08  5274.1  371.87  5285.7  373.72  5296.2  373.91  5317.2  376.15
  5338.1  376.76  5349.5  377.81  5376.7  378.31  5382.0  379.28  5396.1  379.40
#Mann=7,-1,0
  4551.0    0.05       0  4826.7    0.07       0  5005.9   0.033       0
  5116.1    0.07       0  5120.1   0.033       0  5131.6    0.16       0
  5236.0    0.12       0
Bank Sta=5116.1,5120.1
Exp/Cntr=0.3,0.1

Type RM Length L Ch R = 1,5181,192,192,192
BEGIN DESCRIPTION:
South Twin Creek Trib M5181.4
END DESCRIPTION:
XS GIS Cut Line= 3
      2716822.40      6801407.30      2717179.97      6801367.92
      2717600.18      6801163.33
#Sta/Elev= 30
  4642.3  376.30  4657.6  376.01  4676.1  374.61  4736.5  372.41  4806.9  367.73
  4839.5  366.61  4857.2  365.34  4887.4  365.01  4918.6  363.77  4967.9  362.19
  5050.5  362.00  5243.0  362.03  5303.4  362.13  5307.0  361.81  5307.3  361.31
  5310.8  361.31  5311.0  361.81  5348.5  362.84  5354.4  363.70  5371.1  364.40
  5376.6  365.21  5393.6  365.84  5399.2  367.11  5416.2  367.17  5421.7  368.49
  5438.7  368.70  5444.3  369.66  5461.2  370.00  5466.4  371.62  5469.4  371.62
#Mann=7,-1,0
  4642.3    0.05       0  4918.6    0.07       0  5050.5   0.033       0
  5243.0    0.16       0  5307.0    0.07       0  5311.0    0.16       0
  5354.4    0.12       0
Bank Sta=5307,5311
Exp/Cntr=0.3,0.1

Type RM Length L Ch R = 1,4989,60,60,60
BEGIN DESCRIPTION:
South Twin Creek Trib M4988.735
END DESCRIPTION:
XS GIS Cut Line= 4
      2716877.39      6801527.03      2717212.35      6801547.80
      2717400.14      6801502.29      2717738.52      6801339.09
#Sta/Elev= 30
  4664.4  377.60  4693.1  376.76  4733.1  374.21  4833.3  369.52  4880.5  365.94
  4933.5  362.12  4980.8  362.10  5224.5  361.83  5255.3  361.78  5255.5  361.28
  5259.0  361.28  5259.3  361.78  5302.5  361.94  5364.8  365.16  5370.3  364.68
  5387.4  366.73  5415.6  367.86  5421.8  369.19  5438.2  369.86  5455.1  372.22
  5466.3  372.52  5483.4  374.43  5488.9  374.12  5506.0  375.29  5511.6  374.67
  5530.1  375.77  5534.2  375.51  5551.2  376.78  5556.8  375.58  5568.9  376.37
#Mann=7,-1,0
  4664.4    0.05       0  4880.5    0.07       0  4980.8   0.033       0
  5224.5    0.16       0  5255.3   0.033       0  5259.3    0.16       0
  5530.1    0.12       0
Bank Sta=5255.3,5259.3
Exp/Cntr=0.3,0.1

Type RM Length L Ch R = 1,4929,81,81,81
BEGIN DESCRIPTION:
South Twin Creek Trib M4929.12
END DESCRIPTION:
XS GIS Cut Line= 4
      2716876.58      6801592.12      2717251.70      6801589.95
      2717380.73      6801575.61      2717771.68      6801418.21
#Sta/Elev= 30
  4621.7  377.41  4691.1  376.19  4771.1  371.30  4821.1  367.52  4851.1  362.39
  5035.3  362.32  5140.2  363.76  5164.7  365.37  5186.2  364.57  5204.2  362.20
  5218.6  363.47  5228.3  362.25  5233.7  363.50  5255.9  360.96  5256.1  360.46
  5259.9  360.96  5263.3  362.68  5282.1  361.16  5287.5  363.03  5304.8  362.00
  5317.0  362.78  5347.9  367.46  5380.3  369.66  5389.5  371.33  5394.9  370.83
  5401.8  372.63  5419.1  374.19  5455.7  375.62  5497.0  379.03  5548.1  380.24
#Mann=5,-1,0
  4621.7    0.05       0  5035.3    0.07       0  5140.2    0.16       0
  5255.9    0.05       0  5259.9    0.16       0
Bank Sta=5255.9,5259.9
Exp/Cntr=0.3,0.1

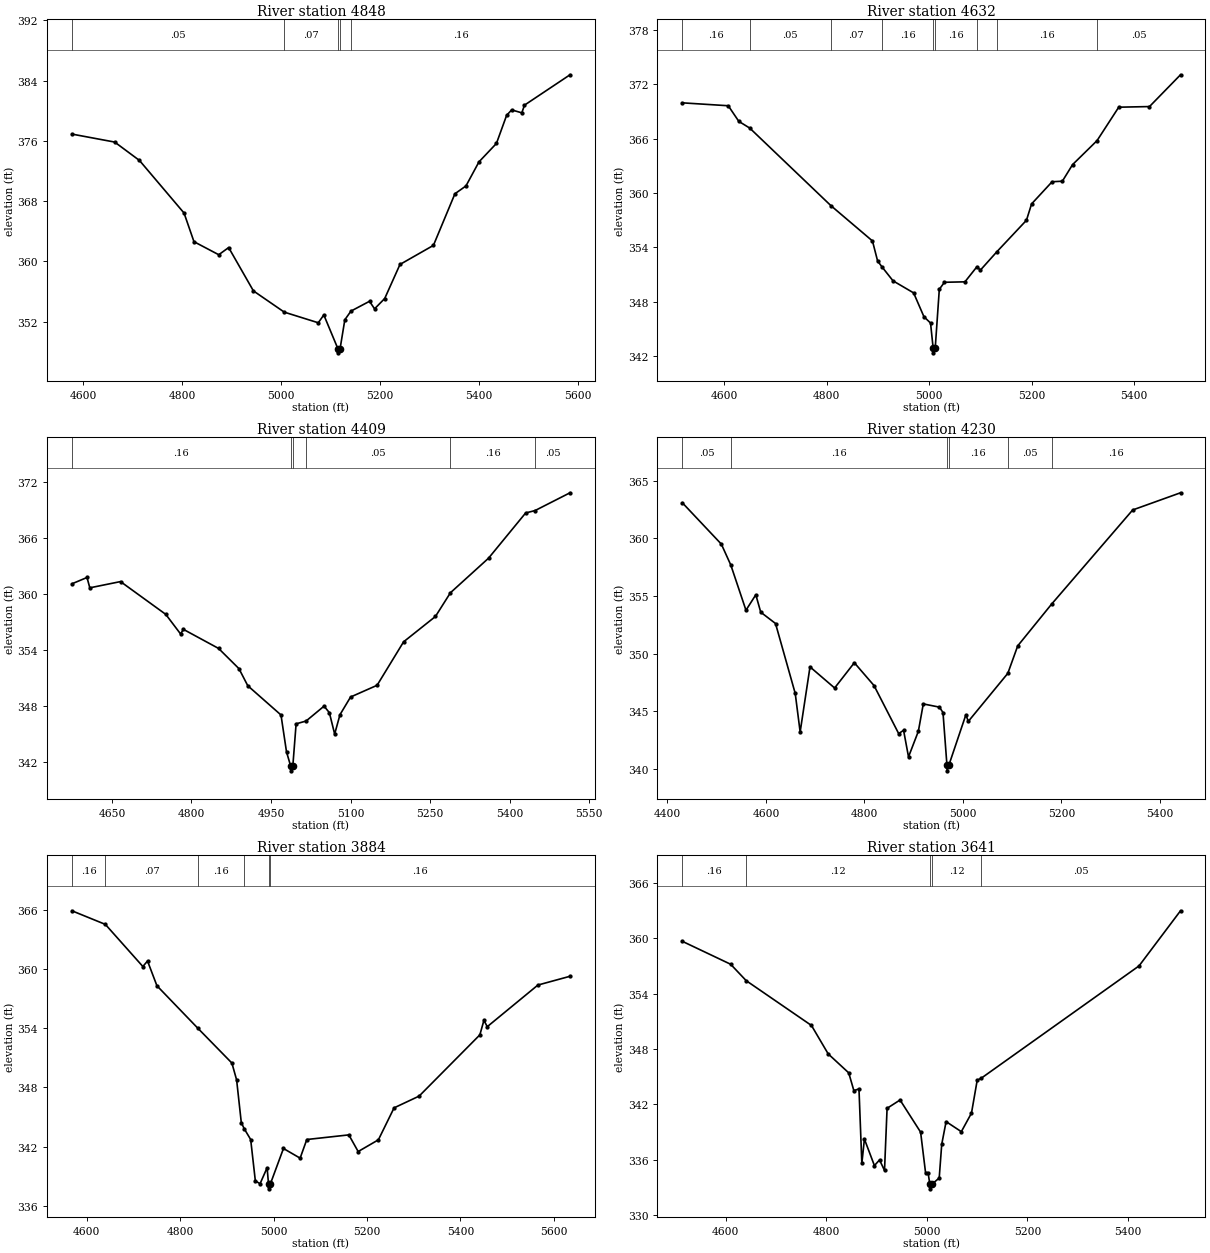
Type RM Length L Ch R = 1,4848,216,216,216
BEGIN DESCRIPTION:
South Twin Creek Trib M4848.298
END DESCRIPTION:
XS GIS Cut Line= 3
      2716859.61      6801663.00      2717281.81      6801663.31
      2717850.95      6801536.01
#Sta/Elev= 30
  4577.8  376.89  4664.2  375.83  4714.2  373.39  4804.2  366.41  4824.2  362.61
  4874.2  360.88  4894.2  361.83  4944.2  356.08  5006.5  353.26  5075.1  351.85
  5086.3  352.89  5115.0  348.36  5115.3  347.86  5119.0  348.36  5128.7  352.25
  5141.1  353.40  5178.5  354.70  5188.7  353.70  5209.2  355.07  5240.0  359.59
  5307.5  362.12  5350.9  368.97  5373.2  370.01  5399.4  373.20  5434.7  375.65
  5455.2  379.37  5465.4  380.10  5485.9  379.71  5491.3  380.73  5583.2  384.76
#Mann=5,-1,0
  4577.8    0.05       0  5006.5    0.07       0  5115.0    0.05       0
  5119.0    0.07       0  5141.1    0.16       0
Bank Sta=5115,5119
Exp/Cntr=0.3,0.1

Type RM Length L Ch R = 1,4632,223,223,223
BEGIN DESCRIPTION:
South Twin Creek Trib M4632.4
END DESCRIPTION:
XS GIS Cut Line= 3
      2716896.86      6801796.19      2717376.74      6801841.02
      2717866.45      6801844.54
#Sta/Elev= 30
  4518.6  369.93  4608.1  369.61  4628.7  367.89  4650.0  367.15  4808.3  358.61
  4889.4  354.72  4899.4  352.52  4907.5  351.90  4929.5  350.33  4969.7  349.00
  4989.8  346.38  5002.7  345.68  5007.8  342.90  5008.1  342.40  5011.8  342.90
  5019.8  349.40  5029.8  350.17  5069.8  350.22  5093.3  351.89  5099.8  351.50
  5132.2  353.54  5189.8  357.00  5199.8  358.80  5239.8  361.24  5259.8  361.30
  5279.8  363.13  5327.5  365.77  5369.8  369.45  5429.8  369.52  5490.3  373.02
#Mann=9,-1,0
  4518.6    0.16       0  4650.0    0.05       0  4808.3    0.07       0
  4907.5    0.16       0  5007.8    0.07       0  5011.8    0.16       0
  5093.3    0.07       0  5132.2    0.16       0  5327.5    0.05       0
Bank Sta=5007.8,5011.8
Exp/Cntr=0.3,0.1

Type RM Length L Ch R = 1,4409,179,179,179
BEGIN DESCRIPTION:
South Twin Creek Trib M4409.47
END DESCRIPTION:
XS GIS Cut Line= 3
      2716918.07      6801926.55      2717325.64      6802047.66
      2717839.74      6802043.94
#Sta/Elev= 30
  4574.5  361.11  4603.0  361.79  4608.3  360.68  4666.2  361.35  4751.5  357.83
  4779.5  355.72  4784.7  356.22  4851.1  354.17  4889.5  352.00  4906.2  350.16
  4968.8  347.02  4979.2  343.06  4987.1  341.52  4987.4  341.02  4991.1  341.52
  4997.3  346.07  5016.1  346.37  5050.0  347.97  5060.0  347.27  5070.0  344.97
  5080.0  347.05  5100.0  348.95  5150.0  350.21  5200.0  354.88  5260.0  357.60
  5288.3  360.15  5360.1  363.86  5430.1  368.72  5447.9  368.98  5513.8  370.89
#Mann=6,-1,0
  4574.5    0.16       0  4987.1    0.07       0  4991.1    0.16       0
  5016.1    0.05       0  5288.3    0.16       0  5447.9    0.05       0
Bank Sta=4987.1,4991.1
Exp/Cntr=0.3,0.1

Type RM Length L Ch R = 1,4230,346,346,346
BEGIN DESCRIPTION:
South Twin Creek Trib M4230.2
END DESCRIPTION:
XS GIS Cut Line= 3
      2716756.96      6802216.38      2717328.12      6802226.95
      2717761.62      6802151.37
#Sta/Elev= 30
  4430.4  363.08  4509.5  359.50  4528.7  357.69  4559.5  353.77  4579.5  355.11
  4589.5  353.60  4619.5  352.62  4659.5  346.56  4669.5  343.22  4689.5  348.86
  4739.5  347.03  4779.5  349.22  4819.5  347.24  4869.5  343.08  4879.5  343.36
  4889.5  341.06  4909.5  343.28  4919.5  345.65  4952.4  345.37  4959.5  344.90
  4967.5  340.35  4967.8  339.85  4971.5  340.35  5005.9  344.70  5011.0  344.14
  5091.1  348.30  5111.2  350.68  5179.8  354.29  5344.6  362.46  5441.7  363.95
#Mann=6,-1,0
  4430.4    0.05       0  4528.7    0.16       0  4967.5    0.07       0
  4971.5    0.16       0  5091.1    0.05       0  5179.8    0.16       0
Bank Sta=4967.5,4971.5
Exp/Cntr=0.3,0.1

Type RM Length L Ch R = 1,3884,243,243,243
BEGIN DESCRIPTION:
South Twin Creek Trib M3884.3
END DESCRIPTION:
XS GIS Cut Line= 4
      2716704.64      6802378.82      2717136.20      6802417.35
      2717356.94      6802412.05      2717716.79      6802209.95
#Sta/Elev= 30
  4568.0  365.91  4639.7  364.53  4720.0  360.26  4730.0  360.82  4750.1  358.31
  4838.0  353.99  4910.7  350.47  4920.8  348.76  4930.8  344.44  4937.1  343.81
  4950.9  342.72  4960.9  338.52  4971.0  338.24  4986.1  339.86  4989.1  338.22
  4989.3  337.72  4993.1  338.22  5021.1  341.81  5056.8  340.83  5071.1  342.72
  5161.1  343.19  5181.1  341.50  5224.4  342.69  5258.0  345.93  5311.6  347.12
  5441.7  353.33  5450.4  354.80  5457.6  354.16  5566.0  358.38  5634.8  359.27
#Mann=6,-1,0
  4568.0    0.16       0  4639.7    0.07       0  4838.0    0.16       0
  4937.1    0.12       0  4989.1    0.07       0  4993.1    0.16       0
Bank Sta=4989.1,4993.1
Exp/Cntr=0.3,0.1

Type RM Length L Ch R = 1,3641,235,235,235
BEGIN DESCRIPTION:
South Twin Creek Trib M3640.81
END DESCRIPTION:
XS GIS Cut Line= 3
      2716792.00      6802513.31      2717270.68      6802612.68
      2717767.62      6802683.89
#Sta/Elev= 30
  4513.6  359.66  4609.6  357.18  4640.6  355.40  4770.4  350.55  4803.7  347.47
  4844.5  345.42  4854.7  343.50  4864.9  343.68  4870.6  335.61  4875.7  338.25
  4895.6  335.38  4905.8  335.99  4915.7  334.85  4920.8  341.58  4946.6  342.48
  4987.5  339.00  4997.5  334.54  5002.5  334.54  5005.9  333.36  5006.1  332.86
  5009.9  333.36  5024.5  334.03  5029.5  337.68  5038.2  340.14  5068.5  339.05
  5088.7  341.06  5100.1  344.63  5107.9  344.83  5422.0  357.00  5504.5  362.97
#Mann=5,-1,0
  4513.6    0.16       0  4640.6    0.12       0  5005.9    0.07       0
  5009.9    0.12       0  5107.9    0.05       0
Bank Sta=5005.9,5009.9
Exp/Cntr=0.3,0.1

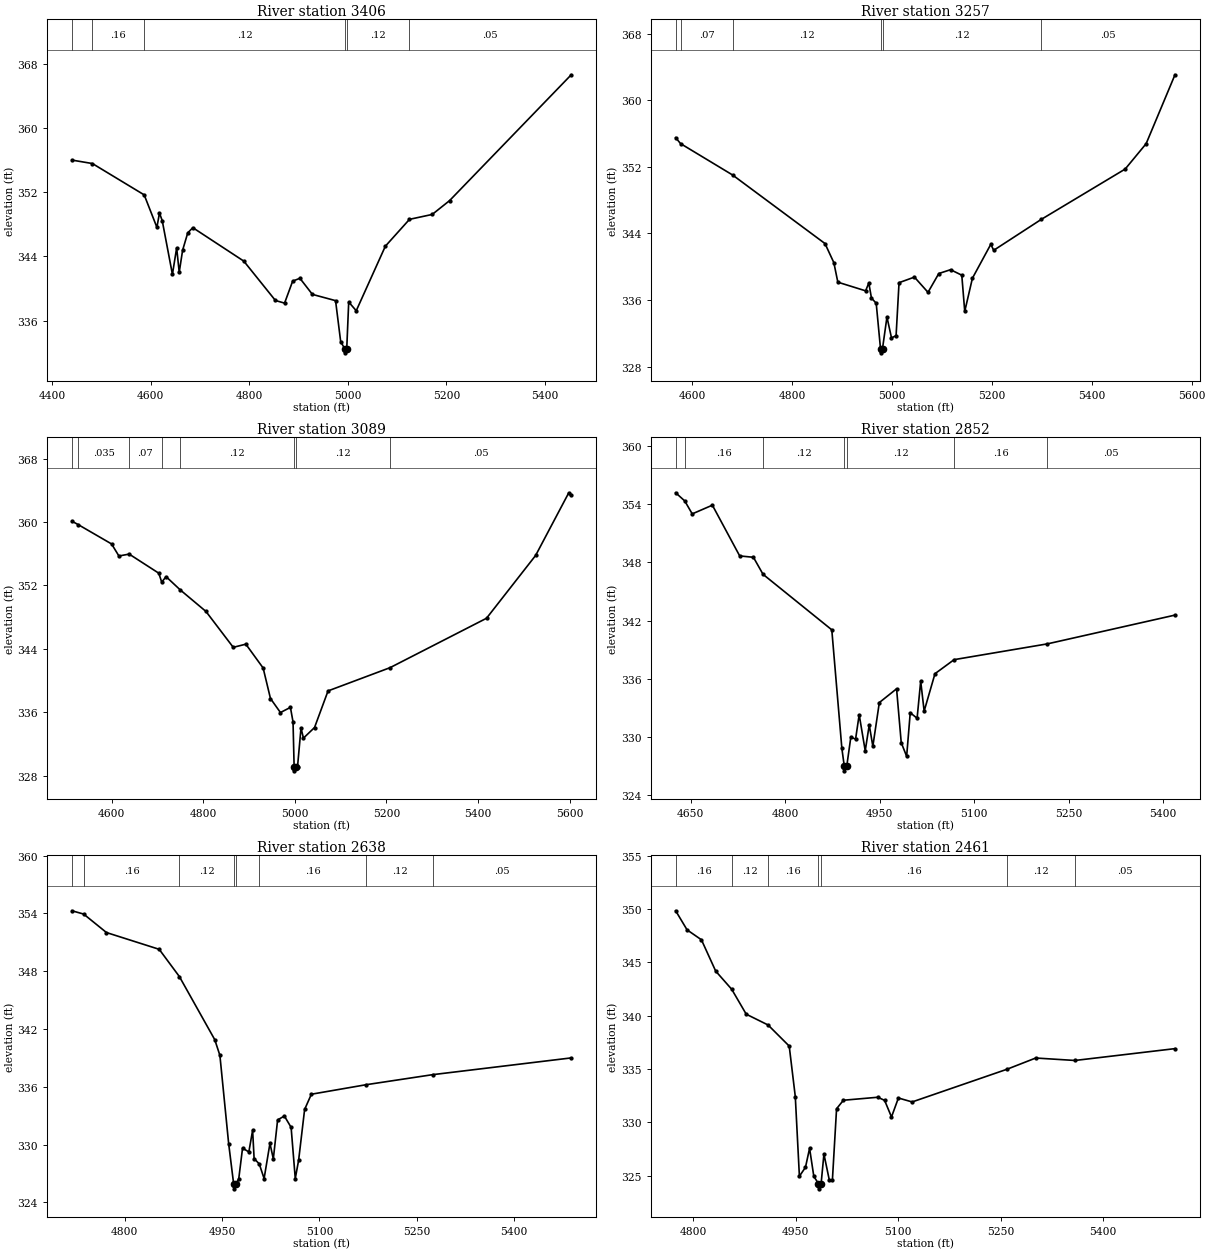
Type RM Length L Ch R = 1,3406,149,149,149
BEGIN DESCRIPTION:
South Twin Creek Trib M3406.46
END DESCRIPTION:
XS GIS Cut Line= 3
      2716728.86      6802670.32      2717272.62      6802815.34
      2717722.65      6802843.85
#Sta/Elev= 30
  4439.9  356.01  4481.4  355.58  4586.6  351.67  4612.4  347.62  4617.6  349.41
  4623.2  348.46  4643.9  341.76  4652.5  345.06  4657.7  342.02  4664.6  344.77
  4675.0  346.93  4685.3  347.58  4788.8  343.41  4853.0  338.50  4871.6  338.17
  4888.0  340.91  4902.7  341.27  4928.1  339.26  4975.1  338.48  4985.5  333.37
  4993.8  332.47  4994.1  331.97  4997.8  332.47  5001.8  338.31  5017.1  337.22
  5076.2  345.27  5125.2  348.62  5171.3  349.23  5206.5  350.95  5453.6  366.65
#Mann=6,-1,0
  4439.9    0.07       0  4481.4    0.16       0  4586.6    0.12       0
  4993.8    0.07       0  4997.8    0.12       0  5125.2    0.05       0
Bank Sta=4993.8,4997.8
Exp/Cntr=0.3,0.1

Type RM Length L Ch R = 1,3257,168,168,168
BEGIN DESCRIPTION:
South Twin Creek Trib M3257.29
END DESCRIPTION:
XS GIS Cut Line= 3
      2716757.29      6802777.48      2717168.68      6802922.04
      2717649.18      6803216.12
#Sta/Elev= 30
  4567.2  355.51  4577.0  354.80  4681.1  351.03  4866.1  342.79  4883.8  340.50
  4891.8  338.15  4947.4  337.11  4953.8  338.05  4959.1  336.24  4968.6  335.62
  4977.2  330.16  4977.5  329.66  4981.2  330.16  4990.1  333.96  4999.2  331.46
  5008.4  331.72  5014.3  338.09  5045.1  338.76  5072.3  336.93  5093.9  339.19
  5117.4  339.65  5139.9  338.99  5145.8  334.64  5161.2  338.63  5198.0  342.70
  5203.8  341.98  5298.9  345.69  5466.9  351.74  5508.9  354.79  5566.6  363.07
#Mann=6,-1,0
  4567.2    0.05       0  4577.0    0.07       0  4681.1    0.12       0
  4977.2    0.07       0  4981.2    0.12       0  5298.9    0.05       0
Bank Sta=4977.2,4981.2
Exp/Cntr=0.3,0.1

Type RM Length L Ch R = 1,3089,237,237,237
BEGIN DESCRIPTION:
South Twin Creek Trib M3089.29
END DESCRIPTION:
XS GIS Cut Line= 3
      2716654.67      6802824.45      2717081.66      6803060.31
      2717640.80      6803286.07
#Sta/Elev= 30
  4512.9  360.11  4526.3  359.69  4599.5  357.24  4615.5  355.72  4637.9  355.96
  4702.6  353.55  4709.0  352.42  4718.6  353.11  4749.5  351.44  4805.7  348.72
  4865.3  344.19  4892.8  344.59  4930.6  341.58  4946.6  337.73  4968.4  335.96
  4990.2  336.61  4995.9  334.78  4998.3  329.10  4998.6  328.60  5002.3  329.10
  5005.7  329.10  5013.3  333.99  5018.7  332.73  5042.9  334.07  5072.4  338.69
  5207.7  341.62  5418.6  347.86  5525.9  355.79  5598.3  363.70  5603.7  363.45
#Mann=8,-1,0
  4512.9    0.05       0  4526.3   0.035       0  4637.9    0.07       0
  4709.0   0.035       0  4749.5    0.12       0  4998.3    0.07       0
  5002.3    0.12       0  5207.7    0.05       0
Bank Sta=4998.3,5002.3
Exp/Cntr=0.3,0.1

Type RM Length L Ch R = 1,2852,214,214,214
BEGIN DESCRIPTION:
South Twin Creek Trib M2851.85
END DESCRIPTION:
XS GIS Cut Line= 3
      2716723.05      6803105.95      2717055.19      6803291.11
      2717427.95      6803468.54
#Sta/Elev= 30
  4626.0  355.19  4640.4  354.35  4652.3  353.01  4684.3  353.91  4727.7  348.67
  4749.5  348.53  4764.8  346.77  4874.0  341.04  4890.0  328.79  4893.8  326.98
  4894.0  326.48  4897.8  326.98  4904.2  329.95  4911.8  329.76  4917.5  332.28
  4927.1  328.55  4933.5  331.22  4939.2  329.01  4949.5  333.53  4976.9  334.95
  4984.3  329.39  4992.9  327.98  4998.6  332.48  5009.5  331.91  5015.2  335.74
  5020.7  332.65  5037.9  336.51  5068.3  337.96  5216.5  339.59  5419.1  342.56
#Mann=7,-1,0
  4626.0   0.035       0  4640.4    0.16       0  4764.8    0.12       0
  4893.8    0.07       0  4897.8    0.12       0  5068.3    0.16       0
  5216.5    0.05       0
Bank Sta=4893.8,4897.8
Exp/Cntr=0.3,0.1

Type RM Length L Ch R = 1,2638,177,177,177
BEGIN DESCRIPTION:
South Twin Creek Trib M2637.79
END DESCRIPTION:
XS GIS Cut Line= 3
      2716640.36      6803264.24      2716881.52      6803408.33
      2717350.89      6803542.54
#Sta/Elev= 30
  4718.8  354.27  4736.8  353.93  4772.0  352.01  4853.2  350.27  4884.3  347.44
  4938.8  340.89  4946.7  339.26  4960.2  330.10  4967.9  325.91  4968.2  325.41
  4971.9  325.91  4975.8  326.48  4981.6  329.64  4991.3  329.24  4997.1  331.48
  4999.4  328.55  5007.3  328.00  5014.8  326.48  5023.8  330.13  5029.0  328.52
  5035.6  332.56  5046.0  332.97  5056.4  331.79  5062.8  326.48  5068.0  328.39
  5077.2  333.65  5087.6  335.23  5172.2  336.22  5274.4  337.26  5487.9  339.00
#Mann=8,-1,0
  4718.8   0.035       0  4736.8    0.16       0  4884.3    0.12       0
  4967.9    0.07       0  4971.9    0.12       0  5007.3    0.16       0
  5172.2    0.12       0  5274.4    0.05       0
Bank Sta=4967.9,4971.9
Exp/Cntr=0.3,0.1

Type RM Length L Ch R = 1,2461,191,191,191
BEGIN DESCRIPTION:
South Twin Creek Trib M2461.2
END DESCRIPTION:
XS GIS Cut Line= 3
      2716660.11      6803364.29      2716789.93      6803553.41
      2717288.79      6803603.89
#Sta/Elev= 30
  4774.4  349.83  4791.1  348.04  4812.1  347.11  4833.0  344.17  4856.4  342.47
  4877.7  340.13  4909.6  339.12  4940.6  337.14  4949.5  332.40  4955.5  324.93
  4964.4  325.77  4970.4  327.55  4976.6  324.92  4983.3  324.25  4983.6  323.75
  4987.3  324.25  4991.4  327.01  4999.3  324.57  5003.8  324.57  5009.9  331.26
  5019.9  332.06  5070.2  332.34  5080.2  332.05  5090.3  330.49  5100.4  332.27
  5120.5  331.90  5259.5  334.97  5301.4  336.02  5358.8  335.79  5505.2  336.90
#Mann=7,-1,0
  4774.4    0.16       0  4856.4    0.12       0  4909.6    0.16       0
  4983.3    0.07       0  4987.3    0.16       0  5259.5    0.12       0
  5358.8    0.05       0
Bank Sta=4983.3,4987.3
Exp/Cntr=0.3,0.1

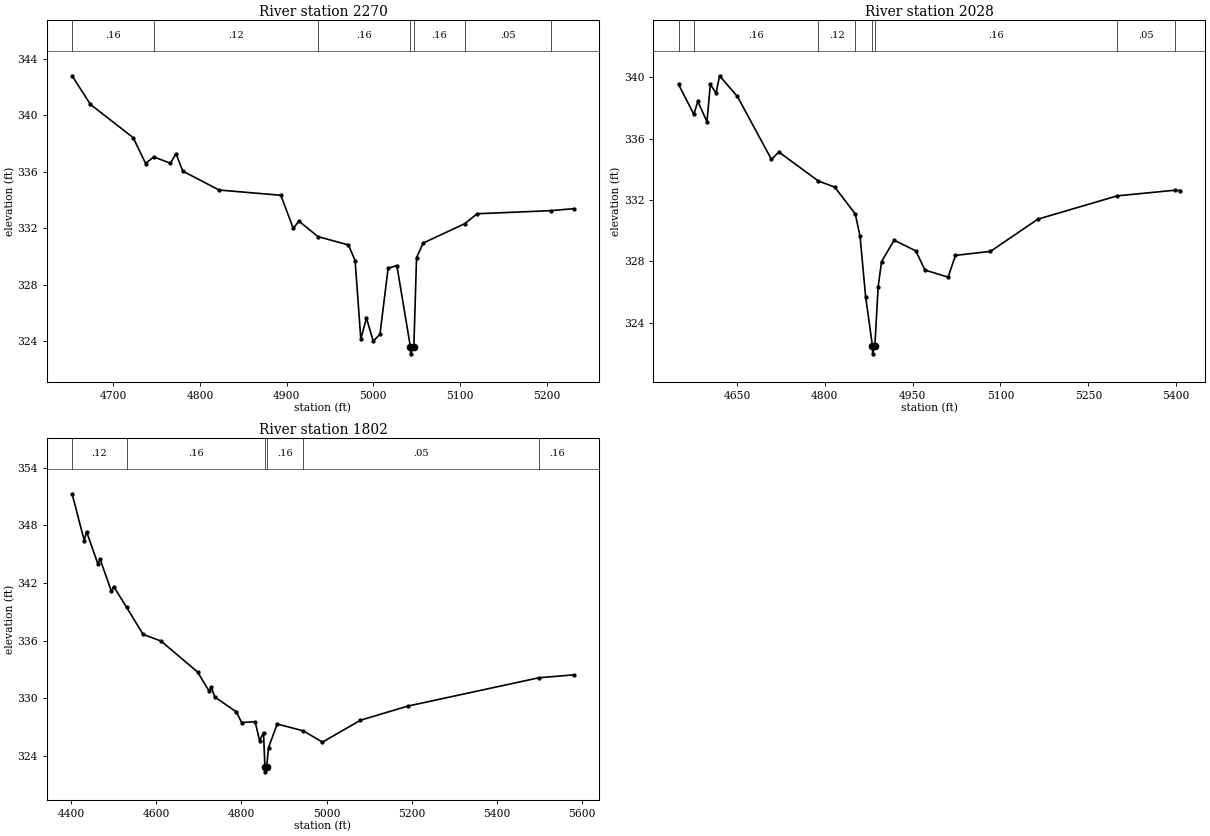
Type RM Length L Ch R = 1,2270,242,242,242
BEGIN DESCRIPTION:
South Twin Creek Trib M2270.11
END DESCRIPTION:
XS GIS Cut Line= 3
      2716516.19      6803431.18      2716742.40      6803699.66
      2716968.14      6803732.58
#Sta/Elev= 30
  4652.3  342.80  4673.5  340.77  4722.9  338.41  4737.2  336.58  4746.5  337.05
  4765.8  336.60  4772.3  337.28  4780.1  336.04  4822.1  334.70  4893.3  334.33
  4907.6  331.98  4914.1  332.50  4936.1  331.40  4971.3  330.81  4979.0  329.70
  4985.6  324.13  4992.1  325.63  4999.9  323.99  5007.7  324.48  5017.1  329.16
  5027.2  329.35  5042.8  323.59  5043.1  323.09  5046.8  323.59  5049.9  329.90
  5057.5  330.94  5105.3  332.31  5119.9  333.02  5204.9  333.24  5231.5  333.38
#Mann=7,-1,0
  4652.3    0.16       0  4746.5    0.12       0  4936.1    0.16       0
  5042.8    0.07       0  5046.8    0.16       0  5105.3    0.05       0
  5204.9    0.16       0
Bank Sta=5042.8,5046.8
Exp/Cntr=0.3,0.1

Type RM Length L Ch R = 1,2028,226,226,226
BEGIN DESCRIPTION:
South Twin Creek Trib M2027.57
END DESCRIPTION:
XS GIS Cut Line= 4
      2716316.01      6803374.62      2716545.39      6803760.93
      2716649.19      6803787.56      2716949.33      6803784.09
#Sta/Elev= 30
  4550.4  339.54  4576.5  337.59  4583.3  338.43  4598.9  337.11  4604.7  339.54
  4614.5  338.97  4620.4  340.10  4650.9  338.75  4709.0  334.65  4721.7  335.13
  4789.0  333.24  4817.1  332.84  4852.1  331.09  4860.2  329.65  4869.8  325.69
  4881.5  322.47  4881.7  321.97  4885.5  322.47  4891.2  326.35  4897.0  327.99
  4918.5  329.38  4955.5  328.68  4971.1  327.43  5010.6  326.97  5023.1  328.39
  5082.9  328.65  5163.7  330.75  5299.2  332.27  5398.2  332.64  5407.0  332.62
#Mann=8,-1,0
  4550.4    0.12       0  4576.5    0.16       0  4789.0    0.12       0
  4852.1    0.16       0  4881.5    0.07       0  4885.5    0.16       0
  5299.2    0.05       0  5398.2    0.16       0
Bank Sta=4881.5,4885.5
Exp/Cntr=0.3,0.1

Type RM Length L Ch R = 1,1802,0,0,0
BEGIN DESCRIPTION:
South Twin Creek Trib M1801.887
END DESCRIPTION:
XS GIS Cut Line= 3
      2716161.01      6803272.33      2716345.44      6803840.45
      2716925.22      6803809.51
#Sta/Elev= 30
  4402.7  351.28  4431.3  346.41  4436.6  347.35  4463.3  343.98  4468.5  344.47
  4495.2  341.12  4500.5  341.63  4530.6  339.47  4569.7  336.64  4611.6  335.96
  4697.5  332.73  4724.2  330.76  4729.5  331.14  4737.7  330.14  4788.2  328.59
  4800.8  327.48  4832.4  327.57  4842.9  325.59  4852.1  326.44  4855.4  322.85
  4855.6  322.35  4859.4  322.85  4863.9  324.87  4884.1  327.33  4945.7  326.61
  4990.5  325.44  5079.6  327.72  5190.8  329.19  5498.9  332.14  5580.6  332.44
#Mann=6,-1,0
  4402.7    0.12       0  4530.6    0.16       0  4855.4    0.05       0
  4859.4    0.16       0  4945.7    0.05       0  5498.9    0.16       0
Bank Sta=4855.4,4859.4
Exp/Cntr=0.3,0.1

Chan Stop Cuts=-1