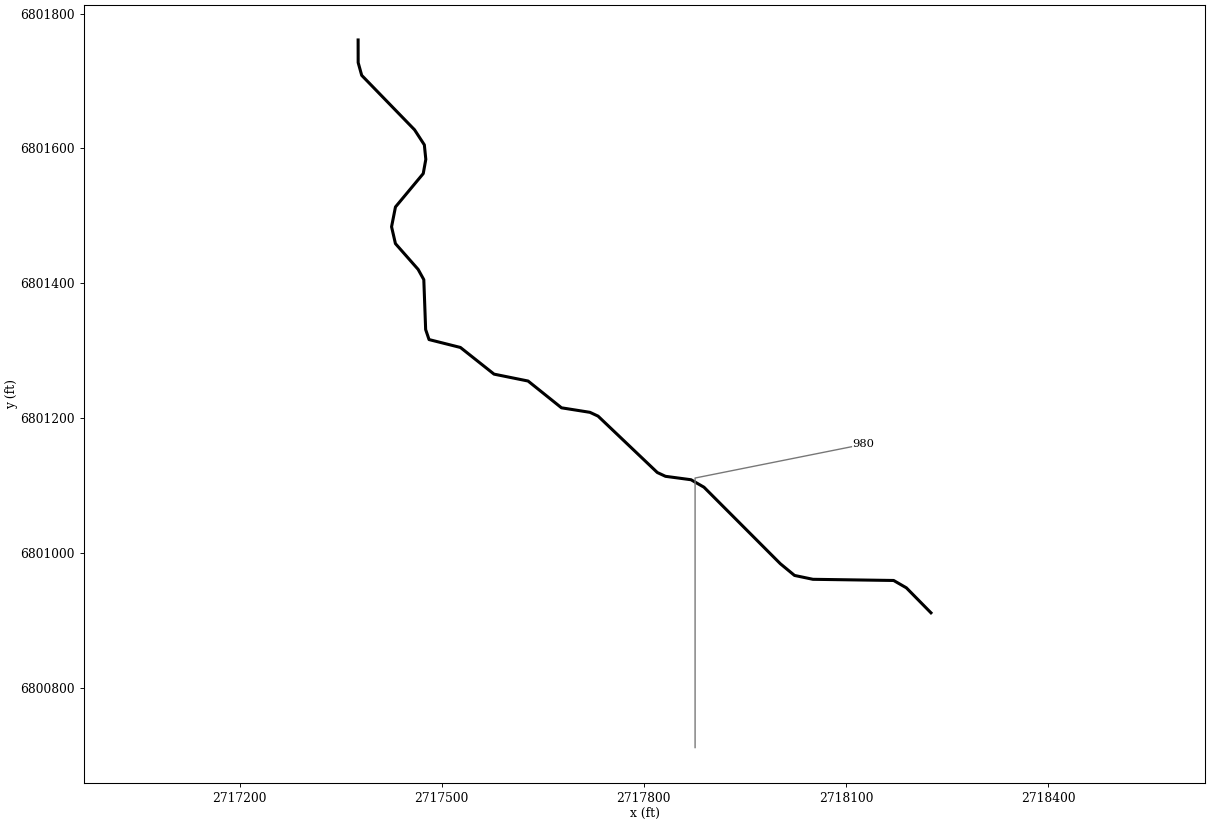
--- South Twin Creek Trib M1.prj (project) ---

Proj Title=South Twin Creek Trib M1 Base Level Engineering
Current Plan=p01
Default Exp/Contr=0.3,0.1
English Units
Geom File=g01
Flow File=f01
Plan File=p01
BEGIN DESCRIPTION:
South Twin Creek Trib M1
END DESCRIPTION:

--- South Twin Creek Trib M1.p01 (plan) ---

Plan Title=Multiple Run
Short Identifier=Multiple
Geom File=g01
Flow File=f01
Subcritical Flow
K Sum by GR= 0
Std Step Tol= 0.01
Critical Tol= 0.01
Num of Std Step Trials= 20
Max Error Tol= 0.3
Flow Tol Ratio= 0.001
Split Flow NTrial= 30
Split Flow Tol= 0.02
Split Flow Ratio= 0.02
Log Output Level= 0
Friction Slope Method= 1
Unsteady Friction Slope Method= 2
Unsteady Bridges Friction Slope Method= 1
Parabolic Critical Depth
Global Vel Dist=  1 , 1 , 1
Global Log Level= 0
CheckData=True
Encroach Param= -1, 0, 0, 0
BEGIN DESCRIPTION:
Multiple Run
END DESCRIPTION:

--- South Twin Creek Trib M1.f01 (steady flow) ---

Flow Title=Multiple
Number of Profiles=7
Profile Names=10-year,25-year,50-year,1pct_min,100-year,1pct_plu,500-year
River Rch & RM= South Twin Creek,Reach-1,980
      69      79      86      47      94     188     112
Boundary for River Rch & Prof#=South Twin Creek,Reach-1,1
Up Type=0
Dn Type=3
Dn Slope=0.005
Boundary for River Rch & Prof#=South Twin Creek,Reach-1,2
Up Type=0
Dn Type=3
Dn Slope=0.005
Boundary for River Rch & Prof#=South Twin Creek,Reach-1,3
Up Type=0
Dn Type=3
Dn Slope=0.005
Boundary for River Rch & Prof#=South Twin Creek,Reach-1,4
Up Type=0
Dn Type=3
Dn Slope=0.005
Boundary for River Rch & Prof#=South Twin Creek,Reach-1,5
Up Type=0
Dn Type=3
Dn Slope=0.005
Boundary for River Rch & Prof#=South Twin Creek,Reach-1,6
Up Type=0
Dn Type=3
Dn Slope=0.005
Boundary for River Rch & Prof#=South Twin Creek,Reach-1,7
Up Type=0
Dn Type=3
Dn Slope=0.005

--- South Twin Creek Trib M1.g01 (geometry) ---

Geom Title=Existing Conditions

River Reach=South Twin Creek,Reach-1
Reach XY= 30
      2718226.00      6800911.00      2718189.50      6800948.08
      2718170.62      6800958.99      2718050.88      6800960.72
      2718023.55      6800966.46      2718002.47      6800983.86
      2717889.21      6801097.37      2717869.95      6801108.47
      2717832.05      6801113.54      2717819.96      6801119.18
      2717732.05      6801202.84      2717719.96      6801208.49
      2717677.74      6801215.19      2717628.19      6801254.92
      2717577.69      6801265.15      2717527.80      6801304.73
      2717481.25      6801316.44      2717476.21      6801331.25
      2717473.47      6801405.35      2717465.03      6801420.61
      2717431.37      6801458.82      2717425.63      6801483.81
      2717431.42      6801513.20      2717472.63      6801562.73
      2717476.45      6801583.84      2717474.27      6801605.37
      2717459.78      6801627.67      2717381.33      6801708.49
      2717376.08      6801727.37      2717376.00      6801761.00

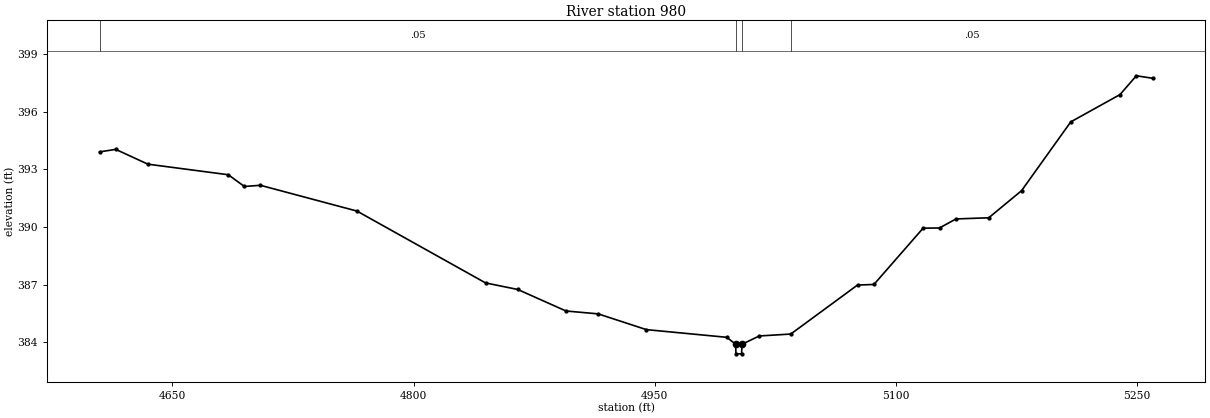
Type RM Length L Ch R = 1,980,0,0,0
BEGIN DESCRIPTION:
South Twin Creek Trib M1980.129
END DESCRIPTION:
XS GIS Cut Line= 3
      2717876.00      6800711.04      2717876.00      6801111.00
      2718125.99      6801161.00
#Sta/Elev= 30
  4604.8  393.91  4614.8  394.04  4634.8  393.27  4684.8  392.72  4694.8  392.11
  4704.8  392.17  4764.8  390.83  4844.8  387.09  4864.8  386.75  4894.8  385.63
  4914.8  385.48  4944.8  384.66  4994.8  384.26  5000.3  383.90  5000.5  383.40
  5004.0  383.40  5004.3  383.90  5015.0  384.33  5034.6  384.43  5076.1  386.98
  5086.3  387.01  5116.9  389.94  5127.1  389.95  5137.3  390.42  5157.7  390.48
  5178.1  391.89  5208.7  395.47  5239.3  396.89  5249.5  397.87  5259.7  397.74
#Mann=4,-1,0
  4604.8    0.05       0  5000.3    0.05       0  5004.3    0.05       0
  5034.6    0.05       0
Bank Sta=5000.3,5004.3
Exp/Cntr=0.3,0.1

Chan Stop Cuts=-1