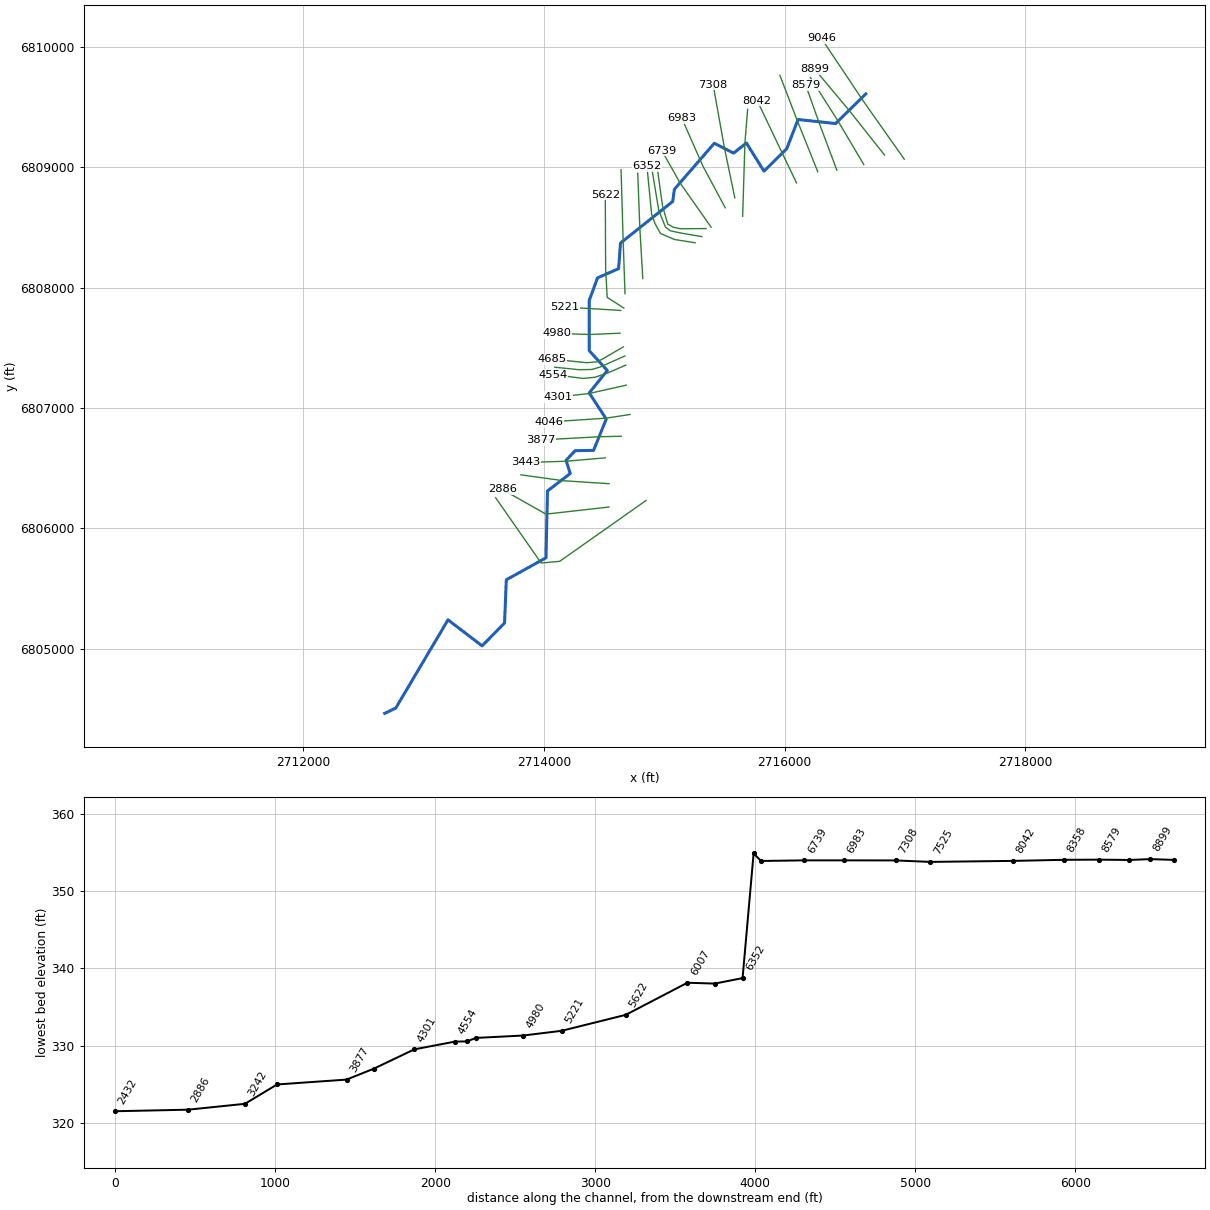
--- South Twin Creek Trib N.prj (project) ---

Proj Title=South Twin Creek Trib N Base Level Engineering
Current Plan=p01
Default Exp/Contr=0.3,0.1
English Units
Geom File=g01
Flow File=f01
Plan File=p01
BEGIN DESCRIPTION:
South Twin Creek Trib N
END DESCRIPTION:

--- South Twin Creek Trib N.p01 (plan) ---

Plan Title=Multiple Run
Short Identifier=Multiple
Geom File=g01
Flow File=f01
Subcritical Flow
K Sum by GR= 0
Std Step Tol= 0.01
Critical Tol= 0.01
Num of Std Step Trials= 20
Max Error Tol= 0.3
Flow Tol Ratio= 0.001
Split Flow NTrial= 30
Split Flow Tol= 0.02
Split Flow Ratio= 0.02
Log Output Level= 0
Friction Slope Method= 1
Unsteady Friction Slope Method= 2
Unsteady Bridges Friction Slope Method= 1
Parabolic Critical Depth
Global Vel Dist=  1 , 1 , 1
Global Log Level= 0
CheckData=True
Encroach Param= -1, 0, 0, 0
BEGIN DESCRIPTION:
Multiple Run
END DESCRIPTION:

--- South Twin Creek Trib N.f01 (steady flow) ---

Flow Title=Multiple
Number of Profiles=7
Profile Names=10-year,25-year,50-year,1pct_min,100-year,1pct_plu,500-year
River Rch & RM= South Twin Creek,Reach-1,9046
     291     365     421     240     480     957     623
River Rch & RM= South Twin Creek,Reach-1,6983
     502     657     779     458     914    1823    1257
Boundary for River Rch & Prof#=South Twin Creek,Reach-1,1
Up Type=0
Dn Type=3
Dn Slope=0.005
Boundary for River Rch & Prof#=South Twin Creek,Reach-1,2
Up Type=0
Dn Type=3
Dn Slope=0.005
Boundary for River Rch & Prof#=South Twin Creek,Reach-1,3
Up Type=0
Dn Type=3
Dn Slope=0.005
Boundary for River Rch & Prof#=South Twin Creek,Reach-1,4
Up Type=0
Dn Type=3
Dn Slope=0.005
Boundary for River Rch & Prof#=South Twin Creek,Reach-1,5
Up Type=0
Dn Type=3
Dn Slope=0.005
Boundary for River Rch & Prof#=South Twin Creek,Reach-1,6
Up Type=0
Dn Type=3
Dn Slope=0.005
Boundary for River Rch & Prof#=South Twin Creek,Reach-1,7
Up Type=0
Dn Type=3
Dn Slope=0.005

--- South Twin Creek Trib N.g01 (geometry) ---

Geom Title=Existing Conditions

River Reach=South Twin Creek,Reach-1
Reach XY= 30
      2716676.00      6809611.00      2716424.35      6809364.16
      2716112.31      6809397.51      2716018.14      6809154.83
      2715829.15      6808968.51      2715682.95      6809202.15
      2715576.09      6809118.31      2715415.92      6809199.93
      2715083.88      6808817.14      2715070.74      6808716.47
      2714636.47      6808370.82      2714620.54      6808158.00
      2714445.37      6808081.09      2714376.10      6807892.78
      2714376.50      6807475.91      2714526.89      6807310.97
      2714376.02      6807125.12      2714517.95      6806907.71
      2714412.53      6806647.29      2714259.23      6806644.70
      2714183.82      6806564.44      2714218.51      6806454.93
      2714029.45      6806309.75      2714016.88      6805754.24
      2713687.10      6805571.08      2713672.54      6805212.50
      2713486.05      6805022.08      2713202.62      6805238.64
      2712768.04      6804504.69      2712676.00      6804461.00

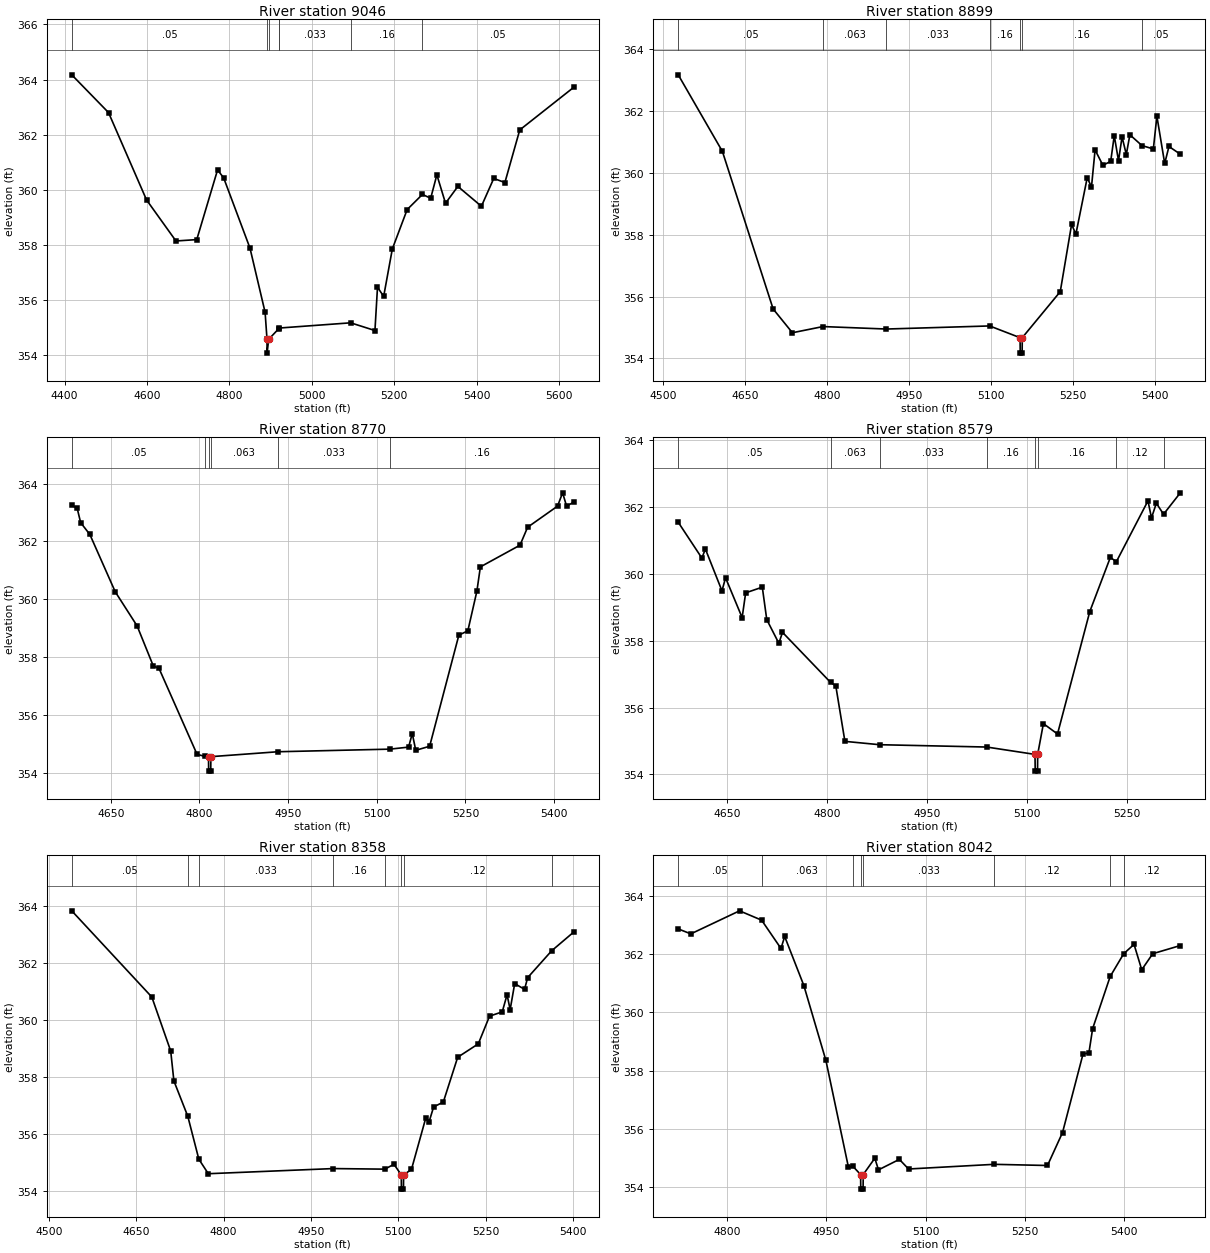
Type RM Length L Ch R = 1,9046,147,147,147
BEGIN DESCRIPTION:
South Twin Creek Trib N9046.205
END DESCRIPTION:
XS GIS Cut Line= 3
      2716995.36      6809067.37      2716659.64      6809543.76
      2716306.09      6810072.32
#Sta/Elev= 30
  4417.2  364.17  4506.4  362.80  4598.7  359.63  4670.1  358.14  4720.6  358.19
  4771.1  360.72  4785.9  360.43  4849.8  357.88  4886.5  355.55  4891.1  354.57
  4891.3  354.07  4895.1  354.57  4919.2  354.95  4920.4  354.98  5094.2  355.17
  5153.1  354.89  5159.3  356.46  5174.3  356.13  5195.3  357.85  5231.3  359.28
  5268.4  359.83  5288.4  359.69  5303.4  360.54  5324.4  359.51  5354.4  360.12
  5411.5  359.40  5441.5  360.41  5468.5  360.26  5504.6  362.17  5635.9  363.72
#Mann=7,-1,0
  4417.2    0.05       0  4891.1   0.033       0  4895.1    0.05       0
  4919.2   0.063       0  4920.4   0.033       0  5094.2    0.16       0
  5268.4    0.05       0
Bank Sta=4891.1,4895.1
Exp/Cntr=0.3,0.1

Type RM Length L Ch R = 1,8899,129,129,129
BEGIN DESCRIPTION:
South Twin Creek Trib N8899.48
END DESCRIPTION:
XS GIS Cut Line= 3
      2716831.16      6809102.48      2716533.54      6809477.49
      2716250.70      6809815.63
#Sta/Elev= 30
  4527.3  363.18  4608.2  360.70  4701.1  355.60  4736.4  354.83  4792.4  355.03
  4908.5  354.95  5097.7  355.05  5153.4  354.67  5153.7  354.17  5157.2  354.17
  5157.4  354.67  5227.0  356.16  5247.8  358.34  5255.6  358.02  5276.4  359.85
  5284.2  359.55  5290.8  360.75  5305.1  360.25  5319.4  360.38  5325.9  361.21
  5333.7  360.40  5340.2  361.17  5348.0  360.60  5354.5  361.24  5376.6  360.89
  5397.5  360.78  5404.0  361.84  5418.3  360.31  5426.1  360.86  5446.9  360.61
#Mann=7,-1,0
  4527.3    0.05       0  4792.4   0.063       0  4908.5   0.033       0
  5097.7    0.16       0  5153.4   0.033       0  5157.4    0.16       0
  5376.6    0.05       0
Bank Sta=5153.4,5157.4
Exp/Cntr=0.3,0.1

Type RM Length L Ch R = 1,8770,191,191,191
BEGIN DESCRIPTION:
South Twin Creek Trib N8770.45
END DESCRIPTION:
XS GIS Cut Line= 3
      2716658.71      6809023.20      2716442.99      6809387.09
      2716214.78      6809747.02
#Sta/Elev= 30
  4584.1  363.25  4593.2  363.15  4599.1  362.65  4614.7  362.24  4657.6  360.26
  4694.6  359.08  4721.9  357.70  4731.7  357.61  4796.0  354.64  4809.2  354.57
  4815.4  354.56  4815.6  354.06  4819.1  354.06  4819.4  354.56  4932.7  354.73
  5122.3  354.82  5153.8  354.89  5160.0  355.36  5165.9  354.78  5189.4  354.92
  5238.8  358.76  5254.0  358.91  5269.3  360.28  5275.2  361.12  5342.2  361.87
  5355.1  362.49  5405.7  363.22  5414.3  363.68  5421.0  363.22  5433.3  363.36
#Mann=6,-1,0
  4584.1    0.05       0  4809.2   0.063       0  4815.4   0.033       0
  4819.4   0.063       0  4932.7   0.033       0  5122.3    0.16       0
Bank Sta=4815.4,4819.4
Exp/Cntr=0.3,0.1

Type RM Length L Ch R = 1,8579,221,221,221
BEGIN DESCRIPTION:
South Twin Creek Trib N8579.07
END DESCRIPTION:
XS GIS Cut Line= 3
      2716434.81      6808976.47      2716284.38      6809378.23
      2716175.84      6809684.89
#Sta/Elev= 30
  4576.4  361.54  4611.9  360.47  4617.2  360.74  4642.1  359.49  4647.5  359.88
  4672.4  358.69  4677.7  359.43  4702.7  359.60  4709.4  358.63  4727.6  357.92
  4733.0  358.25  4805.4  356.75  4813.1  356.65  4826.8  354.99  4878.8  354.89
  5039.9  354.82  5112.4  354.60  5112.7  354.10  5116.2  354.10  5116.4  354.60
  5125.0  355.52  5146.2  355.21  5194.7  358.87  5225.6  360.49  5234.6  360.36
  5282.1  362.18  5287.4  361.67  5294.7  362.11  5305.5  361.78  5330.7  362.42
#Mann=8,-1,0
  4576.4    0.05       0  4805.4   0.063       0  4878.8   0.033       0
  5039.9    0.16       0  5112.4   0.033       0  5116.4    0.16       0
  5234.6    0.12       0  5305.5    0.05       0
Bank Sta=5112.4,5116.4
Exp/Cntr=0.3,0.1

Type RM Length L Ch R = 1,8358,316,316,316
BEGIN DESCRIPTION:
South Twin Creek Trib N8357.72
END DESCRIPTION:
XS GIS Cut Line= 3
      2716276.29      6808963.33      2716101.57      6809399.13
      2715960.99      6809765.89
#Sta/Elev= 30
  4539.2  363.83  4676.7  360.81  4709.1  358.92  4714.6  357.87  4738.5  356.63
  4757.4  355.13  4773.7  354.62  4988.3  354.80  5076.8  354.78  5092.6  354.95
  5105.1  354.58  5105.4  354.08  5108.9  354.08  5109.1  354.58  5122.6  354.77
  5147.3  356.58  5152.7  356.43  5160.7  356.96  5177.3  357.13  5202.0  358.70
  5237.4  359.17  5256.7  360.14  5278.5  360.29  5286.8  360.89  5292.1  360.37
  5299.9  361.28  5316.8  361.08  5322.2  361.49  5363.4  362.43  5401.5  363.09
#Mann=8,-1,0
  4539.2    0.05       0  4738.5   0.063       0  4757.4   0.033       0
  4988.3    0.16       0  5076.8    0.12       0  5105.1    0.07       0
  5109.1    0.12       0  5363.4    0.05       0
Bank Sta=5105.1,5109.1
Exp/Cntr=0.3,0.1

Type RM Length L Ch R = 1,8042,517,517,517
BEGIN DESCRIPTION:
South Twin Creek Trib N8041.97
END DESCRIPTION:
XS GIS Cut Line= 3
      2716099.78      6808870.06      2715979.29      6809121.83
      2715773.04      6809553.48
#Sta/Elev= 30
  4726.9  362.86  4745.9  362.69  4819.4  363.48  4852.7  363.16  4881.9  362.19
  4887.5  362.60  4916.4  360.92  4949.7  358.35  4983.7  354.69  4990.1  354.73
  5002.0  354.44  5002.3  353.94  5005.8  353.94  5006.0  354.44  5023.5  355.00
  5029.0  354.60  5060.5  354.96  5074.4  354.63  5203.5  354.79  5284.0  354.75
  5306.7  355.88  5337.6  358.57  5346.5  358.61  5352.1  359.44  5378.6  361.23
  5399.0  362.01  5414.6  362.33  5426.2  361.46  5442.8  362.01  5484.4  362.29
#Mann=8,-1,0
  4726.9    0.05       0  4852.7   0.063       0  4990.1   0.033       0
  5002.0   0.033       0  5006.0   0.033       0  5203.5    0.12       0
  5378.6    0.05       0  5399.0    0.12       0
Bank Sta=5002,5006
Exp/Cntr=0.3,0.1

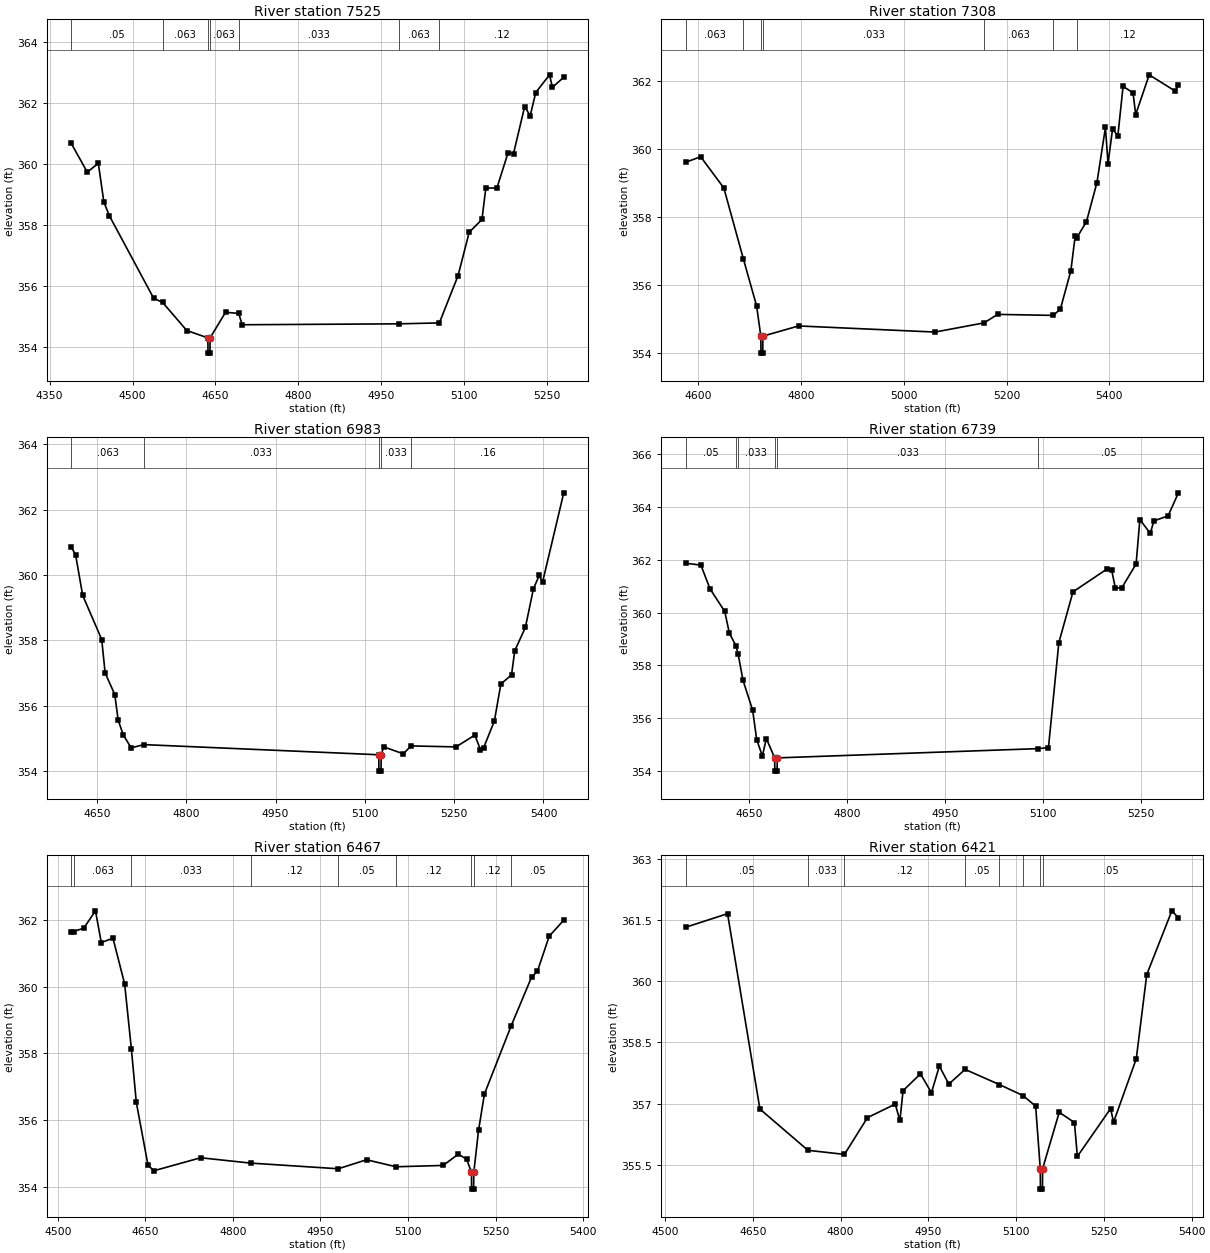
Type RM Length L Ch R = 1,7525,217,217,217
BEGIN DESCRIPTION:
South Twin Creek Trib N7525.03
END DESCRIPTION:
XS GIS Cut Line= 3
      2715651.81      6808592.15      2715670.77      6809205.64
      2715693.09      6809481.46
#Sta/Elev= 30
  4389.3  360.68  4418.2  359.74  4438.2  360.03  4448.2  358.76  4458.2  358.31
  4538.2  355.61  4554.5  355.47  4598.2  354.55  4636.3  354.31  4636.5  353.81
  4640.0  353.81  4640.3  354.31  4668.3  355.15  4692.1  355.11  4698.3  354.74
  4981.8  354.77  5054.9  354.80  5088.7  356.35  5108.8  357.77  5131.9  358.19
  5138.9  359.22  5158.9  359.22  5179.0  360.37  5189.0  360.35  5209.1  361.89
  5219.1  361.59  5229.2  362.35  5254.1  362.93  5259.3  362.52  5279.8  362.85
#Mann=7,-1,0
  4389.3    0.05       0  4554.5   0.063       0  4636.3   0.063       0
  4640.3   0.063       0  4692.1   0.033       0  4981.8   0.063       0
  5054.9    0.12       0
Bank Sta=4636.3,4640.3
Exp/Cntr=0.3,0.1

Type RM Length L Ch R = 1,7308,325,325,325
BEGIN DESCRIPTION:
South Twin Creek Trib N7307.7
END DESCRIPTION:
XS GIS Cut Line= 3
      2715586.51      6808746.47      2715499.65      6809165.33
      2715406.18      6809686.95
#Sta/Elev= 30
  4576.6  359.62  4605.2  359.78  4650.3  358.86  4688.5  356.76  4714.0  355.39
  4722.2  354.50  4722.5  354.00  4726.0  354.00  4726.2  354.50  4795.7  354.80
  5060.9  354.62  5156.3  354.89  5182.8  355.14  5291.3  355.11  5304.8  355.30
  5325.1  356.42  5333.5  357.44  5336.5  357.39  5355.5  357.87  5375.9  359.02
  5392.4  360.64  5397.4  359.58  5406.3  360.60  5416.5  360.39  5426.7  361.85
  5446.1  361.66  5451.2  361.02  5477.5  362.19  5528.3  361.71  5534.3  361.90
#Mann=7,-1,0
  4576.6   0.063       0  4688.5   0.033       0  4722.2   0.033       0
  4726.2   0.033       0  5156.3   0.063       0  5291.3    0.16       0
  5336.5    0.12       0
Bank Sta=4722.2,4726.2
Exp/Cntr=0.3,0.1

Type RM Length L Ch R = 1,6983,244,244,244
BEGIN DESCRIPTION:
South Twin Creek Trib N6982.89
END DESCRIPTION:
XS GIS Cut Line= 3
      2715506.79      6808664.13      2715320.08      6809013.13
      2715146.22      6809407.61
#Sta/Elev= 30
  4607.1  360.85  4614.3  360.62  4626.2  359.38  4658.2  358.03  4663.9  357.01
  4680.1  356.35  4685.8  355.57  4694.3  355.12  4707.7  354.72  4728.7  354.82
  5123.4  354.51  5123.7  354.01  5127.2  354.01  5127.4  354.51  5131.7  354.75
  5164.5  354.54  5177.8  354.78  5253.0  354.75  5284.7  355.11  5294.2  354.66
  5299.6  354.73  5317.5  355.54  5328.4  356.67  5346.3  356.95  5351.8  357.69
  5369.6  358.40  5383.1  359.58  5392.9  359.99  5398.4  359.78  5434.0  362.51
#Mann=5,-1,0
  4607.1   0.063       0  4728.7   0.033       0  5123.4   0.033       0
  5127.4   0.033       0  5177.8    0.16       0
Bank Sta=5123.4,5127.4
Exp/Cntr=0.3,0.1

Type RM Length L Ch R = 1,6739,272,272,272
BEGIN DESCRIPTION:
South Twin Creek Trib N6738.78
END DESCRIPTION:
XS GIS Cut Line= 3
      2715389.84      6808502.29      2715131.37      6808870.42
      2714981.43      6809136.58
#Sta/Elev= 30
  4552.6  361.86  4575.5  361.79  4589.6  360.89  4612.1  360.04  4619.2  359.22
  4629.1  358.75  4632.6  358.44  4640.1  357.44  4654.9  356.31  4661.1  355.20
  4669.8  354.58  4675.9  355.24  4688.7  354.51  4688.9  354.01  4692.4  354.01
  4692.7  354.51  5093.1  354.86  5108.6  354.90  5124.5  358.86  5146.2  360.78
  5198.2  361.64  5205.4  361.62  5211.2  360.92  5221.2  360.94  5243.0  361.83
  5248.8  363.51  5264.7  362.99  5270.4  363.46  5292.1  363.65  5307.9  364.52
#Mann=6,-1,0
  4552.6    0.05       0  4629.1   0.063       0  4632.6   0.033       0
  4688.7   0.033       0  4692.7   0.033       0  5093.1    0.05       0
Bank Sta=4688.7,4692.7
Exp/Cntr=0.3,0.1

Type RM Length L Ch R = 1,6467,46,46,46
BEGIN DESCRIPTION:
South Twin Creek Trib N6466.62
END DESCRIPTION:
XS GIS Cut Line= 6
      2715347.45      6808490.94      2715132.79      6808489.47
      2715075.15      6808501.99      2715028.95      6808528.64
      2714985.81      6808678.31      2714936.41      6809035.65
#Sta/Elev= 30
  4523.1  361.65  4527.0  361.65  4544.5  361.75  4564.5  362.27  4574.5  361.32
  4594.5  361.45  4614.5  360.08  4626.0  358.14  4634.5  356.53  4654.5  354.65
  4664.5  354.48  4744.7  354.87  4830.4  354.71  4980.4  354.54  5029.0  354.81
  5079.4  354.60  5160.2  354.64  5186.3  354.98  5200.6  354.82  5208.7  354.43
  5208.9  353.93  5212.4  353.93  5212.7  354.43  5220.8  355.69  5230.9  356.78
  5276.4  358.81  5311.6  360.28  5321.7  360.46  5341.9  361.51  5366.8  361.99
#Mann=9,-1,0
  4523.1    0.05       0  4527.0   0.063       0  4626.0   0.033       0
  4830.4    0.12       0  4980.4    0.05       0  5079.4    0.12       0
  5208.7    0.05       0  5212.7    0.12       0  5276.4    0.05       0
Bank Sta=5208.7,5212.7
Exp/Cntr=0.3,0.1

Type RM Length L Ch R = 1,6421,69,69,69
BEGIN DESCRIPTION:
South Twin Creek Trib N6421.22
END DESCRIPTION:
XS GIS Cut Line= 6
      2715312.24      6808424.32      2715132.11      6808454.81
      2715052.31      6808472.03      2715010.44      6808502.24
      2714954.27      6808642.95      2714892.84      6809012.09
#Sta/Elev= 30
  4535.7  361.32  4606.8  361.65  4662.1  356.87  4744.2  355.86  4806.6  355.76
  4846.0  356.66  4893.4  356.99  4901.4  356.59  4906.8  357.32  4936.5  357.73
  4955.3  357.27  4968.8  357.92  4985.0  357.48  5012.8  357.84  5071.2  357.47
  5111.8  357.20  5133.4  356.94  5141.3  355.41  5141.6  354.91  5145.1  354.91
  5145.3  355.41  5173.7  356.79  5199.7  356.54  5204.7  355.71  5261.5  356.88
  5266.6  356.55  5305.4  358.10  5323.3  360.16  5366.2  361.72  5377.4  361.55
#Mann=8,-1,0
  4535.7    0.05       0  4744.2   0.033       0  4806.6    0.12       0
  5012.8    0.05       0  5071.2    0.12       0  5111.8    0.05       0
  5141.3    0.07       0  5145.3    0.05       0
Bank Sta=5141.3,5145.3
Exp/Cntr=0.3,0.1

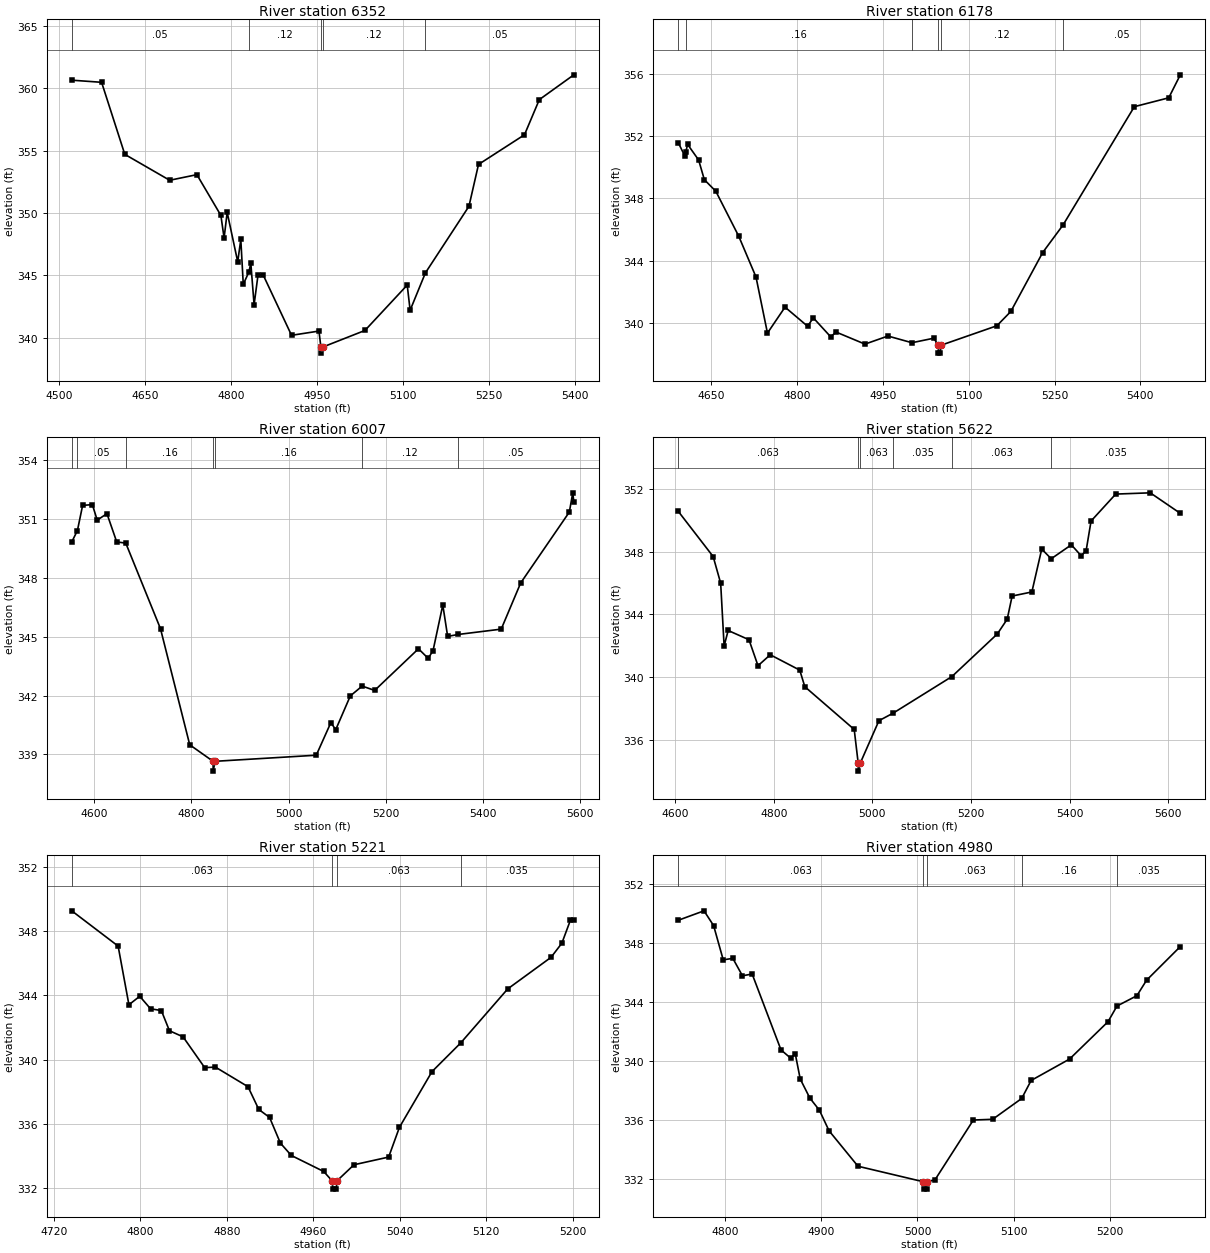
Type RM Length L Ch R = 1,6352,174,174,174
BEGIN DESCRIPTION:
South Twin Creek Trib N6352.09
END DESCRIPTION:
XS GIS Cut Line= 6
      2715257.50      6808372.85      2715086.32      6808400.08
      2714969.02      6808449.33      2714922.97      6808533.13
      2714894.65      6808613.87      2714856.24      6809006.95
#Sta/Elev= 30
  4521.7  360.65  4573.8  360.48  4614.3  354.70  4692.7  352.62  4740.2  353.07
  4782.1  349.80  4787.7  347.99  4793.1  350.04  4811.5  346.08  4816.9  347.87
  4821.2  344.27  4830.9  345.25  4834.4  345.96  4840.1  342.63  4847.0  345.04
  4856.2  345.00  4905.5  340.18  4953.4  340.52  4956.7  339.25  4956.9  338.75
  4960.7  339.25  5033.7  340.57  5107.5  344.21  5112.6  342.19  5139.3  345.19
  5215.3  350.53  5232.0  353.89  5312.3  356.27  5338.2  359.09  5398.5  361.08
#Mann=5,-1,0
  4521.7    0.05       0  4830.9    0.12       0  4956.7    0.07       0
  4960.7    0.12       0  5139.3    0.05       0
Bank Sta=4956.7,4960.7
Exp/Cntr=0.3,0.1

Type RM Length L Ch R = 1,6178,171,171,171
BEGIN DESCRIPTION:
South Twin Creek Trib N6177.84
END DESCRIPTION:
XS GIS Cut Line= 3
      2714821.72      6808075.47      2714797.62      6808484.07
      2714779.52      6808951.21
#Sta/Elev= 30
  4592.9  351.59  4604.3  350.73  4606.2  351.01  4609.3  351.47  4628.5  350.47
  4638.5  349.20  4658.5  348.46  4698.6  345.56  4728.7  342.94  4748.7  339.33
  4779.4  341.00  4818.8  339.77  4828.8  340.31  4858.9  339.10  4868.9  339.39
  4919.0  338.62  4959.1  339.14  5001.0  338.71  5039.2  339.00  5047.2  338.54
  5047.4  338.04  5050.9  338.04  5051.2  338.54  5149.3  339.80  5173.7  340.72
  5229.3  344.51  5264.8  346.28  5389.4  353.90  5449.5  354.47  5469.7  355.95
#Mann=6,-1,0
  4592.9    0.05       0  4606.2    0.16       0  5001.0    0.12       0
  5047.2    0.07       0  5051.2    0.12       0  5264.8    0.05       0
Bank Sta=5047.2,5051.2
Exp/Cntr=0.3,0.1

Type RM Length L Ch R = 1,6007,385,385,385
BEGIN DESCRIPTION:
South Twin Creek Trib N6007.11
END DESCRIPTION:
XS GIS Cut Line= 3
      2714673.91      6807948.70      2714658.00      6808400.76
      2714640.99      6808980.27
#Sta/Elev= 30
  4554.4  349.82  4566.0  350.40  4576.7  351.68  4596.7  351.72  4606.7  350.93
  4626.7  351.26  4646.8  349.82  4665.4  349.76  4736.8  345.40  4796.9  339.49
  4844.9  338.65  4845.1  338.15  4848.9  338.65  5057.0  338.96  5087.0  340.62
  5097.0  340.26  5127.0  341.98  5151.3  342.48  5177.1  342.26  5267.1  344.38
  5287.1  343.89  5297.1  344.29  5317.1  346.61  5327.1  345.01  5349.2  345.11
  5437.2  345.38  5477.2  347.73  5577.2  351.34  5584.3  352.32  5586.5  351.84
#Mann=7,-1,0
  4554.4   0.063       0  4566.0    0.05       0  4665.4    0.16       0
  4844.9    0.07       0  4848.9    0.16       0  5151.3    0.12       0
  5349.2    0.05       0
Bank Sta=4844.9,4848.9
Exp/Cntr=0.3,0.1

Type RM Length L Ch R = 1,5622,401,401,401
BEGIN DESCRIPTION:
South Twin Creek Trib N5621.93
END DESCRIPTION:
XS GIS Cut Line= 4
      2714664.08      6807829.87      2714525.69      6807919.32
      2714512.97      6808152.82      2714509.77      6808771.89
#Sta/Elev= 30
  4606.4  350.58  4677.2  347.69  4692.4  345.99  4699.4  341.98  4707.6  342.97
  4749.8  342.38  4768.1  340.72  4792.9  341.42  4852.7  340.44  4863.0  339.38
  4963.1  336.65  4971.2  334.49  4971.4  333.99  4975.2  334.49  5013.2  337.21
  5042.4  337.70  5161.2  340.03  5253.2  342.75  5273.2  343.69  5283.2  345.17
  5323.2  345.43  5343.2  348.17  5362.4  347.55  5403.2  348.44  5423.2  347.74
  5433.2  348.07  5443.2  349.96  5493.2  351.68  5563.2  351.76  5624.1  350.45
#Mann=6,-1,0
  4606.4   0.063       0  4971.2   0.063       0  4975.2   0.063       0
  5042.4   0.035       0  5161.2   0.063       0  5362.4   0.035       0
Bank Sta=4971.2,4975.2
Exp/Cntr=0.3,0.1

Type RM Length L Ch R = 1,5221,241,241,241
BEGIN DESCRIPTION:
South Twin Creek Trib N5221.37
END DESCRIPTION:
XS GIS Cut Line= 3
      2714638.77      6807810.22      2714375.13      6807826.67
      2714174.88      6807837.66
#Sta/Elev= 30
  4736.5  349.28  4779.4  347.08  4789.4  343.42  4799.4  343.95  4809.4  343.17
  4819.4  343.06  4826.9  341.80  4839.5  341.42  4859.5  339.50  4869.5  339.53
  4899.6  338.31  4909.6  336.89  4919.6  336.39  4929.6  334.79  4939.7  334.02
  4969.7  333.02  4977.7  332.42  4978.0  331.92  4981.5  331.92  4981.7  332.42
  4997.7  333.44  5029.8  333.92  5039.8  335.78  5069.9  339.25  5096.5  341.04
  5140.0  344.41  5180.1  346.38  5190.1  347.26  5198.1  348.71  5201.2  348.71
#Mann=4,-1,0
  4736.5   0.063       0  4977.7   0.063       0  4981.7   0.063       0
  5096.5   0.035       0
Bank Sta=4977.7,4981.7
Exp/Cntr=0.3,0.1

Type RM Length L Ch R = 1,4980,295,295,295
BEGIN DESCRIPTION:
South Twin Creek Trib N4979.55
END DESCRIPTION:
XS GIS Cut Line= 3
      2714632.78      6807621.32      2714383.05      6807610.39
      2714110.88      6807619.71
#Sta/Elev= 30
  4751.1  349.52  4777.9  350.16  4787.9  349.16  4797.9  346.84  4807.9  346.94
  4817.9  345.76  4828.0  345.88  4858.0  340.74  4867.9  340.19  4872.9  340.46
  4878.0  338.77  4888.0  337.48  4898.0  336.65  4908.0  335.26  4938.1  332.86
  5006.1  331.81  5006.4  331.31  5009.9  331.31  5010.1  331.81  5018.1  331.93
  5058.1  335.99  5078.2  336.04  5108.4  337.45  5118.2  338.67  5158.2  340.12
  5198.2  342.65  5207.5  343.71  5228.2  344.41  5238.3  345.46  5273.4  347.74
#Mann=5,-1,0
  4751.1   0.063       0  5006.1   0.063       0  5010.1   0.063       0
  5108.4    0.16       0  5207.5   0.035       0
Bank Sta=5006.1,5010.1
Exp/Cntr=0.3,0.1

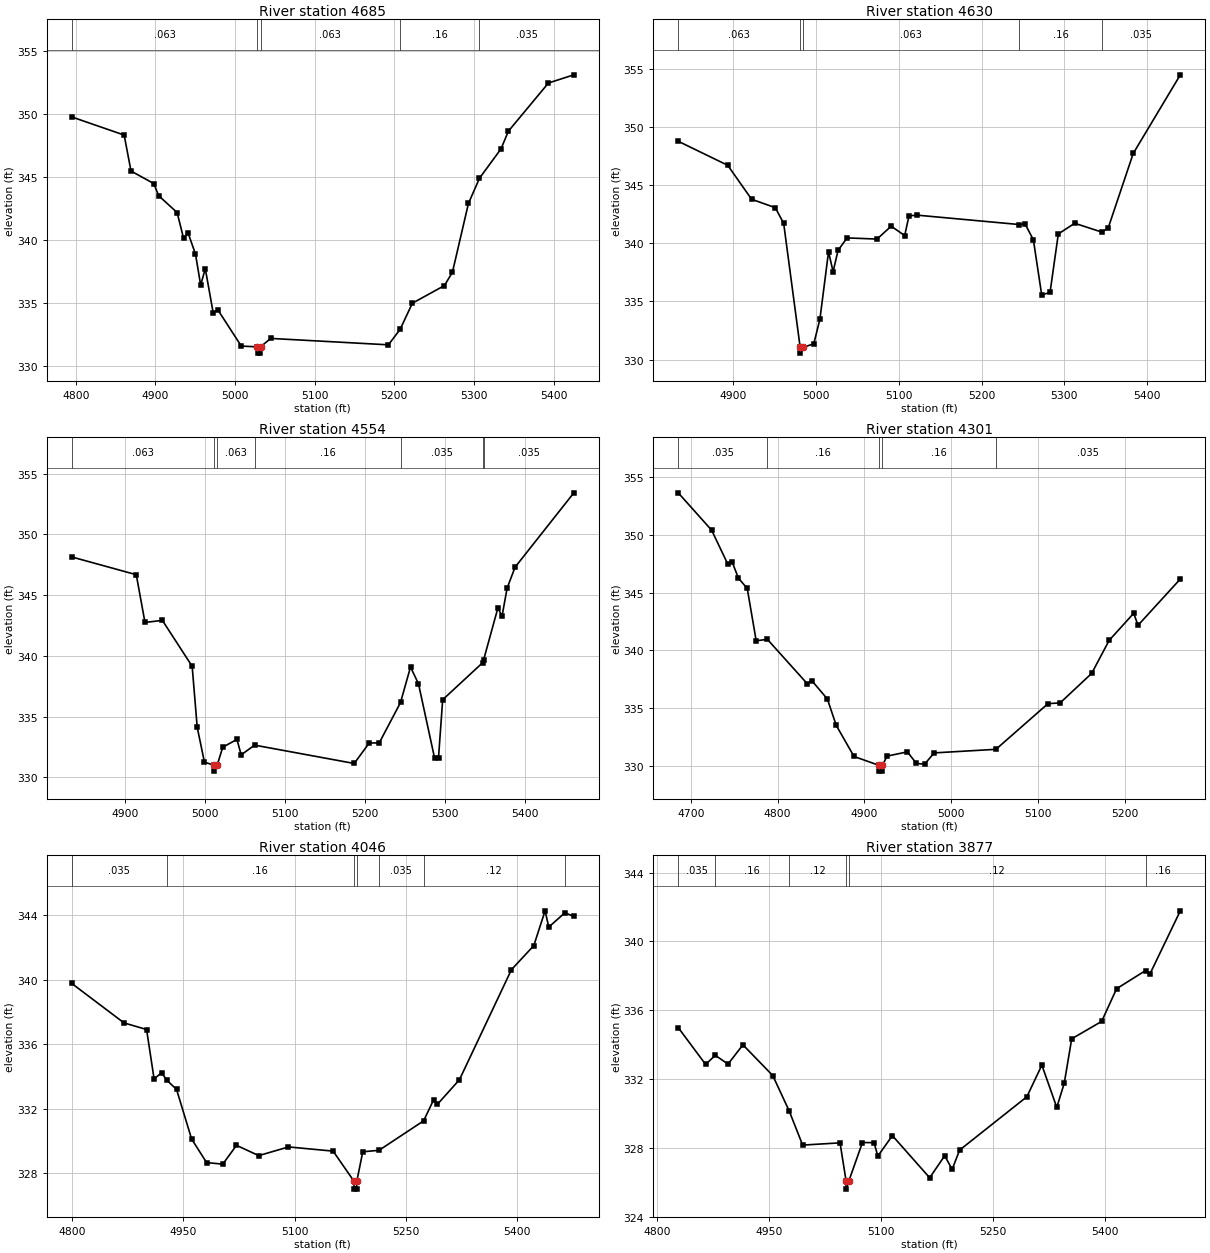
Type RM Length L Ch R = 1,4685,55,55,55
BEGIN DESCRIPTION:
South Twin Creek Trib N4684.98
END DESCRIPTION:
XS GIS Cut Line= 5
      2714660.37      6807507.65      2714483.36      6807404.88
      2714438.27      6807383.06      2714357.55      6807376.01
      2714064.24      6807405.64
#Sta/Elev= 30
  4794.9  349.78  4860.7  348.34  4869.3  345.48  4898.0  344.48  4904.0  343.52
  4927.2  342.18  4935.3  340.14  4941.0  340.55  4950.3  338.87  4956.8  336.41
  4962.6  337.72  4972.5  334.21  4978.3  334.45  5007.8  331.56  5028.0  331.50
  5028.2  331.00  5031.7  331.00  5032.0  331.50  5044.8  332.17  5192.6  331.66
  5207.3  332.89  5222.7  334.97  5262.9  336.37  5273.0  337.43  5293.1  342.90
  5307.0  344.91  5334.0  347.24  5343.3  348.65  5393.6  352.48  5425.5  353.13
#Mann=5,-1,0
  4794.9   0.063       0  5028.0   0.063       0  5032.0   0.063       0
  5207.3    0.16       0  5307.0   0.035       0
Bank Sta=5028,5032
Exp/Cntr=0.3,0.1

Type RM Length L Ch R = 1,4630,76,76,76
BEGIN DESCRIPTION:
South Twin Creek Trib N4629.78
END DESCRIPTION:
XS GIS Cut Line= 5
      2714672.44      6807431.74      2714462.82      6807338.60
      2714398.55      6807319.81      2714295.67      6807317.44
      2714089.39      6807338.48
#Sta/Elev= 30
  4833.4  348.79  4893.2  346.72  4922.0  343.80  4950.7  343.07  4960.8  341.72
  4980.7  331.05  4981.0  330.55  4984.7  331.05  4997.2  331.36  5004.6  333.49
  5015.0  339.28  5020.5  337.56  5026.5  339.40  5037.4  340.47  5073.6  340.37
  5090.7  341.48  5107.0  340.67  5112.2  342.37  5122.0  342.43  5245.5  341.62
  5252.4  341.68  5262.5  340.30  5272.5  335.57  5282.6  335.77  5292.6  340.81
  5312.4  341.73  5345.2  340.97  5352.9  341.33  5383.1  347.74  5440.0  354.51
#Mann=5,-1,0
  4833.4   0.063       0  4980.7   0.063       0  4984.7   0.063       0
  5245.5    0.16       0  5345.2   0.035       0
Bank Sta=4980.7,4984.7
Exp/Cntr=0.3,0.1

Type RM Length L Ch R = 1,4554,253,253,253
BEGIN DESCRIPTION:
South Twin Creek Trib N4553.75
END DESCRIPTION:
XS GIS Cut Line= 5
      2714680.08      6807355.72      2714524.28      6807288.06
      2714420.64      6807254.51      2714323.79      6807245.35
      2714073.04      6807277.69
#Sta/Elev= 30
  4832.7  348.15  4913.5  346.69  4924.4  342.76  4946.2  342.93  4983.5  339.15
  4989.8  334.14  4998.9  331.25  5010.9  331.02  5011.1  330.52  5014.9  331.02
  5021.8  332.49  5039.6  333.13  5044.9  331.86  5061.7  332.66  5186.5  331.15
  5205.3  332.84  5217.8  332.84  5244.5  336.17  5257.0  339.09  5267.0  337.71
  5287.1  331.61  5292.1  331.64  5297.3  336.40  5347.6  339.46  5348.5  339.66
  5366.5  343.96  5371.6  343.26  5378.0  345.58  5388.0  347.31  5461.6  353.43
#Mann=7,-1,0
  4832.7   0.063       0  5010.9   0.063       0  5014.9   0.063       0
  5061.7    0.16       0  5244.5   0.035       0  5347.6    0.16       0
  5348.5   0.035       0
Bank Sta=5010.9,5014.9
Exp/Cntr=0.3,0.1

Type RM Length L Ch R = 1,4301,255,255,255
BEGIN DESCRIPTION:
South Twin Creek Trib N4301.48
END DESCRIPTION:
XS GIS Cut Line= 3
      2714683.60      6807189.12      2714374.17      6807119.66
      2714114.55      6807090.31
#Sta/Elev= 30
  4685.6  353.64  4724.1  350.40  4742.5  347.49  4747.6  347.67  4754.9  346.25
  4765.1  345.35  4775.4  340.82  4788.3  340.94  4834.3  337.09  4839.4  337.37
  4857.4  335.77  4867.6  333.49  4888.1  330.79  4916.9  330.02  4917.1  329.52
  4920.6  329.52  4920.9  330.02  4926.1  330.82  4949.6  331.19  4959.9  330.19
  4969.4  330.12  4980.4  331.10  5051.6  331.41  5111.6  335.37  5125.5  335.43
  5161.9  337.99  5182.0  340.85  5210.3  343.20  5215.3  342.16  5264.0  346.17
#Mann=5,-1,0
  4685.6   0.035       0  4788.3    0.16       0  4916.9    0.07       0
  4920.9    0.16       0  5051.6   0.035       0
Bank Sta=4916.9,4920.9
Exp/Cntr=0.3,0.1

Type RM Length L Ch R = 1,4046,169,169,169
BEGIN DESCRIPTION:
South Twin Creek Trib N4045.59
END DESCRIPTION:
XS GIS Cut Line= 3
      2714715.68      6806945.68      2714517.84      6806915.15
      2714042.08      6806883.43
#Sta/Elev= 30
  4799.6  339.77  4870.1  337.32  4900.5  336.91  4910.6  333.84  4920.7  334.23
  4927.6  333.77  4940.9  333.19  4961.2  330.11  4981.4  328.65  5003.2  328.55
  5021.7  329.72  5051.7  329.08  5091.8  329.62  5152.0  329.36  5180.0  327.50
  5180.3  327.00  5183.8  327.00  5184.0  327.50  5192.0  329.32  5213.9  329.41
  5274.0  331.24  5287.5  332.54  5292.5  332.26  5322.3  333.79  5392.5  340.63
  5422.6  342.12  5437.8  344.28  5442.8  343.27  5464.5  344.16  5476.6  343.93
#Mann=7,-1,0
  4799.6   0.035       0  4927.6    0.16       0  5180.0    0.07       0
  5184.0    0.16       0  5213.9   0.035       0  5274.0    0.12       0
  5464.5    0.16       0
Bank Sta=5180,5184
Exp/Cntr=0.3,0.1

Type RM Length L Ch R = 1,3877,434,434,434
BEGIN DESCRIPTION:
South Twin Creek Trib N3876.55
END DESCRIPTION:
XS GIS Cut Line= 3
      2714642.65      6806764.76      2714466.24      6806760.70
      2713970.73      6806733.73
#Sta/Elev= 30
  4828.6  334.99  4865.3  332.85  4878.2  333.38  4895.3  332.87  4915.3  333.99
  4955.3  332.20  4977.2  330.15  4995.3  328.16  5045.4  328.29  5053.4  326.10
  5053.6  325.60  5057.4  326.10  5075.4  328.31  5091.0  328.30  5096.0  327.52
  5115.5  328.71  5165.5  326.26  5185.6  327.54  5195.6  326.75  5205.6  327.87
  5295.7  330.97  5315.8  332.81  5335.8  330.35  5345.8  331.76  5355.8  334.34
  5395.9  335.35  5415.9  337.25  5454.8  338.31  5460.3  338.08  5501.3  341.78
#Mann=6,-1,0
  4828.6   0.035       0  4878.2    0.16       0  4977.2    0.12       0
  5053.4    0.07       0  5057.4    0.12       0  5454.8    0.16       0
Bank Sta=5053.4,5057.4
Exp/Cntr=0.3,0.1

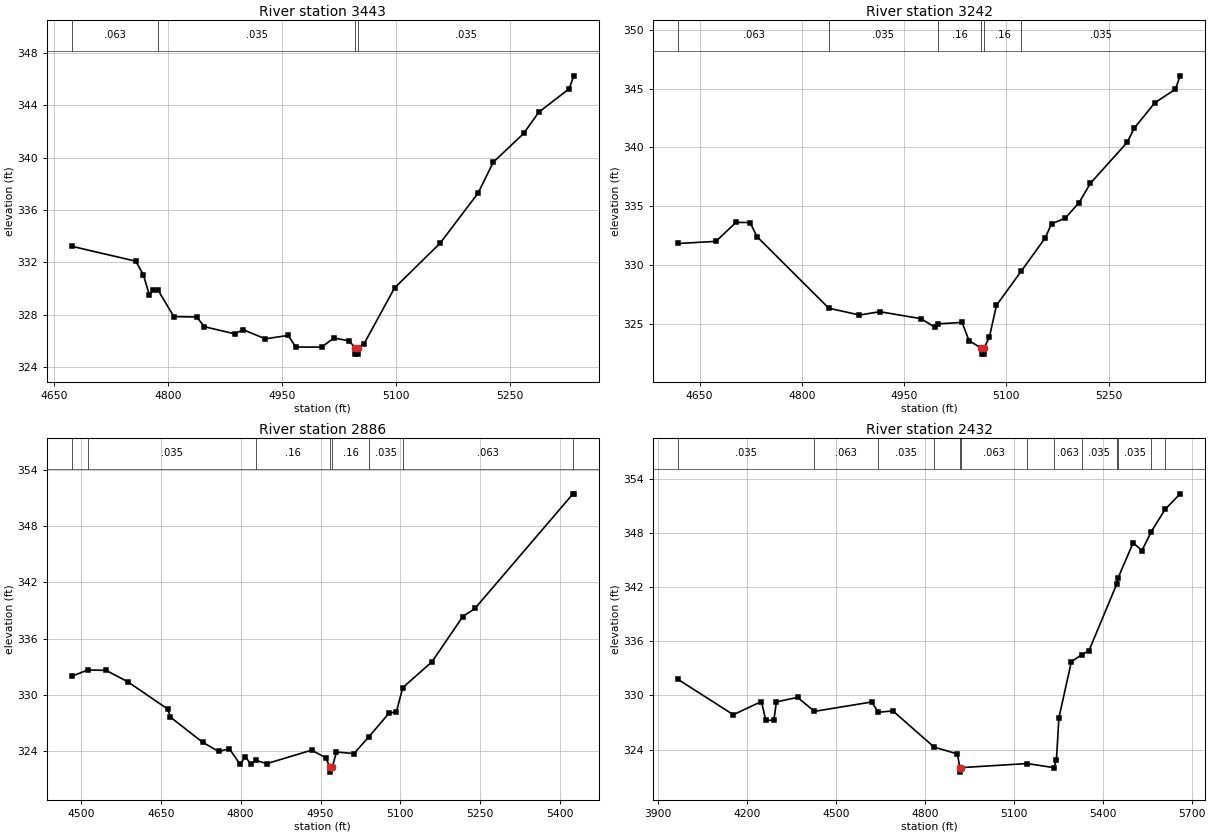
Type RM Length L Ch R = 1,3443,201,201,201
BEGIN DESCRIPTION:
South Twin Creek Trib N3442.9
END DESCRIPTION:
XS GIS Cut Line= 3
      2714509.96      6806585.07      2714181.97      6806556.75
      2713850.04      6806546.53
#Sta/Elev= 30
  4673.1  333.22  4757.4  332.08  4767.4  331.04  4775.5  329.46  4780.5  329.91
  4787.0  329.84  4807.6  327.84  4837.7  327.81  4847.7  327.07  4887.9  326.52
  4898.8  326.84  4928.0  326.14  4958.1  326.40  4968.2  325.51  5002.3  325.51
  5018.3  326.20  5038.3  325.99  5046.3  325.47  5046.6  324.97  5050.1  324.97
  5050.3  325.47  5058.3  325.78  5098.3  330.03  5158.4  333.46  5208.4  337.29
  5228.4  339.65  5268.4  341.85  5288.4  343.48  5328.4  345.27  5334.4  346.26
#Mann=4,-1,0
  4673.1   0.063       0  4787.0   0.035       0  5046.3   0.035       0
  5050.3   0.035       0
Bank Sta=5046.3,5050.3
Exp/Cntr=0.3,0.1

Type RM Length L Ch R = 1,3242,356,356,356
BEGIN DESCRIPTION:
South Twin Creek Trib N3241.83
END DESCRIPTION:
XS GIS Cut Line= 3
      2714541.42      6806370.18      2714159.21      6806395.17
      2713809.22      6806443.97
#Sta/Elev= 30
  4618.5  331.85  4674.0  332.03  4703.4  333.64  4724.1  333.63  4734.2  332.43
  4839.5  326.36  4884.5  325.78  4914.5  326.06  4974.7  325.47  4994.7  324.76
  4999.3  325.03  5035.1  325.15  5045.2  323.61  5063.3  322.96  5063.6  322.46
  5067.1  322.46  5067.3  322.96  5075.2  323.92  5085.5  326.60  5121.7  329.49
  5156.8  332.30  5166.3  333.52  5186.5  334.00  5206.7  335.32  5223.3  336.96
  5277.4  340.44  5287.5  341.63  5317.8  343.79  5348.1  344.95  5354.9  346.08
#Mann=6,-1,0
  4618.5   0.063       0  4839.5   0.035       0  4999.3    0.16       0
  5063.3    0.07       0  5067.3    0.16       0  5121.7   0.035       0
Bank Sta=5063.3,5067.3
Exp/Cntr=0.3,0.1

Type RM Length L Ch R = 1,2886,454,454,454
BEGIN DESCRIPTION:
Mapping XS c42ba6fc
END DESCRIPTION:
XS GIS Cut Line= 3
      2714540.14      6806176.10      2714016.48      6806117.31
      2713654.39      6806322.01
#Sta/Elev= 30
  4482.7  331.97  4513.3  332.64  4547.2  332.59  4587.5  331.39  4662.9  328.45
  4668.0  327.59  4728.4  324.90  4758.6  323.91  4778.7  324.21  4798.8  322.54
  4808.9  323.34  4818.9  322.56  4829.0  322.95  4849.1  322.61  4933.2  324.05
  4959.8  323.24  4967.9  322.20  4968.1  321.70  4971.9  322.20  4979.9  323.85
  5012.8  323.69  5040.7  325.48  5079.1  328.04  5092.3  328.12  5104.5  330.75
  5159.5  333.52  5217.0  338.34  5240.0  339.22  5424.2  351.49  5425.6  351.49
#Mann=8,-1,0
  4482.7   0.063       0  4513.3   0.035       0  4829.0    0.16       0
  4967.9    0.07       0  4971.9    0.16       0  5040.7   0.035       0
  5104.5   0.063       0  5424.2   0.035       0
Bank Sta=4967.9,4971.9
Exp/Cntr=0.3,0.1

Type RM Length L Ch R = 1,2432,0,0,0
BEGIN DESCRIPTION:
South Twin Creek Trib N2988.69
END DESCRIPTION:
XS GIS Cut Line= 4
      2714847.71      6806229.92      2714131.37      6805725.10
      2713976.58      6805710.75      2713598.65      6806253.17
#Sta/Elev= 30
  3968.2  331.78  4154.3  327.87  4249.2  329.33  4263.9  327.25  4291.0  327.25
  4299.7  329.29  4371.1  329.79  4427.8  328.24  4621.1  329.28  4643.3  328.14
  4692.5  328.29  4831.8  324.27  4910.2  323.52  4918.2  322.00  4918.5  321.50
  4922.2  322.00  5145.3  322.45  5235.3  322.00  5244.1  322.86  5252.4  327.53
  5294.3  333.73  5328.8  334.52  5353.6  334.96  5447.4  342.36  5451.2  342.98
  5502.8  346.94  5532.5  346.07  5563.6  348.16  5610.5  350.64  5661.1  352.37
#Mann=13,-1,0
  3968.2   0.035       0  4427.8   0.063       0  4643.3   0.035       0
  4831.8   0.063       0  4918.2   0.063       0  4922.2   0.063       0
  5145.3    0.16       0  5235.3   0.063       0  5328.8   0.035       0
  5447.4   0.063       0  5451.2   0.035       0  5563.6   0.063       0
  5610.5   0.035       0
Bank Sta=4918.2,4922.2
Exp/Cntr=0.3,0.1

Chan Stop Cuts=-1