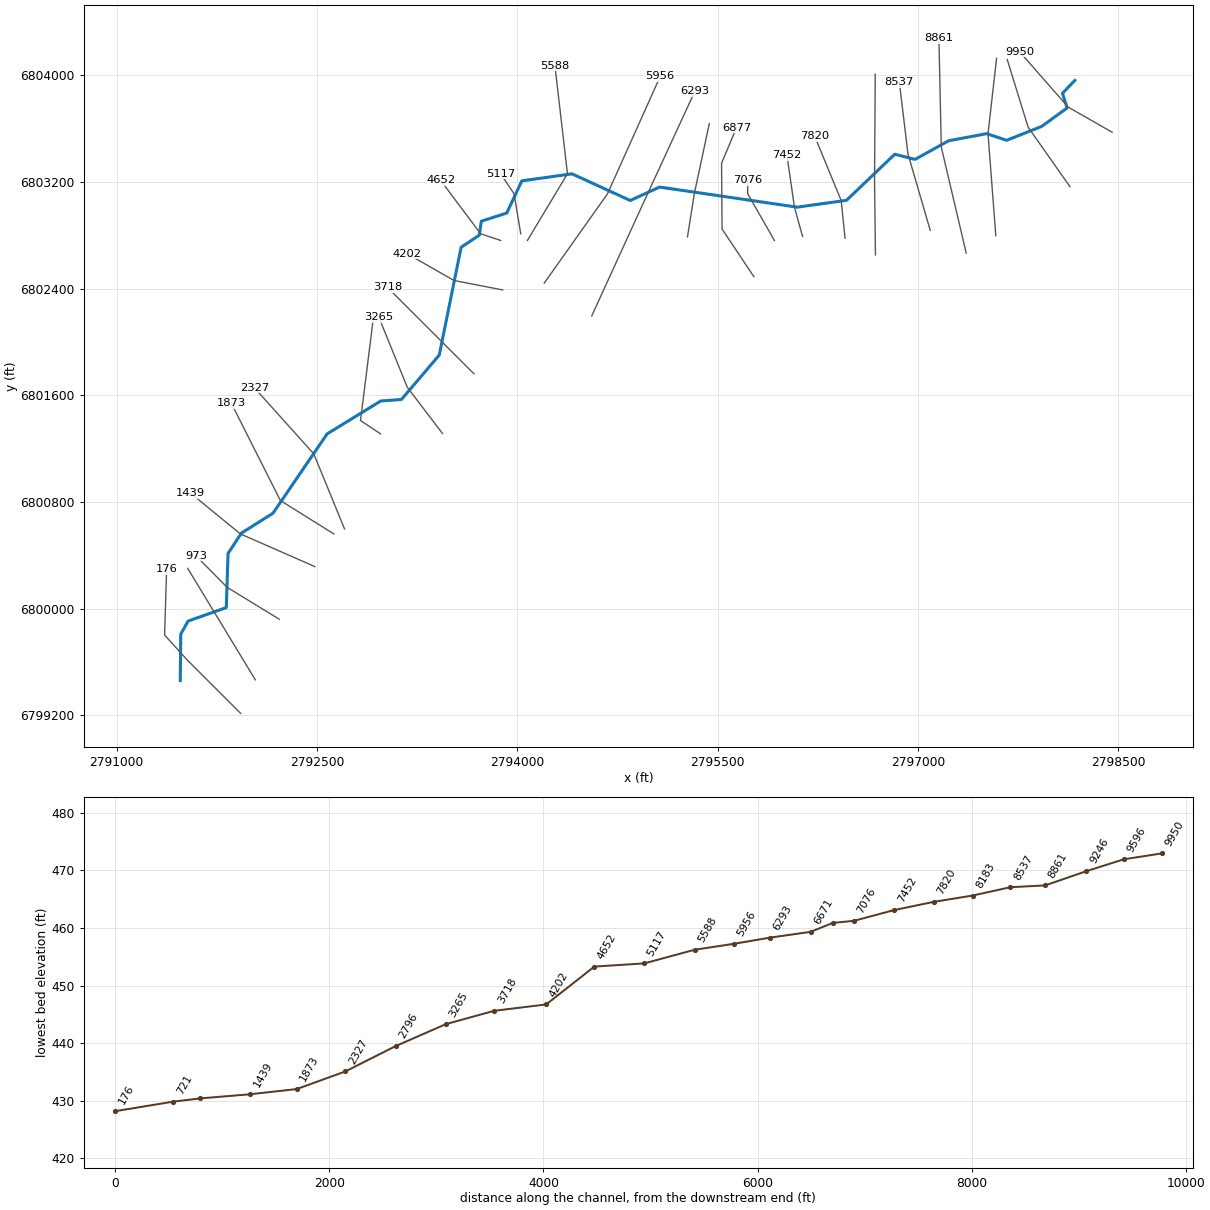
--- Third Caney Creek.prj (project) ---

Proj Title=Third Caney Creek Base Level Engineering
Current Plan=p01
Default Exp/Contr=0.3,0.1
English Units
Geom File=g01
Flow File=f01
Plan File=p01
Y Axis Title=Elevation
X Axis Title(PF)=Main Channel Distance
X Axis Title(XS)=Station
BEGIN DESCRIPTION:
Third Caney Creek
END DESCRIPTION:
DSS Export Rating Curves= 0
DSS Export Rating Curve Sorted= 0
DSS Export Volume Flow Curves= 0
DXF OffsetX= 0
DXF OffsetY= 0
DXF ScaleX= 1
DXF ScaleY= 10

--- Third Caney Creek.p01 (plan) ---

Plan Title=Multiple Run
Short Identifier=Multiple
Geom File=g01
Flow File=f01
Subcritical Flow
K Sum by GR= 0
Std Step Tol= 0.01
Critical Tol= 0.01
Num of Std Step Trials= 20
Max Error Tol= 0.3
Flow Tol Ratio= 0.001
Split Flow NTrial= 30
Split Flow Tol= 0.02
Split Flow Ratio= 0.02
Log Output Level= 0
Friction Slope Method= 1
Unsteady Friction Slope Method= 2
Unsteady Bridges Friction Slope Method= 1
Parabolic Critical Depth
Global Vel Dist=  1 , 1 , 1
Global Log Level= 0
CheckData=True
Encroach Param= -1, 0, 0, 0
BEGIN DESCRIPTION:
Multiple Run
END DESCRIPTION:

--- Third Caney Creek.f01 (steady flow) ---

Flow Title=Multiple
Program Version=4.10
Number of Profiles= 7
Profile Names=10-year,25-year,50-year,1pct_min,100-year,1pct_plu,500-year
River Rch & RM=Third Caney Cree,Reach-1         ,9950
     625     849    1033     625    1248    2490    1824
River Rch & RM=Third Caney Cree,Reach-1         ,6293
     731    1000    1222     743    1482    2956    2182
River Rch & RM=Third Caney Cree,Reach-1         ,2327
    1424    2019    2528    1570    3132    6249    4822
Boundary for River Rch & Prof#=Third Caney Cree,Reach-1         , 1
Up Type= 0
Dn Type= 3
Dn Slope=0.005
Boundary for River Rch & Prof#=Third Caney Cree,Reach-1         , 2
Up Type= 0
Dn Type= 3
Dn Slope=0.005
Boundary for River Rch & Prof#=Third Caney Cree,Reach-1         , 3
Up Type= 0
Dn Type= 3
Dn Slope=0.005
Boundary for River Rch & Prof#=Third Caney Cree,Reach-1         , 4
Up Type= 0
Dn Type= 3
Dn Slope=0.005
Boundary for River Rch & Prof#=Third Caney Cree,Reach-1         , 5
Up Type= 0
Dn Type= 3
Dn Slope=0.005
Boundary for River Rch & Prof#=Third Caney Cree,Reach-1         , 6
Up Type= 0
Dn Type= 3
Dn Slope=0.005
Boundary for River Rch & Prof#=Third Caney Cree,Reach-1         , 7
Up Type= 0
Dn Type= 3
Dn Slope=0.005
DSS Import GetInterval= 0
DSS Import GetPeak= 0
DSS Import FillOption= 0

--- Third Caney Creek.g01 (geometry) ---

Geom Title=Existing Conditions
Program Version=4.10

River Reach=Third Caney Cree,Reach-1
Reach XY= 30
        2798176.        6803961.       2798083.7      6803864.41
      2798118.62      6803754.67      2797928.42      6803616.54
      2797665.32      6803511.75      2797515.95      6803561.77
      2797231.85      6803508.92      2796979.42      6803368.83
      2796827.49      6803407.54      2796465.72      6803061.99
      2796096.18      6803010.72      2795065.81      6803161.46
      2794846.18      6803060.71      2794409.88      6803260.51
       2794034.3      6803207.93       2793921.1      6802966.28
      2793731.11      6802905.89      2793715.59      6802800.94
      2793579.52      6802709.72      2793415.52       6801901.2
      2793132.47       6801568.7      2792977.47      6801557.46
        2792576.        6801311.      2792170.73      6800716.51
      2791934.15      6800567.07      2791833.81      6800414.41
      2791820.65      6800008.26      2791534.46       6799907.5
      2791479.33      6799809.31        2791476.        6799461.

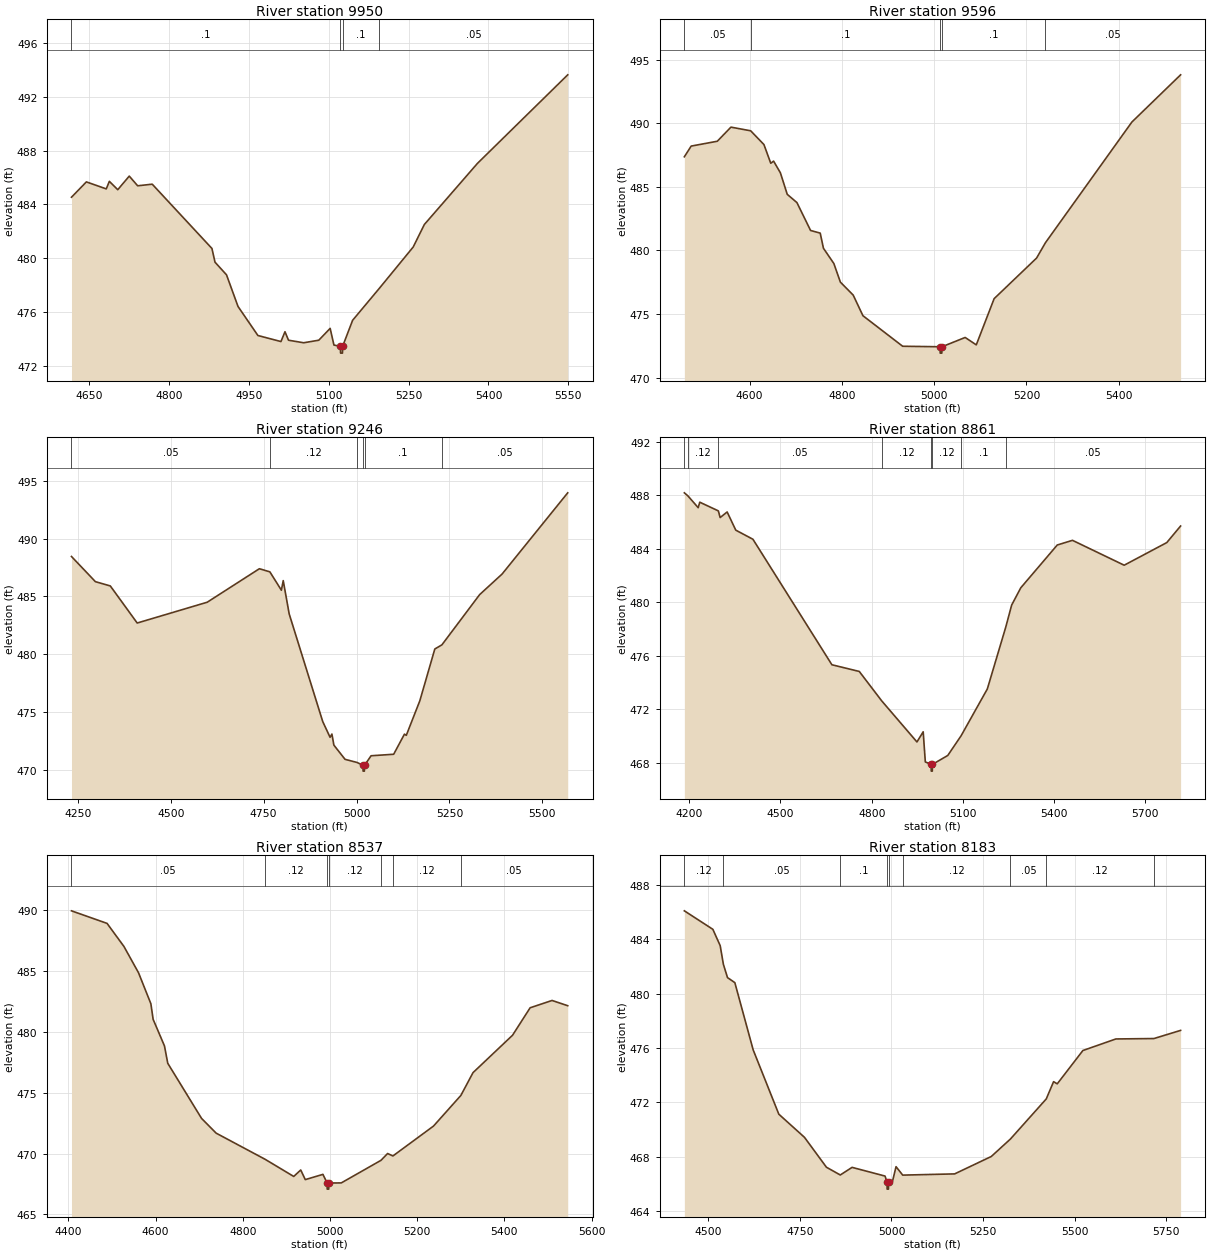
Type RM Length L Ch R = 1 ,9950    ,354,354,354
BEGIN DESCRIPTION:
Third Caney Creek 24.0
END DESCRIPTION:
XS GIS Cut Line= 3
      2798455.78      6803572.39        2798126.        6803761.
      2797761.81      6804176.87
#Sta/Elev= 30
  4616.2  484.54  4644.2  485.68  4681.6  485.16  4687.4  485.72  4703.2   485.1
  4724.8  486.11  4740.6  485.39    4768  485.51  4880.2  480.73    4886  479.71
  4907.6  478.77  4929.2  476.42  4966.6  474.26  5009.9  473.81  5017.5  474.54
  5024.1  473.91  5052.6  473.72    5081  473.91  5102.4  474.79  5109.5  473.55
  5121.8  473.45    5122  472.95  5125.5  472.95  5125.8  473.45  5144.6  475.39
  5195.1  477.78  5258.5  480.84  5279.4  482.51  5379.1  487.05  5548.9  493.64
#Mann= 4 ,-1 , 0
  4616.2      .1       0  5121.8     .07       0  5125.8      .1       0
  5195.1     .05       0
Bank Sta=5121.8,5125.8
XS Rating Curve= 0 ,0
Exp/Cntr=0.3,0.1

Type RM Length L Ch R = 1 ,9596    ,350,350,350
BEGIN DESCRIPTION:
Third Caney Creek 23.0
END DESCRIPTION:
XS GIS Cut Line= 3
      2798139.69      6803164.22        2797826.        6803611.
        2797670.       6804117.3
#Sta/Elev= 30
  4458.4  487.36  4473.2   488.2  4529.8  488.58  4559.4  489.69  4602.2   489.4
  4630.9  488.32  4645.7  486.85  4651.8  487.02  4666.6   486.1  4681.4  484.41
  4702.4  483.76    4732  481.57  4752.9  481.36  4759.9  480.17  4782.5  478.97
  4796.6  477.51  4824.4  476.49  4845.5  474.87  4931.6  472.47  5012.8  472.43
    5013  471.93  5016.5  471.93  5016.8  472.43  5067.1  473.16  5091.2  472.58
  5129.9  476.21  5221.9   479.4    5241   480.6  5428.5  490.09  5534.1   493.8
#Mann= 5 ,-1 , 0
  4458.4     .05       0  4602.2      .1       0  5012.8     .07       0
  5016.8      .1       0    5241     .05       0
Bank Sta=5012.8,5016.8
XS Rating Curve= 0 ,0
Exp/Cntr=0.3,0.1

Type RM Length L Ch R = 1 ,9246    ,385,385,385
BEGIN DESCRIPTION:
Third Caney Creek 22.0
END DESCRIPTION:
XS GIS Cut Line= 3
      2797584.22      6802796.79        2797526.        6803561.
       2797589.9      6804126.48
#Sta/Elev= 30
  4232.8  488.45  4297.2  486.27  4337.3   485.9  4409.7  482.69  4598.1  484.49
  4738.5  487.39  4766.7  487.12  4797.7  485.53  4802.7  486.36  4818.7  483.48
    4909  474.16  4928.7   472.8  4933.7  473.08    4939  472.12  4969.1  470.89
  5001.4  470.62  5017.4  470.37  5017.6  469.87  5021.1  469.87  5021.4  470.37
  5039.1   471.2  5099.9  471.33  5128.9  473.07  5133.9  472.97  5170.3  475.96
  5210.6  480.44  5229.7   480.8  5331.3  485.15  5391.7  486.93  5568.3  493.96
#Mann= 6 ,-1 , 0
  4232.8     .05       0  4766.7     .12       0  5001.4      .1       0
  5017.4     .07       0  5021.4      .1       0  5229.7     .05       0
Bank Sta=5017.4,5021.4
XS Rating Curve= 0 ,0
Exp/Cntr=0.3,0.1

Type RM Length L Ch R = 1 ,8861    ,324,324,324
BEGIN DESCRIPTION:
Third Caney Creek 21.0
END DESCRIPTION:
XS GIS Cut Line= 3
      2797362.51      6802666.38        2797176.        6803461.
      2797158.11      6804276.49
#Sta/Elev= 30
  4183.9  488.19  4195.6  487.96  4229.4  487.08  4234.6  487.49  4295.7  486.84
  4301.6  486.34  4324.6  486.76    4353   485.4  4409.4  484.72  4669.1  475.34
  4759.1  474.84  4833.3  472.63  4948.8  469.57  4969.3  470.33  4976.3  468.08
  4995.5  467.89  4995.8  467.39  4999.3  467.39  4999.5  467.89  5050.1  468.56
  5093.9  470.03  5180.2  473.53  5240.8  478.15  5260.2   479.8  5290.2  481.09
  5410.2  484.29  5460.2  484.64  5630.3  482.78  5770.3  484.47  5815.8  485.71
#Mann= 8 ,-1 , 0
  4183.9      .1       0  4195.6     .12       0  4295.7     .05       0
  4833.3     .12       0  4995.5     .07       0  4999.5     .12       0
  5093.9      .1       0  5240.8     .05       0
Bank Sta=4995.5,4999.5
XS Rating Curve= 0 ,0
Exp/Cntr=0.3,0.1

Type RM Length L Ch R = 1 ,8537    ,354,354,354
BEGIN DESCRIPTION:
Third Caney Creek 20.0
END DESCRIPTION:
XS GIS Cut Line= 3
      2797093.39       6802836.2        2796926.        6803411.
      2796862.13      6803946.62
#Sta/Elev= 30
  4407.1   489.9  4488.7  488.87  4527.4  486.98  4560.9  484.82  4589.2  482.28
  4594.4     481  4620.4  478.82  4627.9   477.4  4705.4  472.88  4738.9  471.67
    4851  469.53  4916.8  468.12  4932.9  468.65  4943.3  467.86  4983.8  468.29
  4993.4  467.58  4993.6  467.08  4997.1  467.08  4997.4  467.58  5025.9  467.59
  5116.9  469.44  5132.1     470  5144.3   469.8  5237.4  472.25  5300.1  474.76
    5328  476.63  5418.7   479.7    5459  481.95  5509.3  482.55  5545.2  482.12
#Mann= 7 ,-1 , 0
  4407.1     .05       0    4851     .12       0  4993.4     .07       0
  4997.4     .12       0  5116.9      .1       0  5144.3     .12       0
  5300.1     .05       0
Bank Sta=4993.4,4997.4
XS Rating Curve= 0 ,0
Exp/Cntr=0.3,0.1

Type RM Length L Ch R = 1 ,8183    ,363,363,363
BEGIN DESCRIPTION:
Third Caney Creek 19.0
END DESCRIPTION:
XS GIS Cut Line= 3
      2796682.81      6802653.24        2796676.        6803211.
      2796681.29      6804007.69
#Sta/Elev= 30
  4434.7  486.09  4512.5  484.73  4532.5  483.53  4541.2  482.16  4552.5  481.18
  4572.5  480.81  4622.5  475.87  4692.5  471.14  4762.5  469.44  4822.5  467.24
  4860.3  466.67  4892.5  467.23  4982.5  466.59    4988  466.13  4988.2  465.63
  4991.7  465.63    4992  466.13  5002.5  466.17  5012.5  467.28  5030.7  466.66
  5172.5  466.75  5272.5  468.03  5324.6  469.31  5422.5  472.26  5442.5  473.53
  5452.5  473.37  5522.5  475.82  5612.5  476.67  5716.4   476.7  5789.2   477.3
#Mann= 9 ,-1 , 0
  4434.7     .12       0  4541.2     .05       0  4860.3      .1       0
    4988     .07       0    4992      .1       0  5030.7     .12       0
  5324.6     .05       0  5422.5     .12       0  5716.4      .1       0
Bank Sta=4988,4992
XS Rating Curve= 0 ,0
Exp/Cntr=0.3,0.1

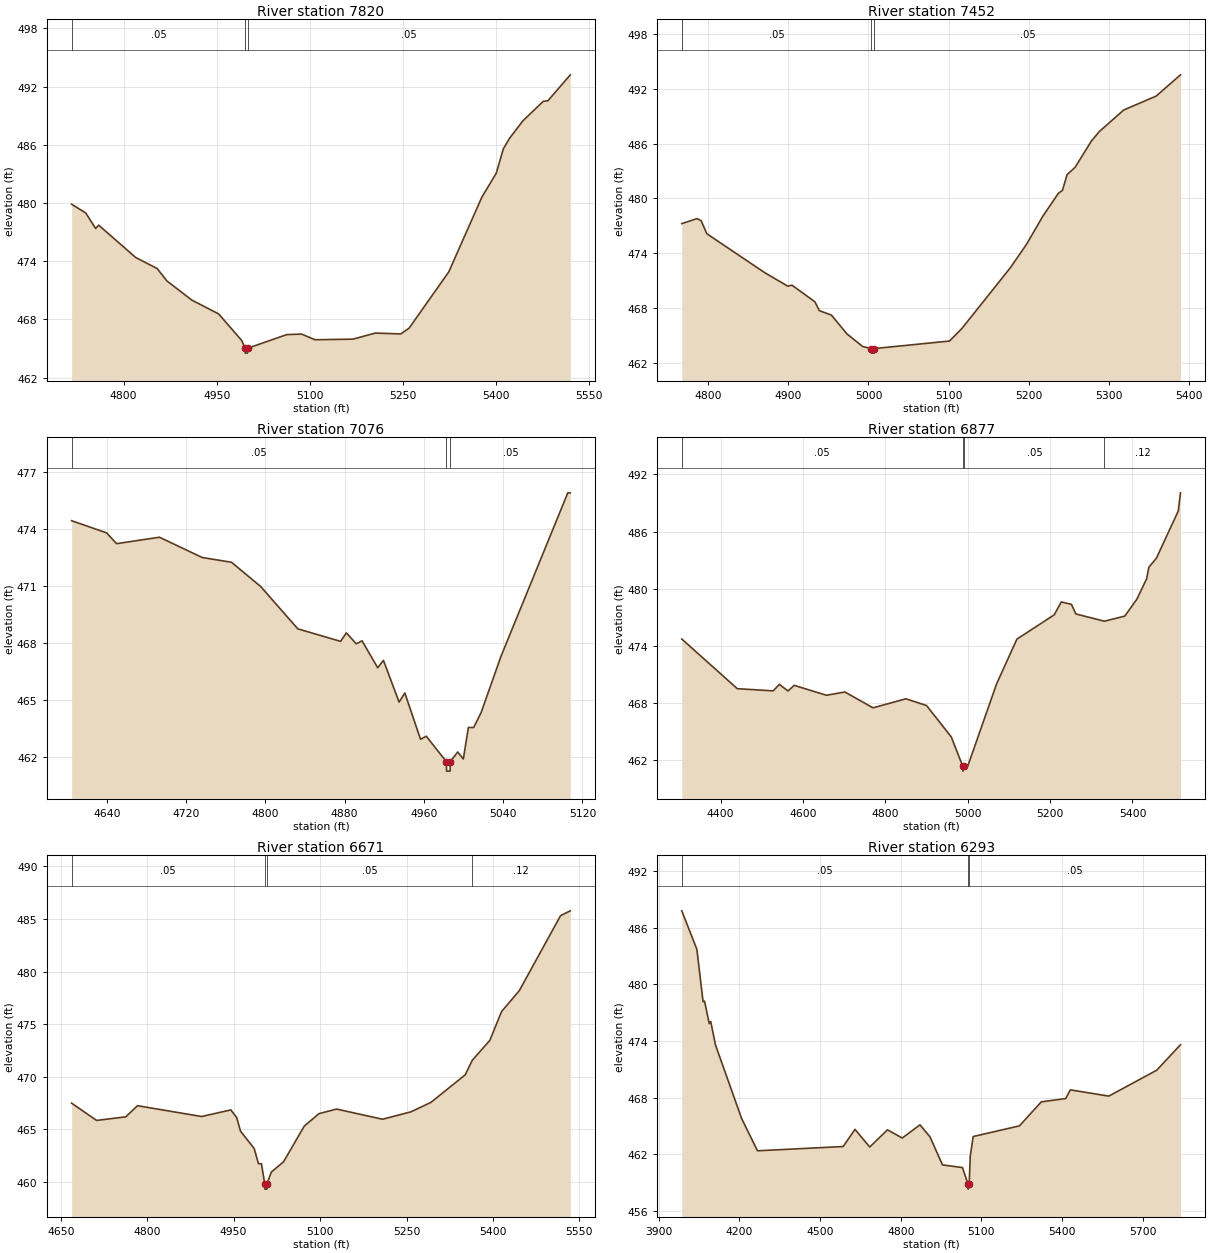
Type RM Length L Ch R = 1 ,7820    ,368,368,368
BEGIN DESCRIPTION:
Third Caney Creek 18.0
END DESCRIPTION:
XS GIS Cut Line= 3
      2796455.03      6802778.27        2796426.        6803061.
      2796228.16      6803541.45
#Sta/Elev= 30
  4716.2  479.88    4739  478.98  4754.9  477.38  4759.9  477.72  4819.5  474.39
  4854.1  473.25  4869.7  471.98  4909.9     470  4953.3  468.57  4990.4  465.83
  4995.9  465.03  4996.1  464.53  4999.6  464.53  4999.9  465.03    5063  466.44
  5086.9  466.49  5108.6  465.91  5169.6  465.97  5205.9   466.6  5246.8  466.51
    5260  467.09  5324.1   472.9  5377.4   480.6  5400.6  483.07  5412.1  485.59
  5422.2  486.69  5443.8  488.49  5476.3  490.48    5484  490.55    5520  493.22
#Mann= 3 ,-1 , 0
  4716.2     .05       0  4995.9     .04       0  4999.9     .05       0
Bank Sta=4995.9,4999.9
XS Rating Curve= 0 ,0
Exp/Cntr=0.3,0.1

Type RM Length L Ch R = 1 ,7452    ,376,376,376
BEGIN DESCRIPTION:
Third Caney Creek 17.0
END DESCRIPTION:
XS GIS Cut Line= 3
      2796136.99      6802790.94        2796076.        6803011.
      2796019.93      6803401.04
#Sta/Elev= 30
    4767  477.25    4786   477.8  4791.2  477.57  4798.2  476.15  4870.8  471.88
  4899.3  470.42  4904.5  470.53  4933.1  468.72  4938.7  467.75  4953.8  467.26
    4973  465.22  4992.8  463.83  5003.5  463.61  5003.7  463.11  5007.2  463.11
  5007.5  463.61  5101.1  464.43  5116.6   465.8  5177.2  472.45  5197.4  475.01
  5217.6  478.06  5237.1  480.57  5242.1  480.89  5247.9   482.6    5258  483.41
  5278.2  486.27  5288.3  487.32  5318.6  489.66  5359.1  491.18  5389.4   493.5
#Mann= 3 ,-1 , 0
    4767     .05       0  5003.5     .04       0  5007.5     .05       0
Bank Sta=5003.5,5007.5
XS Rating Curve= 0 ,0
Exp/Cntr=0.3,0.1

Type RM Length L Ch R = 1 ,7076    ,199,199,199
BEGIN DESCRIPTION:
Third Caney Creek 16.0
END DESCRIPTION:
XS GIS Cut Line= 3
      2795926.01      6802760.98        2795726.        6803111.
        2795726.      6803210.97
#Sta/Elev= 30
  4604.6  474.44  4639.9   473.8    4650  473.23  4693.2  473.57  4736.4   472.5
  4765.9  472.25  4795.4  470.97  4832.8  468.74    4876  468.08  4881.8  468.53
  4891.8  467.95  4897.6  468.11  4913.4  466.69  4919.2  467.08    4935  464.88
  4940.8  465.36  4956.6  462.92  4962.4  463.08  4982.7  461.74  4982.9  461.24
  4986.4  461.24  4986.7  461.74  4994.1  462.25  4999.8  461.88  5004.9  463.54
  5010.2  463.54  5017.7  464.32  5037.7  467.28  5105.2  475.91  5107.7  475.91
#Mann= 3 ,-1 , 0
  4604.6     .05       0  4982.7     .04       0  4986.7     .05       0
Bank Sta=4982.7,4986.7
XS Rating Curve= 0 ,0
Exp/Cntr=0.3,0.1

Type RM Length L Ch R = 1 ,6877    ,206,206,206
BEGIN DESCRIPTION:
Mapping XS 1728e653
END DESCRIPTION:
XS GIS Cut Line= 4
      2795772.53        6802489.      2795533.95      6802846.61
       2795530.2       6803340.1      2795641.34      6803605.14
#Sta/Elev= 30
  4305.7  474.73  4440.5  469.52  4527.6  469.29  4542.6  469.97  4563.6  469.28
  4578.7  469.87  4656.8  468.83  4701.8  469.17    4770  467.51    4850  468.46
    4900  467.75    4960  464.46    4988  461.37  4988.2  460.87    4992  461.37
    5000  461.39    5070  470.02  5119.4  474.72    5210  477.27    5227  478.62
  5251.7  478.37  5262.6  477.36  5331.9   476.6  5381.4  477.14  5410.6  478.91
  5434.4  481.06  5439.8  482.27  5457.8  483.19  5511.1  488.16  5516.5  490.07
#Mann= 4 ,-1 , 0
  4305.7     .05       0    4988     .04       0    4992     .05       0
  5331.9     .12       0
Bank Sta=4988,4992
XS Rating Curve= 0 ,0
Exp/Cntr=0.3,0.1

Type RM Length L Ch R = 1 ,6671    ,378,378,378
BEGIN DESCRIPTION:
Third Caney Creek 15.0
END DESCRIPTION:
XS GIS Cut Line= 3
       2795275.1      6802788.11        2795326.        6803111.
       2795438.4      6803637.56
#Sta/Elev= 30
  4668.9  467.49  4712.3  465.85  4762.9  466.19  4783.2  467.25  4894.5  466.22
  4945.2  466.85  4955.3  466.13    4962  464.83  4985.7  463.18  4993.2  461.74
  4998.3  461.74    5004  459.82  5004.3  459.32  5007.8  459.32    5008  459.82
  5015.4  460.94  5036.7  461.92  5072.5   465.3    5098  466.49  5128.7  466.93
  5208.4  465.96  5257.9  466.67  5292.3  467.56  5351.8  470.18  5364.2  471.57
  5394.6  473.46    5415   476.2  5445.7  478.18  5517.3  485.31  5534.2  485.77
#Mann= 4 ,-1 , 0
  4668.9     .05       0    5004     .04       0    5008     .05       0
  5364.2     .12       0
Bank Sta=5004,5008
XS Rating Curve= 0 ,0
Exp/Cntr=0.3,0.1

Type RM Length L Ch R = 1 ,6293    ,337,337,337
BEGIN DESCRIPTION:
Third Caney Creek 14.0
END DESCRIPTION:
XS GIS Cut Line= 3
      2794557.68      6802194.84        2794976.        6803111.
      2795331.05      6803881.38
#Sta/Elev= 30
  3985.5  487.79  4041.7  483.71  4064.7  478.17  4070.2  478.23  4087.7  475.84
  4093.2  476.07  4110.8  473.59  4208.4  465.78  4267.1  462.38  4585.9  462.83
  4629.9  464.65  4684.8  462.78  4750.8   464.6  4805.8  463.73  4871.7  465.13
  4909.3  463.84  4955.3  460.89  5029.8   460.6  5050.8  458.82    5051  458.32
  5054.8  458.82  5058.7  461.79  5069.7  463.89  5241.9  465.02    5323  467.56
  5413.7  467.91  5431.1  468.83  5574.3  468.17  5752.4  470.91  5840.9  473.61
#Mann= 3 ,-1 , 0
  3985.5     .05       0  5050.8     .04       0  5054.8     .05       0
Bank Sta=5050.8,5054.8
XS Rating Curve= 0 ,0
Exp/Cntr=0.3,0.1

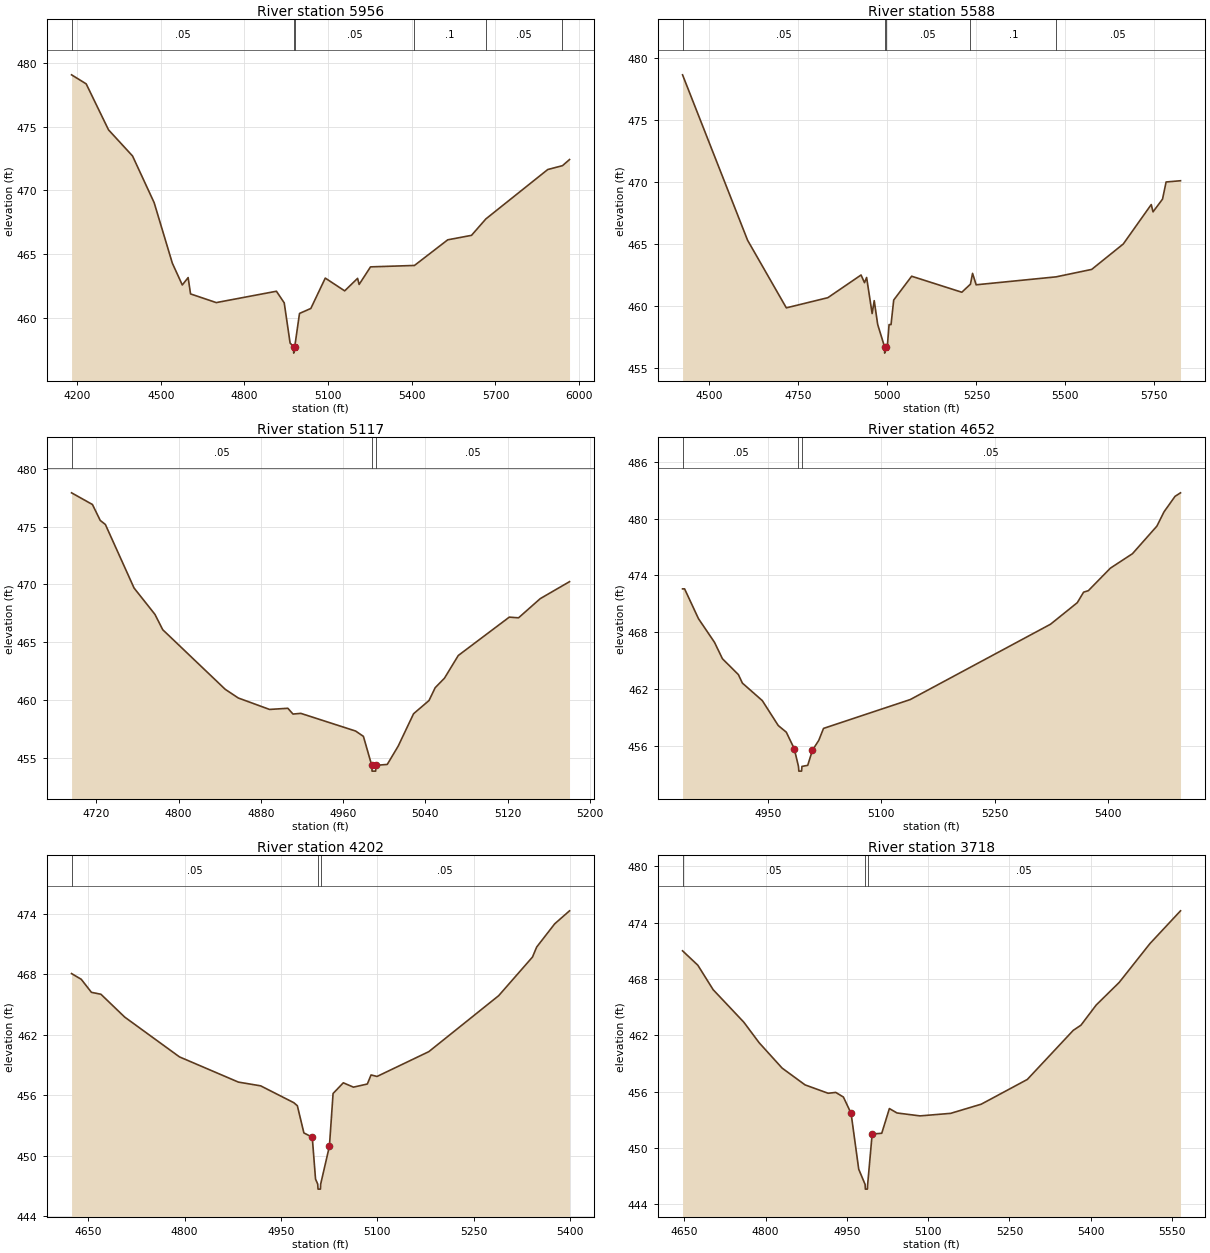
Type RM Length L Ch R = 1 ,5956    ,368,368,368
BEGIN DESCRIPTION:
Third Caney Creek 13.0
END DESCRIPTION:
XS GIS Cut Line= 3
      2794202.07      6802441.23        2794676.        6803111.
      2795070.88      6803991.74
#Sta/Elev= 30
  4179.9  479.06  4232.4  478.35  4312.4  474.75  4398.6   472.7  4476.1  469.04
  4541.3   464.3    4577  462.59  4597.9  463.17  4606.6  461.89  4698.8  461.21
  4914.6   462.1  4942.5  461.19  4963.6  458.04  4976.2  457.75  4976.5  457.25
  4980.2  457.75  4997.3  460.36  5037.9  460.75  5089.7  463.13  5159.3  462.13
  5205.6  463.11  5211.1  462.63    5252  464.01  5409.5  464.12  5528.9  466.13
  5614.1  466.48  5665.7  467.77  5887.6  471.64  5940.3  471.94  5965.6  472.42
#Mann= 6 ,-1 , 0
  4179.9     .05       0  4976.2     .04       0  4980.2     .05       0
  5409.5      .1       0  5665.7     .05       0  5940.3     .12       0
Bank Sta=4976.2,4980.2
XS Rating Curve= 0 ,0
Exp/Cntr=0.3,0.1

Type RM Length L Ch R = 1 ,5588    ,471,471,471
BEGIN DESCRIPTION:
Third Caney Creek 12.0
END DESCRIPTION:
XS GIS Cut Line= 3
      2794076.02      6802761.03        2794376.        6803261.
      2794281.92       6804071.2
#Sta/Elev= 30
  4424.7  478.65  4607.4  465.31  4716.2  459.86  4832.8  460.68  4926.1  462.51
  4935.8  461.89  4941.7  462.31  4957.2   459.4  4963.1  460.44  4972.8  458.52
  4992.2  456.71  4992.4  456.21  4996.2  456.71    5000   456.8  5004.8  458.51
  5010.3  458.51  5017.8  460.49  5068.2  462.41  5209.1  461.12  5233.3  461.77
  5239.3  462.64  5249.4  461.72  5473.9  462.36  5573.9  462.96  5662.6  465.01
  5741.2  468.19  5746.2   467.6  5772.9  468.63  5782.9  470.01  5823.4  470.11
#Mann= 5 ,-1 , 0
  4424.7     .05       0  4992.2     .04       0  4996.2     .05       0
  5233.3      .1       0  5473.9     .05       0
Bank Sta=4992.2,4996.2
XS Rating Curve= 0 ,0
Exp/Cntr=0.3,0.1

Type RM Length L Ch R = 1 ,5117    ,465,465,465
BEGIN DESCRIPTION:
Third Caney Creek 11.0
END DESCRIPTION:
XS GIS Cut Line= 3
        2794026.        6802811.        2793976.        6803111.
      2793876.01      6803260.99
#Sta/Elev= 30
  4695.9  477.93  4716.2  476.92  4723.8  475.54  4728.8  475.19  4756.7  469.69
    4777  467.41  4784.6  466.08  4845.4  460.92  4858.1  460.17  4888.5  459.18
  4906.3  459.28  4911.3  458.78  4918.9  458.84  4972.2  457.31  4979.8  456.85
  4987.9  454.34  4988.2  453.84  4991.7  453.84    4992  454.34    5003  454.42
  5013.6     456  5028.6  458.81  5043.6  459.95  5049.6  461.06  5058.6  461.88
  5072.1  463.85  5121.7  467.17  5130.7  467.11  5151.8  468.77  5180.3  470.24
#Mann= 3 ,-1 , 0
  4695.9     .05       0  4987.9     .04       0    4992     .05       0
Bank Sta=4987.9,4992
XS Rating Curve= 0 ,0
Exp/Cntr=0.3,0.1

Type RM Length L Ch R = 1 ,4652    ,450,450,450
BEGIN DESCRIPTION:
Third Caney Creek 10.0
END DESCRIPTION:
XS GIS Cut Line= 3
      2793876.03      6802760.99        2793726.        6802811.
      2793426.03      6803210.97
#Sta/Elev= 30
  4837.2  472.57  4839.9  472.57  4858.3  469.41  4879.4  466.92  4889.9  465.18
    4911   463.5  4916.3   462.6  4942.6  460.75  4963.7  458.11  4974.3  457.41
  4984.8  455.67  4990.4  453.79  4990.9  453.29  4994.5  453.29    4995  453.79
  5002.6   453.9  5008.9  455.51  5017.2  456.54  5023.5  457.81  5138.1  460.86
  5323.5  468.83  5358.9  471.11  5367.2  472.22  5373.5  472.38  5402.6  474.76
  5431.8  476.29  5464.1  479.21  5473.5  480.72  5488.1  482.36  5495.3  482.73
#Mann= 3 ,-1 , 0
  4837.2     .05       0  4990.4     .04       0    4995     .05       0
Bank Sta=4984.8,5008.9
XS Rating Curve= 0 ,0
Exp/Cntr=0.3,0.1

Type RM Length L Ch R = 1 ,4202    ,484,484,484
BEGIN DESCRIPTION:
Third Caney Creek 9.0
END DESCRIPTION:
XS GIS Cut Line= 3
      2793890.81      6802389.98        2793526.        6802461.
      2793175.97      6802661.01
#Sta/Elev= 30
  4624.1  468.08  4639.2  467.51    4655  466.22  4669.8  466.03  4706.7  463.77
    4792  459.82  4883.7  457.32  4918.3  456.95  4969.9  455.28  4975.4  454.98
  4985.6  452.28  4998.6  451.86  5003.7  447.71  5007.1  447.21  5007.6  446.71
  5011.3  446.71  5011.7  447.21  5025.3  450.96    5031  456.19  5046.9  457.25
  5062.7  456.82  5084.3  457.13  5090.1  458.03  5099.4  457.88    5180  460.34
  5288.7  465.89  5341.3  469.72  5347.8  470.71  5375.8  473.01  5398.9   474.3
#Mann= 3 ,-1 , 0
  4624.1     .05       0  5007.1     .04       0  5011.7     .05       0
Bank Sta=4998.6,5025.3
XS Rating Curve= 0 ,0
Exp/Cntr=0.3,0.1

Type RM Length L Ch R = 1 ,3718    ,453,453,453
BEGIN DESCRIPTION:
Third Caney Creek 8.0
END DESCRIPTION:
XS GIS Cut Line= 3
      2793675.97      6801761.03        2793426.        6802011.
        2793026.        6802411.
#Sta/Elev= 30
  4646.6  470.99  4674.8  469.46  4703.1  466.85  4759.7  463.39    4788   461.2
  4830.4   458.5  4872.8  456.71  4915.3  455.82  4929.4  455.91  4943.5  455.42
  4957.7  453.68  4971.8  447.73  4983.6  446.11  4984.1  445.61  4987.8  445.61
  4988.3  446.11  4996.6  451.48  5014.3  451.56  5028.4  454.19  5042.5  453.72
    5085  453.41  5141.5  453.68  5198.1  454.66    5283  457.29  5367.8  462.52
    5382  463.07  5410.2  465.22  5452.7  467.63  5509.2  471.75  5565.8  475.25
#Mann= 3 ,-1 , 0
  4646.6     .05       0  4983.6     .04       0  4988.3     .05       0
Bank Sta=4957.7,4996.6
XS Rating Curve= 0 ,0
Exp/Cntr=0.3,0.1

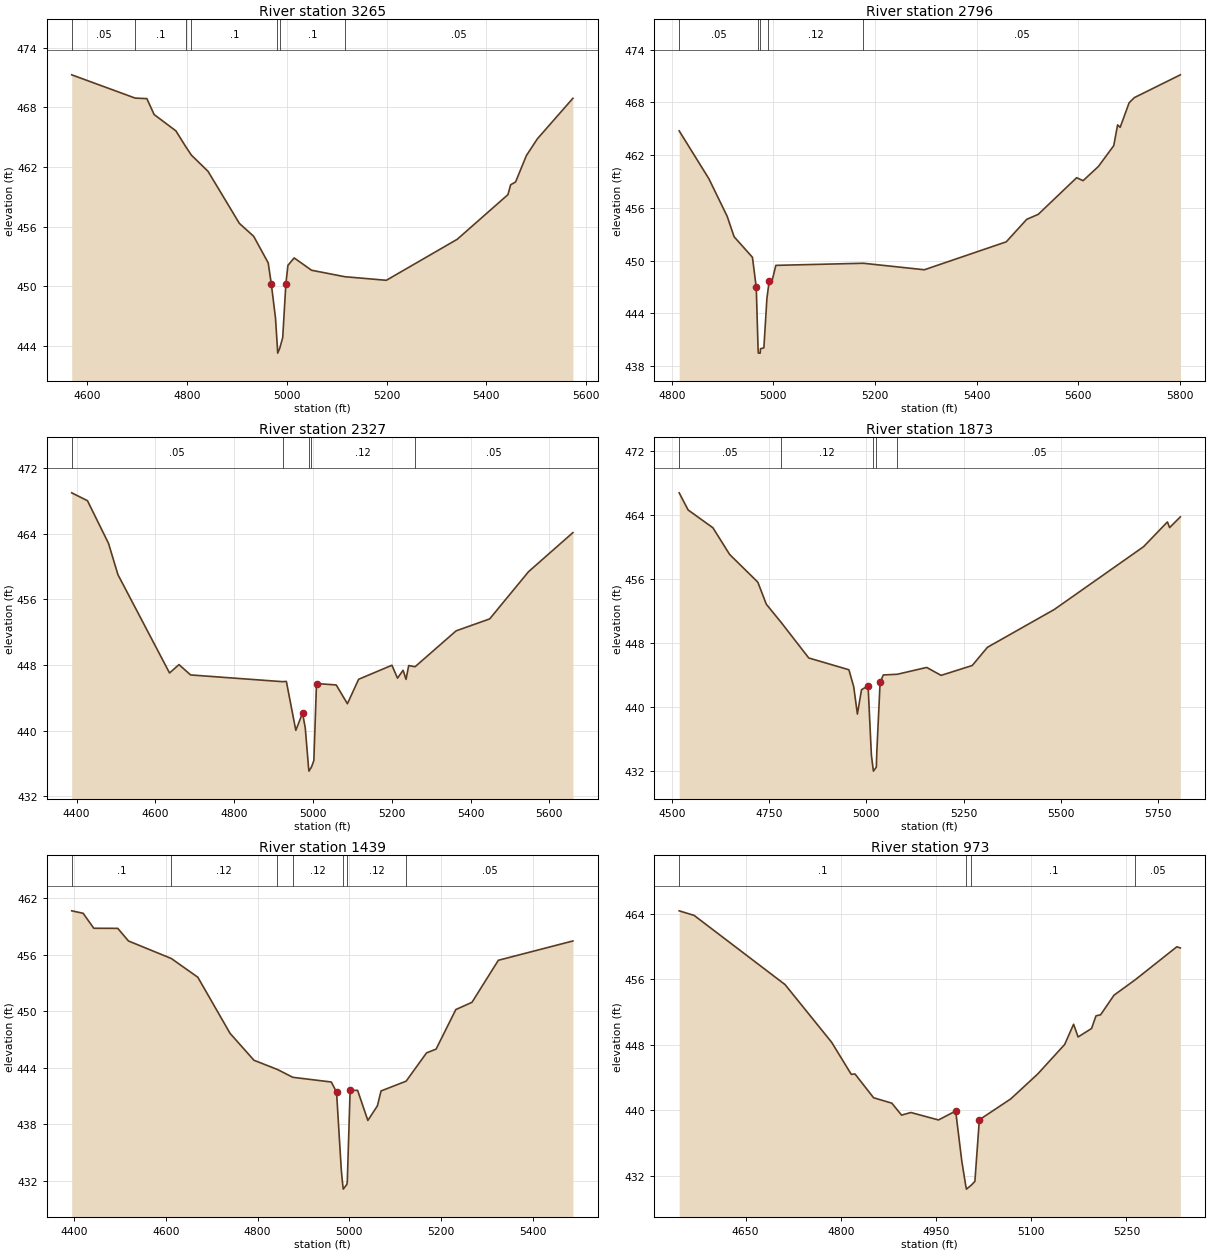
Type RM Length L Ch R = 1 ,3265    ,469,469,469
BEGIN DESCRIPTION:
Third Caney Creek 7.0
END DESCRIPTION:
XS GIS Cut Line= 3
      2793440.11      6801313.41        2793176.        6801661.
       2792962.4      6802187.47
#Sta/Elev= 30
  4568.7  471.26    4696  468.92  4719.3  468.87  4733.9  467.27  4777.5  465.63
  4798.2  463.97  4808.6  463.19    4842  461.56  4904.8  456.33  4933.5  455.03
  4962.6  452.36  4968.9  450.21  4977.2  446.82  4981.1  443.79  4981.6  443.29
  4985.8  443.79  4991.7  444.86    4998  450.25  5002.1  452.11  5014.6  452.86
  5049.5  451.62  5116.1  450.97  5199.4  450.61  5341.5  454.73  5443.2  459.22
  5448.6  460.21  5458.5  460.49  5480.1  463.14  5502.2  464.83  5573.4   468.9
#Mann= 7 ,-1 , 0
  4568.7     .05       0    4696      .1       0  4798.2     .05       0
  4808.6      .1       0  4981.1     .07       0  4985.8      .1       0
  5116.1     .05       0
Bank Sta=4968.9,4998
XS Rating Curve= 0 ,0
Exp/Cntr=0.3,0.1

Type RM Length L Ch R = 1 ,2796    ,469,469,469
BEGIN DESCRIPTION:
Third Caney Creek 6.0
END DESCRIPTION:
XS GIS Cut Line= 3
      2792975.96      6801311.03        2792826.        6801411.
      2792926.01      6802211.05
#Sta/Elev= 30
  4814.7  464.77  4873.2  459.32  4909.3  455.03  4922.8  452.72  4958.9  450.38
  4966.4  446.96    4970  439.97  4970.5  439.47  4974.2  439.47  4974.7  439.97
  4981.4  440.07  4987.4  445.71  4989.1  446.45  4991.9  447.68  4997.4  447.68
    5005  449.46  5177.2   449.7  5297.3  448.96  5458.5  452.14  5498.8   454.7
  5521.5  455.27  5597.1  459.44  5609.7   459.1  5639.9  460.72  5670.1  463.09
  5677.7  465.45  5682.7  465.17  5700.4  467.97  5710.5  468.55  5801.2  471.15
#Mann= 5 ,-1 , 0
  4814.7     .05       0    4970     .07       0  4974.7     .05       0
  4989.1     .12       0  5177.2     .05       0
Bank Sta=4966.4,4991.9
XS Rating Curve= 0 ,0
Exp/Cntr=0.3,0.1

Type RM Length L Ch R = 1 ,2327    ,454,454,454
BEGIN DESCRIPTION:
Third Caney Creek 5.0
END DESCRIPTION:
XS GIS Cut Line= 3
      2792706.03      6800598.74        2792476.        6801161.
      2792031.92      6801655.46
#Sta/Elev= 30
  4387.7  468.98  4427.7  468.02  4481.1  462.82  4505.1     459    4636  447.03
    4660  448.05  4689.4  446.79  4922.8  445.97  4932.5     446  4956.5  440.04
  4973.6  442.14  4980.5  440.33  4988.7  435.57  4989.8  435.07  4996.3  435.57
  5002.3  436.37    5009  445.74  5059.1  445.57  5087.5  443.28  5115.9  446.26
  5200.4  447.97  5214.6   446.4  5228.8  447.36  5236.3  446.25    5243  447.93
  5259.2  447.79  5363.3  452.16  5448.6  453.62  5547.2  459.37  5659.8  464.13
#Mann= 5 ,-1 , 0
  4387.7     .05       0  4922.8     .12       0  4988.7     .07       0
  4996.3     .12       0  5259.2     .05       0
Bank Sta=4973.6,5009
XS Rating Curve= 0 ,0
Exp/Cntr=0.3,0.1

Type RM Length L Ch R = 1 ,1873    ,434,434,434
BEGIN DESCRIPTION:
Third Caney Creek 4.0
END DESCRIPTION:
XS GIS Cut Line= 3
        2792626.        6800561.        2792226.        6800811.
      2791858.36      6801540.17
#Sta/Elev= 30
    4519  466.74    4542   464.6  4605.7  462.38  4648.7  459.05  4721.2  455.59
  4743.1  452.83  4781.1  450.57  4852.1  446.13  4955.3  444.66  4967.7  442.53
  4977.1  439.13  4987.7  442.17  5004.6  442.66  5013.1     434    5017  432.51
  5018.3  432.01  5025.8  432.51    5027   434.4  5035.5   443.1  5043.7  444.01
  5079.9   444.1  5155.2  444.95  5192.3  443.96  5272.3  445.19  5311.3  447.46
  5483.5  452.19  5712.8  460.02  5774.1  463.11  5779.7   462.4  5807.3  463.74
#Mann= 5 ,-1 , 0
    4519     .05       0  4781.1     .12       0    5017     .07       0
  5025.8     .12       0  5079.9     .05       0
Bank Sta=5004.6,5035.5
XS Rating Curve= 0 ,0
Exp/Cntr=0.3,0.1

Type RM Length L Ch R = 1 ,1439    ,466,466,466
BEGIN DESCRIPTION:
Third Caney Creek 3.0
END DESCRIPTION:
XS GIS Cut Line= 3
      2792483.68      6800316.05        2791926.        6800561.
      2791552.67      6800866.66
#Sta/Elev= 30
  4395.2  460.65    4420  460.39  4443.3   458.8  4495.5  458.79  4518.8  457.45
  4612.1  455.59  4669.9   453.6    4740  447.65  4792.1  444.79  4843.2  443.81
  4876.7  442.98  4960.6  442.48    4972  441.41  4982.5  433.05  4985.4  431.61
  4986.7  431.11  4994.4  431.61  4995.4  431.89  5001.6  441.61  5017.9  441.59
  5040.2   438.4    5061  439.95  5068.9  441.53  5123.6  442.57    5168  445.57
  5188.8  445.97  5231.8  450.17    5267  450.94  5324.4   455.4  5486.8  457.45
#Mann= 7 ,-1 , 0
  4395.2      .1       0  4612.1     .12       0  4843.2     .05       0
  4876.7     .12       0  4985.4     .07       0  4994.4     .12       0
  5123.6     .05       0
Bank Sta=4972,5001.6
XS Rating Curve= 0 ,0
Exp/Cntr=0.3,0.1

Type RM Length L Ch R = 1 ,973     ,252,252,252
BEGIN DESCRIPTION:
Third Caney Creek 2.0
END DESCRIPTION:
XS GIS Cut Line= 3
       2792217.2      6799921.32        2791826.        6800161.
      2791593.83      6800396.65
#Sta/Elev= 30
  4545.4  464.35    4569  463.79  4712.2  455.35  4785.6  448.31  4816.5   444.4
  4822.4  444.44  4851.7  441.54  4880.4  440.88  4895.8  439.42  4910.4  439.74
  4953.9  438.83    4981  439.92  4990.6  433.85  4996.7  430.89    4998  430.39
  5005.8  430.89  5011.3  431.34  5018.3  438.85  5067.8   441.4  5110.3  444.44
  5152.7  448.04  5166.8  450.51  5173.9  448.96  5195.1  449.99  5202.1  451.54
  5209.3  451.66  5230.4  454.05  5264.1  455.95  5329.4  459.96    5335  459.82
#Mann= 4 ,-1 , 0
  4545.4      .1       0  4996.7     .07       0  5005.8      .1       0
  5264.1     .05       0
Bank Sta=4981,5018.3
XS Rating Curve= 0 ,0
Exp/Cntr=0.3,0.1

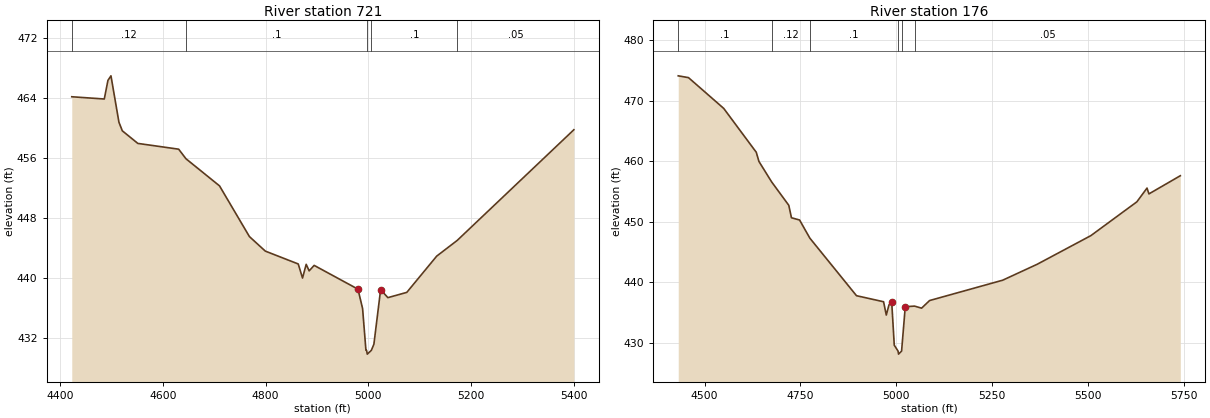
Type RM Length L Ch R = 1 ,721     ,545,545,545
BEGIN DESCRIPTION:
Mapping XS 83df3cb5
END DESCRIPTION:
XS GIS Cut Line= 2
      2792038.17      6799466.87      2791531.55       6800302.6
#Sta/Elev= 30
  4422.7  464.14    4486  463.84  4493.1  466.32    4499  466.93  4514.5  460.75
  4521.1   459.6  4551.3  457.92  4630.8  457.15  4644.9  455.88  4710.3  452.26
  4768.5   445.5  4799.5  443.56  4863.5  441.85  4871.9  439.97    4879   441.8
  4884.8  440.93  4894.5  441.66  4979.8  438.49  4988.8   435.9  4995.3  430.35
  4996.6  430.33  4997.9  429.83  5005.8  430.33  5010.8  431.15  5023.9  438.43
    5038  437.36  5074.8  438.06    5133  442.89    5173  444.99    5400  459.74
#Mann= 5 ,-1 , 0
  4422.7     .12       0  4644.9      .1       0  4996.6     .07       0
  5005.8      .1       0    5173     .05       0
Bank Sta=4979.8,5023.9
XS Rating Curve= 0 ,0
Exp/Cntr=0.3,0.1

Type RM Length L Ch R = 1 ,176     ,0,0,0
BEGIN DESCRIPTION:
Third Caney Creek 1.0
END DESCRIPTION:
XS GIS Cut Line= 4
      2791928.32      6799215.39      2791528.33      6799615.37
      2791358.61      6799802.62       2791373.6      6800294.31
#Sta/Elev= 30
  4431.1  474.12  4457.9  473.82  4549.8  468.74  4634.7   461.5  4641.8  459.97
    4675  456.59  4719.6  452.74  4726.6  450.68  4747.8  450.31  4774.5  447.32
  4896.3  437.81    4967  436.81  4974.1  434.62  4981.2  436.31  4988.3  436.69
  4994.9  429.63  5004.8  428.66  5006.1  428.16    5014  428.66  5023.6  435.99
  5047.8  436.09  5066.2  435.75  5087.1  437.01  5277.9  440.37  5367.9     443
    5508  447.73    5628  453.31  5654.5  455.58  5659.5  454.62  5741.4  457.62
#Mann= 6 ,-1 , 0
  4431.1      .1       0    4675     .12       0  4774.5      .1       0
  5004.8     .07       0    5014      .1       0  5047.8     .05       0
Bank Sta=4988.3,5023.6
XS Rating Curve= 0 ,0
Exp/Cntr=0.3,0.1

Chan Stop Cuts=-1
Use User Specified Reach Order=0
Composite Channel Slope=5