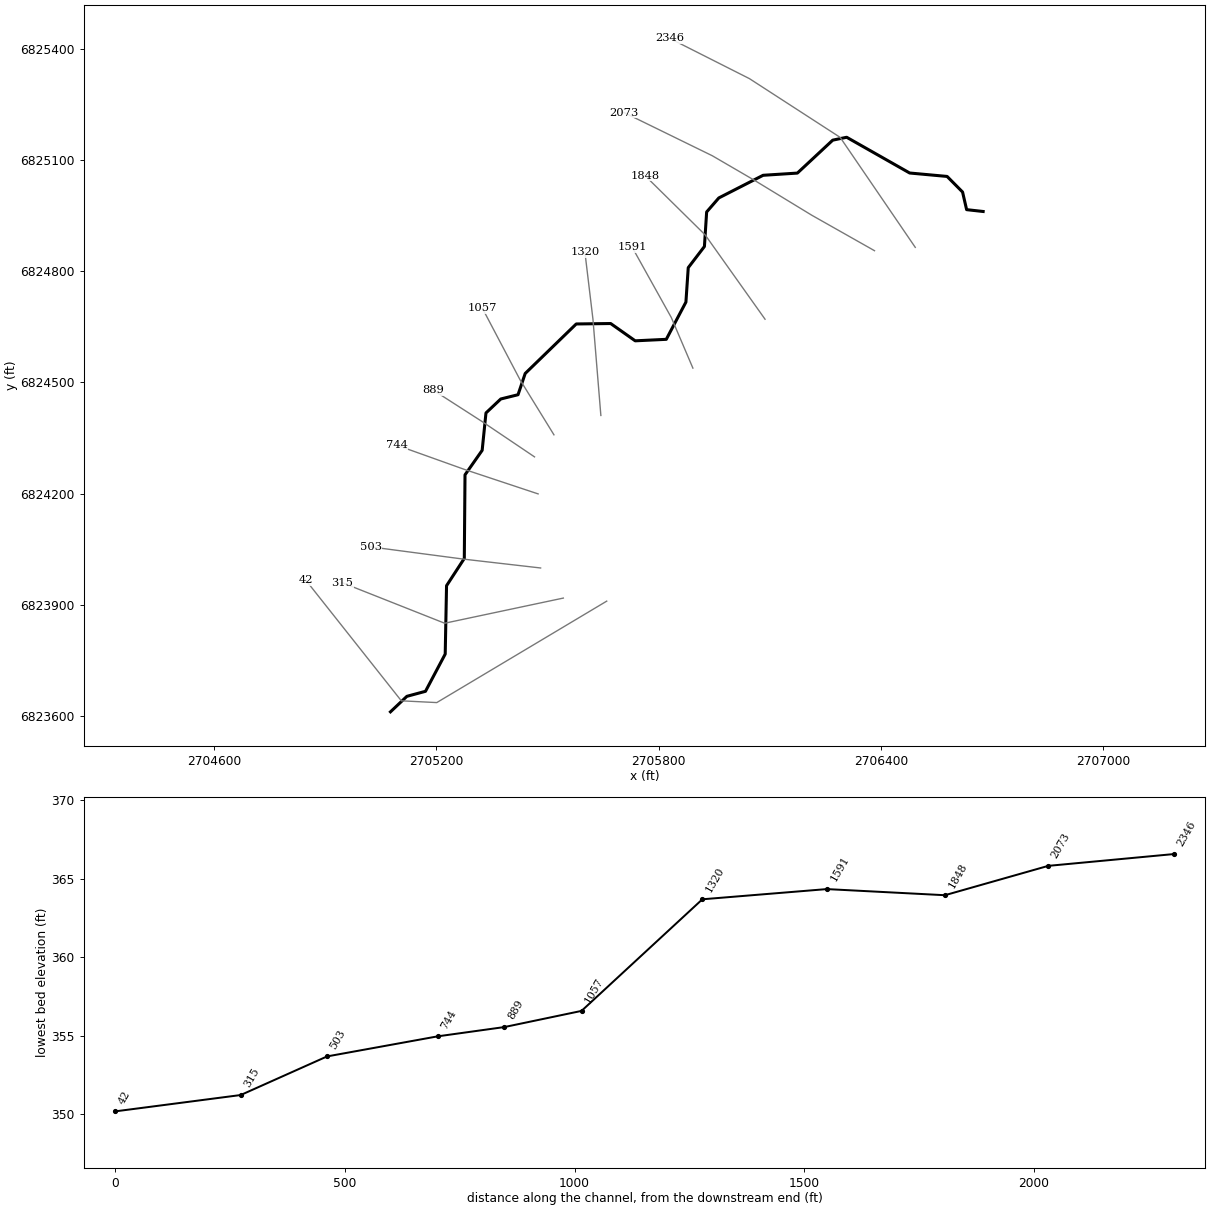
--- Twin Creek132.prj (project) ---

Proj Title=Twin Creek132 Base Level Engineering
Current Plan=p01
Default Exp/Contr=0.3,0.1
English Units
Geom File=g01
Flow File=f01
Plan File=p01
BEGIN DESCRIPTION:
Twin Creek132
END DESCRIPTION:

--- Twin Creek132.p01 (plan) ---

Plan Title=Multiple Run
Short Identifier=Multiple
Geom File=g01
Flow File=f01
Subcritical Flow
K Sum by GR= 0
Std Step Tol= 0.01
Critical Tol= 0.01
Num of Std Step Trials= 20
Max Error Tol= 0.3
Flow Tol Ratio= 0.001
Split Flow NTrial= 30
Split Flow Tol= 0.02
Split Flow Ratio= 0.02
Log Output Level= 0
Friction Slope Method= 1
Unsteady Friction Slope Method= 2
Unsteady Bridges Friction Slope Method= 1
Parabolic Critical Depth
Global Vel Dist=  1 , 1 , 1
Global Log Level= 0
CheckData=True
Encroach Param= -1, 0, 0, 0
BEGIN DESCRIPTION:
Multiple Run
END DESCRIPTION:

--- Twin Creek132.f01 (steady flow) ---

Flow Title=Multiple
Number of Profiles=7
Profile Names=10-year,25-year,50-year,1pct_min,100-year,1pct_plu,500-year
River Rch & RM= Twin Creek132,Reach-1,2346
     339     436     511     298     594    1185     801
Boundary for River Rch & Prof#=Twin Creek132,Reach-1,1
Up Type=0
Dn Type=3
Dn Slope=0.005
Boundary for River Rch & Prof#=Twin Creek132,Reach-1,2
Up Type=0
Dn Type=3
Dn Slope=0.005
Boundary for River Rch & Prof#=Twin Creek132,Reach-1,3
Up Type=0
Dn Type=3
Dn Slope=0.005
Boundary for River Rch & Prof#=Twin Creek132,Reach-1,4
Up Type=0
Dn Type=3
Dn Slope=0.005
Boundary for River Rch & Prof#=Twin Creek132,Reach-1,5
Up Type=0
Dn Type=3
Dn Slope=0.005
Boundary for River Rch & Prof#=Twin Creek132,Reach-1,6
Up Type=0
Dn Type=3
Dn Slope=0.005
Boundary for River Rch & Prof#=Twin Creek132,Reach-1,7
Up Type=0
Dn Type=3
Dn Slope=0.005

--- Twin Creek132.g01 (geometry) ---

Geom Title=Existing Conditions

River Reach=Twin Creek132,Reach-1
Reach XY= 30
      2706676.00      6824961.00      2706631.35      6824965.96
      2706620.42      6825013.46      2706578.67      6825055.58
      2706477.59      6825064.83      2706307.55      6825161.26
      2706269.95      6825153.50      2706174.50      6825064.62
      2706081.97      6825058.67      2705962.37      6824997.55
      2705929.52      6824959.72      2705923.53      6824866.57
      2705879.85      6824809.40      2705873.57      6824716.53
      2705820.56      6824616.09      2705736.66      6824612.06
      2705670.43      6824658.71      2705577.50      6824657.54
      2705439.72      6824523.98      2705420.35      6824466.64
      2705373.76      6824455.12      2705333.79      6824417.44
      2705323.53      6824316.57      2705277.22      6824250.50
      2705275.32      6824024.92      2705227.38      6823951.34
      2705223.77      6823766.90      2705170.53      6823666.42
      2705120.30      6823652.88      2705076.00      6823611.00

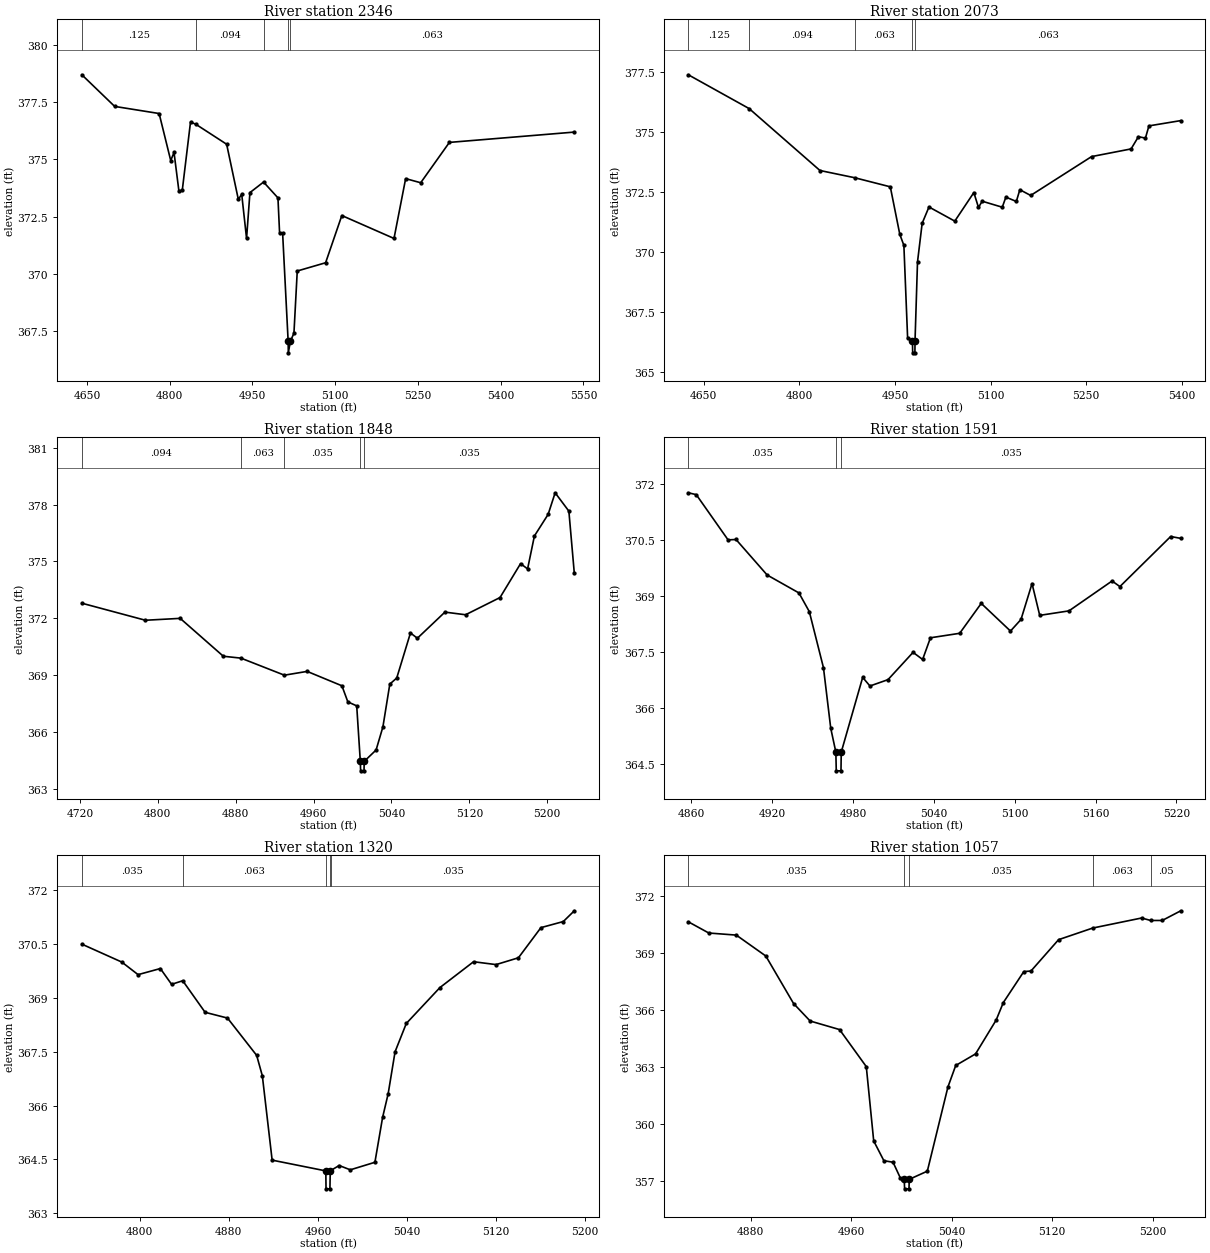
Type RM Length L Ch R = 1,2346,273,273,273
BEGIN DESCRIPTION:
Twin Creek1322384.403
END DESCRIPTION:
XS GIS Cut Line= 4
      2706492.71      6824864.21      2706290.04      6825160.90
      2706045.12      6825319.42      2705829.31      6825428.38
#Sta/Elev= 30
  4640.7  378.69  4700.2  377.31  4780.8  377.00  4801.8  374.95  4807.8  375.30
  4816.7  373.61  4822.8  373.66  4837.7  376.63  4847.4  376.53  4903.2  375.66
  4924.4  373.25  4930.5  373.48  4939.3  371.55  4945.4  373.55  4970.1  374.01
  4996.2  373.32  4999.2  371.77  5004.7  371.77  5014.7  367.06  5015.0  366.56
  5018.7  367.06  5025.2  367.42  5031.2  370.13  5082.6  370.49  5112.0  372.55
  5206.6  371.55  5227.7  374.16  5255.0  373.98  5307.0  375.74  5533.5  376.19
#Mann=5,-1,0
  4640.7   0.125       0  4847.4   0.094       0  4970.1   0.063       0
  5014.7   0.063       0  5018.7   0.063       0
Bank Sta=5014.7,5018.7
Exp/Cntr=0.3,0.1

Type RM Length L Ch R = 1,2073,225,225,225
BEGIN DESCRIPTION:
Twin Creek1322072.04
END DESCRIPTION:
XS GIS Cut Line= 5
      2706382.70      6824855.20      2706213.34      6824950.92
      2706056.55      6825046.36      2705944.84      6825111.36
      2705706.28      6825228.03
#Sta/Elev= 30
  4625.6  377.40  4721.1  375.99  4832.2  373.41  4886.5  373.11  4942.6  372.73
  4957.5  370.75  4963.9  370.29  4969.8  366.41  4977.4  366.31  4977.7  365.81
  4981.2  365.81  4981.4  366.31  4985.3  369.60  4992.6  371.21  5003.3  371.89
  5043.8  371.30  5073.7  372.49  5081.0  371.87  5086.8  372.13  5118.3  371.88
  5124.0  372.30  5140.4  372.12  5145.9  372.61  5162.9  372.37  5258.5  373.99
  5320.5  374.31  5332.0  374.82  5343.0  374.76  5348.5  375.27  5398.5  375.49
#Mann=5,-1,0
  4625.6   0.125       0  4721.1   0.094       0  4886.5   0.063       0
  4977.4   0.063       0  4981.4   0.063       0
Bank Sta=4977.4,4981.4
Exp/Cntr=0.3,0.1

Type RM Length L Ch R = 1,1848,257,257,257
BEGIN DESCRIPTION:
Twin Creek1321847.84
END DESCRIPTION:
XS GIS Cut Line= 3
      2706087.17      6824670.36      2705925.45      6824897.91
      2705764.00      6825056.96
#Sta/Elev= 30
  4722.0  372.79  4787.3  371.89  4823.0  371.99  4867.3  369.99  4885.4  369.89
  4930.0  368.99  4953.4  369.19  4989.1  368.43  4995.2  367.58  5004.3  367.37
  5008.0  364.44  5008.3  363.94  5011.8  363.94  5012.0  364.44  5024.2  365.04
  5031.2  366.26  5038.3  368.52  5045.4  368.84  5059.5  371.22  5066.6  370.94
  5094.9  372.32  5116.1  372.18  5151.5  373.09  5172.6  374.88  5179.8  374.60
  5186.8  376.34  5200.9  377.48  5208.1  378.62  5222.2  377.65  5227.8  374.36
#Mann=5,-1,0
  4722.0   0.094       0  4885.4   0.063       0  4930.0   0.035       0
  5008.0   0.035       0  5012.0   0.035       0
Bank Sta=5008,5012
Exp/Cntr=0.3,0.1

Type RM Length L Ch R = 1,1591,271,271,271
BEGIN DESCRIPTION:
Twin Creek1321590.69
END DESCRIPTION:
XS GIS Cut Line= 3
      2705892.39      6824538.44      2705834.18      6824674.78
      2705728.46      6824864.58
#Sta/Elev= 30
  4857.8  371.77  4863.7  371.72  4887.3  370.51  4893.2  370.52  4916.3  369.57
  4939.9  369.09  4947.6  368.59  4958.1  367.09  4963.5  365.47  4967.3  364.83
  4967.6  364.33  4971.1  364.33  4971.3  364.83  4987.2  366.83  4992.6  366.60
  5006.0  366.77  5024.6  367.50  5031.7  367.31  5037.5  367.89  5059.2  368.01
  5075.2  368.81  5096.9  368.07  5104.7  368.38  5112.9  369.34  5118.6  368.49
  5140.3  368.61  5172.3  369.41  5178.1  369.26  5215.8  370.60  5223.3  370.55
#Mann=3,-1,0
  4857.8   0.035       0  4967.3   0.035       0  4971.3   0.035       0
Bank Sta=4967.3,4971.3
Exp/Cntr=0.3,0.1

Type RM Length L Ch R = 1,1320,263,263,263
BEGIN DESCRIPTION:
Twin Creek1321319.57
END DESCRIPTION:
XS GIS Cut Line= 3
      2705643.97      6824410.69      2705622.65      6824669.97
      2705600.95      6824850.81
#Sta/Elev= 30
  4748.0  370.50  4783.9  370.00  4798.5  369.65  4818.5  369.82  4828.6  369.38
  4838.6  369.48  4858.7  368.60  4878.8  368.44  4905.0  367.40  4910.1  366.83
  4918.9  364.48  4967.1  364.18  4967.3  363.68  4970.8  363.68  4971.1  364.18
  4971.5  364.19  4979.1  364.33  4989.1  364.21  5011.2  364.42  5018.1  365.67
  5023.1  366.33  5029.3  367.50  5039.4  368.29  5069.6  369.29  5099.8  370.01
  5120.0  369.93  5140.1  370.12  5160.3  370.96  5180.4  371.13  5190.3  371.43
#Mann=5,-1,0
  4748.0   0.035       0  4838.6   0.063       0  4967.1   0.035       0
  4971.1   0.063       0  4971.5   0.035       0
Bank Sta=4967.1,4971.1
Exp/Cntr=0.3,0.1

Type RM Length L Ch R = 1,1057,168,168,168
BEGIN DESCRIPTION:
Twin Creek1321056.72
END DESCRIPTION:
XS GIS Cut Line= 3
      2705517.29      6824358.46      2705425.73      6824507.04
      2705324.35      6824699.55
#Sta/Elev= 30
  4830.4  370.62  4846.7  370.03  4868.6  369.92  4892.1  368.82  4914.2  366.32
  4927.4  365.40  4950.8  364.95  4972.1  363.00  4978.0  359.09  4986.1  358.05
  4993.4  357.97  4999.3  357.13  5002.3  357.07  5002.6  356.57  5006.1  356.57
  5006.3  357.07  5020.7  357.50  5037.1  361.93  5043.3  363.06  5059.1  363.67
  5075.5  365.45  5081.2  366.37  5097.5  368.00  5103.2  368.03  5125.2  369.68
  5152.3  370.29  5191.3  370.82  5198.5  370.69  5207.7  370.69  5222.5  371.20
#Mann=5,-1,0
  4830.4   0.035       0  5002.3   0.035       0  5006.3   0.035       0
  5152.3   0.063       0  5198.5    0.05       0
Bank Sta=5002.3,5006.3
Exp/Cntr=0.3,0.1

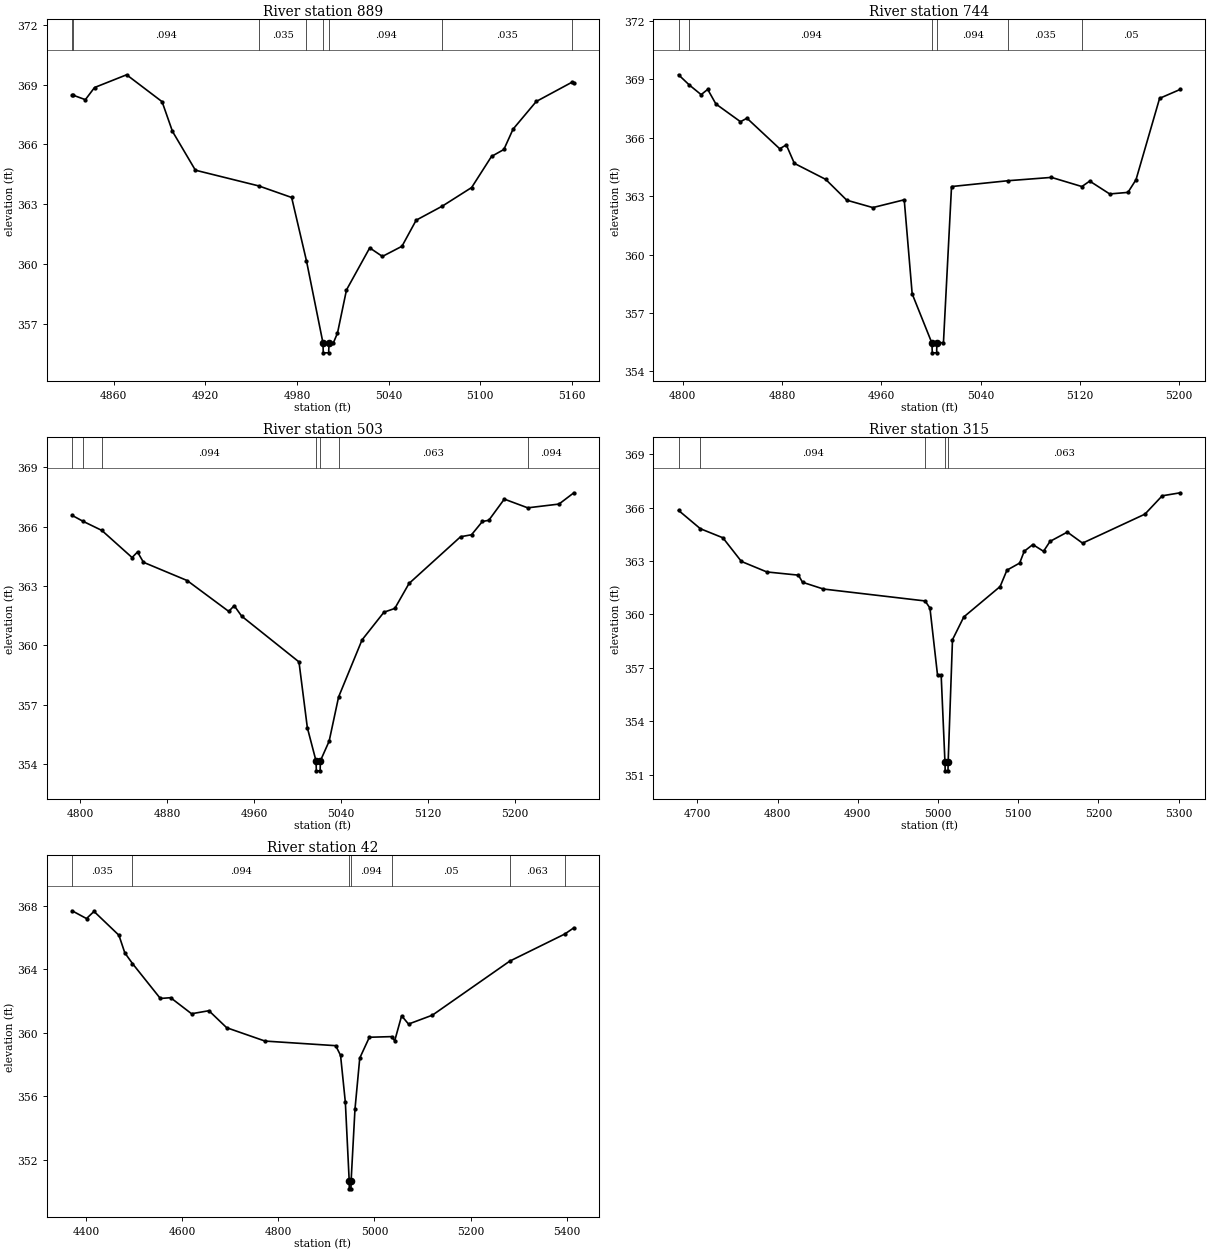
Type RM Length L Ch R = 1,889,145,145,145
BEGIN DESCRIPTION:
Mapping XS d4ceaec0
END DESCRIPTION:
XS GIS Cut Line= 3
      2705464.88      6824298.92      2705323.08      6824394.41
      2705190.63      6824479.53
#Sta/Elev= 30
  4832.8  368.47  4833.7  368.47  4841.5  368.25  4847.5  368.86  4868.5  369.50
  4891.7  368.15  4898.5  366.66  4913.5  364.71  4955.0  363.92  4976.5  363.34
  4986.2  360.16  4997.0  356.04  4997.2  355.54  5000.7  355.54  5001.0  356.04
  5003.8  356.04  5006.5  356.53  5012.4  358.70  5027.6  360.81  5035.9  360.38
  5048.7  360.89  5058.0  362.20  5075.2  362.91  5094.3  363.84  5107.3  365.40
  5115.4  365.75  5121.4  366.77  5136.6  368.16  5160.3  369.14  5161.2  369.10
#Mann=8,-1,0
  4832.8   0.035       0  4833.7   0.094       0  4955.0   0.035       0
  4986.2   0.094       0  4997.0    0.07       0  5001.0   0.094       0
  5075.2   0.035       0  5160.3    0.05       0
Bank Sta=4997,5001
Exp/Cntr=0.3,0.1

Type RM Length L Ch R = 1,744,241,241,241
BEGIN DESCRIPTION:
Twin Creek132744.38
END DESCRIPTION:
XS GIS Cut Line= 3
      2705474.57      6824199.05      2705276.91      6824264.67
      2705092.41      6824330.62
#Sta/Elev= 30
  4796.7  369.23  4805.3  368.71  4814.9  368.21  4820.2  368.48  4826.8  367.73
  4846.6  366.82  4851.8  367.00  4878.2  365.43  4883.5  365.63  4890.0  364.68
  4915.2  363.86  4932.2  362.79  4953.2  362.41  4978.5  362.81  4984.9  357.98
  5000.8  355.45  5001.1  354.95  5004.6  354.95  5004.8  355.45  5010.1  355.48
  5016.6  363.49  5062.2  363.79  5097.1  363.96  5121.6  363.49  5127.9  363.77
  5144.0  363.11  5158.7  363.19  5165.2  363.84  5184.2  368.02  5200.9  368.48
#Mann=6,-1,0
  4796.7   0.035       0  4805.3   0.094       0  5000.8    0.07       0
  5004.8   0.094       0  5062.2   0.035       0  5121.6    0.05       0
Bank Sta=5000.8,5004.8
Exp/Cntr=0.3,0.1

Type RM Length L Ch R = 1,503,188,188,188
BEGIN DESCRIPTION:
Twin Creek132503.16
END DESCRIPTION:
XS GIS Cut Line= 3
      2705481.32      6823999.17      2705273.59      6824023.02
      2705022.46      6824056.13
#Sta/Elev= 30
  4792.3  366.57  4802.4  366.27  4819.7  365.81  4847.6  364.44  4852.6  364.72
  4858.1  364.20  4898.3  363.28  4936.7  361.72  4941.7  362.01  4948.6  361.48
  5001.4  359.17  5009.1  355.85  5017.1  354.17  5017.4  353.67  5020.9  353.67
  5021.1  354.17  5029.2  355.17  5037.9  357.40  5059.5  360.28  5079.7  361.68
  5089.7  361.87  5102.8  363.13  5150.3  365.49  5160.4  365.59  5170.4  366.26
  5176.3  366.32  5190.6  367.39  5212.2  366.95  5241.0  367.14  5254.7  367.71
#Mann=7,-1,0
  4792.3   0.063       0  4802.4   0.035       0  4819.7   0.094       0
  5017.1    0.07       0  5021.1   0.094       0  5037.9   0.063       0
  5212.2   0.094       0
Bank Sta=5017.1,5021.1
Exp/Cntr=0.3,0.1

Type RM Length L Ch R = 1,315,273,273,273
BEGIN DESCRIPTION:
Mapping XS 5059c671
END DESCRIPTION:
XS GIS Cut Line= 3
      2705542.65      6823917.98      2705222.28      6823850.08
      2704944.98      6823959.79
#Sta/Elev= 30
  4676.4  365.85  4703.6  364.82  4731.7  364.31  4754.8  362.98  4786.5  362.39
  4825.9  362.21  4831.0  361.81  4857.0  361.43  4983.8  360.76  4989.9  360.36
  4999.4  356.57  5003.9  356.57  5008.6  351.71  5008.9  351.21  5012.4  351.21
  5012.6  351.71  5018.0  358.58  5032.1  359.86  5077.4  361.57  5085.9  362.49
  5101.8  362.89  5107.4  363.55  5118.2  363.93  5131.5  363.55  5139.7  364.11
  5161.2  364.63  5180.2  364.01  5258.0  365.64  5279.5  366.67  5302.1  366.84
#Mann=5,-1,0
  4676.4   0.035       0  4703.6   0.094       0  4983.8   0.063       0
  5008.6   0.063       0  5012.6   0.063       0
Bank Sta=5008.6,5012.6
Exp/Cntr=0.3,0.1

Type RM Length L Ch R = 1,42,0,0,0
BEGIN DESCRIPTION:
Twin Creek13241.784
END DESCRIPTION:
XS GIS Cut Line= 4
      2705659.78      6823909.71      2705201.00      6823636.00
      2705105.34      6823640.75      2704847.42      6823966.25
#Sta/Elev= 30
  4370.0  367.67  4400.1  367.18  4415.7  367.63  4467.6  366.13  4479.9  365.02
  4495.8  364.35  4553.9  362.15  4575.3  362.20  4618.9  361.19  4655.1  361.38
  4692.1  360.31  4771.9  359.47  4919.2  359.18  4929.3  358.57  4939.3  355.61
  4947.3  350.67  4947.5  350.17  4951.0  350.17  4951.3  350.67  4959.3  355.17
  4969.3  358.40  4989.3  359.71  5035.5  359.75  5042.1  359.49  5056.5  361.06
  5070.9  360.54  5120.6  361.10  5281.7  364.50  5396.6  366.21  5415.3  366.60
#Mann=7,-1,0
  4370.0   0.035       0  4495.8   0.094       0  4947.3    0.07       0
  4951.3   0.094       0  5035.5    0.05       0  5281.7   0.063       0
  5396.6    0.05       0
Bank Sta=4947.3,4951.3
Exp/Cntr=0.3,0.1

Chan Stop Cuts=-1