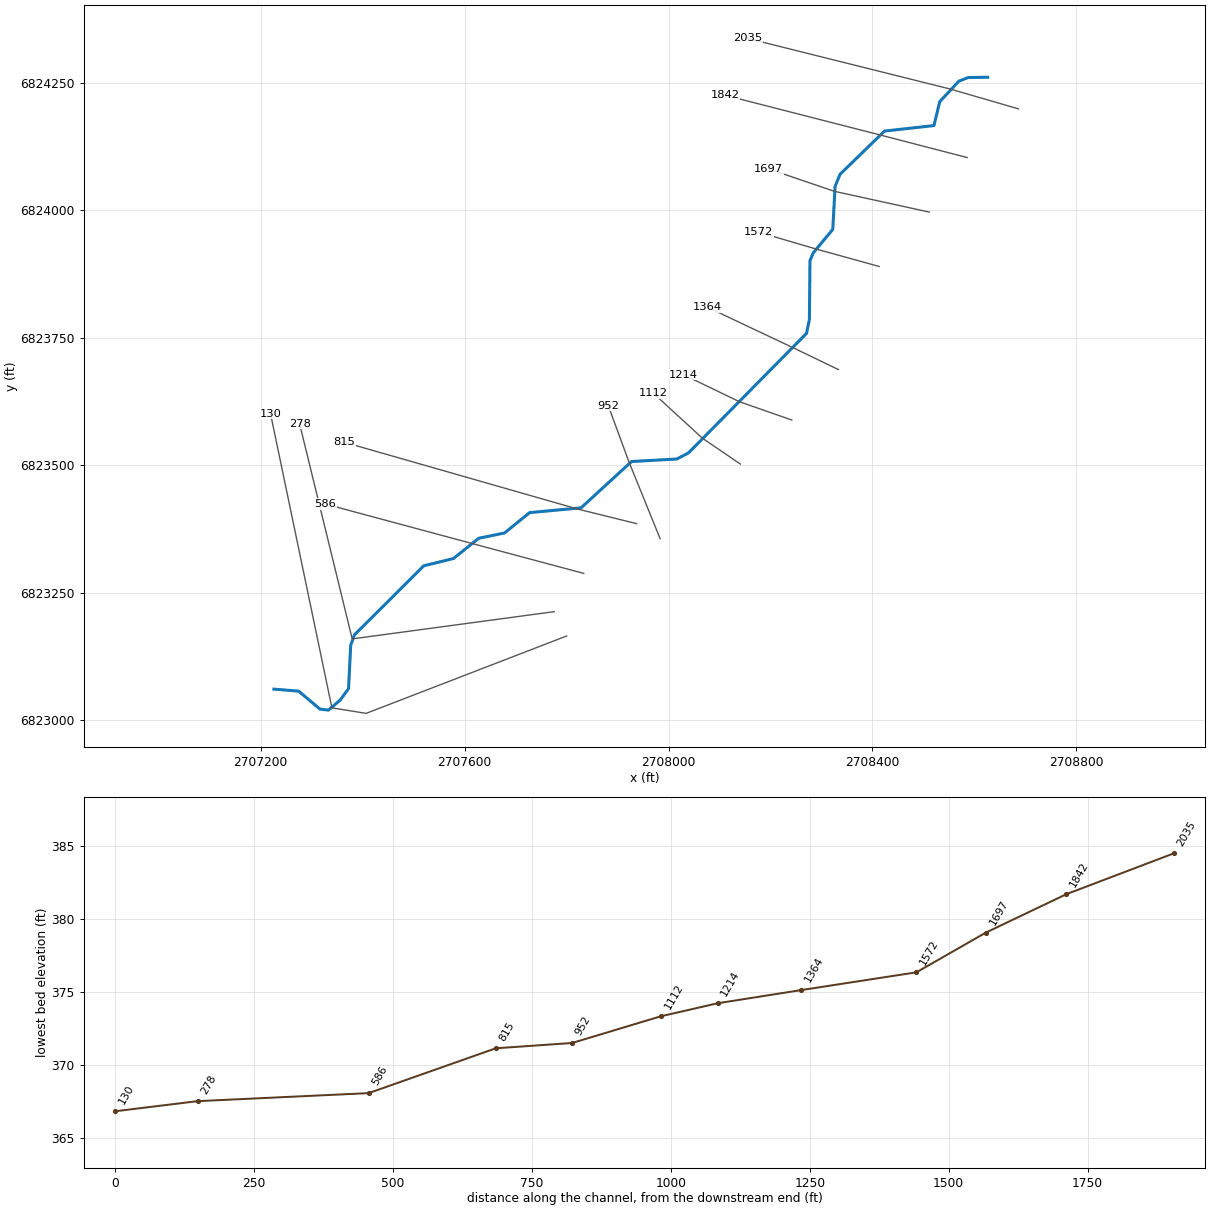
--- Twin Creek134.prj (project) ---

Proj Title=Twin Creek134 Base Level Engineering
Current Plan=p01
Default Exp/Contr=0.3,0.1
English Units
Geom File=g01
Flow File=f01
Plan File=p01
BEGIN DESCRIPTION:
Twin Creek134
END DESCRIPTION:

--- Twin Creek134.p01 (plan) ---

Plan Title=Multiple Run
Short Identifier=Multiple
Geom File=g01
Flow File=f01
Subcritical Flow
K Sum by GR= 0
Std Step Tol= 0.01
Critical Tol= 0.01
Num of Std Step Trials= 20
Max Error Tol= 0.3
Flow Tol Ratio= 0.001
Split Flow NTrial= 30
Split Flow Tol= 0.02
Split Flow Ratio= 0.02
Log Output Level= 0
Friction Slope Method= 1
Unsteady Friction Slope Method= 2
Unsteady Bridges Friction Slope Method= 1
Parabolic Critical Depth
Global Vel Dist=  1 , 1 , 1
Global Log Level= 0
CheckData=True
Encroach Param= -1, 0, 0, 0
BEGIN DESCRIPTION:
Multiple Run
END DESCRIPTION:

--- Twin Creek134.f01 (steady flow) ---

Flow Title=Multiple
Number of Profiles=7
Profile Names=10-year,25-year,50-year,1pct_min,100-year,1pct_plu,500-year
River Rch & RM= Twin Creek134,Reach-1,2035
     109     129     143      79     159     316     193
Boundary for River Rch & Prof#=Twin Creek134,Reach-1,1
Up Type=0
Dn Type=3
Dn Slope=0.005
Boundary for River Rch & Prof#=Twin Creek134,Reach-1,2
Up Type=0
Dn Type=3
Dn Slope=0.005
Boundary for River Rch & Prof#=Twin Creek134,Reach-1,3
Up Type=0
Dn Type=3
Dn Slope=0.005
Boundary for River Rch & Prof#=Twin Creek134,Reach-1,4
Up Type=0
Dn Type=3
Dn Slope=0.005
Boundary for River Rch & Prof#=Twin Creek134,Reach-1,5
Up Type=0
Dn Type=3
Dn Slope=0.005
Boundary for River Rch & Prof#=Twin Creek134,Reach-1,6
Up Type=0
Dn Type=3
Dn Slope=0.005
Boundary for River Rch & Prof#=Twin Creek134,Reach-1,7
Up Type=0
Dn Type=3
Dn Slope=0.005

--- Twin Creek134.g01 (geometry) ---

Geom Title=Existing Conditions

River Reach=Twin Creek134,Reach-1
Reach XY= 30
      2708626.00      6824261.00      2708587.63      6824260.47
      2708569.40      6824253.34      2708531.89      6824213.07
      2708520.55      6824166.25      2708423.62      6824155.46
      2708336.51      6824070.81      2708326.66      6824047.09
      2708322.14      6823962.60      2708284.14      6823917.06
      2708277.39      6823901.33      2708276.27      6823785.89
      2708270.53      6823758.55      2708039.30      6823524.40
      2708016.36      6823512.32      2707927.50      6823507.37
      2707828.42      6823416.54      2707727.59      6823407.17
      2707678.18      6823367.12      2707627.72      6823356.84
      2707578.19      6823317.10      2707519.94      6823302.86
      2707383.86      6823167.17      2707376.67      6823147.07
      2707372.40      6823062.02      2707356.41      6823039.90
      2707333.06      6823019.83      2707316.27      6823021.82
      2707274.66      6823056.97      2707226.00      6823061.00

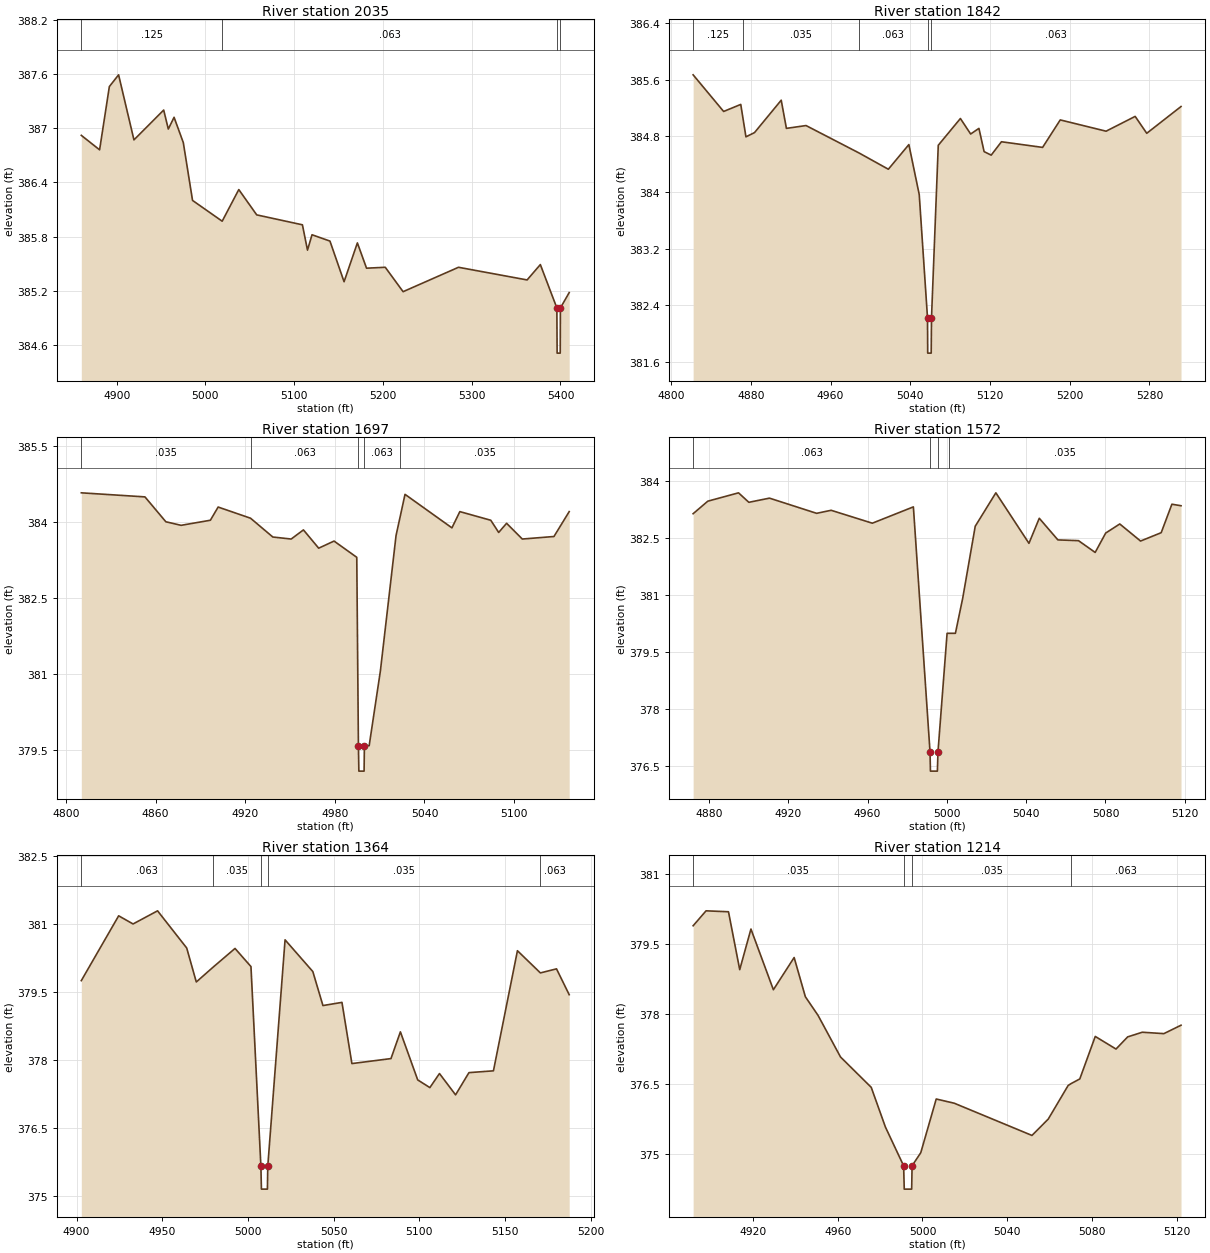
Type RM Length L Ch R = 1,2035,193,193,193
BEGIN DESCRIPTION:
Twin Creek1342034.655
END DESCRIPTION:
XS GIS Cut Line= 3
      2708686.32      6824198.97      2708552.08      6824238.01
      2708154.50      6824337.34
#Sta/Elev= 30
  4860.2  386.92  4880.8  386.76  4891.8  387.46  4902.2  387.59  4919.5  386.87
  4953.0  387.20  4958.2  386.99  4964.7  387.12  4975.1  386.84  4985.5  386.20
  5018.9  385.97  5037.6  386.32  5057.8  386.04  5109.3  385.93  5115.0  385.65
  5120.1  385.82  5140.3  385.75  5156.2  385.30  5171.2  385.73  5181.5  385.45
  5202.6  385.46  5222.7  385.19  5285.1  385.46  5362.4  385.32  5377.3  385.49
  5395.9  385.01  5396.2  384.51  5399.7  384.51  5399.9  385.01  5409.8  385.18
#Mann=4,-1,0
  4860.2   0.125       0  5018.9   0.063       0  5395.9    0.07       0
  5399.9   0.063       0
Bank Sta=5395.9,5399.9
Exp/Cntr=0.3,0.1

Type RM Length L Ch R = 1,1842,145,145,145
BEGIN DESCRIPTION:
Twin Creek1341842.31
END DESCRIPTION:
XS GIS Cut Line= 3
      2708585.65      6824103.58      2708412.82      6824148.36
      2708111.48      6824225.53
#Sta/Elev= 30
  4822.1  385.67  4852.7  385.15  4869.9  385.25  4872.6  385.01  4875.1  384.79
  4883.7  384.85  4910.5  385.31  4915.7  384.91  4935.4  384.95  4988.7  384.56
  5018.0  384.33  5038.6  384.68  5049.0  383.97  5057.3  382.22  5057.5  381.72
  5061.0  381.72  5061.3  382.22  5068.1  384.67  5090.3  385.05  5100.6  384.83
  5108.9  384.91  5114.1  384.58  5121.2  384.53  5131.5  384.72  5172.8  384.64
  5190.5  385.03  5236.5  384.87  5265.7  385.08  5277.3  384.84  5311.7  385.22
#Mann=5,-1,0
  4822.1   0.125       0  4872.6   0.035       0  4988.7   0.063       0
  5057.3   0.063       0  5061.3   0.063       0
Bank Sta=5057.3,5061.3
Exp/Cntr=0.3,0.1

Type RM Length L Ch R = 1,1697,125,125,125
BEGIN DESCRIPTION:
Twin Creek1341697.13
END DESCRIPTION:
XS GIS Cut Line= 3
      2708511.26      6823996.58      2708325.16      6824037.36
      2708196.31      6824081.17
#Sta/Elev= 30
  4810.3  384.57  4852.9  384.49  4866.9  384.00  4877.1  383.93  4896.7  384.03
  4901.9  384.29  4923.6  384.07  4938.5  383.70  4950.8  383.66  4959.0  383.84
  4969.2  383.48  4979.5  383.62  4994.7  383.30  4995.8  379.59  4996.1  379.09
  4999.6  379.09  4999.8  379.59  5003.0  379.59  5010.5  381.06  5021.0  383.73
  5023.6  384.08  5027.0  384.54  5058.4  383.88  5063.7  384.20  5084.4  384.03
  5089.7  383.79  5095.0  383.97  5105.5  383.66  5126.7  383.71  5136.9  384.20
#Mann=5,-1,0
  4810.3   0.035       0  4923.6   0.063       0  4995.8   0.063       0
  4999.8   0.063       0  5023.6   0.035       0
Bank Sta=4995.8,4999.8
Exp/Cntr=0.3,0.1

Type RM Length L Ch R = 1,1572,208,208,208
BEGIN DESCRIPTION:
Twin Creek1341571.53
END DESCRIPTION:
XS GIS Cut Line= 3
      2708413.09      6823889.92      2708288.21      6823924.49
      2708176.38      6823957.25
#Sta/Elev= 30
  4872.0  383.15  4879.4  383.48  4894.9  383.70  4900.1  383.45  4910.5  383.56
  4934.3  383.16  4941.6  383.24  4962.4  382.90  4983.1  383.33  4991.5  376.87
  4991.7  376.37  4995.2  376.37  4995.5  376.87  5000.1  380.00  5001.0  380.00
  5004.3  380.00  5008.0  380.93  5014.3  382.82  5024.7  383.70  5041.4  382.37
  5046.6  383.03  5056.0  382.46  5066.4  382.44  5074.8  382.13  5080.1  382.64
  5087.2  382.88  5097.7  382.43  5108.1  382.65  5113.5  383.40  5118.1  383.36
#Mann=4,-1,0
  4872.0   0.063       0  4991.5   0.063       0  4995.5   0.063       0
  5001.0   0.035       0
Bank Sta=4991.5,4995.5
Exp/Cntr=0.3,0.1

Type RM Length L Ch R = 1,1364,150,150,150
BEGIN DESCRIPTION:
Twin Creek1341363.5
END DESCRIPTION:
XS GIS Cut Line= 3
      2708333.16      6823687.71      2708243.97      6823730.72
      2708076.07      6823810.01
#Sta/Elev= 30
  4902.8  379.75  4924.6  381.18  4933.0  381.00  4947.3  381.29  4964.3  380.47
  4969.9  379.72  4979.8  380.05  4992.5  380.46  5001.8  380.06  5007.6  375.65
  5007.9  375.15  5011.4  375.15  5011.6  375.65  5021.7  380.65  5037.9  379.95
  5043.8  379.20  5054.9  379.27  5060.7  377.92  5083.5  378.03  5089.0  378.62
  5099.1  377.56  5106.2  377.39  5111.8  377.70  5121.2  377.23  5129.0  377.72
  5143.3  377.76  5157.3  380.41  5170.7  379.92  5180.1  380.01  5187.5  379.44
#Mann=5,-1,0
  4902.8   0.063       0  4979.8   0.035       0  5007.6   0.035       0
  5011.6   0.035       0  5170.7   0.063       0
Bank Sta=5007.6,5011.6
Exp/Cntr=0.3,0.1

Type RM Length L Ch R = 1,1214,102,102,102
BEGIN DESCRIPTION:
Twin Creek1341213.92
END DESCRIPTION:
XS GIS Cut Line= 3
      2708241.74      6823588.72      2708139.50      6823624.49
      2708029.53      6823677.51
#Sta/Elev= 30
  4891.7  379.89  4897.8  380.21  4908.4  380.19  4913.7  378.95  4919.0  379.82
  4929.6  378.52  4939.4  379.21  4944.7  378.37  4950.7  377.97  4961.3  377.08
  4975.8  376.43  4982.5  375.58  4991.1  374.75  4991.4  374.25  4994.9  374.25
  4995.1  374.75  4999.2  375.03  5006.5  376.18  5015.0  376.09  5051.7  375.40
  5059.4  375.75  5068.8  376.47  5070.2  376.51  5074.3  376.61  5081.6  377.52
  5091.4  377.25  5096.9  377.51  5103.8  377.61  5114.0  377.58  5122.1  377.76
#Mann=4,-1,0
  4891.7   0.035       0  4991.1   0.035       0  4995.1   0.035       0
  5070.2   0.063       0
Bank Sta=4991.1,4995.1
Exp/Cntr=0.3,0.1

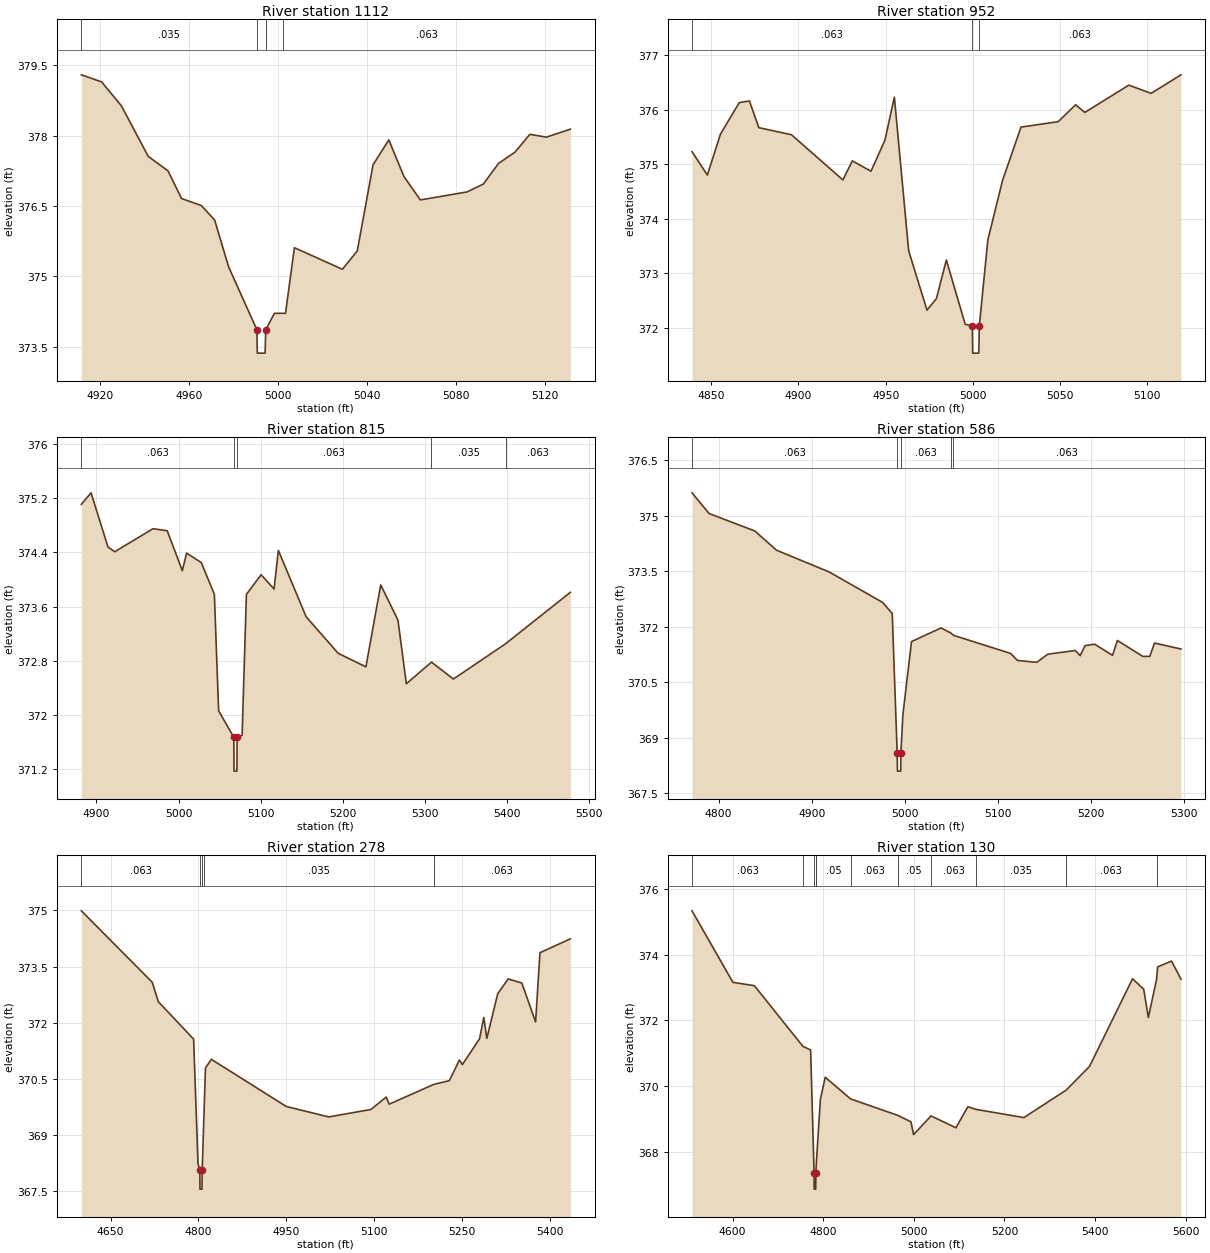
Type RM Length L Ch R = 1,1112,160,160,160
BEGIN DESCRIPTION:
Twin Creek1341112
END DESCRIPTION:
XS GIS Cut Line= 3
      2708140.85      6823502.41      2708066.91      6823552.70
      2707970.56      6823640.98
#Sta/Elev= 30
  4911.5  379.30  4920.6  379.15  4929.5  378.64  4941.6  377.56  4950.5  377.25
  4956.6  376.66  4965.5  376.51  4971.5  376.20  4977.8  375.20  4990.5  373.86
  4990.7  373.36  4994.2  373.36  4994.5  373.86  4998.4  374.21  5002.2  374.21
  5003.4  374.21  5007.4  375.61  5029.0  375.15  5035.7  375.54  5042.8  377.38
  5049.9  377.91  5056.7  377.13  5064.1  376.63  5085.1  376.80  5092.5  376.97
  5099.3  377.41  5106.7  377.65  5113.4  378.03  5120.8  377.97  5131.6  378.14
#Mann=4,-1,0
  4911.5   0.035       0  4990.5   0.035       0  4994.5   0.035       0
  5002.2   0.063       0
Bank Sta=4990.5,4994.5
Exp/Cntr=0.3,0.1

Type RM Length L Ch R = 1,952,137,137,137
BEGIN DESCRIPTION:
Twin Creek134951.56
END DESCRIPTION:
XS GIS Cut Line= 3
      2707983.54      6823355.92      2707922.13      6823507.26
      2707881.75      6823617.04
#Sta/Elev= 30
  4839.0  375.23  4847.8  374.80  4855.3  375.55  4866.1  376.13  4871.9  376.16
  4877.3  375.67  4896.0  375.54  4925.5  374.71  4930.9  375.06  4941.6  374.87
  4949.6  375.44  4955.0  376.23  4963.2  373.41  4973.7  372.32  4979.1  372.53
  4984.8  373.24  4995.6  372.06  4999.7  372.03  4999.9  371.53  5003.4  371.53
  5003.7  372.03  5008.6  373.61  5017.0  374.70  5027.6  375.68  5048.9  375.78
  5058.9  376.09  5064.2  375.95  5089.4  376.45  5102.2  376.30  5119.3  376.64
#Mann=3,-1,0
  4839.0   0.063       0  4999.7   0.063       0  5003.7   0.063       0
Bank Sta=4999.7,5003.7
Exp/Cntr=0.3,0.1

Type RM Length L Ch R = 1,815,229,229,229
BEGIN DESCRIPTION:
Twin Creek134815.26
END DESCRIPTION:
XS GIS Cut Line= 3
      2707937.44      6823385.51      2707822.10      6823414.06
      2707364.10      6823545.12
#Sta/Elev= 30
  4881.6  375.11  4893.4  375.28  4914.0  374.48  4922.2  374.41  4968.8  374.75
  4986.1  374.72  5004.5  374.13  5009.7  374.39  5027.6  374.25  5043.5  373.78
  5048.7  372.06  5067.2  371.67  5067.4  371.17  5070.9  371.17  5071.2  371.67
  5077.3  371.70  5082.5  373.78  5100.4  374.07  5116.2  373.86  5121.4  374.43
  5155.2  373.45  5194.2  372.91  5228.0  372.71  5246.0  373.92  5267.0  373.40
  5277.2  372.46  5307.8  372.78  5334.5  372.53  5397.9  373.05  5476.8  373.81
#Mann=5,-1,0
  4881.6   0.063       0  5067.2   0.063       0  5071.2   0.063       0
  5307.8   0.035       0  5397.9   0.063       0
Bank Sta=5067.2,5071.2
Exp/Cntr=0.3,0.1

Type RM Length L Ch R = 1,586,308,308,308
BEGIN DESCRIPTION:
Twin Creek134586.104
END DESCRIPTION:
XS GIS Cut Line= 3
      2707833.76      6823287.92      2707612.93      6823347.03
      2707326.42      6823424.12
#Sta/Elev= 30
  4771.4  375.62  4789.8  375.06  4838.8  374.59  4862.2  374.07  4918.9  373.48
  4976.1  372.66  4986.5  372.36  4991.8  368.60  4992.1  368.10  4995.6  368.10
  4995.8  368.60  4998.0  369.63  5007.2  371.60  5039.0  371.97  5049.6  371.83
  5052.3  371.77  5113.7  371.28  5121.1  371.09  5141.8  371.04  5153.7  371.26
  5183.2  371.36  5188.4  371.22  5193.6  371.49  5203.9  371.53  5223.2  371.23
  5228.4  371.63  5255.7  371.20  5263.2  371.20  5268.3  371.56  5296.7  371.40
#Mann=5,-1,0
  4771.4   0.063       0  4991.8   0.063       0  4995.8   0.063       0
  5049.6   0.035       0  5052.3   0.063       0
Bank Sta=4991.8,4995.8
Exp/Cntr=0.3,0.1

Type RM Length L Ch R = 1,278,148,148,148
BEGIN DESCRIPTION:
Twin Creek134278.376
END DESCRIPTION:
XS GIS Cut Line= 3
      2707775.83      6823212.92      2707379.61      6823159.50
      2707276.42      6823581.36
#Sta/Elev= 30
  4600.2  374.99  4721.1  373.08  4731.5  372.56  4791.7  371.56  4799.2  368.23
  4802.3  368.05  4802.5  367.55  4806.0  367.55  4806.3  368.05  4808.6  369.18
  4811.9  370.79  4822.0  371.02  4949.7  369.76  5022.1  369.48  5094.2  369.68
  5120.2  370.01  5125.3  369.82  5201.4  370.35  5228.0  370.45  5245.1  371.00
  5250.2  370.88  5279.5  371.57  5286.7  372.14  5291.9  371.58  5310.4  372.77
  5328.3  373.17  5351.6  373.06  5375.1  372.02  5382.5  373.87  5434.3  374.24
#Mann=5,-1,0
  4600.2   0.063       0  4802.3   0.035       0  4806.3   0.063       0
  4808.6   0.035       0  5201.4   0.063       0
Bank Sta=4802.3,4806.3
Exp/Cntr=0.3,0.1

Type RM Length L Ch R = 1,130,0,0,0
BEGIN DESCRIPTION:
Twin Creek134129.841
END DESCRIPTION:
XS GIS Cut Line= 4
      2707800.25      6823165.24      2707406.90      6823013.42
      2707339.81      6823024.28      2707219.32      6823601.43
#Sta/Elev= 30
  4510.4  375.34  4600.7  373.16  4648.0  373.06  4755.2  371.21  4772.2  371.10
  4779.8  367.36  4780.0  366.86  4783.5  366.86  4783.8  367.36  4784.8  367.65
  4793.7  369.59  4804.4  370.27  4860.3  369.61  4964.0  369.11  4993.7  368.91
  4999.4  368.52  5037.9  369.09  5092.9  368.73  5119.2  369.37  5137.4  369.29
  5242.9  369.04  5336.5  369.88  5387.8  370.60  5482.7  373.27  5507.4  372.95
  5517.6  372.09  5535.6  373.24  5538.1  373.63  5568.7  373.81  5589.6  373.26
#Mann=11,-1,0
  4510.4   0.063       0  4755.2   0.035       0  4779.8    0.05       0
  4783.8   0.035       0  4784.8    0.05       0  4860.3   0.063       0
  4964.0    0.05       0  5037.9   0.063       0  5137.4   0.035       0
  5336.5   0.063       0  5535.6   0.094       0
Bank Sta=4779.8,4783.8
Exp/Cntr=0.3,0.1

Chan Stop Cuts=-1