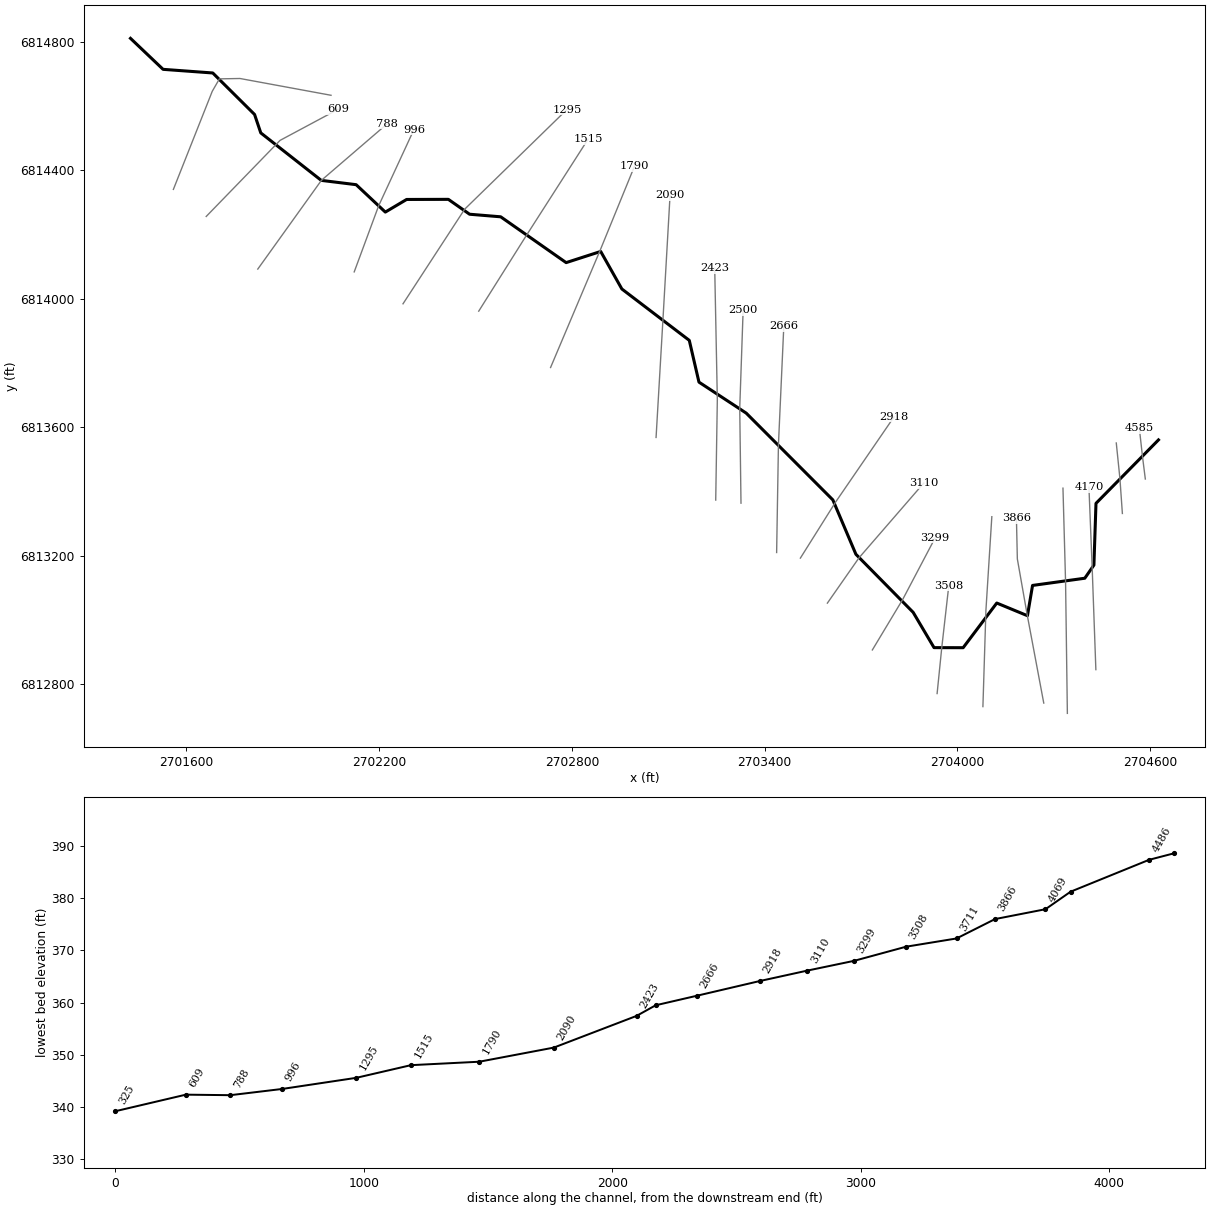
--- Twin Creek136.prj (project) ---

Proj Title=Twin Creek136 Base Level Engineering
Current Plan=p01
Default Exp/Contr=0.3,0.1
English Units
Geom File=g01
Flow File=f01
Plan File=p01
BEGIN DESCRIPTION:
Twin Creek136
END DESCRIPTION:

--- Twin Creek136.p01 (plan) ---

Plan Title=Multiple Run
Short Identifier=Multiple
Geom File=g01
Flow File=f01
Subcritical Flow
K Sum by GR= 0
Std Step Tol= 0.01
Critical Tol= 0.01
Num of Std Step Trials= 20
Max Error Tol= 0.3
Flow Tol Ratio= 0.001
Split Flow NTrial= 30
Split Flow Tol= 0.02
Split Flow Ratio= 0.02
Log Output Level= 0
Friction Slope Method= 1
Unsteady Friction Slope Method= 2
Unsteady Bridges Friction Slope Method= 1
Parabolic Critical Depth
Global Vel Dist=  1 , 1 , 1
Global Log Level= 0
CheckData=True
Encroach Param= -1, 0, 0, 0
BEGIN DESCRIPTION:
Multiple Run
END DESCRIPTION:

--- Twin Creek136.f01 (steady flow) ---

Flow Title=Multiple
Number of Profiles=7
Profile Names=10-year,25-year,50-year,1pct_min,100-year,1pct_plu,500-year
River Rch & RM= Twin Creek136,Reach-1,4585
     206     258     296     170     339     677     442
Boundary for River Rch & Prof#=Twin Creek136,Reach-1,1
Up Type=0
Dn Type=3
Dn Slope=0.005
Boundary for River Rch & Prof#=Twin Creek136,Reach-1,2
Up Type=0
Dn Type=3
Dn Slope=0.005
Boundary for River Rch & Prof#=Twin Creek136,Reach-1,3
Up Type=0
Dn Type=3
Dn Slope=0.005
Boundary for River Rch & Prof#=Twin Creek136,Reach-1,4
Up Type=0
Dn Type=3
Dn Slope=0.005
Boundary for River Rch & Prof#=Twin Creek136,Reach-1,5
Up Type=0
Dn Type=3
Dn Slope=0.005
Boundary for River Rch & Prof#=Twin Creek136,Reach-1,6
Up Type=0
Dn Type=3
Dn Slope=0.005
Boundary for River Rch & Prof#=Twin Creek136,Reach-1,7
Up Type=0
Dn Type=3
Dn Slope=0.005

--- Twin Creek136.g01 (geometry) ---

Geom Title=Existing Conditions

River Reach=Twin Creek136,Reach-1
Reach XY= 30
      2704626.00      6813561.00      2704431.46      6813363.45
      2704425.02      6813171.26      2704396.65      6813130.40
      2704234.00      6813107.99      2704218.10      6813013.76
      2704122.60      6813053.17      2704017.95      6812914.14
      2703927.35      6812914.34      2703862.36      6813024.20
      2703684.14      6813204.94      2703612.38      6813374.21
      2703342.67      6813644.35      2703195.61      6813740.80
      2703165.49      6813870.81      2702955.58      6814030.78
      2702889.73      6814147.60      2702782.13      6814112.84
      2702578.42      6814255.46      2702481.57      6814263.47
      2702415.49      6814309.80      2702285.59      6814309.46
      2702219.27      6814270.15      2702128.43      6814355.45
      2702019.83      6814368.86      2701831.62      6814516.62
      2701812.28      6814573.98      2701682.19      6814703.18
      2701527.45      6814714.49      2701426.00      6814811.00

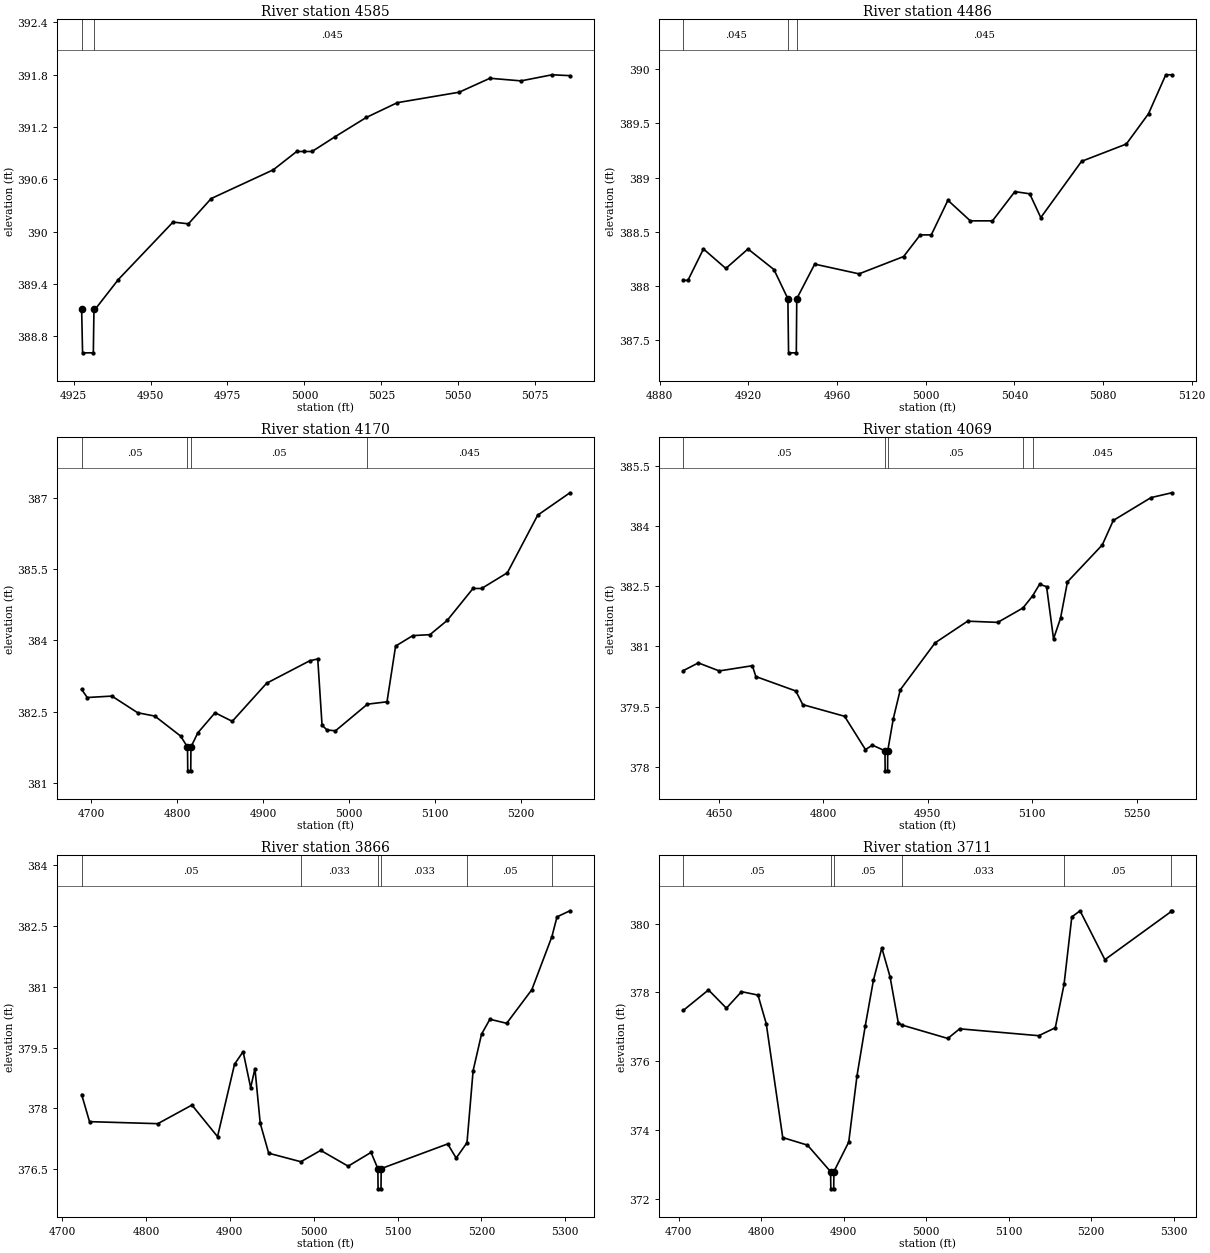
Type RM Length L Ch R = 1,4585,99,99,99
BEGIN DESCRIPTION:
Twin Creek1364584.789
END DESCRIPTION:
XS GIS Cut Line= 3
      2704585.05      6813439.19      2704576.00      6813511.00
      2704566.47      6813596.80
#Sta/Elev= 21
  4927.6  389.11  4927.9  388.61  4931.4  388.61  4931.6  389.11  4932.0  389.11
  4939.5  389.45  4957.3  390.11  4962.3  390.09  4969.7  390.38  4989.9  390.71
  4997.5  390.92  5000.0  390.92  5002.5  390.92  5010.0  391.09  5020.1  391.31
  5030.2  391.48  5050.3  391.60  5060.3  391.76  5070.4  391.73  5080.5  391.80
  5086.3  391.79
#Mann=2,-1,0
  4927.6   0.045       0  4931.6   0.045       0
Bank Sta=4927.6,4931.6
Exp/Cntr=0.3,0.1

Type RM Length L Ch R = 1,4486,316,316,316
BEGIN DESCRIPTION:
Twin Creek1364485.76
END DESCRIPTION:
XS GIS Cut Line= 3
      2704513.62      6813331.99      2704505.95      6813441.02
      2704494.63      6813551.44
#Sta/Elev= 26
  4890.7  388.05  4892.7  388.05  4899.7  388.34  4909.8  388.16  4919.8  388.34
  4931.5  388.15  4937.8  387.88  4938.1  387.38  4941.6  387.38  4941.8  387.88
  4949.9  388.20  4969.9  388.11  4990.0  388.27  4997.5  388.47  5002.5  388.47
  5010.0  388.79  5020.1  388.60  5030.1  388.60  5040.2  388.87  5046.9  388.85
  5051.9  388.63  5070.3  389.15  5090.5  389.31  5100.5  389.59  5108.3  389.95
  5111.0  389.95
#Mann=3,-1,0
  4890.7   0.045       0  4937.8   0.045       0  4941.8   0.045       0
Bank Sta=4937.8,4941.8
Exp/Cntr=0.3,0.1

Type RM Length L Ch R = 1,4170,101,101,101
BEGIN DESCRIPTION:
Twin Creek1364169.7
END DESCRIPTION:
XS GIS Cut Line= 3
      2704431.10      6812845.84      2704419.56      6813164.53
      2704409.50      6813413.72
#Sta/Elev= 30
  4688.7  382.97  4695.2  382.80  4723.9  382.83  4753.9  382.48  4773.9  382.41
  4803.9  381.99  4811.9  381.76  4812.2  381.26  4815.7  381.26  4815.9  381.76
  4824.0  382.06  4844.0  382.48  4864.0  382.30  4904.0  383.10  4954.0  383.57
  4963.5  383.61  4968.5  382.22  4974.1  382.12  4984.1  382.10  5021.3  382.66
  5044.1  382.71  5054.1  383.88  5074.1  384.10  5094.1  384.12  5114.2  384.42
  5144.2  385.09  5154.2  385.09  5184.2  385.42  5219.5  386.63  5257.0  387.10
#Mann=4,-1,0
  4688.7    0.05       0  4811.9    0.05       0  4815.9    0.05       0
  5021.3   0.045       0
Bank Sta=4811.9,4815.9
Exp/Cntr=0.3,0.1

Type RM Length L Ch R = 1,4069,203,203,203
BEGIN DESCRIPTION:
Twin Creek1364068.66
END DESCRIPTION:
XS GIS Cut Line= 3
      2704342.39      6812709.71      2704336.78      6813119.36
      2704328.69      6813410.76
#Sta/Elev= 30
  4599.1  380.40  4620.4  380.59  4650.4  380.39  4698.0  380.52  4703.0  380.25
  4760.4  379.89  4770.4  379.55  4830.4  379.26  4860.4  378.43  4870.4  378.54
  4888.4  378.40  4888.7  377.90  4892.2  377.90  4892.4  378.40  4900.4  379.20
  4910.4  379.92  4960.4  381.09  5007.1  381.63  5050.4  381.60  5086.7  381.96
  5100.4  382.26  5110.5  382.55  5120.5  382.49  5130.5  381.19  5140.5  381.70
  5150.5  382.61  5200.5  383.53  5216.3  384.14  5270.5  384.71  5300.3  384.83
#Mann=5,-1,0
  4599.1    0.05       0  4888.4   0.033       0  4892.4    0.05       0
  5086.7    0.05       0  5100.4   0.045       0
Bank Sta=4888.4,4892.4
Exp/Cntr=0.3,0.1

Type RM Length L Ch R = 1,3866,155,155,155
BEGIN DESCRIPTION:
Twin Creek1363866.26
END DESCRIPTION:
XS GIS Cut Line= 4
      2704268.88      6812741.80      2704217.05      6813017.93
      2704186.68      6813190.42      2704183.82      6813316.39
#Sta/Elev= 30
  4723.4  378.34  4732.8  377.67  4814.2  377.62  4854.9  378.08  4885.4  377.30
  4905.7  379.09  4915.9  379.40  4924.9  378.51  4930.0  378.98  4936.3  377.63
  4946.4  376.89  4984.7  376.68  5008.4  376.96  5041.1  376.57  5068.4  376.91
  5076.5  376.51  5076.8  376.01  5080.3  376.01  5080.5  376.51  5159.8  377.12
  5169.9  376.77  5182.8  377.15  5190.1  378.93  5200.1  379.83  5210.1  380.20
  5230.1  380.10  5260.1  380.93  5284.0  382.24  5290.1  382.73  5305.5  382.88
#Mann=6,-1,0
  4723.4    0.05       0  4984.7   0.033       0  5076.5   0.033       0
  5080.5   0.033       0  5182.8    0.05       0  5284.0   0.045       0
Bank Sta=5076.5,5080.5
Exp/Cntr=0.3,0.1

Type RM Length L Ch R = 1,3711,203,203,203
BEGIN DESCRIPTION:
Twin Creek1363711.2
END DESCRIPTION:
XS GIS Cut Line= 3
      2704079.48      6812730.76      2704088.85      6813030.61
      2704107.24      6813321.94
#Sta/Elev= 30
  4706.0  377.48  4736.3  378.07  4758.0  377.54  4776.3  378.02  4796.3  377.92
  4806.3  377.09  4826.3  373.78  4856.3  373.56  4884.3  372.79  4884.6  372.29
  4888.1  372.29  4888.3  372.79  4906.3  373.65  4916.3  375.57  4926.3  377.02
  4936.3  378.36  4946.4  379.29  4956.4  378.45  4966.4  377.11  4970.8  377.05
  5026.4  376.66  5040.8  376.94  5136.6  376.74  5156.7  376.97  5167.3  378.23
  5176.7  380.19  5186.7  380.37  5216.8  378.95  5297.3  380.35  5297.9  380.35
#Mann=6,-1,0
  4706.0    0.05       0  4884.3   0.033       0  4888.3    0.05       0
  4970.8   0.033       0  5167.3    0.05       0  5297.3   0.045       0
Bank Sta=4884.3,4888.3
Exp/Cntr=0.3,0.1

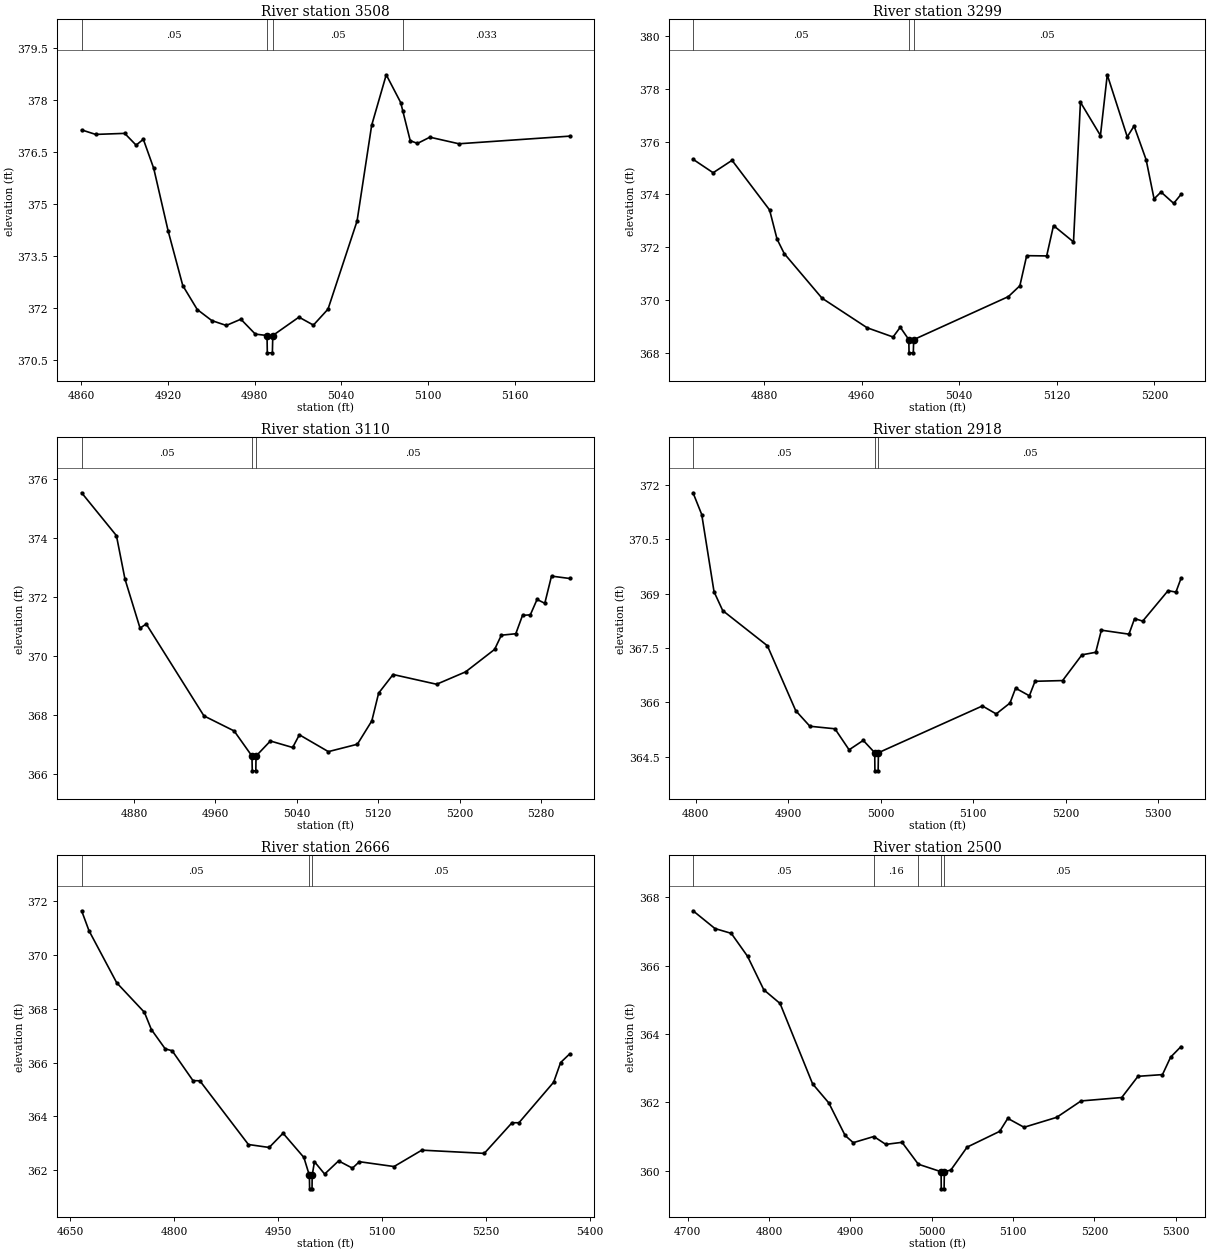
Type RM Length L Ch R = 1,3508,209,209,209
BEGIN DESCRIPTION:
Twin Creek1363507.77
END DESCRIPTION:
XS GIS Cut Line= 3
      2703936.91      6812771.40      2703951.33      6812913.78
      2703973.27      6813107.13
#Sta/Elev= 30
  4860.3  377.14  4870.0  377.01  4890.1  377.04  4898.0  376.70  4903.0  376.87
  4910.2  376.03  4920.2  374.22  4930.3  372.65  4940.3  371.96  4950.4  371.64
  4960.4  371.50  4970.5  371.68  4980.5  371.25  4988.6  371.21  4988.8  370.71
  4992.3  370.71  4992.6  371.21  5010.7  371.74  5020.7  371.51  5030.8  371.97
  5050.9  374.51  5061.0  377.27  5071.1  378.73  5081.1  377.93  5082.6  377.68
  5087.7  376.83  5092.7  376.75  5101.3  376.93  5121.4  376.74  5198.0  376.96
#Mann=4,-1,0
  4860.3    0.05       0  4988.6    0.05       0  4992.6    0.05       0
  5082.6   0.033       0
Bank Sta=4988.6,4992.6
Exp/Cntr=0.3,0.1

Type RM Length L Ch R = 1,3299,189,189,189
BEGIN DESCRIPTION:
Twin Creek1363299.39
END DESCRIPTION:
XS GIS Cut Line= 3
      2703735.36      6812907.16      2703830.28      6813065.16
      2703930.89      6813256.28
#Sta/Elev= 30
  4821.6  375.33  4838.1  374.82  4853.6  375.29  4884.4  373.41  4890.5  372.31
  4896.4  371.76  4927.4  370.07  4964.4  368.95  4985.7  368.60  4991.6  368.97
  4998.6  368.50  4998.8  368.00  5002.3  368.00  5002.6  368.50  5080.3  370.13
  5089.7  370.54  5095.3  371.68  5111.7  371.67  5117.3  372.82  5133.7  372.20
  5139.4  377.49  5155.8  376.23  5161.4  378.53  5177.8  376.18  5183.4  376.59
  5193.3  375.31  5199.8  373.83  5205.5  374.09  5215.9  373.66  5221.9  374.00
#Mann=3,-1,0
  4821.6    0.05       0  4998.6    0.05       0  5002.6    0.05       0
Bank Sta=4998.6,5002.6
Exp/Cntr=0.3,0.1

Type RM Length L Ch R = 1,3110,192,192,192
BEGIN DESCRIPTION:
Twin Creek1363110.46
END DESCRIPTION:
XS GIS Cut Line= 3
      2703595.33      6813052.92      2703693.58      6813193.67
      2703895.22      6813426.42
#Sta/Elev= 30
  4828.6  375.53  4862.8  374.08  4871.2  372.61  4886.0  370.95  4892.1  371.09
  4948.8  367.98  4978.5  367.47  4996.0  366.62  4996.3  366.12  4999.8  366.12
  5000.0  366.62  5014.1  367.13  5036.0  366.91  5042.6  367.34  5071.1  366.77
  5099.6  367.02  5113.8  367.81  5120.5  368.75  5134.7  369.38  5177.5  369.05
  5206.0  369.47  5234.5  370.23  5241.1  370.71  5255.3  370.76  5261.9  371.38
  5269.6  371.40  5276.2  371.92  5283.8  371.79  5290.4  372.71  5308.2  372.63
#Mann=3,-1,0
  4828.6    0.05       0  4996.0    0.05       0  5000.0    0.05       0
Bank Sta=4996,5000
Exp/Cntr=0.3,0.1

Type RM Length L Ch R = 1,2918,252,252,252
BEGIN DESCRIPTION:
Twin Creek1362917.62
END DESCRIPTION:
XS GIS Cut Line= 3
      2703511.29      6813193.02      2703620.55      6813366.92
      2703802.74      6813632.57
#Sta/Elev= 30
  4797.1  371.78  4806.5  371.18  4819.8  369.05  4829.2  368.53  4877.5  367.56
  4908.1  365.77  4923.4  365.34  4950.5  365.27  4965.8  364.69  4981.1  364.95
  4993.5  364.61  4993.7  364.11  4997.2  364.11  4997.5  364.61  5109.9  365.90
  5124.8  365.68  5139.7  365.98  5145.8  366.39  5160.7  366.18  5166.8  366.58
  5196.6  366.60  5217.5  367.31  5232.4  367.38  5238.5  367.99  5268.3  367.88
  5274.4  368.31  5283.2  368.24  5310.6  369.08  5319.1  369.04  5324.6  369.42
#Mann=3,-1,0
  4797.1    0.05       0  4993.5    0.05       0  4997.5    0.05       0
Bank Sta=4993.5,4997.5
Exp/Cntr=0.3,0.1

Type RM Length L Ch R = 1,2666,166,166,166
BEGIN DESCRIPTION:
Twin Creek1362666.05
END DESCRIPTION:
XS GIS Cut Line= 3
      2703437.37      6813210.43      2703442.99      6813546.47
      2703459.66      6813914.01
#Sta/Elev= 30
  4666.3  371.65  4676.9  370.91  4716.9  368.97  4756.9  367.87  4766.9  367.23
  4786.9  366.51  4796.9  366.44  4826.9  365.33  4836.9  365.32  4906.9  362.95
  4936.9  362.84  4956.9  363.37  4986.9  362.47  4994.9  361.80  4995.2  361.30
  4998.7  361.30  4998.9  361.80  5002.2  362.31  5016.9  361.85  5037.0  362.34
  5057.0  362.07  5067.0  362.31  5117.0  362.13  5157.1  362.74  5247.2  362.62
  5287.2  363.76  5297.2  363.76  5347.3  365.27  5357.3  366.00  5370.3  366.32
#Mann=3,-1,0
  4666.3    0.05       0  4994.9    0.05       0  4998.9    0.05       0
Bank Sta=4994.9,4998.9
Exp/Cntr=0.3,0.1

Type RM Length L Ch R = 1,2500,77,77,77
BEGIN DESCRIPTION:
Twin Creek1362499.93
END DESCRIPTION:
XS GIS Cut Line= 3
      2703326.44      6813364.05      2703322.51      6813659.44
      2703333.07      6813963.84
#Sta/Elev= 30
  4706.4  367.60  4733.4  367.08  4753.4  366.94  4773.4  366.27  4793.4  365.29
  4813.4  364.89  4853.4  362.54  4873.4  361.98  4893.4  361.03  4903.4  360.82
  4928.7  361.00  4943.4  360.77  4963.4  360.83  4983.4  360.19  5011.4  359.97
  5011.6  359.47  5015.1  359.47  5015.4  359.97  5023.4  360.02  5043.4  360.69
  5083.4  361.15  5093.4  361.53  5113.4  361.27  5153.5  361.56  5183.5  362.04
  5233.5  362.14  5253.5  362.76  5283.6  362.81  5293.6  363.32  5306.4  363.63
#Mann=5,-1,0
  4706.4    0.05       0  4928.7    0.16       0  4983.4    0.05       0
  5011.4    0.05       0  5015.4    0.05       0
Bank Sta=5011.4,5015.4
Exp/Cntr=0.3,0.1

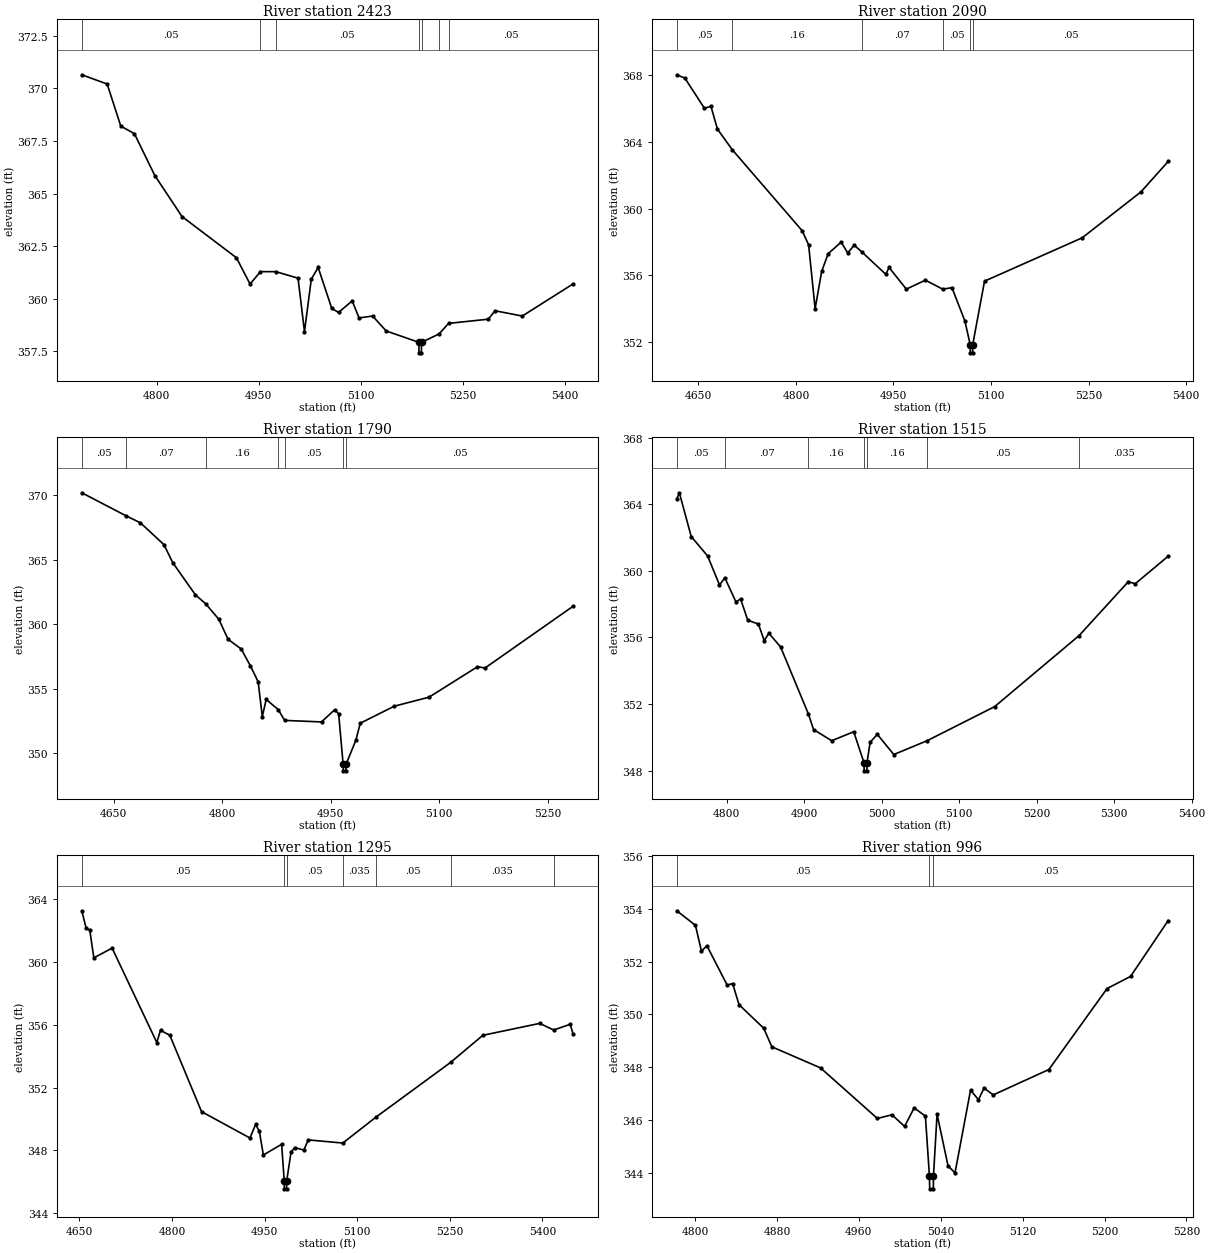
Type RM Length L Ch R = 1,2423,333,333,333
BEGIN DESCRIPTION:
Twin Creek1362422.93
END DESCRIPTION:
XS GIS Cut Line= 3
      2703247.75      6813373.70      2703252.78      6813686.87
      2703244.62      6814095.77
#Sta/Elev= 30
  4689.9  370.65  4727.2  370.21  4747.2  368.21  4767.2  367.85  4797.2  365.86
  4837.2  363.91  4917.2  361.95  4937.2  360.70  4952.5  361.29  4975.0  361.29
  5007.7  360.98  5017.2  358.44  5027.2  360.93  5037.3  361.49  5057.3  359.54
  5067.3  359.35  5087.3  359.90  5097.4  359.09  5117.3  359.18  5137.3  358.47
  5185.3  357.93  5185.5  357.43  5189.0  357.43  5189.3  357.93  5215.1  358.33
  5228.9  358.83  5287.3  359.03  5297.3  359.43  5337.3  359.18  5412.1  360.71
#Mann=7,-1,0
  4689.9    0.05       0  4952.5    0.16       0  4975.0    0.05       0
  5185.3    0.05       0  5189.3    0.05       0  5215.1    0.16       0
  5228.9    0.05       0
Bank Sta=5185.3,5189.3
Exp/Cntr=0.3,0.1

Type RM Length L Ch R = 1,2090,300,300,300
BEGIN DESCRIPTION:
Twin Creek1362089.72
END DESCRIPTION:
XS GIS Cut Line= 3
      2703062.08      6813568.62      2703084.58      6813954.45
      2703105.65      6814322.96
#Sta/Elev= 30
  4616.8  368.03  4629.2  367.83  4659.3  366.02  4669.3  366.14  4679.3  364.77
  4702.4  363.52  4809.5  358.68  4819.5  357.83  4829.5  354.00  4839.6  356.24
  4849.6  357.30  4869.6  357.99  4879.6  357.34  4889.6  357.81  4901.4  357.40
  4938.2  356.06  4943.2  356.47  4969.8  355.17  4999.0  355.71  5025.7  355.17
  5039.9  355.26  5059.9  353.25  5067.9  351.85  5068.2  351.35  5071.7  351.35
  5071.9  351.85  5090.0  355.65  5240.2  358.25  5330.4  361.00  5372.4  362.83
#Mann=6,-1,0
  4616.8    0.05       0  4702.4    0.16       0  4901.4    0.07       0
  5025.7    0.05       0  5067.9    0.07       0  5071.9    0.05       0
Bank Sta=5067.9,5071.9
Exp/Cntr=0.3,0.1

Type RM Length L Ch R = 1,1790,275,275,275
BEGIN DESCRIPTION:
Twin Creek1361790.24
END DESCRIPTION:
XS GIS Cut Line= 3
      2702733.70      6813786.33      2702888.95      6814153.50
      2702995.16      6814413.50
#Sta/Elev= 30
  4605.8  370.19  4666.8  368.41  4686.9  367.86  4719.4  366.17  4731.5  364.78
  4762.9  362.28  4776.9  361.60  4795.4  360.38  4808.0  358.84  4826.3  358.08
  4838.9  356.78  4849.7  355.54  4855.4  352.85  4860.8  354.17  4877.4  353.39
  4886.3  352.55  4937.3  352.43  4955.6  353.38  4961.0  353.05  4967.2  349.14
  4967.4  348.64  4970.9  348.64  4971.2  349.14  4984.7  351.00  4990.9  352.33
  5037.9  353.65  5086.0  354.35  5153.0  356.71  5163.4  356.61  5285.3  361.40
#Mann=7,-1,0
  4605.8    0.05       0  4666.8    0.07       0  4776.9    0.16       0
  4877.4    0.07       0  4886.3    0.05       0  4967.2    0.05       0
  4971.2    0.05       0
Bank Sta=4967.2,4971.2
Exp/Cntr=0.3,0.1

Type RM Length L Ch R = 1,1515,220,220,220
BEGIN DESCRIPTION:
Twin Creek1361514.9
END DESCRIPTION:
XS GIS Cut Line= 3
      2702510.09      6813961.79      2702653.80      6814190.20
      2702850.30      6814496.89
#Sta/Elev= 30
  4735.5  364.32  4738.8  364.69  4754.1  362.06  4775.3  360.89  4790.6  359.15
  4797.5  359.58  4811.8  358.13  4817.8  358.31  4827.1  357.03  4840.9  356.80
  4848.3  355.80  4854.3  356.25  4869.5  355.42  4905.3  351.40  4912.0  350.46
  4935.4  349.79  4963.8  350.33  4977.0  348.48  4977.3  347.98  4980.8  347.98
  4981.0  348.48  4985.0  349.70  4994.3  350.17  5015.5  348.96  5058.5  349.79
  5145.7  351.84  5254.7  356.11  5318.2  359.35  5327.0  359.22  5369.6  360.88
#Mann=7,-1,0
  4735.5    0.05       0  4797.5    0.07       0  4905.3    0.16       0
  4977.0    0.07       0  4981.0    0.16       0  5058.5    0.05       0
  5254.7   0.035       0
Bank Sta=4977,4981
Exp/Cntr=0.3,0.1

Type RM Length L Ch R = 1,1295,299,299,299
BEGIN DESCRIPTION:
Twin Creek1361294.57
END DESCRIPTION:
XS GIS Cut Line= 3
      2702274.36      6813984.63      2702466.18      6814279.04
      2702784.47      6814589.33
#Sta/Elev= 30
  4654.0  363.28  4660.9  362.19  4666.9  362.05  4673.5  360.28  4703.1  360.90
  4775.5  354.88  4781.5  355.66  4796.6  355.34  4848.0  350.47  4926.4  348.79
  4935.5  349.66  4941.5  349.23  4948.1  347.71  4977.7  348.39  4981.9  346.05
  4982.1  345.55  4985.6  345.55  4985.9  346.05  4992.9  347.89  4998.8  348.18
  5013.7  348.02  5020.7  348.67  5076.8  348.47  5130.4  350.12  5251.3  353.61
  5303.6  355.34  5395.7  356.10  5418.3  355.68  5445.1  356.04  5449.9  355.41
#Mann=7,-1,0
  4654.0    0.05       0  4981.9    0.05       0  4985.9    0.05       0
  5076.8   0.035       0  5130.4    0.05       0  5251.3   0.035       0
  5418.3    0.05       0
Bank Sta=4981.9,4985.9
Exp/Cntr=0.3,0.1

Type RM Length L Ch R = 1,996,208,208,208
BEGIN DESCRIPTION:
Twin Creek136995.52
END DESCRIPTION:
XS GIS Cut Line= 3
      2702122.44      6814083.94      2702198.63      6814289.98
      2702307.92      6814526.14
#Sta/Elev= 30
  4782.2  353.92  4800.4  353.37  4806.3  352.39  4811.6  352.60  4831.4  351.11
  4836.7  351.17  4843.0  350.37  4867.1  349.48  4875.0  348.78  4922.6  347.98
  4978.1  346.07  4992.3  346.21  5004.7  345.77  5014.0  346.47  5025.0  346.16
  5028.9  343.91  5029.2  343.41  5032.7  343.41  5032.9  343.91  5036.4  346.23
  5047.1  344.28  5053.9  344.01  5069.1  347.14  5076.8  346.78  5082.3  347.22
  5091.2  346.96  5145.6  347.92  5202.4  350.98  5225.4  351.44  5262.1  353.55
#Mann=3,-1,0
  4782.2    0.05       0  5028.9    0.05       0  5032.9    0.05       0
Bank Sta=5028.9,5032.9
Exp/Cntr=0.3,0.1

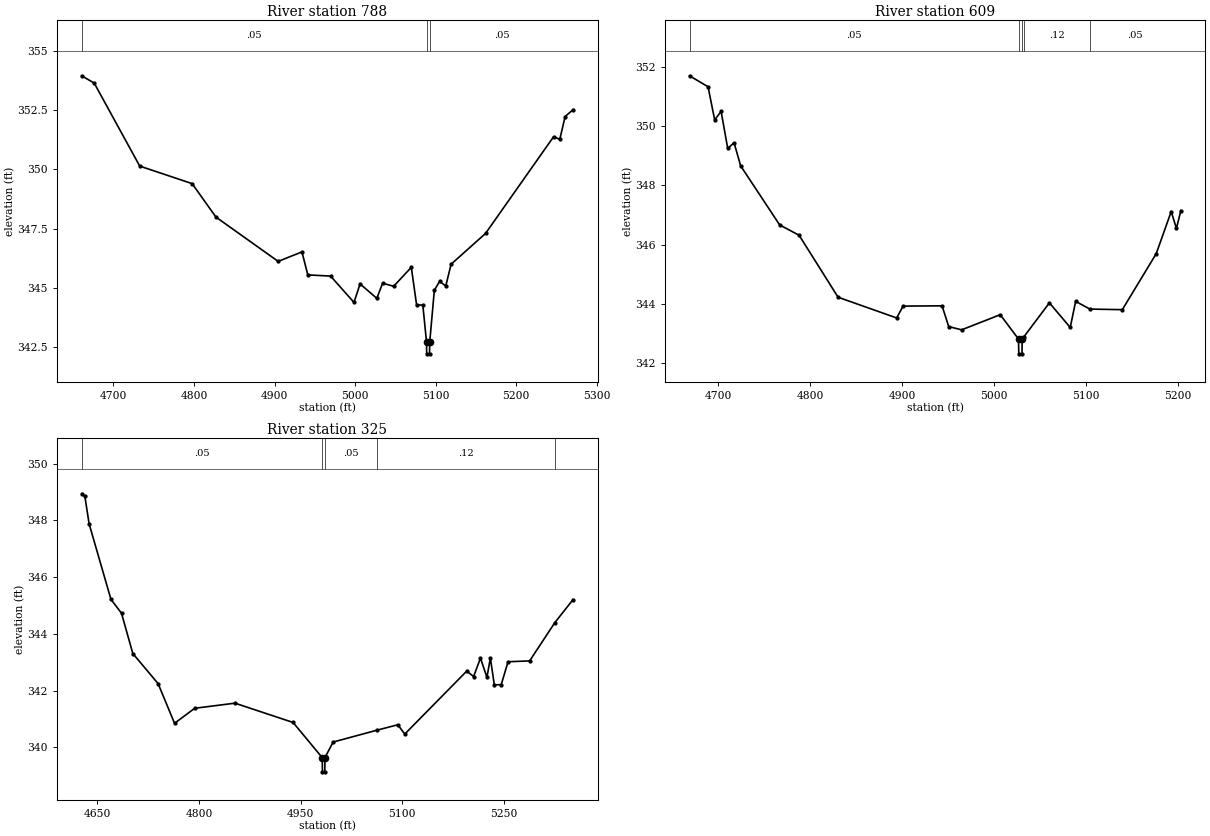
Type RM Length L Ch R = 1,788,179,179,179
BEGIN DESCRIPTION:
Twin Creek136787.99
END DESCRIPTION:
XS GIS Cut Line= 3
      2701822.33      6814092.75      2702020.42      6814369.07
      2702225.23      6814545.17
#Sta/Elev= 30
  4660.5  353.95  4676.1  353.64  4732.6  350.14  4797.7  349.40  4827.2  347.99
  4904.5  346.12  4934.0  346.52  4941.3  345.55  4969.6  345.50  4998.6  344.39
  5006.2  345.17  5027.0  344.56  5034.2  345.20  5047.9  345.07  5069.8  345.87
  5076.4  344.28  5084.1  344.28  5088.7  342.72  5088.9  342.22  5092.4  342.22
  5092.7  342.72  5098.4  344.90  5105.0  345.28  5112.6  345.08  5119.2  346.00
  5162.0  347.30  5246.5  351.38  5254.2  351.27  5260.8  352.23  5270.6  352.52
#Mann=3,-1,0
  4660.5    0.05       0  5088.7    0.05       0  5092.7    0.05       0
Bank Sta=5088.7,5092.7
Exp/Cntr=0.3,0.1

Type RM Length L Ch R = 1,609,284,284,284
BEGIN DESCRIPTION:
Twin Creek136609.26
END DESCRIPTION:
XS GIS Cut Line= 3
      2701661.73      6814256.50      2701891.63      6814493.34
      2702072.14      6814589.95
#Sta/Elev= 30
  4668.6  351.70  4688.8  351.33  4696.0  350.21  4703.0  350.50  4710.2  349.25
  4717.1  349.44  4724.3  348.66  4766.7  346.67  4787.9  346.32  4830.3  344.23
  4894.1  343.53  4901.0  343.93  4943.5  343.94  4950.7  343.24  4964.8  343.13
  5006.8  343.64  5026.7  342.82  5027.0  342.32  5030.5  342.32  5030.7  342.82
  5032.7  342.90  5060.3  344.04  5083.0  343.21  5088.9  344.09  5104.4  343.83
  5139.7  343.81  5176.6  345.70  5192.9  347.12  5198.6  346.55  5203.4  347.15
#Mann=5,-1,0
  4668.6    0.05       0  5026.7    0.05       0  5030.7    0.05       0
  5032.7    0.12       0  5104.4    0.05       0
Bank Sta=5026.7,5030.7
Exp/Cntr=0.3,0.1

Type RM Length L Ch R = 1,325,0,0,0
BEGIN DESCRIPTION:
Twin Creek136324.812
END DESCRIPTION:
XS GIS Cut Line= 5
      2701559.57      6814340.81      2701680.58      6814646.17
      2701702.88      6814684.83      2701766.79      6814686.00
      2702050.29      6814633.74
#Sta/Elev= 30
  4626.9  348.94  4631.6  348.85  4637.9  347.88  4670.1  345.22  4685.7  344.73
  4702.4  343.31  4739.7  342.25  4764.0  340.85  4793.7  341.38  4853.2  341.56
  4939.0  340.88  4982.0  339.64  4982.3  339.14  4985.8  339.14  4986.0  339.64
  4998.1  340.19  5063.1  340.61  5093.6  340.80  5103.8  340.47  5195.3  342.69
  5205.5  342.50  5215.6  343.15  5225.1  342.47  5230.2  343.15  5236.0  342.21
  5246.2  342.21  5256.3  343.02  5288.2  343.05  5325.4  344.40  5352.2  345.21
#Mann=5,-1,0
  4626.9    0.05       0  4982.0    0.05       0  4986.0    0.05       0
  5063.1    0.12       0  5325.4    0.05       0
Bank Sta=4982,4986
Exp/Cntr=0.3,0.1

Chan Stop Cuts=-1