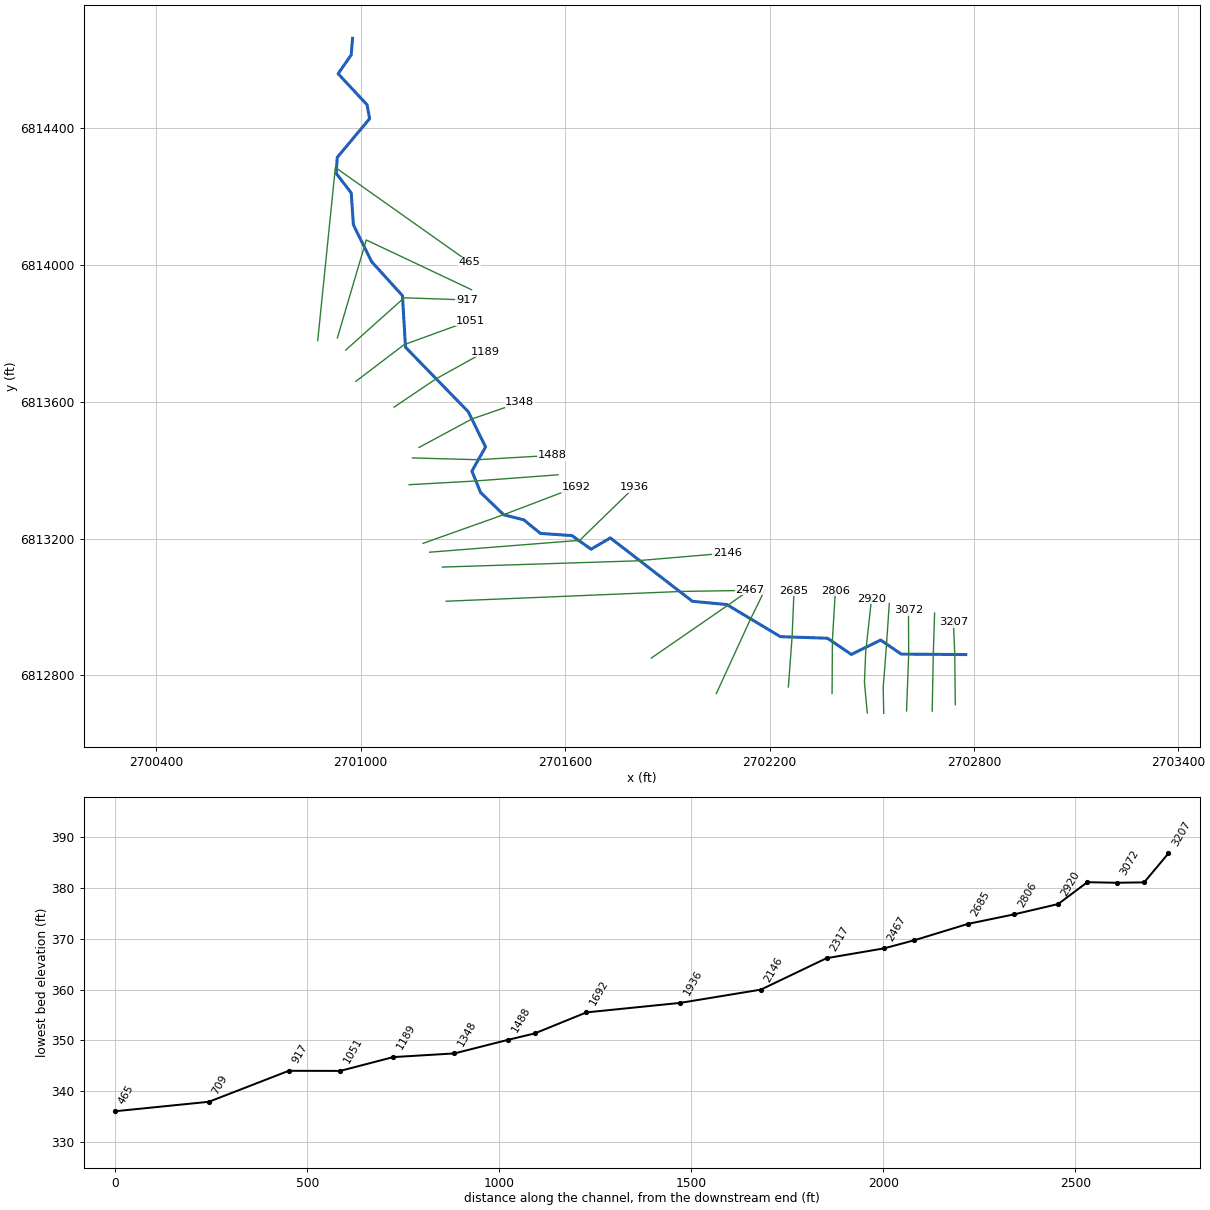
--- Twin Creek138.prj (project) ---

Proj Title=Twin Creek138 Base Level Engineering
Current Plan=p01
Default Exp/Contr=0.3,0.1
English Units
Geom File=g01
Flow File=f01
Plan File=p01
BEGIN DESCRIPTION:
Twin Creek138
END DESCRIPTION:

--- Twin Creek138.p01 (plan) ---

Plan Title=Multiple Run
Short Identifier=Multiple
Geom File=g01
Flow File=f01
Subcritical Flow
K Sum by GR= 0
Std Step Tol= 0.01
Critical Tol= 0.01
Num of Std Step Trials= 20
Max Error Tol= 0.3
Flow Tol Ratio= 0.001
Split Flow NTrial= 30
Split Flow Tol= 0.02
Split Flow Ratio= 0.02
Log Output Level= 0
Friction Slope Method= 1
Unsteady Friction Slope Method= 2
Unsteady Bridges Friction Slope Method= 1
Parabolic Critical Depth
Global Vel Dist=  1 , 1 , 1
Global Log Level= 0
CheckData=True
Encroach Param= -1, 0, 0, 0
BEGIN DESCRIPTION:
Multiple Run
END DESCRIPTION:

--- Twin Creek138.f01 (steady flow) ---

Flow Title=Multiple
Number of Profiles=7
Profile Names=10-year,25-year,50-year,1pct_min,100-year,1pct_plu,500-year
River Rch & RM= Twin Creek138,Reach-1,3207
     133     162     182     103     205     410     258
Boundary for River Rch & Prof#=Twin Creek138,Reach-1,1
Up Type=0
Dn Type=3
Dn Slope=0.005
Boundary for River Rch & Prof#=Twin Creek138,Reach-1,2
Up Type=0
Dn Type=3
Dn Slope=0.005
Boundary for River Rch & Prof#=Twin Creek138,Reach-1,3
Up Type=0
Dn Type=3
Dn Slope=0.005
Boundary for River Rch & Prof#=Twin Creek138,Reach-1,4
Up Type=0
Dn Type=3
Dn Slope=0.005
Boundary for River Rch & Prof#=Twin Creek138,Reach-1,5
Up Type=0
Dn Type=3
Dn Slope=0.005
Boundary for River Rch & Prof#=Twin Creek138,Reach-1,6
Up Type=0
Dn Type=3
Dn Slope=0.005
Boundary for River Rch & Prof#=Twin Creek138,Reach-1,7
Up Type=0
Dn Type=3
Dn Slope=0.005

--- Twin Creek138.g01 (geometry) ---

Geom Title=Existing Conditions

River Reach=Twin Creek138,Reach-1
Reach XY= 30
      2702776.00      6812861.00      2702586.43      6812862.37
      2702525.99      6812903.41      2702440.12      6812861.30
      2702370.07      6812908.70      2702231.93      6812913.25
      2702074.41      6813007.17      2701973.58      6813016.54
      2701732.66      6813201.69      2701676.10      6813168.80
      2701620.11      6813208.46      2701527.59      6813214.82
      2701478.17      6813254.86      2701419.92      6813269.13
      2701352.02      6813334.12      2701326.33      6813396.93
      2701366.57      6813467.61      2701315.25      6813570.68
      2701131.47      6813758.55      2701122.45      6813909.53
      2701031.85      6814008.71      2700978.44      6814116.56
      2700972.11      6814209.42      2700927.90      6814266.73
      2700931.11      6814313.29      2701026.10      6814426.36
      2701018.50      6814467.05      2700933.60      6814557.62
      2700971.98      6814612.36      2700976.00      6814661.00

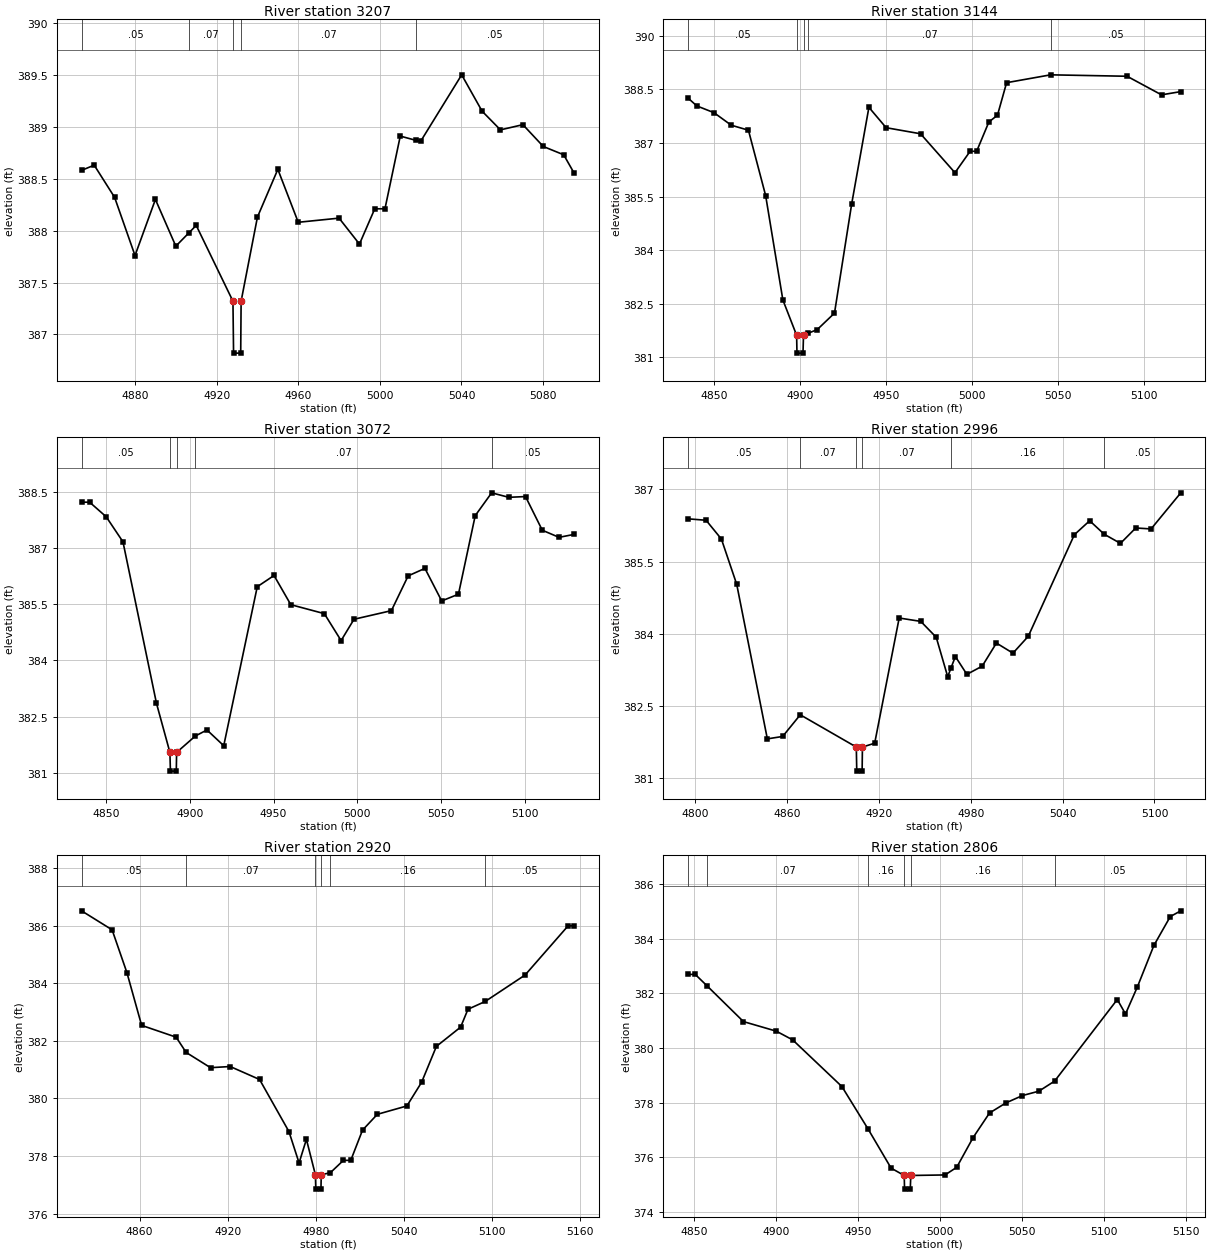
Type RM Length L Ch R = 1,3207,63,63,63
BEGIN DESCRIPTION:
Twin Creek1383207.363
END DESCRIPTION:
XS GIS Cut Line= 3
      2702745.16      6812714.79      2702743.57      6812860.98
      2702739.70      6812956.20
#Sta/Elev= 29
  4853.8  388.58  4860.0  388.63  4870.0  388.32  4880.0  387.76  4890.0  388.30
  4900.0  387.85  4906.5  387.98  4910.0  388.05  4928.0  387.32  4928.3  386.82
  4931.8  386.82  4932.0  387.32  4940.0  388.13  4950.0  388.59  4960.0  388.08
  4980.0  388.12  4990.0  387.87  4997.5  388.21  5002.5  388.21  5010.0  388.91
  5017.5  388.87  5020.0  388.86  5040.1  389.50  5050.1  389.15  5059.1  388.97
  5070.1  389.02  5080.1  388.81  5090.1  388.73  5095.3  388.55
#Mann=5,-1,0
  4853.8    0.05       0  4906.5    0.07       0  4928.0    0.07       0
  4932.0    0.07       0  5017.5    0.05       0
Bank Sta=4928,4932
Exp/Cntr=0.3,0.1

Type RM Length L Ch R = 1,3144,72,72,72
BEGIN DESCRIPTION:
Twin Creek1383144.36
END DESCRIPTION:
XS GIS Cut Line= 3
      2702677.36      6812695.94      2702680.63      6812863.61
      2702684.41      6812982.15
#Sta/Elev= 28
  4835.0  388.26  4840.1  388.04  4850.1  387.85  4860.1  387.50  4870.1  387.36
  4880.1  385.53  4890.1  382.61  4898.1  381.62  4898.3  381.12  4901.8  381.12
  4902.1  381.62  4905.0  381.68  4910.1  381.78  4920.1  382.24  4930.1  385.30
  4940.1  388.00  4950.1  387.43  4970.1  387.26  4990.1  386.17  4998.9  386.77
  5002.7  386.77  5009.8  387.59  5014.8  387.78  5020.1  388.69  5045.7  388.91
  5090.1  388.87  5110.1  388.35  5121.3  388.44
#Mann=5,-1,0
  4835.0    0.05       0  4898.1    0.07       0  4902.1    0.05       0
  4905.0    0.07       0  5045.7    0.05       0
Bank Sta=4898.1,4902.1
Exp/Cntr=0.3,0.1

Type RM Length L Ch R = 1,3072,76,76,76
BEGIN DESCRIPTION:
Twin Creek1383072.11
END DESCRIPTION:
XS GIS Cut Line= 3
      2702602.08      6812696.30      2702608.34      6812861.28
      2702607.78      6812990.08
#Sta/Elev= 30
  4835.5  388.23  4840.3  388.23  4850.2  387.84  4860.2  387.17  4880.2  382.85
  4888.2  381.54  4888.5  381.04  4892.0  381.04  4892.2  381.54  4903.4  381.98
  4910.3  382.14  4920.3  381.72  4940.3  385.97  4950.3  386.27  4960.3  385.49
  4980.3  385.25  4990.3  384.53  4998.0  385.10  5020.3  385.33  5030.3  386.26
  5040.3  386.46  5050.3  385.59  5060.3  385.77  5070.3  387.87  5080.1  388.48
  5090.3  388.36  5100.3  388.38  5110.3  387.48  5120.3  387.29  5129.4  387.37
#Mann=5,-1,0
  4835.5    0.05       0  4888.2    0.07       0  4892.2    0.05       0
  4903.4    0.07       0  5080.1    0.05       0
Bank Sta=4888.2,4892.2
Exp/Cntr=0.3,0.1

Type RM Length L Ch R = 1,2996,76,76,76
BEGIN DESCRIPTION:
Twin Creek1382996.23
END DESCRIPTION:
XS GIS Cut Line= 5
      2702535.19      6812689.22      2702533.47      6812765.38
      2702538.52      6812827.84      2702543.49      6812894.45
      2702551.45      6813010.34
#Sta/Elev= 30
  4795.4  386.39  4807.2  386.36  4817.2  385.97  4827.2  385.03  4847.2  381.82
  4857.2  381.87  4868.7  382.32  4905.3  381.65  4905.6  381.15  4909.1  381.15
  4909.3  381.65  4917.3  381.73  4933.3  384.33  4947.4  384.26  4957.5  383.93
  4965.0  383.11  4967.1  383.29  4970.0  383.53  4977.5  383.16  4987.5  383.33
  4996.8  383.81  5007.6  383.60  5017.6  383.95  5047.7  386.06  5057.7  386.35
  5067.2  386.07  5077.8  385.88  5087.8  386.20  5097.8  386.18  5117.2  386.93
#Mann=6,-1,0
  4795.4    0.05       0  4868.7    0.07       0  4905.3    0.07       0
  4909.3    0.07       0  4967.1    0.16       0  5067.2    0.05       0
Bank Sta=4905.3,4909.3
Exp/Cntr=0.3,0.1

Type RM Length L Ch R = 1,2920,114,114,114
BEGIN DESCRIPTION:
Twin Creek1382919.57
END DESCRIPTION:
XS GIS Cut Line= 4
      2702486.94      6812690.26      2702478.46      6812779.38
      2702482.28      6812870.21      2702499.37      6813024.33
#Sta/Elev= 30
  4820.5  386.52  4841.3  385.86  4851.4  384.37  4861.4  382.54  4884.9  382.13
  4891.7  381.60  4908.3  381.07  4921.7  381.11  4941.7  380.66  4961.7  378.85
  4968.6  377.76  4973.6  378.58  4979.7  377.35  4980.0  376.85  4983.5  376.85
  4983.7  377.35  4989.9  377.42  4998.8  377.85  5003.8  377.85  5011.8  378.90
  5021.9  379.45  5042.0  379.74  5052.0  380.56  5062.1  381.81  5078.6  382.48
  5083.6  383.10  5095.3  383.37  5122.5  384.29  5151.8  386.00  5156.0  386.00
#Mann=6,-1,0
  4820.5    0.05       0  4891.7    0.07       0  4979.7    0.07       0
  4983.7    0.07       0  4989.9    0.16       0  5095.3    0.05       0
Bank Sta=4979.7,4983.7
Exp/Cntr=0.3,0.1

Type RM Length L Ch R = 1,2806,121,121,121
BEGIN DESCRIPTION:
Twin Creek1382805.91
END DESCRIPTION:
XS GIS Cut Line= 3
      2702383.51      6812747.23      2702384.43      6812901.81
      2702393.15      6813047.37
#Sta/Elev= 27
  4846.2  382.70  4850.6  382.70  4857.8  382.28  4880.0  380.97  4900.0  380.62
  4910.0  380.30  4940.0  378.59  4955.8  377.05  4970.0  375.60  4978.0  375.33
  4978.2  374.83  4981.7  374.83  4982.0  375.33  5002.9  375.35  5010.0  375.63
  5020.0  376.72  5030.0  377.62  5040.0  377.99  5050.1  378.26  5060.1  378.42
  5069.7  378.79  5107.9  381.78  5112.9  381.25  5120.2  382.25  5130.2  383.76
  5140.2  384.82  5146.6  385.03
#Mann=6,-1,0
  4846.2    0.05       0  4857.8    0.07       0  4955.8    0.16       0
  4978.0    0.07       0  4982.0    0.16       0  5069.7    0.05       0
Bank Sta=4978,4982
Exp/Cntr=0.3,0.1

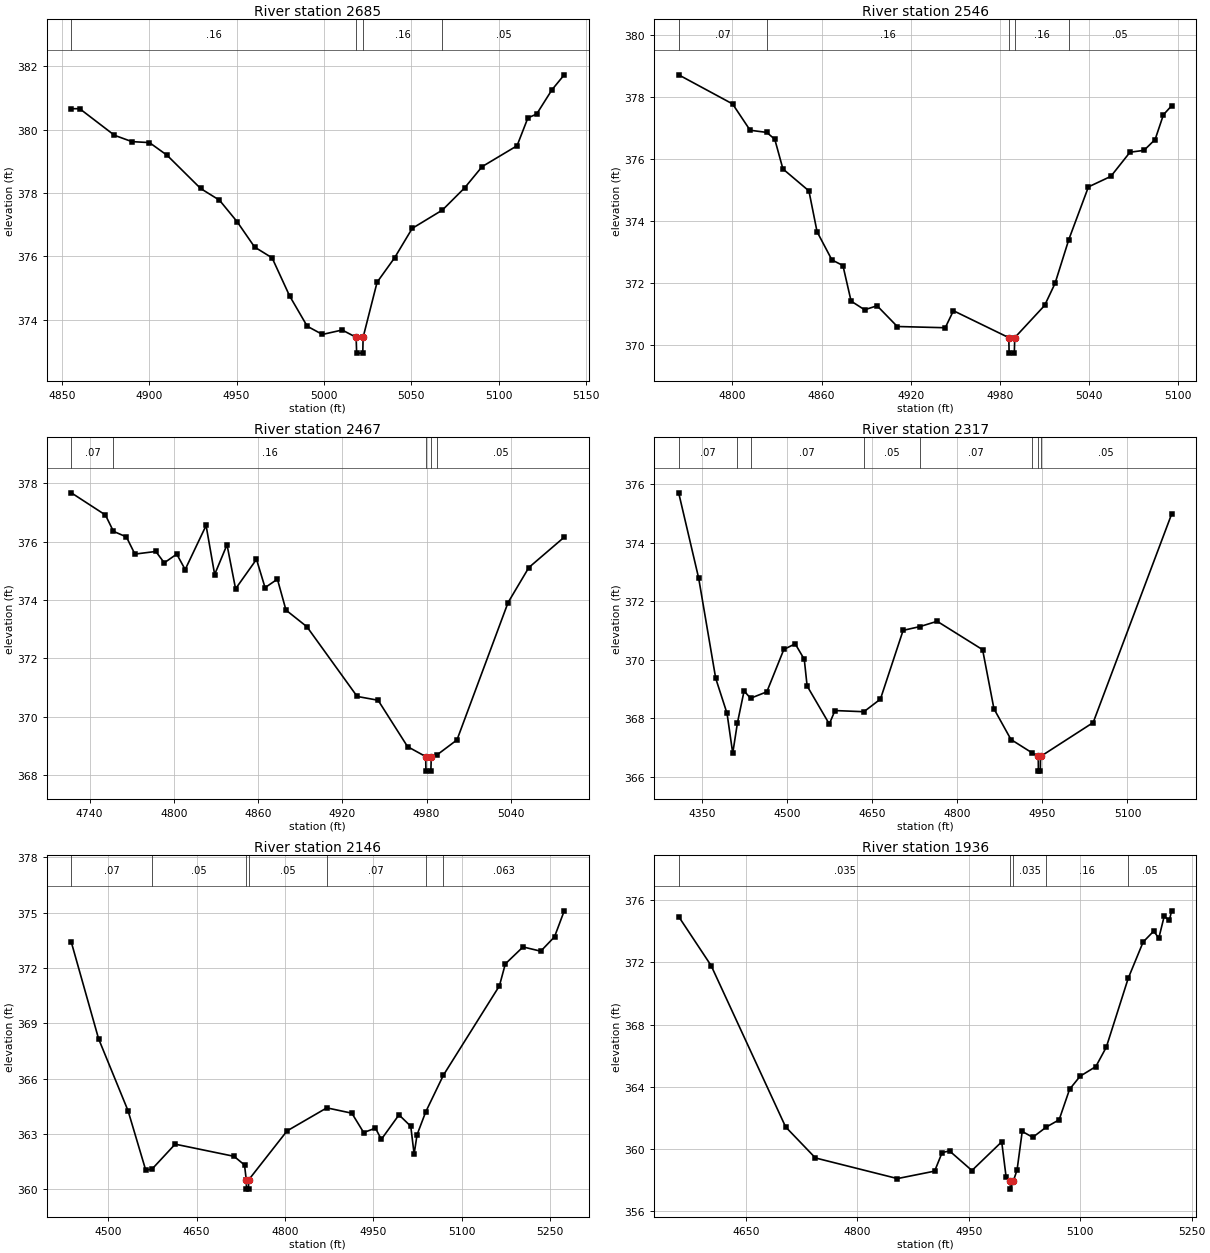
Type RM Length L Ch R = 1,2685,139,139,139
BEGIN DESCRIPTION:
Twin Creek1382685.21
END DESCRIPTION:
XS GIS Cut Line= 3
      2702255.16      6812766.40      2702266.18      6812913.43
      2702271.83      6813047.97
#Sta/Elev= 30
  4855.4  380.66  4860.2  380.66  4880.1  379.82  4890.1  379.62  4900.1  379.59
  4910.2  379.19  4929.4  378.14  4940.2  377.77  4950.3  377.09  4960.3  376.29
  4970.3  375.95  4980.3  374.75  4990.4  373.79  4999.1  373.53  5010.4  373.67
  5018.4  373.44  5018.7  372.94  5022.2  372.94  5022.4  373.44  5030.4  375.18
  5040.4  375.95  5050.5  376.88  5067.8  377.46  5080.5  378.16  5090.5  378.83
  5110.5  379.49  5116.7  380.37  5121.7  380.49  5130.5  381.26  5137.5  381.73
#Mann=4,-1,0
  4855.4    0.16       0  5018.4    0.07       0  5022.4    0.16       0
  5067.8    0.05       0
Bank Sta=5018.4,5022.4
Exp/Cntr=0.3,0.1

Type RM Length L Ch R = 1,2546,79,79,79
BEGIN DESCRIPTION:
Twin Creek1382546.12
END DESCRIPTION:
XS GIS Cut Line= 3
      2702043.87      6812747.32      2702143.74      6812963.91
      2702185.10      6813047.64
#Sta/Elev= 30
  4763.8  378.72  4800.1  377.78  4811.9  376.93  4823.1  376.86  4828.5  376.64
  4834.0  375.68  4851.5  374.97  4857.0  373.65  4867.0  372.74  4874.4  372.56
  4879.9  371.41  4889.0  371.13  4897.4  371.26  4911.0  370.59  4943.3  370.55
  4948.8  371.10  4986.1  370.23  4986.3  369.73  4989.8  369.73  4990.1  370.23
  5010.2  371.27  5017.2  371.98  5026.5  373.40  5039.7  375.10  5054.8  375.44
  5067.7  376.22  5077.1  376.28  5084.6  376.63  5090.2  377.43  5095.7  377.72
#Mann=5,-1,0
  4763.8    0.07       0  4823.1    0.16       0  4986.1    0.07       0
  4990.1    0.16       0  5026.5    0.05       0
Bank Sta=4986.1,4990.1
Exp/Cntr=0.3,0.1

Type RM Length L Ch R = 1,2467,150,150,150
BEGIN DESCRIPTION:
Twin Creek1382466.51
END DESCRIPTION:
XS GIS Cut Line= 3
      2701853.00      6812850.85      2702079.92      6813006.62
      2702141.96      6813050.27
#Sta/Elev= 30
  4727.0  377.67  4751.3  376.91  4757.0  376.35  4766.2  376.16  4772.3  375.57
  4787.2  375.66  4793.2  375.27  4802.1  375.57  4808.1  375.04  4823.0  376.55
  4829.1  374.87  4837.9  375.89  4844.0  374.38  4858.9  375.39  4865.0  374.42
  4873.8  374.71  4879.9  373.65  4894.8  373.08  4930.6  370.69  4945.5  370.56
  4966.5  368.97  4979.4  368.63  4979.6  368.13  4983.1  368.13  4983.4  368.63
  4987.3  368.68  5001.7  369.20  5038.1  373.91  5052.9  375.11  5078.1  376.15
#Mann=5,-1,0
  4727.0    0.07       0  4757.0    0.16       0  4979.4    0.05       0
  4983.4    0.16       0  4987.3    0.05       0
Bank Sta=4979.4,4983.4
Exp/Cntr=0.3,0.1

Type RM Length L Ch R = 1,2317,171,171,171
BEGIN DESCRIPTION:
Twin Creek1382316.8
END DESCRIPTION:
XS GIS Cut Line= 3
      2701250.75      6813016.80      2701941.50      6813045.40
      2702118.94      6813048.12
#Sta/Elev= 30
  4309.0  375.70  4344.3  372.78  4374.3  369.36  4394.3  368.16  4404.3  366.80
  4412.5  367.83  4424.3  368.93  4435.7  368.68  4464.4  368.90  4494.4  370.35
  4514.4  370.54  4530.4  370.01  4535.4  369.10  4574.5  367.80  4584.5  368.26
  4635.5  368.22  4664.6  368.65  4704.6  371.00  4734.4  371.13  4764.6  371.31
  4844.7  370.34  4864.7  368.32  4894.7  367.27  4932.3  366.81  4942.8  366.69
  4943.0  366.19  4946.5  366.19  4946.8  366.69  5039.6  367.85  5177.8  374.97
#Mann=8,-1,0
  4309.0    0.07       0  4412.5    0.05       0  4435.7    0.07       0
  4635.5    0.05       0  4734.4    0.07       0  4932.3    0.05       0
  4942.8    0.05       0  4946.8    0.05       0
Bank Sta=4942.8,4946.8
Exp/Cntr=0.3,0.1

Type RM Length L Ch R = 1,2146,210,210,210
BEGIN DESCRIPTION:
Twin Creek1382145.75
END DESCRIPTION:
XS GIS Cut Line= 3
      2701239.69      6813116.56      2701804.95      6813134.53
      2702075.73      6813157.54
#Sta/Elev= 30
  4437.2  373.40  4483.5  368.16  4533.6  364.25  4563.6  361.03  4574.4  361.09
  4613.6  362.44  4713.6  361.78  4731.4  361.31  4734.4  360.50  4734.7  360.00
  4738.2  360.00  4738.4  360.50  4803.7  363.16  4871.2  364.41  4913.7  364.12
  4933.8  363.07  4953.8  363.31  4963.8  362.70  4993.8  364.03  5013.8  363.41
  5019.5  361.90  5024.5  362.95  5039.2  364.19  5069.2  366.18  5164.4  371.03
  5174.4  372.22  5204.5  373.14  5234.6  372.91  5258.0  373.69  5274.5  375.10
#Mann=7,-1,0
  4437.2    0.07       0  4574.4    0.05       0  4734.4    0.07       0
  4738.4    0.05       0  4871.2    0.07       0  5039.2   0.035       0
  5069.2   0.063       0
Bank Sta=4734.4,4738.4
Exp/Cntr=0.3,0.1

Type RM Length L Ch R = 1,1936,244,244,244
BEGIN DESCRIPTION:
Twin Creek1381936.41
END DESCRIPTION:
XS GIS Cut Line= 3
      2701202.43      6813160.03      2701642.70      6813194.65
      2701802.21      6813349.01
#Sta/Elev= 30
  4559.3  374.96  4603.0  371.80  4703.3  361.40  4743.4  359.40  4853.8  358.07
  4903.9  358.55  4914.0  359.75  4924.0  359.85  4954.1  358.59  4994.2  360.44
  5000.1  358.18  5005.7  357.89  5005.9  357.39  5009.7  357.89  5014.9  358.63
  5021.8  361.11  5036.0  360.73  5054.2  361.39  5071.5  361.86  5085.6  363.83
  5099.8  364.67  5120.9  365.29  5135.0  366.54  5164.5  370.98  5184.6  373.32
  5198.8  374.02  5205.7  373.57  5212.9  374.97  5219.9  374.71  5222.9  375.33
#Mann=5,-1,0
  4559.3   0.035       0  5005.7   0.035       0  5009.7   0.035       0
  5054.2    0.16       0  5164.5    0.05       0
Bank Sta=5005.7,5009.7
Exp/Cntr=0.3,0.1

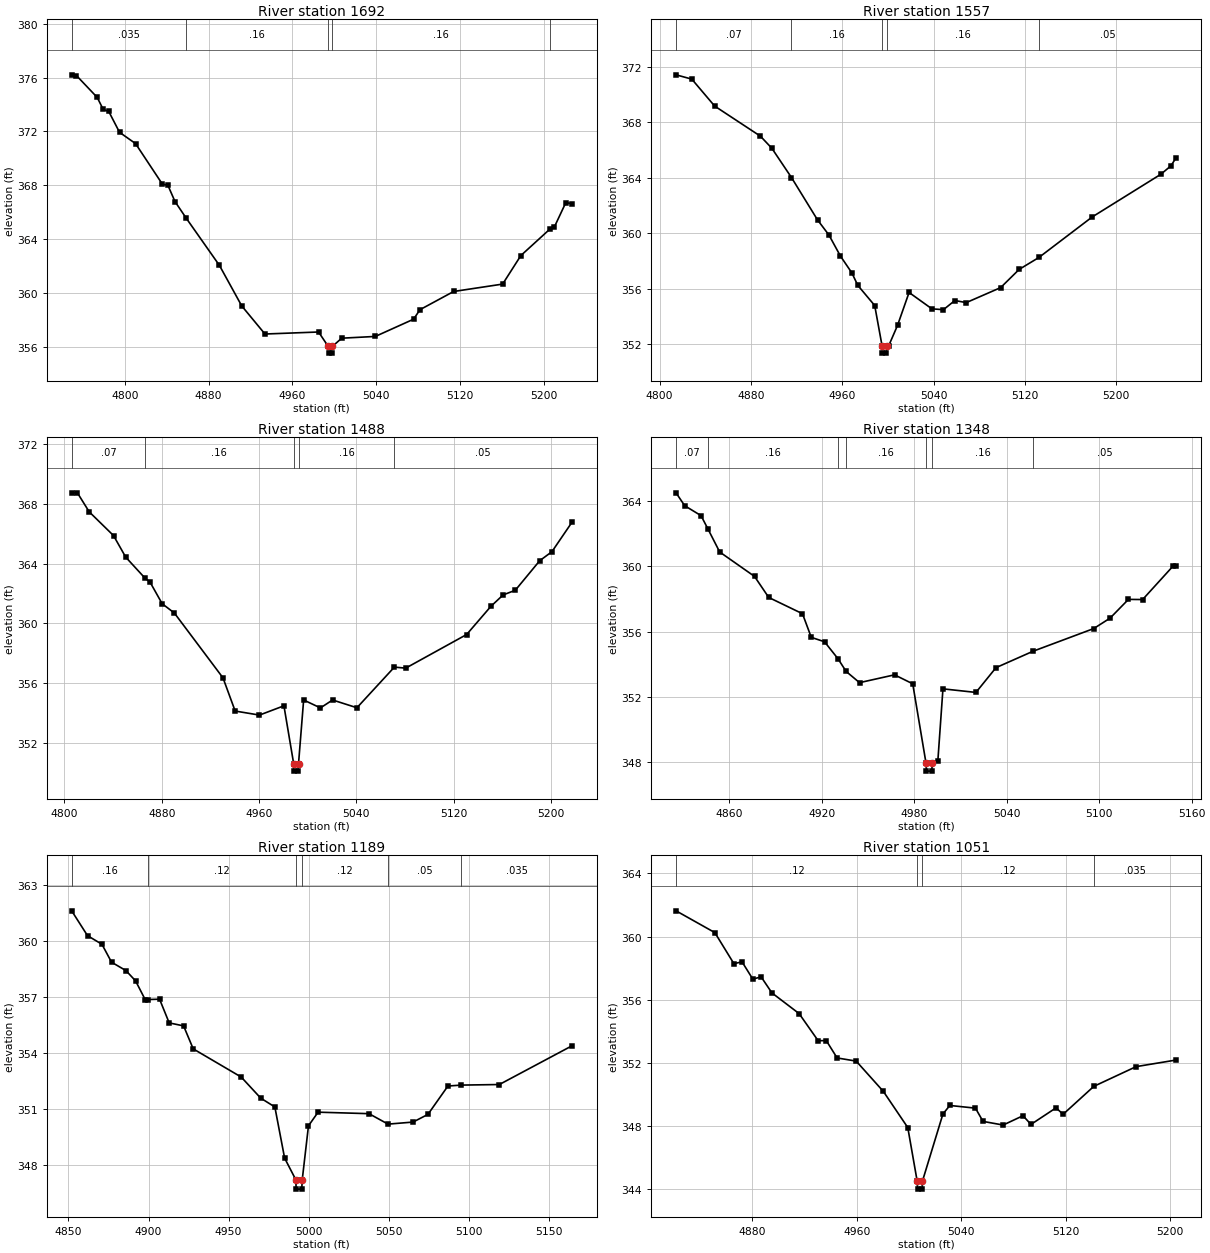
Type RM Length L Ch R = 1,1692,135,135,135
BEGIN DESCRIPTION:
Twin Creek1381692.09
END DESCRIPTION:
XS GIS Cut Line= 3
      2701182.96      6813185.83      2701420.68      6813269.99
      2701631.56      6813349.91
#Sta/Elev= 30
  4749.2  376.20  4753.7  376.15  4773.6  374.52  4779.3  373.63  4784.6  373.48
  4794.9  371.93  4810.2  371.09  4835.8  368.08  4841.1  367.99  4847.9  366.78
  4858.4  365.57  4890.3  362.04  4911.6  359.03  4933.8  356.94  4985.0  357.09
  4994.2  356.02  4994.5  355.52  4998.0  355.52  4998.2  356.02  5007.1  356.63
  5039.2  356.76  5075.7  358.04  5081.9  358.75  5114.0  360.10  5160.8  360.65
  5178.2  362.77  5205.7  364.72  5210.3  364.91  5221.1  366.70  5226.9  366.63
#Mann=5,-1,0
  4749.2   0.035       0  4858.4    0.16       0  4994.2    0.07       0
  4998.2    0.16       0  5205.7    0.05       0
Bank Sta=4994.2,4998.2
Exp/Cntr=0.3,0.1

Type RM Length L Ch R = 1,1557,69,69,69
BEGIN DESCRIPTION:
Twin Creek1381556.88
END DESCRIPTION:
XS GIS Cut Line= 3
      2701142.26      6813357.21      2701328.06      6813367.47
      2701579.39      6813386.08
#Sta/Elev= 30
  4814.4  371.42  4828.2  371.11  4848.2  369.17  4888.3  367.00  4898.3  366.13
  4915.5  364.02  4938.3  360.97  4948.3  359.88  4958.4  358.36  4968.4  357.15
  4973.6  356.25  4988.4  354.80  4994.9  351.87  4995.2  351.37  4998.7  351.37
  4998.9  351.87  5000.5  351.87  5008.4  353.37  5018.5  355.74  5038.5  354.56
  5048.6  354.50  5058.6  355.16  5068.6  355.01  5098.7  356.09  5114.9  357.40
  5132.2  358.26  5178.9  361.18  5239.1  364.26  5247.8  364.86  5252.5  365.46
#Mann=5,-1,0
  4814.4    0.07       0  4915.5    0.16       0  4994.9    0.07       0
  4998.9    0.16       0  5132.2    0.05       0
Bank Sta=4994.9,4998.9
Exp/Cntr=0.3,0.1

Type RM Length L Ch R = 1,1488,140,140,140
BEGIN DESCRIPTION:
Twin Creek1381487.82
END DESCRIPTION:
XS GIS Cut Line= 3
      2701151.61      6813435.35      2701343.55      6813430.16
      2701562.37      6813442.85
#Sta/Elev= 30
  4805.9  368.74  4810.6  368.74  4820.3  367.47  4840.3  365.88  4850.3  364.44
  4866.2  363.03  4870.3  362.77  4880.3  361.32  4890.3  360.70  4930.3  356.36
  4940.3  354.14  4960.3  353.87  4980.4  354.49  4988.4  350.62  4988.6  350.12
  4992.1  350.12  4992.4  350.62  4996.6  354.88  5010.4  354.35  5020.4  354.88
  5040.4  354.36  5071.2  357.08  5080.5  357.01  5130.6  359.26  5150.6  361.15
  5160.6  361.91  5170.6  362.22  5190.7  364.20  5200.7  364.80  5217.1  366.76
#Mann=5,-1,0
  4805.9    0.07       0  4866.2    0.16       0  4988.4    0.07       0
  4992.4    0.16       0  5071.2    0.05       0
Bank Sta=4988.4,4992.4
Exp/Cntr=0.3,0.1

Type RM Length L Ch R = 1,1348,159,159,159
BEGIN DESCRIPTION:
Twin Creek1381347.84
END DESCRIPTION:
XS GIS Cut Line= 3
      2701171.09      6813465.99      2701326.50      6813549.15
      2701466.58      6813597.35
#Sta/Elev= 30
  4825.6  364.52  4831.2  363.73  4841.8  363.12  4846.4  362.28  4853.9  360.89
  4876.5  359.39  4885.7  358.10  4907.6  357.10  4913.3  355.65  4921.9  355.38
  4930.6  354.34  4935.9  353.56  4944.6  352.87  4967.3  353.35  4979.1  352.80
  4987.7  347.94  4988.0  347.44  4991.5  347.44  4991.7  347.94  4995.4  348.08
  4998.7  352.49  5020.1  352.27  5033.1  353.79  5057.2  354.80  5096.5  356.19
  5107.1  356.83  5119.0  357.98  5128.2  357.97  5147.9  360.02  5150.0  360.02
#Mann=7,-1,0
  4825.6    0.07       0  4846.4    0.16       0  4930.6    0.12       0
  4935.9    0.16       0  4987.7    0.07       0  4991.7    0.16       0
  5057.2    0.05       0
Bank Sta=4987.7,4991.7
Exp/Cntr=0.3,0.1

Type RM Length L Ch R = 1,1189,138,138,138
BEGIN DESCRIPTION:
Twin Creek1381188.78
END DESCRIPTION:
XS GIS Cut Line= 3
      2701097.83      6813583.81      2701220.94      6813666.26
      2701364.69      6813745.70
#Sta/Elev= 30
  4852.0  361.62  4861.9  360.29  4870.9  359.83  4876.9  358.87  4885.9  358.42
  4891.9  357.87  4897.9  356.87  4899.8  356.87  4906.9  356.89  4912.9  355.62
  4921.9  355.46  4927.9  354.23  4957.9  352.72  4970.1  351.59  4978.9  351.12
  4985.0  348.38  4992.0  347.22  4992.2  346.72  4995.7  346.72  4996.0  347.22
  4999.9  350.11  5005.9  350.84  5037.7  350.76  5049.6  350.20  5065.2  350.31
  5074.5  350.72  5087.0  352.24  5095.4  352.29  5119.1  352.32  5164.4  354.39
#Mann=6,-1,0
  4852.0    0.16       0  4899.8    0.12       0  4992.0    0.07       0
  4996.0    0.12       0  5049.6    0.05       0  5095.4   0.035       0
Bank Sta=4992,4996
Exp/Cntr=0.3,0.1

Type RM Length L Ch R = 1,1051,134,134,134
BEGIN DESCRIPTION:
Twin Creek1381051.42
END DESCRIPTION:
XS GIS Cut Line= 3
      2700985.84      6813659.20      2701127.53      6813766.32
      2701320.56      6813836.18
#Sta/Elev= 30
  4821.7  361.63  4851.4  360.25  4866.0  358.28  4872.2  358.40  4880.5  357.30
  4886.8  357.45  4895.1  356.43  4915.9  355.12  4930.5  353.40  4936.7  353.41
  4945.0  352.31  4959.6  352.11  4980.4  350.19  4999.1  347.90  5006.3  344.50
  5006.6  344.00  5010.1  344.00  5010.3  344.50  5026.0  348.76  5031.3  349.30
  5050.9  349.13  5056.7  348.29  5072.1  348.06  5087.3  348.65  5093.4  348.10
  5112.6  349.15  5118.0  348.74  5141.5  350.51  5173.9  351.76  5204.6  352.18
#Mann=4,-1,0
  4821.7    0.12       0  5006.3    0.07       0  5010.3    0.12       0
  5141.5   0.035       0
Bank Sta=5006.3,5010.3
Exp/Cntr=0.3,0.1

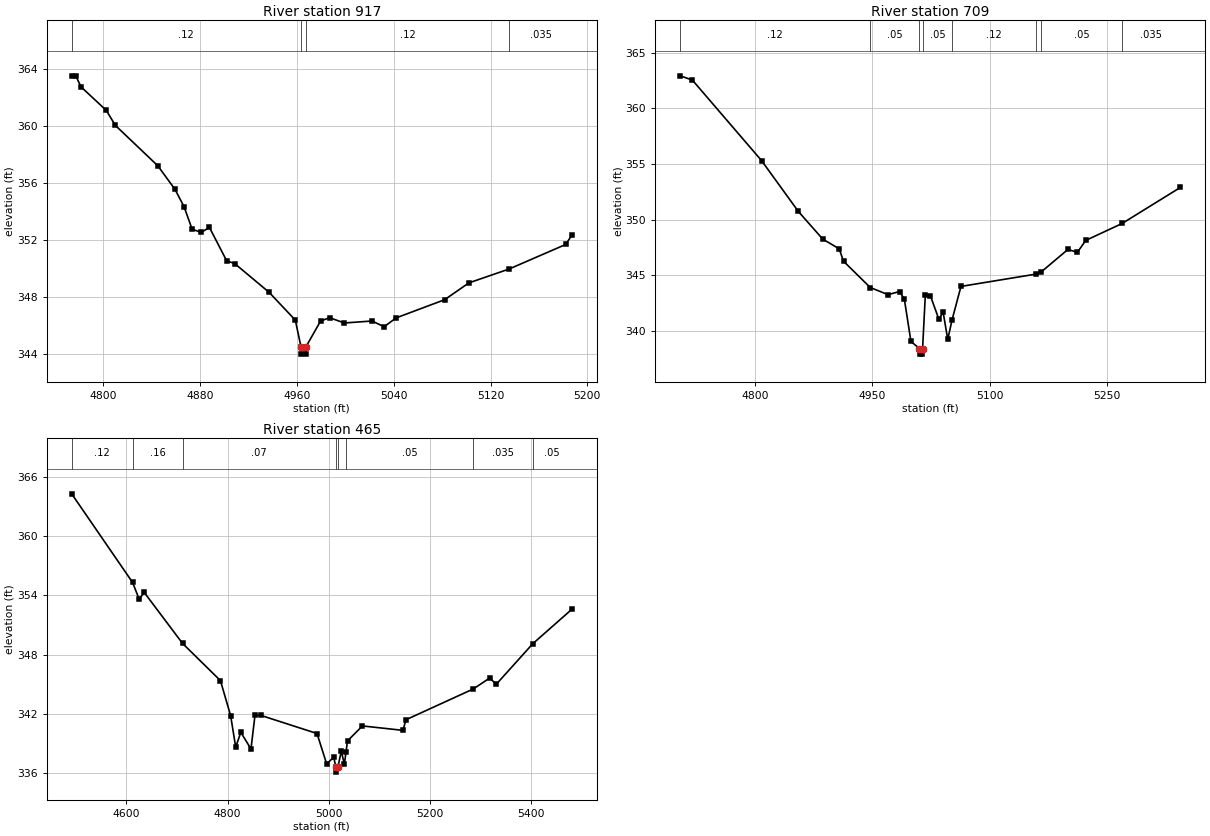
Type RM Length L Ch R = 1,917,208,208,208
BEGIN DESCRIPTION:
Twin Creek138916.8
END DESCRIPTION:
XS GIS Cut Line= 3
      2700955.89      6813750.34      2701127.38      6813903.13
      2701311.10      6813896.90
#Sta/Elev= 30
  4773.7  363.51  4777.1  363.51  4781.4  362.74  4802.3  361.09  4809.8  360.04
  4844.9  357.21  4859.1  355.56  4866.6  354.35  4873.3  352.76  4880.9  352.55
  4887.6  352.89  4901.8  350.56  4908.5  350.36  4936.9  348.35  4958.6  346.40
  4963.3  344.52  4963.6  344.02  4967.1  344.02  4967.3  344.52  4979.5  346.34
  4987.0  346.57  4999.1  346.20  5022.0  346.34  5032.0  345.94  5042.0  346.56
  5082.0  347.83  5102.1  349.01  5135.3  349.98  5182.1  351.70  5187.2  352.35
#Mann=4,-1,0
  4773.7    0.12       0  4963.3    0.07       0  4967.3    0.12       0
  5135.3   0.035       0
Bank Sta=4963.3,4967.3
Exp/Cntr=0.3,0.1

Type RM Length L Ch R = 1,709,244,244,244
BEGIN DESCRIPTION:
Twin Creek138708.96
END DESCRIPTION:
XS GIS Cut Line= 3
      2700931.53      6813786.10      2701016.24      6814072.06
      2701325.30      6813926.66
#Sta/Elev= 30
  4704.3  362.91  4719.8  362.53  4808.3  355.30  4855.4  350.73  4886.7  348.24
  4907.6  347.38  4913.2  346.26  4947.4  343.90  4970.1  343.26  4984.9  343.54
  4991.0  342.85  4999.4  339.06  5010.3  338.42  5010.5  337.92  5014.0  337.92
  5014.3  338.42  5017.8  343.21  5024.4  343.14  5035.1  341.06  5040.6  341.68
  5046.5  339.24  5052.1  341.02  5063.4  344.00  5158.9  345.10  5165.4  345.26
  5200.2  347.32  5212.3  347.06  5223.0  348.13  5269.5  349.65  5344.1  352.89
#Mann=8,-1,0
  4704.3    0.12       0  4947.4    0.05       0  5010.3    0.05       0
  5014.3    0.05       0  5052.1    0.12       0  5158.9   0.035       0
  5165.4    0.05       0  5269.5   0.035       0
Bank Sta=5010.3,5014.3
Exp/Cntr=0.3,0.1

Type RM Length L Ch R = 1,465,0,0,0
BEGIN DESCRIPTION:
Twin Creek138464.916
END DESCRIPTION:
XS GIS Cut Line= 3
      2700873.80      6813778.28      2700925.54      6814283.84
      2701318.86      6814006.97
#Sta/Elev= 30
  4491.8  364.31  4612.3  355.31  4625.2  353.62  4635.3  354.30  4711.0  349.13
  4786.0  345.35  4806.2  341.79  4816.2  338.59  4826.3  340.10  4846.4  338.41
  4854.3  341.82  4866.5  341.81  4977.0  339.98  4996.1  336.89  5010.1  337.58
  5014.3  336.56  5014.5  336.06  5018.3  336.56  5025.0  338.19  5031.1  336.86
  5034.3  338.08  5037.3  339.23  5066.8  340.75  5146.9  340.30  5153.0  341.38
  5286.0  344.50  5318.5  345.61  5331.6  344.98  5403.6  349.09  5481.0  352.59
#Mann=8,-1,0
  4491.8    0.12       0  4612.3    0.16       0  4711.0    0.07       0
  5014.3    0.07       0  5018.3    0.07       0  5034.3    0.05       0
  5286.0   0.035       0  5403.6    0.05       0
Bank Sta=5014.3,5018.3
Exp/Cntr=0.3,0.1

Chan Stop Cuts=-1