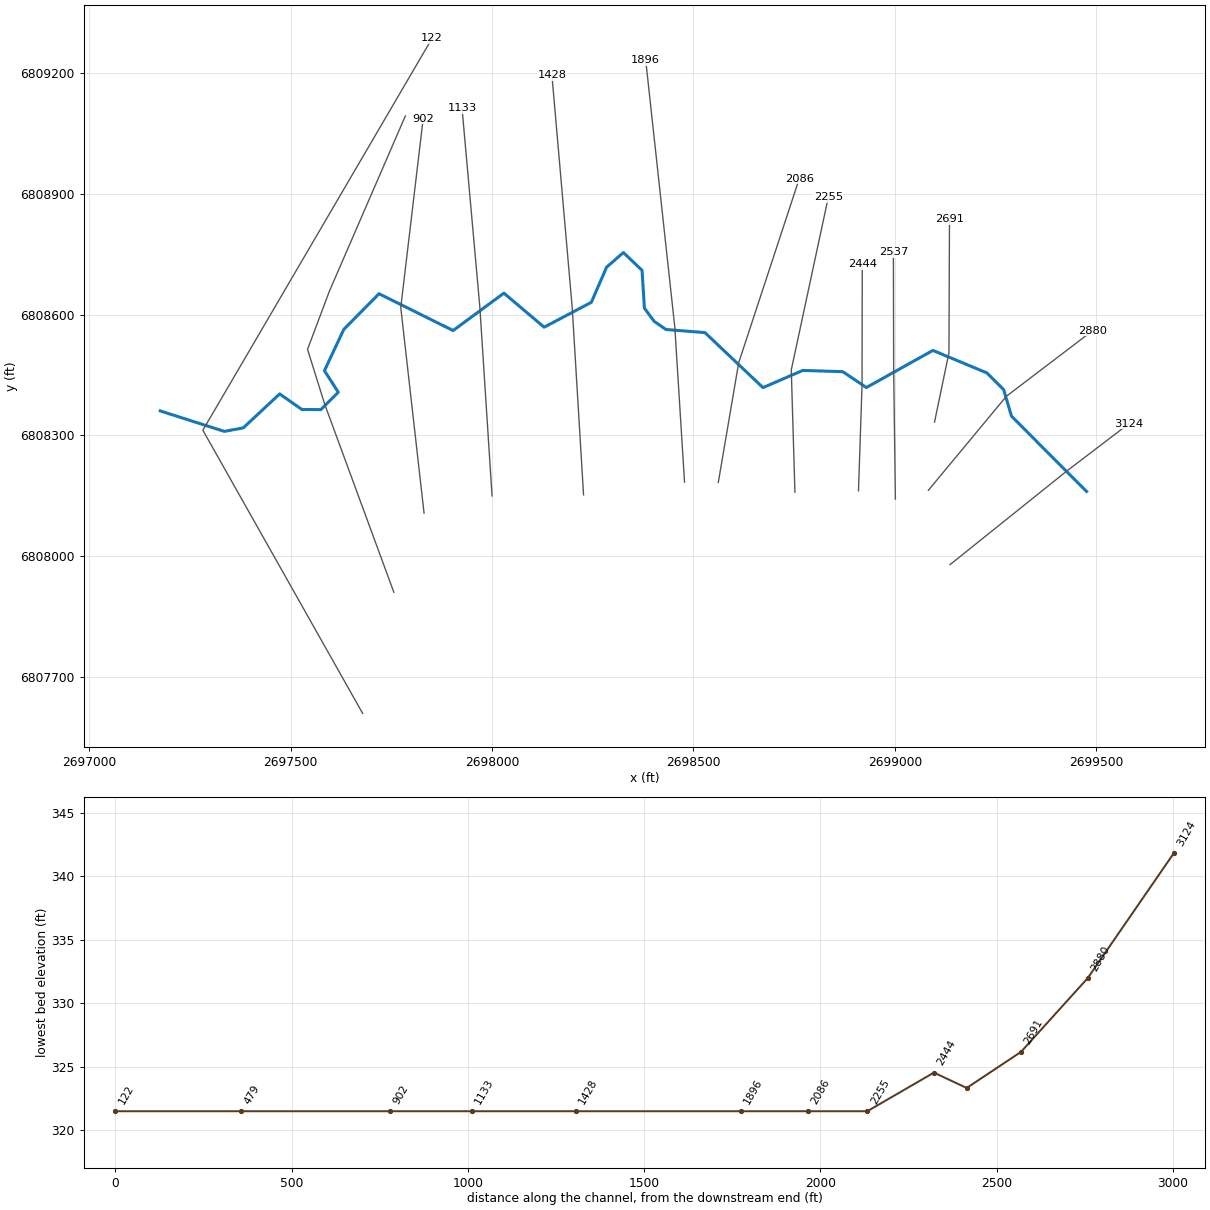
--- Twin Creek141.prj (project) ---

Proj Title=Twin Creek141 Base Level Engineering
Current Plan=p01
Default Exp/Contr=0.3,0.1
English Units
Geom File=g01
Flow File=f01
Plan File=p01
BEGIN DESCRIPTION:
Twin Creek141
END DESCRIPTION:

--- Twin Creek141.p01 (plan) ---

Plan Title=Multiple Run
Short Identifier=Multiple
Geom File=g01
Flow File=f01
Subcritical Flow
K Sum by GR= 0
Std Step Tol= 0.01
Critical Tol= 0.01
Num of Std Step Trials= 20
Max Error Tol= 0.3
Flow Tol Ratio= 0.001
Split Flow NTrial= 30
Split Flow Tol= 0.02
Split Flow Ratio= 0.02
Log Output Level= 0
Friction Slope Method= 1
Unsteady Friction Slope Method= 2
Unsteady Bridges Friction Slope Method= 1
Parabolic Critical Depth
Global Vel Dist=  1 , 1 , 1
Global Log Level= 0
CheckData=True
Encroach Param= -1, 0, 0, 0
BEGIN DESCRIPTION:
Multiple Run
END DESCRIPTION:

--- Twin Creek141.f01 (steady flow) ---

Flow Title=Multiple
Number of Profiles=7
Profile Names=10-year,25-year,50-year,1pct_min,100-year,1pct_plu,500-year
River Rch & RM= Twin Creek141,Reach-1,3124
     277     353     410     237     474     945     630
Boundary for River Rch & Prof#=Twin Creek141,Reach-1,1
Up Type=0
Dn Type=3
Dn Slope=0.005
Boundary for River Rch & Prof#=Twin Creek141,Reach-1,2
Up Type=0
Dn Type=3
Dn Slope=0.005
Boundary for River Rch & Prof#=Twin Creek141,Reach-1,3
Up Type=0
Dn Type=3
Dn Slope=0.005
Boundary for River Rch & Prof#=Twin Creek141,Reach-1,4
Up Type=0
Dn Type=3
Dn Slope=0.005
Boundary for River Rch & Prof#=Twin Creek141,Reach-1,5
Up Type=0
Dn Type=3
Dn Slope=0.005
Boundary for River Rch & Prof#=Twin Creek141,Reach-1,6
Up Type=0
Dn Type=3
Dn Slope=0.005
Boundary for River Rch & Prof#=Twin Creek141,Reach-1,7
Up Type=0
Dn Type=3
Dn Slope=0.005

--- Twin Creek141.g01 (geometry) ---

Geom Title=Existing Conditions

River Reach=Twin Creek141,Reach-1
Reach XY= 30
      2699476.00      6808161.00      2699289.64      6808347.80
      2699270.25      6808413.54      2699228.55      6808455.27
      2699094.43      6808511.20      2698929.32      6808419.04
      2698870.55      6808458.43      2698771.28      6808461.46
      2698672.58      6808418.80      2698528.42      6808555.47
      2698431.69      6808563.07      2698401.99      6808583.68
      2698378.18      6808616.28      2698372.37      6808710.00
      2698326.03      6808754.12      2698284.19      6808717.70
      2698246.47      6808630.62      2698129.23      6808568.85
      2698029.34      6808653.37      2697903.23      6808560.52
      2697719.25      6808651.90      2697631.81      6808563.32
      2697583.78      6808460.90      2697618.11      6808407.34
      2697574.82      6808364.16      2697527.71      6808364.59
      2697472.60      6808403.16      2697382.17      6808318.80
      2697335.16      6808310.17      2697176.00      6808361.00

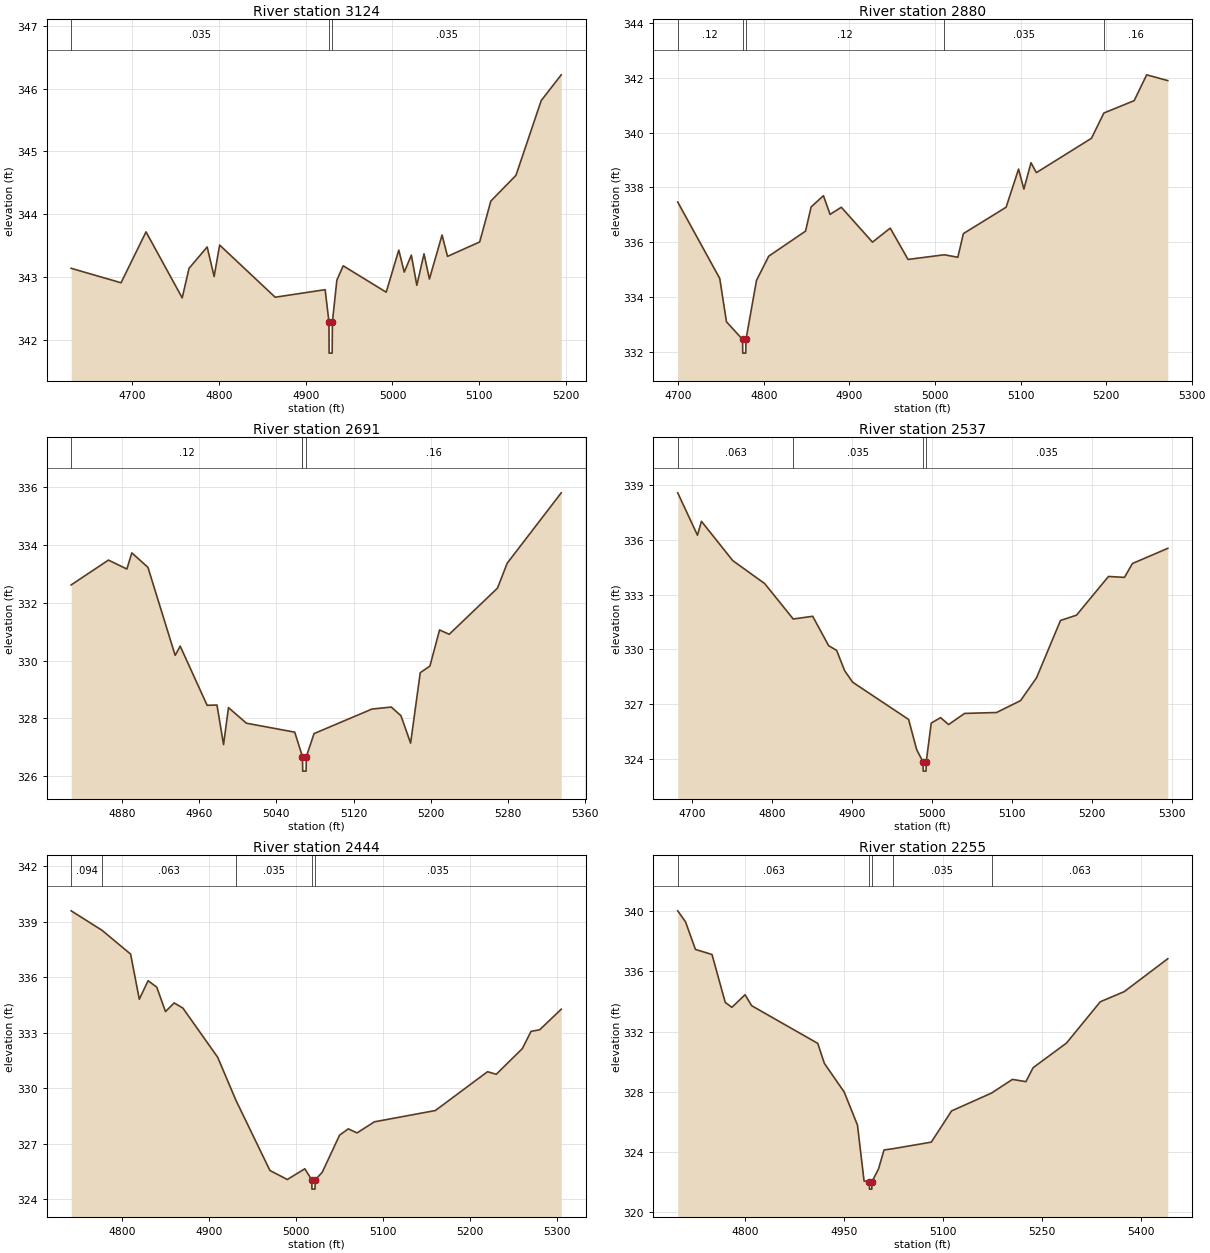
Type RM Length L Ch R = 1,3124,244,244,244
BEGIN DESCRIPTION:
Twin Creek1413123.609
END DESCRIPTION:
XS GIS Cut Line= 3
      2699136.99      6807979.31      2699426.00      6808211.00
      2699580.75      6808328.97
#Sta/Elev= 30
  4629.6  343.14  4687.1  342.91  4715.9  343.72  4757.6  342.67  4765.5  343.14
  4786.4  343.48  4794.4  343.01  4800.8  343.51  4864.8  342.68  4922.4  342.80
  4926.8  342.29  4927.0  341.79  4930.5  341.79  4930.8  342.29  4935.9  342.95
  4943.2  343.18  4992.8  342.76  5007.3  343.43  5013.6  343.08  5021.8  343.35
  5028.1  342.87  5036.4  343.37  5042.6  342.97  5057.2  343.67  5063.5  343.33
  5100.6  343.56  5113.4  344.21  5142.4  344.62  5171.5  345.81  5194.6  346.22
#Mann=3,-1,0
  4629.6   0.035       0  4926.8   0.035       0  4930.8   0.035       0
Bank Sta=4926.8,4930.8
Exp/Cntr=0.3,0.1

Type RM Length L Ch R = 1,2880,189,189,189
BEGIN DESCRIPTION:
Twin Creek1412879.48
END DESCRIPTION:
XS GIS Cut Line= 3
      2699083.22      6808163.85      2699277.04      6808397.46
      2699491.35      6808560.47
#Sta/Elev= 30
  4699.3  337.47  4748.4  334.69  4756.3  333.11  4775.1  332.47  4775.3  331.97
  4778.8  331.97  4779.1  332.47  4791.4  334.62  4805.7  335.50  4848.7  336.41
  4855.2  337.29  4869.6  337.70  4877.4  337.02  4890.5  337.28  4926.9  336.01
  4947.7  336.52  4968.5  335.38  5010.8  335.55  5026.7  335.46  5033.2  336.32
  5083.1  337.28  5097.7  338.67  5103.9  337.94  5112.2  338.90  5118.5  338.54
  5182.9  339.79  5197.4  340.71  5232.8  341.16  5247.4  342.10  5272.1  341.89
#Mann=5,-1,0
  4699.3    0.12       0  4775.1    0.07       0  4779.1    0.12       0
  5010.8   0.035       0  5197.4    0.16       0
Bank Sta=4775.1,4779.1
Exp/Cntr=0.3,0.1

Type RM Length L Ch R = 1,2691,154,154,154
BEGIN DESCRIPTION:
Twin Creek1412691.33
END DESCRIPTION:
XS GIS Cut Line= 3
      2699098.50      6808333.18      2699134.33      6808505.43
      2699135.66      6808837.00
#Sta/Elev= 30
  4827.6  332.62  4866.2  333.48  4885.3  333.17  4890.4  333.73  4907.1  333.23
  4935.3  330.18  4940.5  330.50  4968.4  328.45  4978.6  328.46  4985.4  327.09
  4990.5  328.37  5009.1  327.83  5059.1  327.52  5066.3  326.76  5067.1  326.67
  5067.4  326.17  5070.9  326.17  5071.1  326.67  5079.1  327.47  5139.1  328.32
  5159.1  328.39  5169.1  328.09  5179.1  327.14  5189.1  329.58  5199.1  329.81
  5209.1  331.06  5219.1  330.91  5269.1  332.51  5279.1  333.37  5335.1  335.81
#Mann=4,-1,0
  4827.6    0.12       0  5066.3    0.16       0  5067.1    0.07       0
  5071.1    0.16       0
Bank Sta=5067.1,5071.1
Exp/Cntr=0.3,0.1

Type RM Length L Ch R = 1,2537,93,93,93
BEGIN DESCRIPTION:
Twin Creek1412536.64
END DESCRIPTION:
XS GIS Cut Line= 3
      2699001.34      6808142.19      2698997.07      6808462.51
      2698996.36      6808755.16
#Sta/Elev= 30
  4681.6  338.57  4706.3  336.25  4711.3  337.01  4750.4  334.86  4790.4  333.60
  4826.1  331.66  4850.4  331.81  4870.4  330.20  4880.4  329.94  4890.4  328.83
  4900.4  328.20  4970.4  326.16  4980.4  324.52  4988.4  323.83  4988.7  323.33
  4992.2  323.33  4992.4  323.83  4998.7  325.96  5010.4  326.26  5020.4  325.88
  5040.4  326.49  5080.4  326.54  5110.4  327.19  5130.4  328.44  5160.4  331.58
  5180.4  331.87  5220.4  333.99  5240.4  333.94  5250.4  334.70  5294.6  335.53
#Mann=4,-1,0
  4681.6   0.063       0  4826.1   0.035       0  4988.4   0.035       0
  4992.4   0.035       0
Bank Sta=4988.4,4992.4
Exp/Cntr=0.3,0.1

Type RM Length L Ch R = 1,2444,189,189,189
BEGIN DESCRIPTION:
Twin Creek1412443.7
END DESCRIPTION:
XS GIS Cut Line= 3
      2698909.71      6808162.70      2698918.52      6808424.37
      2698919.09      6808725.75
#Sta/Elev= 30
  4741.5  339.59  4776.9  338.54  4809.8  337.25  4819.8  334.81  4829.9  335.81
  4839.9  335.46  4849.9  334.14  4859.9  334.61  4869.9  334.33  4909.9  331.67
  4930.8  329.35  4969.9  325.55  4989.9  325.06  5010.0  325.64  5018.0  325.04
  5018.2  324.54  5021.7  324.54  5022.0  325.04  5030.0  325.45  5050.0  327.46
  5060.0  327.80  5070.0  327.58  5090.0  328.18  5160.0  328.79  5220.0  330.89
  5230.0  330.75  5260.0  332.14  5270.0  333.07  5280.0  333.16  5304.7  334.27
#Mann=5,-1,0
  4741.5   0.094       0  4776.9   0.063       0  4930.8   0.035       0
  5018.0   0.035       0  5022.0   0.035       0
Bank Sta=5018,5022
Exp/Cntr=0.3,0.1

Type RM Length L Ch R = 1,2255,169,169,169
BEGIN DESCRIPTION:
Twin Creek1412254.63
END DESCRIPTION:
XS GIS Cut Line= 3
      2698751.90      6808159.17      2698742.86      6808462.84
      2698834.68      6808890.89
#Sta/Elev= 30
  4698.5  340.04  4710.3  339.31  4725.3  337.47  4750.4  337.13  4770.4  333.94
  4780.4  333.61  4800.4  334.45  4810.4  333.72  4910.4  331.21  4920.4  329.88
  4950.4  327.97  4970.5  325.77  4980.5  322.04  4988.5  322.00  4988.7  321.50
  4992.2  321.50  4992.5  322.00  5002.3  322.84  5010.7  324.11  5023.9  324.19
  5082.2  324.63  5112.9  326.71  5173.4  327.90  5205.0  328.81  5225.4  328.66
  5236.3  329.59  5286.8  331.23  5337.9  333.98  5374.3  334.66  5440.1  336.85
#Mann=5,-1,0
  4698.5   0.063       0  4988.5   0.063       0  4992.5   0.063       0
  5023.9   0.035       0  5173.4   0.063       0
Bank Sta=4988.5,4992.5
Exp/Cntr=0.3,0.1

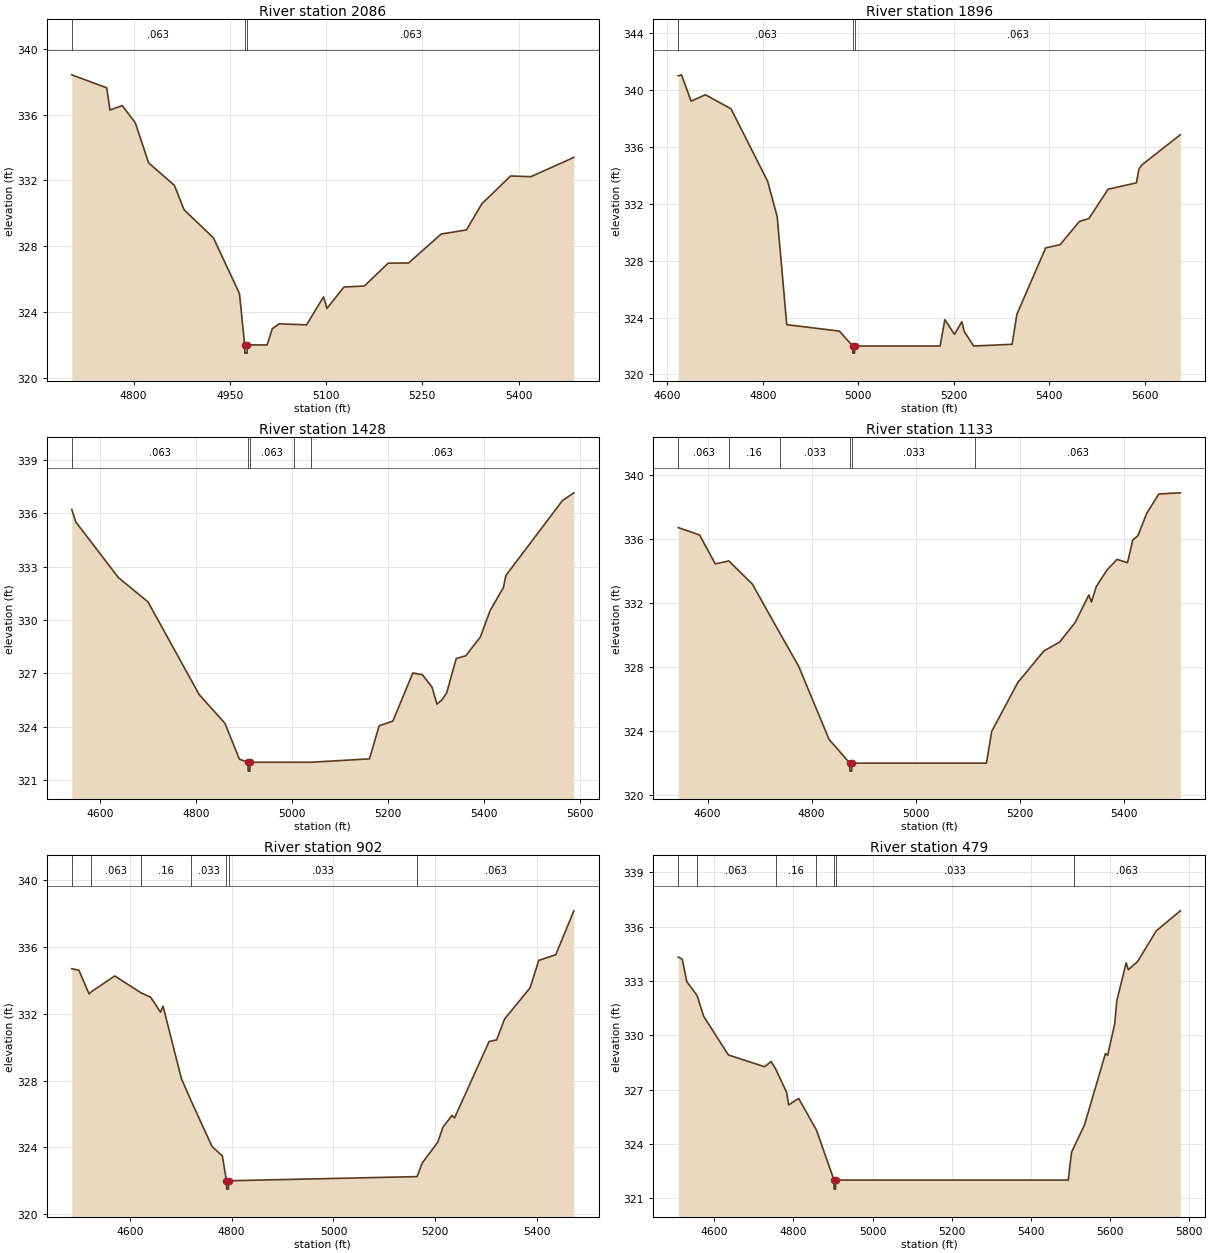
Type RM Length L Ch R = 1,2086,190,190,190
BEGIN DESCRIPTION:
Twin Creek1412086.37
END DESCRIPTION:
XS GIS Cut Line= 3
      2698561.66      6808183.41      2698612.32      6808480.69
      2698762.59      6808937.34
#Sta/Elev= 30
  4703.8  338.42  4758.3  337.63  4763.3  336.28  4782.5  336.55  4802.8  335.50
  4823.5  333.07  4863.7  331.70  4878.7  330.22  4924.5  328.51  4965.1  325.12
  4973.2  322.00  4973.5  321.50  4977.0  321.50  4977.2  322.00  5008.2  322.00
  5016.2  322.98  5026.7  323.28  5069.6  323.22  5096.1  324.92  5101.4  324.22
  5127.9  325.52  5159.7  325.58  5196.8  326.97  5228.6  326.98  5279.4  328.74
  5318.7  328.99  5342.6  330.57  5387.5  332.27  5419.3  332.23  5486.1  333.40
#Mann=3,-1,0
  4703.8   0.063       0  4973.2   0.063       0  4977.2   0.063       0
Bank Sta=4973.2,4977.2
Exp/Cntr=0.3,0.1

Type RM Length L Ch R = 1,1896,468,468,468
BEGIN DESCRIPTION:
Twin Creek1411895.79
END DESCRIPTION:
XS GIS Cut Line= 3
      2698477.83      6808184.08      2698453.75      6808568.04
      2698381.48      6809231.40
#Sta/Elev= 30
  4622.5  340.99  4629.4  341.06  4649.5  339.21  4679.5  339.66  4733.1  338.67
  4809.8  333.58  4829.8  331.10  4849.9  323.50  4960.1  323.05  4988.1  322.00
  4988.4  321.50  4991.9  321.50  4992.1  322.00  5171.1  322.00  5181.2  323.85
  5201.3  322.82  5216.8  323.71  5221.9  323.01  5241.5  322.00  5322.0  322.12
  5332.1  324.23  5392.4  328.90  5422.6  329.12  5462.9  330.75  5483.0  330.96
  5523.2  333.02  5582.6  333.47  5587.6  334.42  5593.6  334.72  5674.5  336.85
#Mann=3,-1,0
  4622.5   0.063       0  4988.1   0.063       0  4992.1   0.063       0
Bank Sta=4988.1,4992.1
Exp/Cntr=0.3,0.1

Type RM Length L Ch R = 1,1428,295,295,295
BEGIN DESCRIPTION:
Twin Creek1411428.15
END DESCRIPTION:
XS GIS Cut Line= 3
      2698227.08      6808152.55      2698199.00      6808616.86
      2698148.50      6809195.00
#Sta/Elev= 30
  4541.1  336.21  4549.6  335.51  4638.3  332.38  4699.8  331.02  4806.3  325.81
  4860.1  324.19  4890.2  322.17  4908.2  322.00  4908.5  321.50  4912.0  321.50
  4912.2  322.00  5004.1  322.00  5039.2  322.00  5161.0  322.19  5181.1  324.05
  5209.6  324.31  5251.3  327.02  5271.4  326.92  5291.5  326.21  5301.5  325.27
  5311.6  325.50  5321.6  325.89  5341.7  327.83  5361.7  327.99  5391.9  329.04
  5411.9  330.51  5440.0  331.83  5445.0  332.50  5562.7  336.71  5586.6  337.15
#Mann=5,-1,0
  4541.1   0.063       0  4908.2   0.063       0  4912.2   0.063       0
  5004.1   0.033       0  5039.2   0.063       0
Bank Sta=4908.2,4912.2
Exp/Cntr=0.3,0.1

Type RM Length L Ch R = 1,1133,231,231,231
BEGIN DESCRIPTION:
Twin Creek1411132.75
END DESCRIPTION:
XS GIS Cut Line= 3
      2697999.95      6808150.02      2697969.55      6808619.49
      2697925.39      6809112.06
#Sta/Elev= 30
  4543.7  336.69  4584.8  336.23  4614.8  334.43  4641.0  334.61  4686.1  333.17
  4739.0  330.11  4775.2  328.04  4833.6  323.48  4873.4  322.00  4873.6  321.50
  4877.1  321.50  4877.4  322.00  5114.9  322.00  5136.1  322.00  5146.2  323.98
  5196.4  327.03  5246.6  329.00  5276.7  329.55  5306.8  330.78  5332.9  332.49
  5337.9  332.05  5347.0  333.00  5367.1  334.02  5387.2  334.71  5407.2  334.50
  5417.3  335.92  5427.3  336.19  5444.1  337.58  5467.5  338.79  5508.7  338.86
#Mann=6,-1,0
  4543.7   0.063       0  4641.0    0.16       0  4739.0   0.033       0
  4873.4   0.033       0  4877.4   0.033       0  5114.9   0.063       0
Bank Sta=4873.4,4877.4
Exp/Cntr=0.3,0.1

Type RM Length L Ch R = 1,902,423,423,423
BEGIN DESCRIPTION:
Twin Creek141901.94
END DESCRIPTION:
XS GIS Cut Line= 3
      2697831.08      6808107.23      2697773.28      6808617.67
      2697828.89      6809086.28
#Sta/Elev= 30
  4486.3  334.70  4500.2  334.62  4520.3  333.19  4524.5  333.32  4570.6  334.27
  4622.8  333.25  4641.1  333.00  4660.5  332.10  4665.5  332.46  4701.4  328.13
  4721.1  326.75  4761.8  324.05  4781.9  323.49  4790.0  322.00  4790.3  321.50
  4793.8  321.50  4794.0  322.00  5164.1  322.25  5174.5  323.08  5204.8  324.31
  5214.8  325.20  5232.6  325.92  5237.6  325.76  5305.5  330.34  5320.3  330.44
  5335.7  331.68  5386.0  333.56  5403.0  335.20  5436.4  335.54  5471.9  338.17
#Mann=7,-1,0
  4486.3    0.16       0  4524.5   0.063       0  4622.8    0.16       0
  4721.1   0.033       0  4790.0   0.033       0  4794.0   0.033       0
  5164.1   0.063       0
Bank Sta=4790,4794
Exp/Cntr=0.3,0.1

Type RM Length L Ch R = 1,479,357,357,357
BEGIN DESCRIPTION:
Twin Creek141479.23
END DESCRIPTION:
XS GIS Cut Line= 5
      2697756.10      6807910.70      2697584.59      6808377.05
      2697541.82      6808513.76      2697595.93      6808657.85
      2697784.64      6809093.26
#Sta/Elev= 30
  4509.1  334.32  4519.3  334.20  4530.7  332.96  4556.9  332.19  4573.4  331.04
  4635.9  328.91  4727.3  328.26  4743.8  328.55  4755.0  328.15  4782.9  326.85
  4788.2  326.15  4813.3  326.51  4858.4  324.76  4902.7  322.00  4903.0  321.50
  4906.5  321.50  4906.7  322.00  5494.6  322.00  5502.8  323.53  5510.2  323.88
  5535.5  325.04  5588.5  328.99  5594.0  328.89  5611.8  330.61  5617.4  331.91
  5640.9  334.00  5646.4  333.62  5669.8  334.07  5716.8  335.76  5777.7  336.87
#Mann=7,-1,0
  4509.1    0.16       0  4556.9   0.063       0  4755.0    0.16       0
  4858.4   0.033       0  4902.7   0.033       0  4906.7   0.033       0
  5510.2   0.063       0
Bank Sta=4902.7,4906.7
Exp/Cntr=0.3,0.1

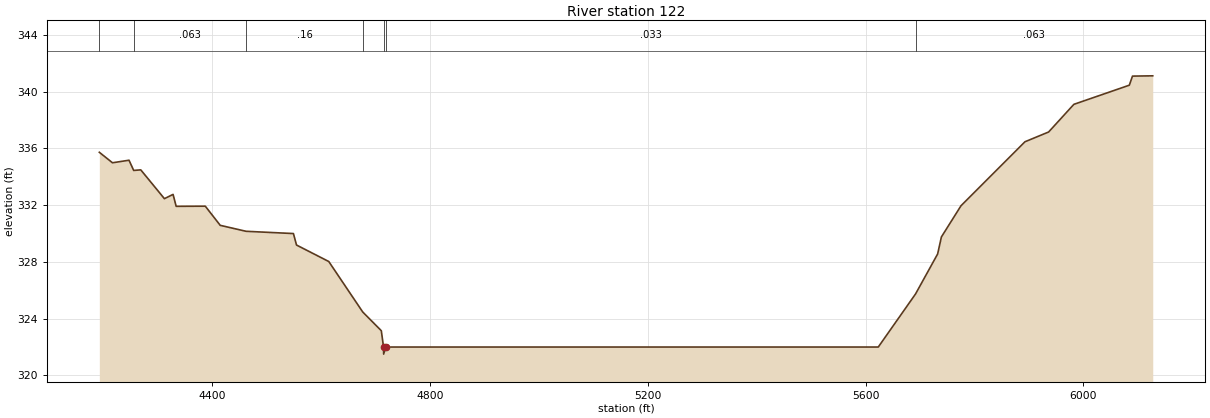
Type RM Length L Ch R = 1,122,0,0,0
BEGIN DESCRIPTION:
Twin Creek141122.097
END DESCRIPTION:
XS GIS Cut Line= 3
      2697678.62      6807610.02      2697281.92      6808313.02
      2697851.01      6809286.02
#Sta/Elev= 30
  4192.8  335.73  4216.9  334.99  4247.3  335.17  4255.9  334.45  4268.9  334.49
  4312.3  332.46  4328.2  332.76  4333.9  331.92  4387.4  331.93  4414.8  330.58
  4462.2  330.16  4549.2  330.00  4554.9  329.19  4614.1  328.03  4676.5  324.47
  4710.6  323.15  4714.7  322.00  4714.9  321.50  4718.7  322.00  5623.2  322.00
  5691.6  325.74  5732.2  328.56  5739.1  329.76  5775.1  331.96  5892.5  336.47
  5936.0  337.16  5982.4  339.11  6084.2  340.46  6090.0  341.10  6127.2  341.12
#Mann=7,-1,0
  4192.8    0.16       0  4255.9   0.063       0  4462.2    0.16       0
  4676.5   0.033       0  4714.7   0.033       0  4718.7   0.033       0
  5691.6   0.063       0
Bank Sta=4714.7,4718.7
Exp/Cntr=0.3,0.1

Chan Stop Cuts=-1