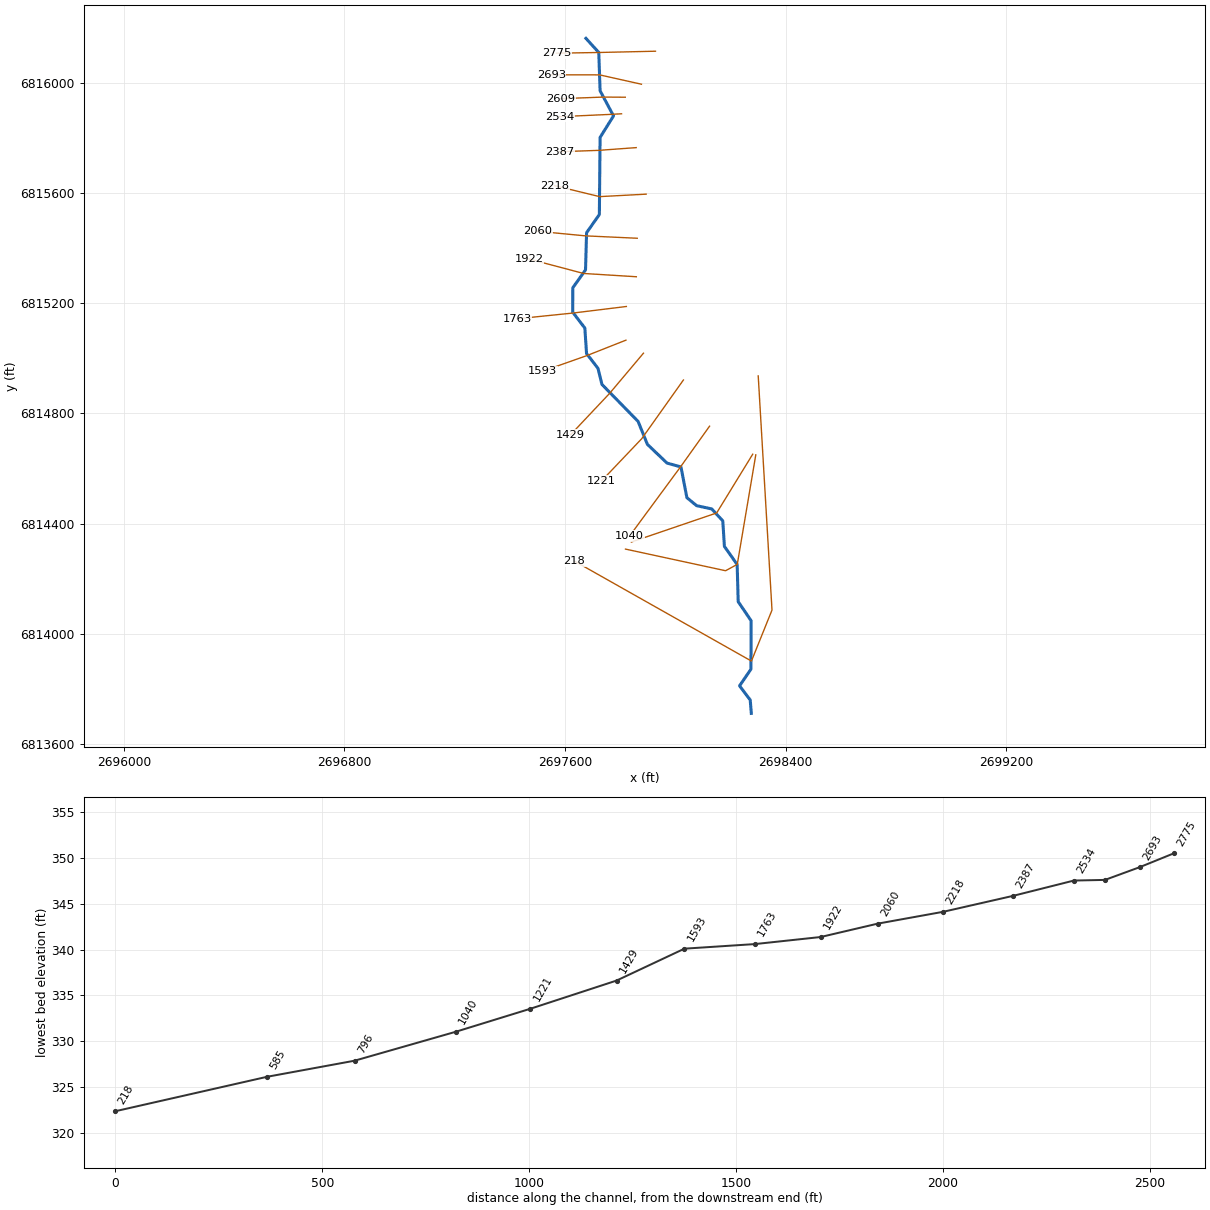
--- Twin Creek142.prj (project) ---

Proj Title=Twin Creek142 Base Level Engineering
Current Plan=p01
Default Exp/Contr=0.3,0.1
English Units
Geom File=g01
Flow File=f01
Plan File=p01
BEGIN DESCRIPTION:
Twin Creek142
END DESCRIPTION:

--- Twin Creek142.p01 (plan) ---

Plan Title=Multiple Run
Short Identifier=Multiple
Geom File=g01
Flow File=f01
Subcritical Flow
K Sum by GR= 0
Std Step Tol= 0.01
Critical Tol= 0.01
Num of Std Step Trials= 20
Max Error Tol= 0.3
Flow Tol Ratio= 0.001
Split Flow NTrial= 30
Split Flow Tol= 0.02
Split Flow Ratio= 0.02
Log Output Level= 0
Friction Slope Method= 1
Unsteady Friction Slope Method= 2
Unsteady Bridges Friction Slope Method= 1
Parabolic Critical Depth
Global Vel Dist=  1 , 1 , 1
Global Log Level= 0
CheckData=True
Encroach Param= -1, 0, 0, 0
BEGIN DESCRIPTION:
Multiple Run
END DESCRIPTION:

--- Twin Creek142.f01 (steady flow) ---

Flow Title=Multiple
Number of Profiles=7
Profile Names=10-year,25-year,50-year,1pct_min,100-year,1pct_plu,500-year
River Rch & RM= Twin Creek142,Reach-1,2775
     130     156     175      98     195     389     242
Boundary for River Rch & Prof#=Twin Creek142,Reach-1,1
Up Type=0
Dn Type=3
Dn Slope=0.005
Boundary for River Rch & Prof#=Twin Creek142,Reach-1,2
Up Type=0
Dn Type=3
Dn Slope=0.005
Boundary for River Rch & Prof#=Twin Creek142,Reach-1,3
Up Type=0
Dn Type=3
Dn Slope=0.005
Boundary for River Rch & Prof#=Twin Creek142,Reach-1,4
Up Type=0
Dn Type=3
Dn Slope=0.005
Boundary for River Rch & Prof#=Twin Creek142,Reach-1,5
Up Type=0
Dn Type=3
Dn Slope=0.005
Boundary for River Rch & Prof#=Twin Creek142,Reach-1,6
Up Type=0
Dn Type=3
Dn Slope=0.005
Boundary for River Rch & Prof#=Twin Creek142,Reach-1,7
Up Type=0
Dn Type=3
Dn Slope=0.005

--- Twin Creek142.g01 (geometry) ---

Geom Title=Existing Conditions

River Reach=Twin Creek142,Reach-1
Reach XY= 30
      2697676.00      6816161.00      2697722.70      6816109.63
      2697727.41      6815970.66      2697776.18      6815879.43
      2697727.40      6815801.35      2697724.78      6815521.50
      2697678.39      6815455.47      2697674.61      6815320.67
      2697628.29      6815255.43      2697628.17      6815166.97
      2697672.14      6815109.40      2697678.33      6815016.97
      2697719.86      6814963.17      2697734.14      6814904.94
      2697865.22      6814770.68      2697899.00      6814687.49
      2697970.28      6814619.30      2698020.74      6814605.52
      2698042.32      6814493.90      2698077.44      6814464.89
      2698132.35      6814452.97      2698172.48      6814409.72
      2698178.36      6814316.98      2698224.61      6814251.33
      2698228.39      6814116.53      2698275.32      6814047.08
      2698274.63      6813871.43      2698233.31      6813810.96
      2698272.00      6813759.64      2698276.00      6813711.00

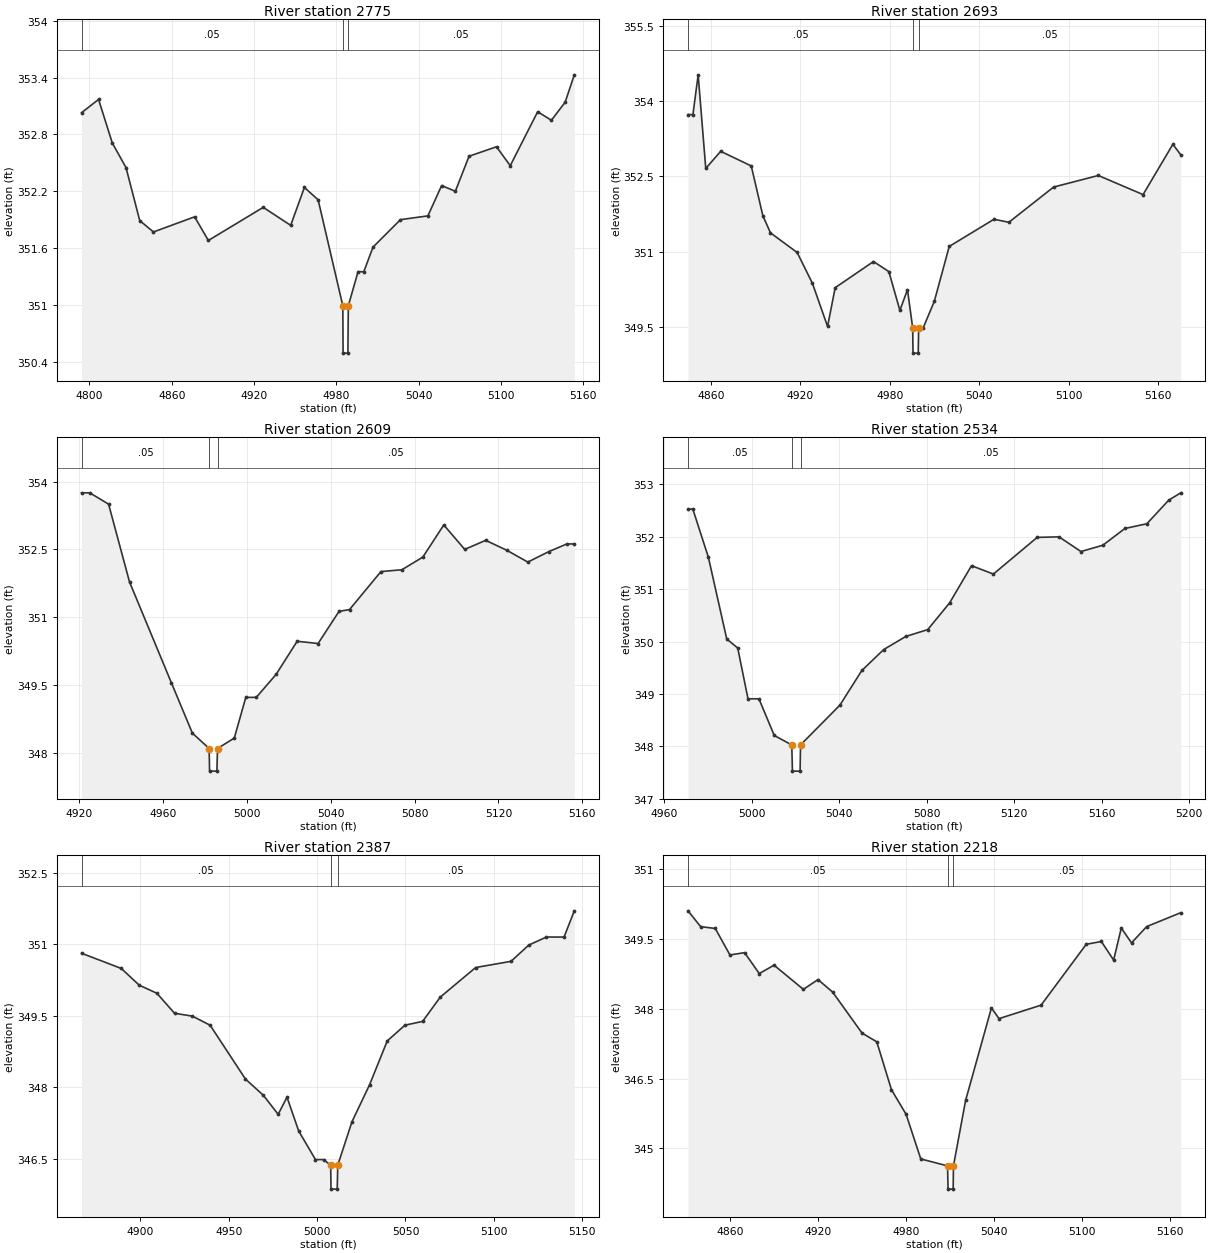
Type RM Length L Ch R = 1,2775,82,82,82
BEGIN DESCRIPTION:
Twin Creek1422774.631
END DESCRIPTION:
XS GIS Cut Line= 3
      2697928.35      6816114.24      2697722.70      6816109.63
      2697569.32      6816107.03
#Sta/Elev= 30
  4794.3  353.03  4806.7  353.17  4816.7  352.71  4826.7  352.45  4836.7  351.89
  4846.7  351.77  4876.7  351.93  4886.7  351.68  4926.7  352.03  4946.7  351.84
  4956.7  352.24  4966.7  352.11  4984.7  350.99  4984.9  350.49  4988.4  350.49
  4988.7  350.99  4995.8  351.35  5000.0  351.35  5006.7  351.61  5026.7  351.90
  5046.7  351.94  5056.7  352.26  5066.7  352.20  5076.7  352.57  5096.7  352.67
  5106.7  352.47  5126.7  353.04  5136.7  352.95  5146.7  353.14  5153.4  353.43
#Mann=3,-1,0
  4794.3    0.05       0  4984.7    0.05       0  4988.7    0.05       0
Bank Sta=4984.7,4988.7
Exp/Cntr=0.3,0.1

Type RM Length L Ch R = 1,2693,84,84,84
BEGIN DESCRIPTION:
Twin Creek1422684.99
END DESCRIPTION:
XS GIS Cut Line= 3
      2697877.42      6815994.47      2697725.86      6816028.37
      2697550.66      6816028.68
#Sta/Elev= 30
  4844.7  353.73  4848.0  353.73  4851.5  354.52  4856.6  352.66  4866.6  353.00
  4887.1  352.71  4894.9  351.72  4900.0  351.38  4917.9  350.99  4928.1  350.38
  4938.3  349.52  4943.4  350.29  4969.1  350.81  4979.4  350.61  4986.8  349.84
  4991.9  350.25  4995.4  349.49  4995.6  348.99  4999.1  348.99  4999.4  349.49
  5002.4  349.49  5009.9  350.02  5019.9  351.11  5049.9  351.65  5059.9  351.59
  5089.9  352.29  5119.9  352.52  5149.9  352.14  5169.9  353.14  5175.2  352.93
#Mann=3,-1,0
  4844.7    0.05       0  4995.4    0.05       0  4999.4    0.05       0
Bank Sta=4995.4,4999.4
Exp/Cntr=0.3,0.1

Type RM Length L Ch R = 1,2609,75,75,75
BEGIN DESCRIPTION:
Twin Creek1422601.24
END DESCRIPTION:
XS GIS Cut Line= 3
      2697818.86      6815947.27      2697739.87      6815947.83
      2697583.78      6815941.98
#Sta/Elev= 29
  4921.0  353.75  4924.9  353.75  4933.9  353.50  4943.9  351.78  4963.9  349.55
  4973.9  348.44  4981.9  348.10  4982.1  347.60  4985.6  347.60  4985.9  348.10
  4993.9  348.33  4999.4  349.23  5004.4  349.23  5013.9  349.74  5023.9  350.47
  5033.9  350.42  5043.9  351.13  5048.9  351.17  5063.9  352.01  5073.9  352.05
  5083.9  352.33  5093.9  353.04  5103.9  352.50  5113.9  352.70  5124.0  352.48
  5134.0  352.22  5144.0  352.45  5152.6  352.62  5156.2  352.62
#Mann=3,-1,0
  4921.0    0.05       0  4981.9    0.05       0  4985.9    0.05       0
Bank Sta=4981.9,4985.9
Exp/Cntr=0.3,0.1

Type RM Length L Ch R = 1,2534,147,147,147
BEGIN DESCRIPTION:
Twin Creek1422533.83
END DESCRIPTION:
XS GIS Cut Line= 3
      2697805.33      6815887.22      2697775.03      6815885.45
      2697580.48      6815876.65
#Sta/Elev= 28
  4971.0  352.53  4973.2  352.53  4980.3  351.61  4988.7  350.05  4993.7  349.88
  4998.4  348.91  5003.4  348.91  5010.4  348.21  5018.4  348.03  5018.7  347.53
  5022.2  347.53  5022.4  348.03  5040.4  348.79  5050.4  349.45  5060.4  349.85
  5070.5  350.10  5080.5  350.23  5090.5  350.74  5100.5  351.45  5110.5  351.29
  5130.5  351.99  5140.5  352.00  5150.5  351.72  5160.5  351.84  5170.6  352.16
  5180.6  352.25  5190.6  352.70  5196.1  352.84
#Mann=3,-1,0
  4971.0    0.05       0  5018.4    0.05       0  5022.4    0.05       0
Bank Sta=5018.4,5022.4
Exp/Cntr=0.3,0.1

Type RM Length L Ch R = 1,2387,169,169,169
BEGIN DESCRIPTION:
Twin Creek1422386.61
END DESCRIPTION:
XS GIS Cut Line= 3
      2697858.48      6815764.38      2697721.99      6815754.38
      2697580.23      6815749.47
#Sta/Elev= 30
  4866.8  350.81  4889.3  350.49  4899.4  350.14  4909.4  349.97  4919.4  349.55
  4929.5  349.49  4939.5  349.30  4959.5  348.17  4969.6  347.83  4978.0  347.43
  4983.0  347.79  4989.6  347.08  4999.1  346.48  5003.7  346.48  5007.7  346.36
  5007.9  345.86  5011.4  345.86  5011.7  346.36  5019.7  347.27  5029.7  348.05
  5039.7  348.97  5049.7  349.30  5059.7  349.38  5069.7  349.89  5089.7  350.51
  5109.7  350.64  5119.7  350.98  5129.7  351.15  5139.7  351.15  5145.5  351.70
#Mann=3,-1,0
  4866.8    0.05       0  5007.7    0.05       0  5011.7    0.05       0
Bank Sta=5007.7,5011.7
Exp/Cntr=0.3,0.1

Type RM Length L Ch R = 1,2218,158,158,158
BEGIN DESCRIPTION:
Twin Creek1422218.47
END DESCRIPTION:
XS GIS Cut Line= 3
      2697894.58      6815595.48      2697725.77      6815586.49
      2697563.38      6815626.07
#Sta/Elev= 30
  4831.4  350.11  4840.0  349.77  4850.0  349.73  4860.0  349.16  4870.0  349.21
  4880.0  348.76  4890.1  348.94  4910.1  348.42  4920.1  348.63  4930.1  348.36
  4950.1  347.48  4960.2  347.29  4970.2  346.26  4980.2  345.73  4990.2  344.77
  5008.5  344.62  5008.8  344.12  5012.3  344.12  5012.5  344.62  5020.8  346.03
  5038.4  348.02  5043.6  347.79  5072.3  348.08  5103.1  349.39  5113.4  349.45
  5121.8  349.05  5127.0  349.74  5134.0  349.42  5144.3  349.77  5167.6  350.07
#Mann=3,-1,0
  4831.4    0.05       0  5008.5    0.05       0  5012.5    0.05       0
Bank Sta=5008.5,5012.5
Exp/Cntr=0.3,0.1

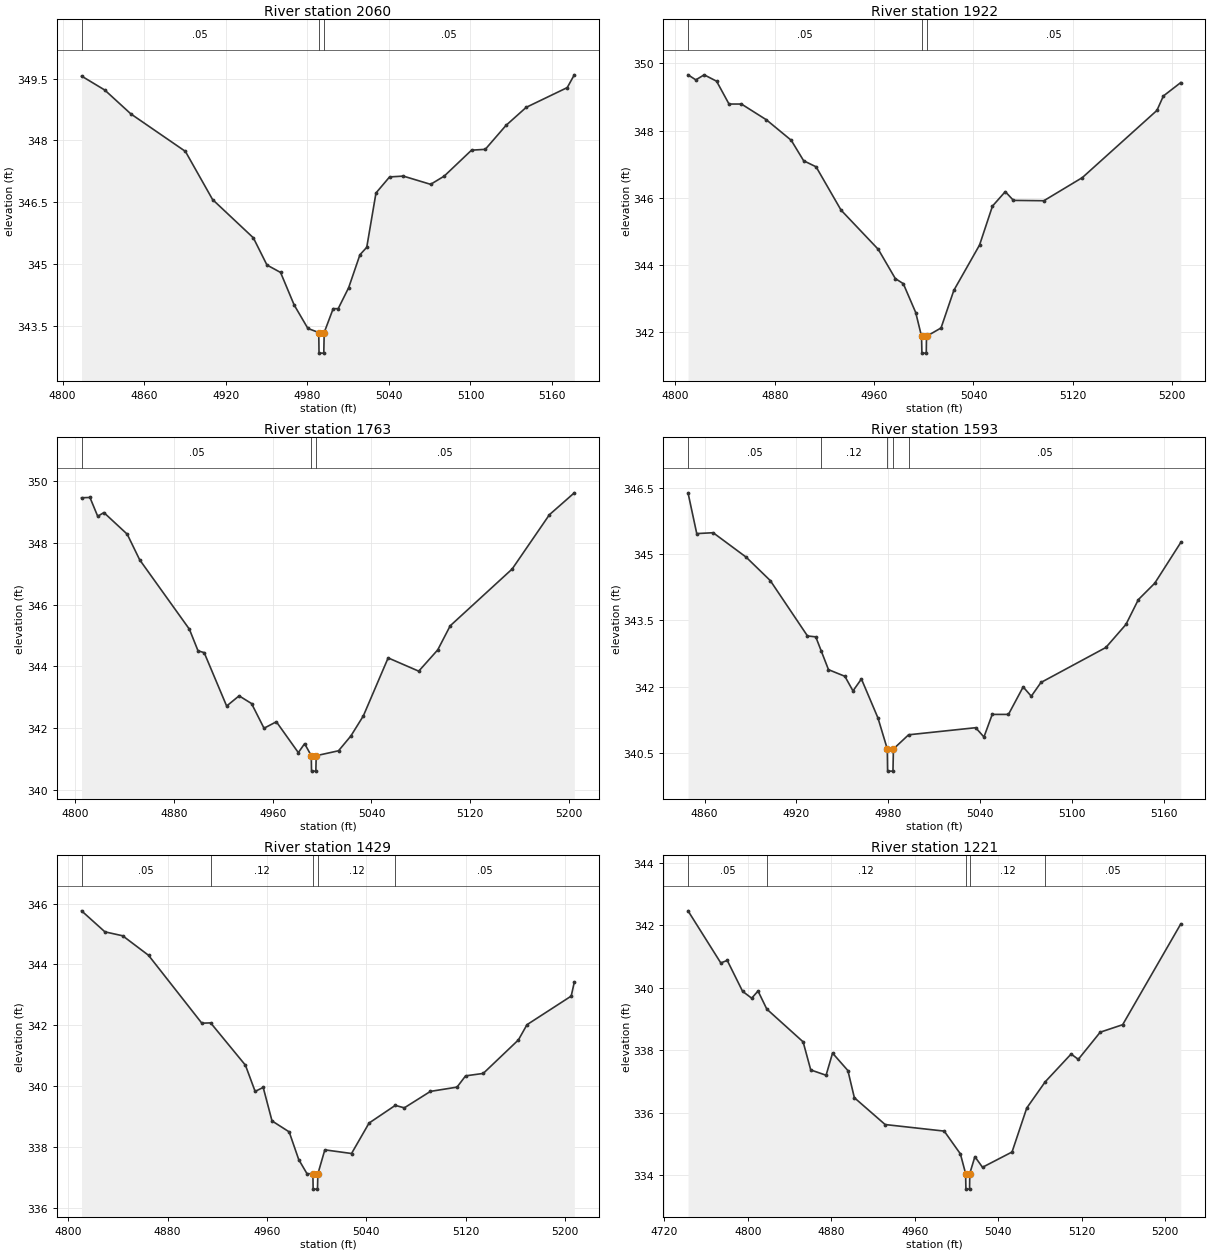
Type RM Length L Ch R = 1,2060,138,138,138
BEGIN DESCRIPTION:
Twin Creek1422059.88
END DESCRIPTION:
XS GIS Cut Line= 3
      2697862.27      6815435.40      2697673.66      6815444.15
      2697500.77      6815460.80
#Sta/Elev= 30
  4813.9  349.56  4831.0  349.22  4850.2  348.64  4890.3  347.73  4910.3  346.56
  4940.3  345.63  4950.3  344.97  4960.3  344.79  4970.3  344.00  4980.4  343.43
  4988.4  343.33  4988.6  342.83  4992.1  342.83  4992.4  343.33  4999.0  343.91
  5002.7  343.91  5010.4  344.42  5018.7  345.22  5023.7  345.40  5030.5  346.72
  5040.5  347.11  5050.6  347.13  5070.7  346.93  5080.7  347.13  5100.8  347.76
  5110.9  347.78  5126.1  348.36  5141.0  348.80  5171.2  349.28  5176.4  349.59
#Mann=3,-1,0
  4813.9    0.05       0  4988.4    0.05       0  4992.4    0.05       0
Bank Sta=4988.4,4992.4
Exp/Cntr=0.3,0.1

Type RM Length L Ch R = 1,1922,159,159,159
BEGIN DESCRIPTION:
Twin Creek1421922.2
END DESCRIPTION:
XS GIS Cut Line= 3
      2697858.93      6815295.71      2697667.54      6815307.64
      2697469.44      6815360.10
#Sta/Elev= 30
  4810.2  349.66  4816.5  349.51  4823.2  349.66  4833.2  349.47  4843.2  348.79
  4853.2  348.79  4873.3  348.32  4893.3  347.71  4903.3  347.10  4913.3  346.92
  4933.4  345.63  4963.4  344.46  4977.1  343.59  4983.5  343.44  4993.5  342.58
  4998.2  341.87  4998.5  341.37  5002.0  341.37  5002.2  341.87  5013.9  342.12
  5024.2  343.24  5044.9  344.59  5055.3  345.75  5065.6  346.18  5072.2  345.92
  5096.7  345.91  5127.7  346.60  5187.7  348.60  5192.9  349.03  5206.9  349.43
#Mann=3,-1,0
  4810.2    0.05       0  4998.2    0.05       0  5002.2    0.05       0
Bank Sta=4998.2,5002.2
Exp/Cntr=0.3,0.1

Type RM Length L Ch R = 1,1763,170,170,170
BEGIN DESCRIPTION:
Twin Creek1421763.22
END DESCRIPTION:
XS GIS Cut Line= 3
      2697822.76      6815187.74      2697628.51      6815163.89
      2697425.89      6815143.10
#Sta/Elev= 30
  4805.0  349.46  4811.8  349.47  4818.1  348.86  4823.1  348.98  4842.0  348.28
  4852.1  347.45  4892.4  345.20  4899.4  344.50  4904.4  344.44  4922.6  342.71
  4932.7  343.04  4942.8  342.79  4952.9  341.99  4962.9  342.20  4980.7  341.20
  4985.8  341.49  4991.2  341.10  4991.4  340.60  4994.9  340.60  4995.2  341.10
  5013.3  341.26  5023.3  341.74  5033.4  342.39  5053.5  344.27  5078.3  343.84
  5093.7  344.53  5103.8  345.31  5154.0  347.15  5184.2  348.91  5204.4  349.62
#Mann=3,-1,0
  4805.0    0.05       0  4991.2    0.05       0  4995.2    0.05       0
Bank Sta=4991.2,4995.2
Exp/Cntr=0.3,0.1

Type RM Length L Ch R = 1,1593,164,164,164
BEGIN DESCRIPTION:
Twin Creek1421592.91
END DESCRIPTION:
XS GIS Cut Line= 3
      2697821.27      6815065.61      2697679.21      6815009.39
      2697519.92      6814953.16
#Sta/Elev= 30
  4849.2  346.38  4854.9  345.46  4865.6  345.48  4887.1  344.93  4902.9  344.40
  4927.2  343.15  4932.6  343.13  4936.3  342.80  4940.9  342.39  4951.6  342.24
  4956.9  341.91  4962.4  342.18  4973.2  341.30  4979.3  340.60  4979.5  340.10
  4983.0  340.10  4983.3  340.60  4993.2  340.92  5037.0  341.08  5042.4  340.87
  5047.8  341.38  5058.4  341.38  5068.0  342.00  5073.3  341.79  5079.6  342.10
  5122.0  342.89  5135.1  343.41  5143.2  343.97  5153.9  344.34  5170.9  345.26
#Mann=5,-1,0
  4849.2    0.05       0  4936.3    0.12       0  4979.3    0.05       0
  4983.3    0.12       0  4993.2    0.05       0
Bank Sta=4979.3,4983.3
Exp/Cntr=0.3,0.1

Type RM Length L Ch R = 1,1429,208,208,208
BEGIN DESCRIPTION:
Twin Creek1421428.52
END DESCRIPTION:
XS GIS Cut Line= 3
      2697884.80      6815018.31      2697762.22      6814872.72
      2697620.71      6814722.63
#Sta/Elev= 30
  4810.8  345.76  4829.6  345.07  4843.9  344.94  4864.7  344.30  4907.6  342.07
  4914.7  342.08  4942.7  340.69  4950.5  339.83  4957.0  339.96  4964.1  338.86
  4977.9  338.50  4985.6  337.59  4992.2  337.13  4997.0  337.12  4997.2  336.62
  5000.7  336.62  5001.0  337.12  5006.6  337.91  5028.1  337.79  5042.2  338.79
  5063.3  339.37  5070.6  339.29  5091.6  339.83  5113.0  339.97  5119.9  340.34
  5134.1  340.42  5162.4  341.52  5169.3  342.02  5204.9  342.96  5207.4  343.42
#Mann=5,-1,0
  4810.8    0.05       0  4914.7    0.12       0  4997.0    0.07       0
  5001.0    0.12       0  5063.3    0.05       0
Bank Sta=4997,5001
Exp/Cntr=0.3,0.1

Type RM Length L Ch R = 1,1221,181,181,181
BEGIN DESCRIPTION:
Twin Creek1421220.82
END DESCRIPTION:
XS GIS Cut Line= 3
      2698029.66      6814920.98      2697878.64      6814708.08
      2697733.07      6814555.10
#Sta/Elev= 30
  4742.6  342.47  4774.0  340.80  4780.2  340.88  4794.9  339.89  4803.6  339.67
  4809.7  339.90  4818.1  339.32  4852.9  338.27  4860.2  337.37  4874.9  337.20
  4881.1  337.91  4895.8  337.35  4902.0  336.48  4931.5  335.62  4988.1  335.41
  5003.6  334.68  5008.6  334.05  5008.9  333.55  5012.4  333.55  5012.6  334.05
  5017.5  334.59  5024.8  334.25  5053.1  334.74  5067.2  336.15  5084.9  336.99
  5109.7  337.88  5116.6  337.71  5137.6  338.58  5159.1  338.82  5214.8  342.05
#Mann=5,-1,0
  4742.6    0.05       0  4818.1    0.12       0  5008.6    0.07       0
  5012.6    0.12       0  5084.9    0.05       0
Bank Sta=5008.6,5012.6
Exp/Cntr=0.3,0.1

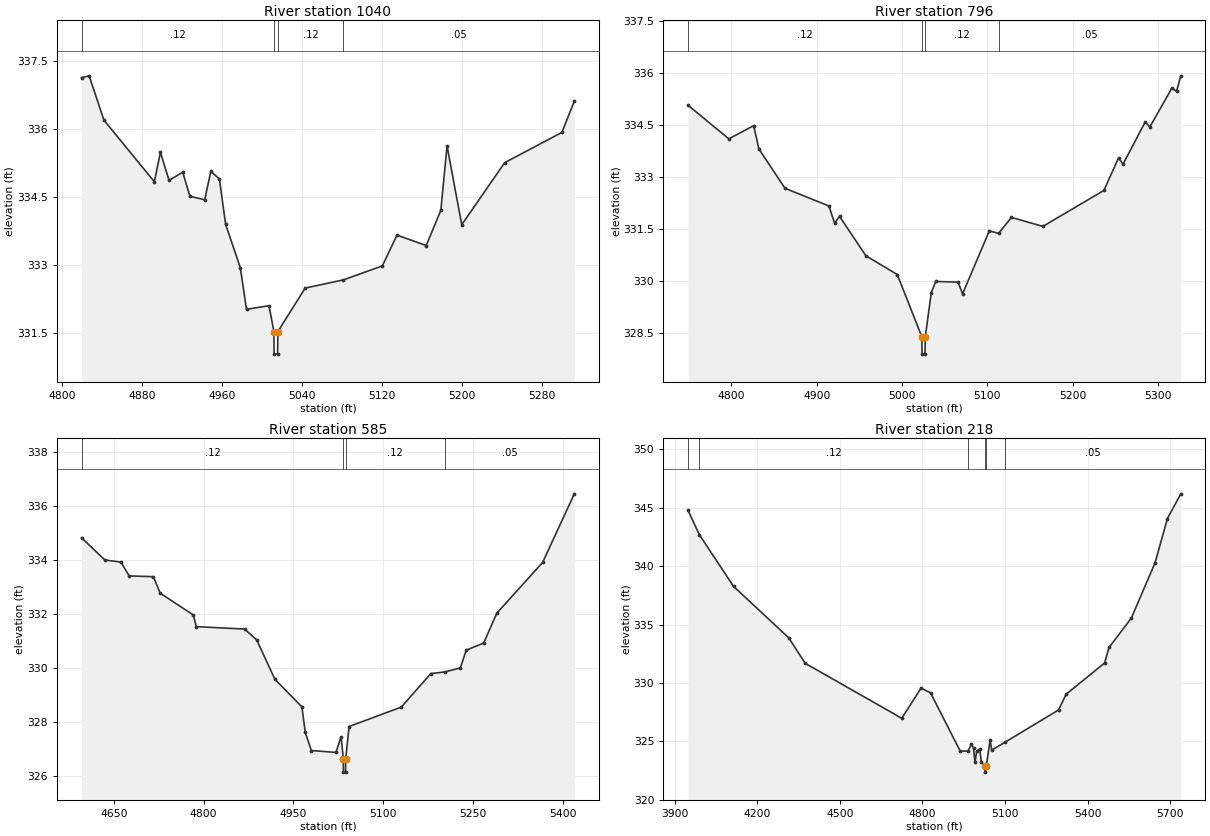
Type RM Length L Ch R = 1,1040,244,244,244
BEGIN DESCRIPTION:
Twin Creek1421040.44
END DESCRIPTION:
XS GIS Cut Line= 3
      2698124.58      6814753.40      2698019.14      6814605.60
      2697834.51      6814354.92
#Sta/Elev= 30
  4819.3  337.14  4826.9  337.18  4841.7  336.20  4892.1  334.84  4898.2  335.49
  4906.8  334.87  4920.5  335.05  4927.7  334.52  4942.5  334.44  4948.6  335.07
  4957.2  334.90  4963.4  333.90  4978.1  332.94  4984.3  332.02  5006.8  332.10
  5011.7  331.53  5011.9  331.03  5015.4  331.03  5015.7  331.53  5043.0  332.49
  5081.1  332.67  5120.2  332.98  5134.8  333.66  5164.1  333.43  5178.7  334.21
  5184.9  335.63  5199.6  333.89  5242.5  335.26  5299.8  335.93  5312.2  336.62
#Mann=4,-1,0
  4819.3    0.12       0  5011.7    0.07       0  5015.7    0.12       0
  5081.1    0.05       0
Bank Sta=5011.7,5015.7
Exp/Cntr=0.3,0.1

Type RM Length L Ch R = 1,796,211,211,211
BEGIN DESCRIPTION:
Twin Creek142796.38
END DESCRIPTION:
XS GIS Cut Line= 3
      2698281.09      6814651.75      2698150.29      6814438.43
      2697840.84      6814332.84
#Sta/Elev= 30
  4749.3  335.07  4797.1  334.10  4826.2  334.48  4832.3  333.81  4862.9  332.67
  4914.4  332.16  4921.0  331.66  4926.8  331.86  4957.7  330.72  4994.4  330.18
  5023.2  328.38  5023.4  327.88  5026.9  327.88  5027.2  328.38  5034.3  329.66
  5039.5  329.98  5065.6  329.96  5070.9  329.62  5102.2  331.44  5113.1  331.37
  5128.2  331.83  5164.9  331.57  5236.5  332.61  5253.6  333.55  5258.9  333.37
  5284.9  334.59  5290.2  334.44  5316.2  335.57  5321.5  335.47  5326.5  335.92
#Mann=4,-1,0
  4749.3    0.12       0  5023.2    0.07       0  5027.2    0.12       0
  5113.1    0.05       0
Bank Sta=5023.2,5027.2
Exp/Cntr=0.3,0.1

Type RM Length L Ch R = 1,585,367,367,367
BEGIN DESCRIPTION:
Twin Creek142585.16
END DESCRIPTION:
XS GIS Cut Line= 4
      2698292.19      6814649.40      2698225.06      6814251.79
      2698182.57      6814228.75      2697819.53      6814307.25
#Sta/Elev= 30
  4596.2  334.81  4635.1  333.99  4662.0  333.91  4675.7  333.40  4716.3  333.37
  4727.5  332.76  4782.9  331.95  4787.9  331.52  4868.4  331.43  4888.7  331.03
  4919.1  329.57  4964.2  328.55  4969.8  327.61  4980.0  326.93  5021.1  326.86
  5029.7  327.44  5033.4  326.63  5033.6  326.13  5037.1  326.13  5037.4  326.63
  5043.0  327.82  5130.3  328.54  5179.5  329.78  5202.7  329.84  5228.8  329.99
  5238.7  330.65  5267.8  330.91  5289.8  332.02  5366.3  333.90  5419.2  336.44
#Mann=4,-1,0
  4596.2    0.12       0  5033.4    0.07       0  5037.4    0.12       0
  5202.7    0.05       0
Bank Sta=5033.4,5037.4
Exp/Cntr=0.3,0.1

Type RM Length L Ch R = 1,218,0,0,0
BEGIN DESCRIPTION:
Twin Creek142218.198
END DESCRIPTION:
XS GIS Cut Line= 4
      2698301.00      6814935.97      2698351.00      6814086.00
      2698276.41      6813900.80      2697633.65      6814264.04
#Sta/Elev= 30
  3948.9  344.78  3989.8  342.70  4114.2  338.27  4314.5  333.87  4374.6  331.68
  4725.2  326.98  4795.3  329.57  4829.9  329.14  4937.3  324.17  4965.7  324.17
  4978.2  324.79  4985.7  324.42  4991.0  323.21  4997.2  324.16  5008.4  324.35
  5014.1  323.21  5028.0  322.87  5028.3  322.37  5032.0  322.87  5046.0  325.14
  5051.7  324.25  5099.4  324.92  5294.3  327.69  5322.1  329.04  5461.7  331.71
  5477.6  333.04  5558.5  335.54  5645.1  340.30  5689.7  344.07  5738.3  346.19
#Mann=6,-1,0
  3948.9    0.16       0  3989.8    0.12       0  4965.7    0.16       0
  5028.0    0.07       0  5032.0    0.16       0  5099.4    0.05       0
Bank Sta=5028,5032
Exp/Cntr=0.3,0.1

Chan Stop Cuts=-1