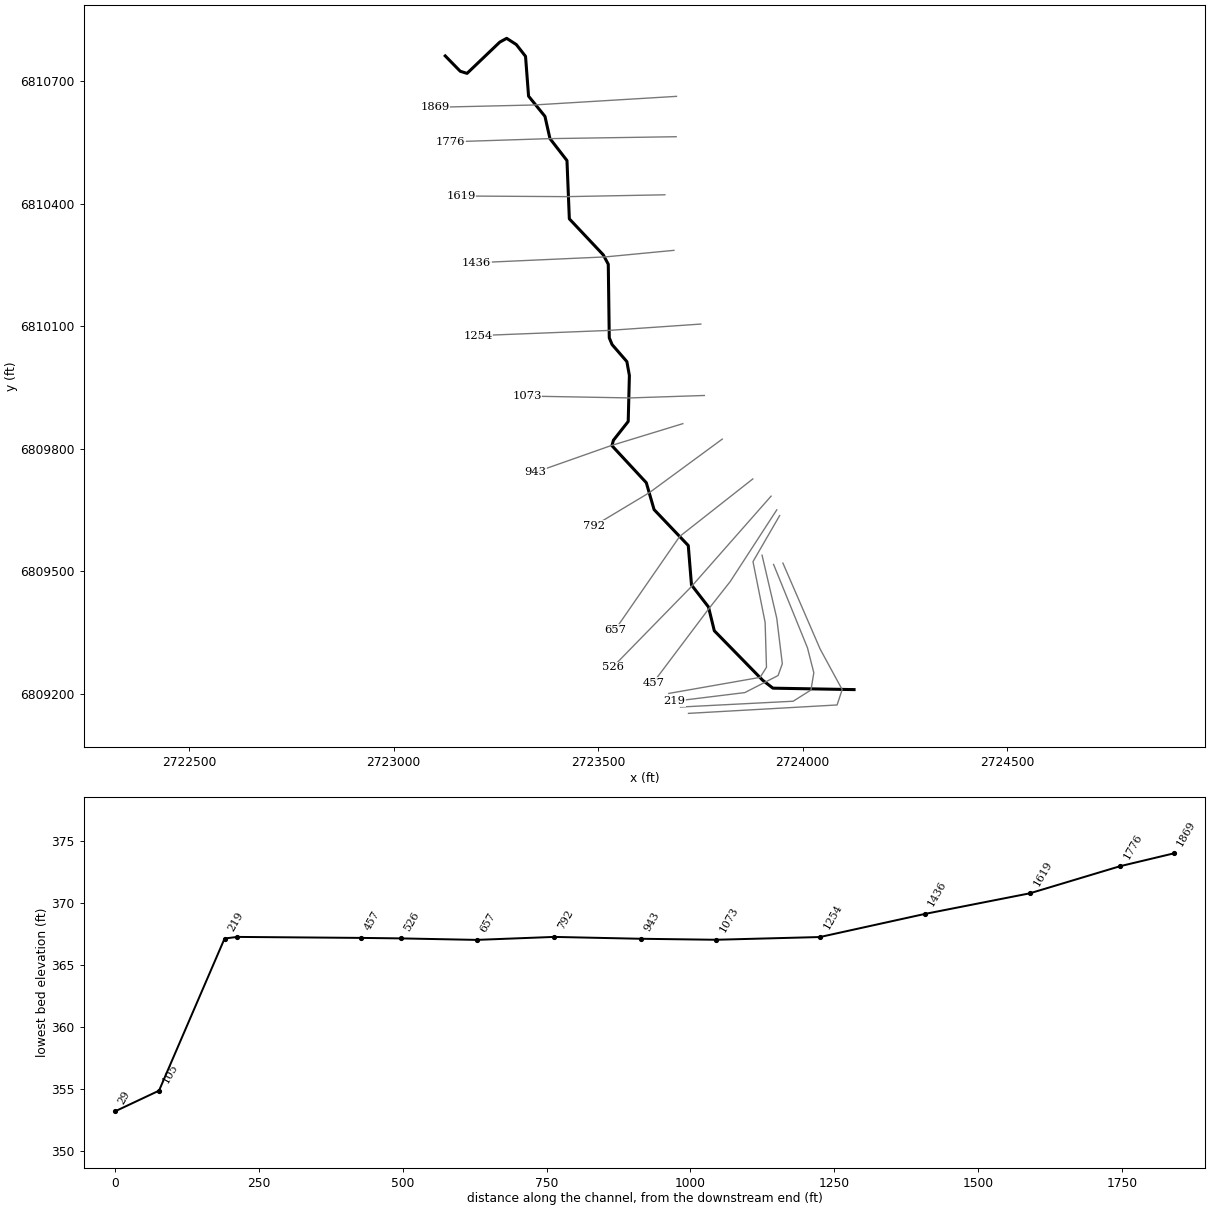
--- Twin Creek145.prj (project) ---

Proj Title=Twin Creek145 Base Level Engineering
Current Plan=p01
Default Exp/Contr=0.3,0.1
English Units
Geom File=g01
Flow File=f01
Plan File=p01
BEGIN DESCRIPTION:
Twin Creek145
END DESCRIPTION:

--- Twin Creek145.p01 (plan) ---

Plan Title=Multiple Run
Short Identifier=Multiple
Geom File=g01
Flow File=f01
Subcritical Flow
K Sum by GR= 0
Std Step Tol= 0.01
Critical Tol= 0.01
Num of Std Step Trials= 20
Max Error Tol= 0.3
Flow Tol Ratio= 0.001
Split Flow NTrial= 30
Split Flow Tol= 0.02
Split Flow Ratio= 0.02
Log Output Level= 0
Friction Slope Method= 1
Unsteady Friction Slope Method= 2
Unsteady Bridges Friction Slope Method= 1
Parabolic Critical Depth
Global Vel Dist=  1 , 1 , 1
Global Log Level= 0
CheckData=True
Encroach Param= -1, 0, 0, 0
BEGIN DESCRIPTION:
Multiple Run
END DESCRIPTION:

--- Twin Creek145.f01 (steady flow) ---

Flow Title=Multiple
Number of Profiles=7
Profile Names=10-year,25-year,50-year,1pct_min,100-year,1pct_plu,500-year
River Rch & RM= Twin Creek145,Reach-1,1869
      86      99     108      59     117     234     137
Boundary for River Rch & Prof#=Twin Creek145,Reach-1,1
Up Type=0
Dn Type=3
Dn Slope=0.005
Boundary for River Rch & Prof#=Twin Creek145,Reach-1,2
Up Type=0
Dn Type=3
Dn Slope=0.005
Boundary for River Rch & Prof#=Twin Creek145,Reach-1,3
Up Type=0
Dn Type=3
Dn Slope=0.005
Boundary for River Rch & Prof#=Twin Creek145,Reach-1,4
Up Type=0
Dn Type=3
Dn Slope=0.005
Boundary for River Rch & Prof#=Twin Creek145,Reach-1,5
Up Type=0
Dn Type=3
Dn Slope=0.005
Boundary for River Rch & Prof#=Twin Creek145,Reach-1,6
Up Type=0
Dn Type=3
Dn Slope=0.005
Boundary for River Rch & Prof#=Twin Creek145,Reach-1,7
Up Type=0
Dn Type=3
Dn Slope=0.005

--- Twin Creek145.g01 (geometry) ---

Geom Title=Existing Conditions

River Reach=Twin Creek145,Reach-1
Reach XY= 30
      2723126.00      6810761.00      2723162.67      6810723.52
      2723179.33      6810718.29      2723259.43      6810794.81
      2723276.24      6810804.02      2723299.82      6810788.81
      2723322.39      6810759.99      2723329.83      6810662.59
      2723369.89      6810613.18      2723382.12      6810558.82
      2723423.75      6810505.07      2723429.56      6810362.47
      2723512.60      6810274.31      2723524.79      6810251.41
      2723527.22      6810071.51      2723534.14      6810054.94
      2723570.26      6810013.33      2723576.42      6809979.33
      2723573.54      6809866.86      2723537.34      6809820.85
      2723533.81      6809807.59      2723617.80      6809717.05
      2723636.80      6809651.33      2723720.46      6809563.42
      2723728.33      6809466.97      2723769.86      6809413.17
      2723784.14      6809354.94      2723902.47      6809233.86
      2723927.46      6809214.53      2724126.00      6809211.00

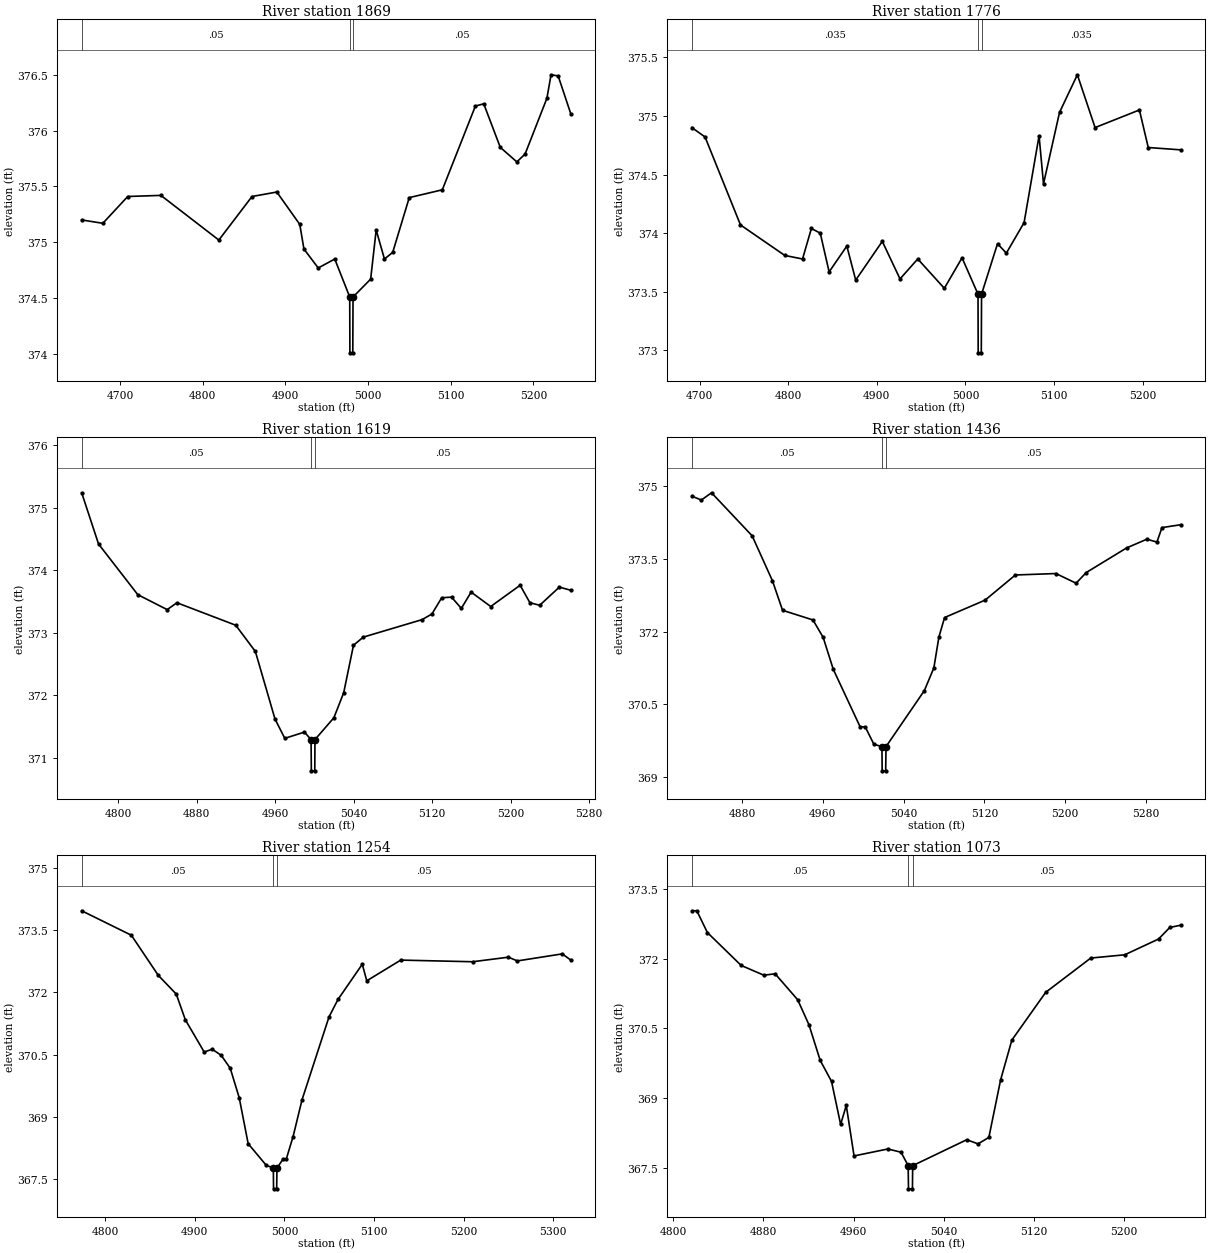
Type RM Length L Ch R = 1,1869,93,93,93
BEGIN DESCRIPTION:
Twin Creek1451868.85
END DESCRIPTION:
XS GIS Cut Line= 3
      2723691.58      6810662.10      2723342.76      6810640.99
      2723100.68      6810635.36
#Sta/Elev= 30
  4653.7  375.20  4679.3  375.17  4709.4  375.41  4749.5  375.42  4819.6  375.02
  4859.7  375.41  4889.7  375.45  4917.5  375.16  4922.5  374.94  4939.8  374.77
  4959.8  374.85  4977.9  374.51  4978.1  374.01  4981.6  374.01  4981.9  374.51
  5003.2  374.67  5009.9  375.11  5019.9  374.85  5029.9  374.91  5049.9  375.40
  5089.9  375.47  5129.9  376.22  5140.0  376.24  5160.0  375.85  5180.0  375.72
  5190.0  375.79  5216.4  376.29  5221.4  376.50  5230.0  376.49  5245.3  376.15
#Mann=3,-1,0
  4653.7    0.05       0  4977.9    0.05       0  4981.9    0.05       0
Bank Sta=4977.9,4981.9
Exp/Cntr=0.3,0.1

Type RM Length L Ch R = 1,1776,157,157,157
BEGIN DESCRIPTION:
Twin Creek1451775.5
END DESCRIPTION:
XS GIS Cut Line= 3
      2723690.86      6810563.37      2723380.68      6810558.68
      2723139.12      6810550.91
#Sta/Elev= 30
  4691.3  374.90  4706.2  374.82  4746.2  374.07  4796.2  373.81  4816.2  373.78
  4826.2  374.04  4836.2  374.00  4846.2  373.67  4866.2  373.89  4876.2  373.60
  4906.2  373.93  4926.2  373.61  4946.2  373.78  4976.2  373.53  4996.2  373.79
  5014.2  373.48  5014.4  372.98  5017.9  372.98  5018.2  373.48  5036.2  373.91
  5046.2  373.83  5066.2  374.09  5083.1  374.83  5088.1  374.42  5106.2  375.03
  5126.3  375.35  5146.3  374.90  5196.3  375.05  5206.3  374.73  5243.2  374.71
#Mann=3,-1,0
  4691.3   0.035       0  5014.2   0.035       0  5018.2   0.035       0
Bank Sta=5014.2,5018.2
Exp/Cntr=0.3,0.1

Type RM Length L Ch R = 1,1619,183,183,183
BEGIN DESCRIPTION:
Twin Creek1451618.7
END DESCRIPTION:
XS GIS Cut Line= 3
      2723663.21      6810421.30      2723423.50      6810416.80
      2723164.26      6810418.35
#Sta/Elev= 30
  4762.5  375.24  4779.7  374.42  4819.7  373.61  4849.7  373.37  4859.7  373.48
  4919.7  373.12  4939.7  372.70  4959.7  371.62  4969.7  371.31  4989.8  371.41
  4996.5  371.29  4996.8  370.79  5000.3  370.79  5000.5  371.29  5019.8  371.64
  5029.8  372.04  5039.8  372.80  5049.8  372.93  5109.8  373.21  5119.8  373.30
  5129.8  373.56  5139.8  373.57  5149.8  373.39  5159.8  373.65  5179.8  373.42
  5209.8  373.76  5219.8  373.48  5229.8  373.44  5249.8  373.73  5261.5  373.68
#Mann=3,-1,0
  4762.5    0.05       0  4996.5    0.05       0  5000.5    0.05       0
Bank Sta=4996.5,5000.5
Exp/Cntr=0.3,0.1

Type RM Length L Ch R = 1,1436,182,182,182
BEGIN DESCRIPTION:
Twin Creek1451436.05
END DESCRIPTION:
XS GIS Cut Line= 3
      2723685.40      6810285.44      2723518.10      6810269.42
      2723202.29      6810255.15
#Sta/Elev= 30
  4830.4  374.80  4839.8  374.72  4849.9  374.87  4890.1  373.98  4910.2  373.05
  4920.2  372.44  4950.3  372.24  4960.4  371.88  4970.4  371.22  4997.0  370.03
  5002.0  370.03  5010.6  369.67  5018.6  369.62  5018.8  369.12  5022.3  369.12
  5022.6  369.62  5060.6  370.78  5070.0  371.25  5075.0  371.89  5080.6  372.29
  5120.7  372.65  5150.7  373.17  5190.8  373.20  5210.8  373.00  5220.8  373.22
  5260.8  373.73  5280.9  373.91  5290.8  373.85  5295.8  374.15  5314.6  374.21
#Mann=3,-1,0
  4830.4    0.05       0  5018.6    0.05       0  5022.6    0.05       0
Bank Sta=5018.6,5022.6
Exp/Cntr=0.3,0.1

Type RM Length L Ch R = 1,1254,181,181,181
BEGIN DESCRIPTION:
Twin Creek1451254.19
END DESCRIPTION:
XS GIS Cut Line= 3
      2723751.28      6810105.14      2723523.76      6810089.45
      2723206.47      6810076.87
#Sta/Elev= 30
  4773.9  373.97  4829.3  373.38  4859.4  372.41  4879.4  371.96  4889.5  371.34
  4910.6  370.56  4919.5  370.63  4929.6  370.48  4939.6  370.17  4949.6  369.46
  4959.6  368.35  4979.7  367.83  4987.7  367.76  4987.9  367.26  4991.4  367.26
  4991.7  367.76  4998.3  367.97  5002.0  367.97  5009.7  368.52  5019.7  369.41
  5049.8  371.41  5059.8  371.83  5086.9  372.68  5091.9  372.28  5129.8  372.78
  5209.9  372.74  5249.9  372.85  5259.9  372.76  5310.0  372.93  5319.5  372.78
#Mann=3,-1,0
  4773.9    0.05       0  4987.7    0.05       0  4991.7    0.05       0
Bank Sta=4987.7,4991.7
Exp/Cntr=0.3,0.1

Type RM Length L Ch R = 1,1073,130,130,130
BEGIN DESCRIPTION:
Twin Creek1451072.93
END DESCRIPTION:
XS GIS Cut Line= 3
      2723759.82      6809930.43      2723577.59      6809924.45
      2723326.06      6809928.99
#Sta/Elev= 30
  4816.5  373.04  4820.9  373.04  4830.3  372.57  4860.3  371.86  4880.4  371.65
  4890.4  371.68  4910.4  371.12  4920.4  370.58  4930.4  369.81  4940.4  369.36
  4948.5  368.43  4953.5  368.84  4960.4  367.75  4990.4  367.90  5002.1  367.83
  5008.4  367.54  5008.7  367.04  5012.2  367.04  5012.4  367.54  5060.4  368.10
  5070.4  368.01  5080.0  368.15  5090.4  369.39  5100.4  370.25  5130.4  371.28
  5170.4  372.02  5200.5  372.09  5230.5  372.43  5240.5  372.68  5250.4  372.73
#Mann=3,-1,0
  4816.5    0.05       0  5008.4    0.05       0  5012.4    0.05       0
Bank Sta=5008.4,5012.4
Exp/Cntr=0.3,0.1

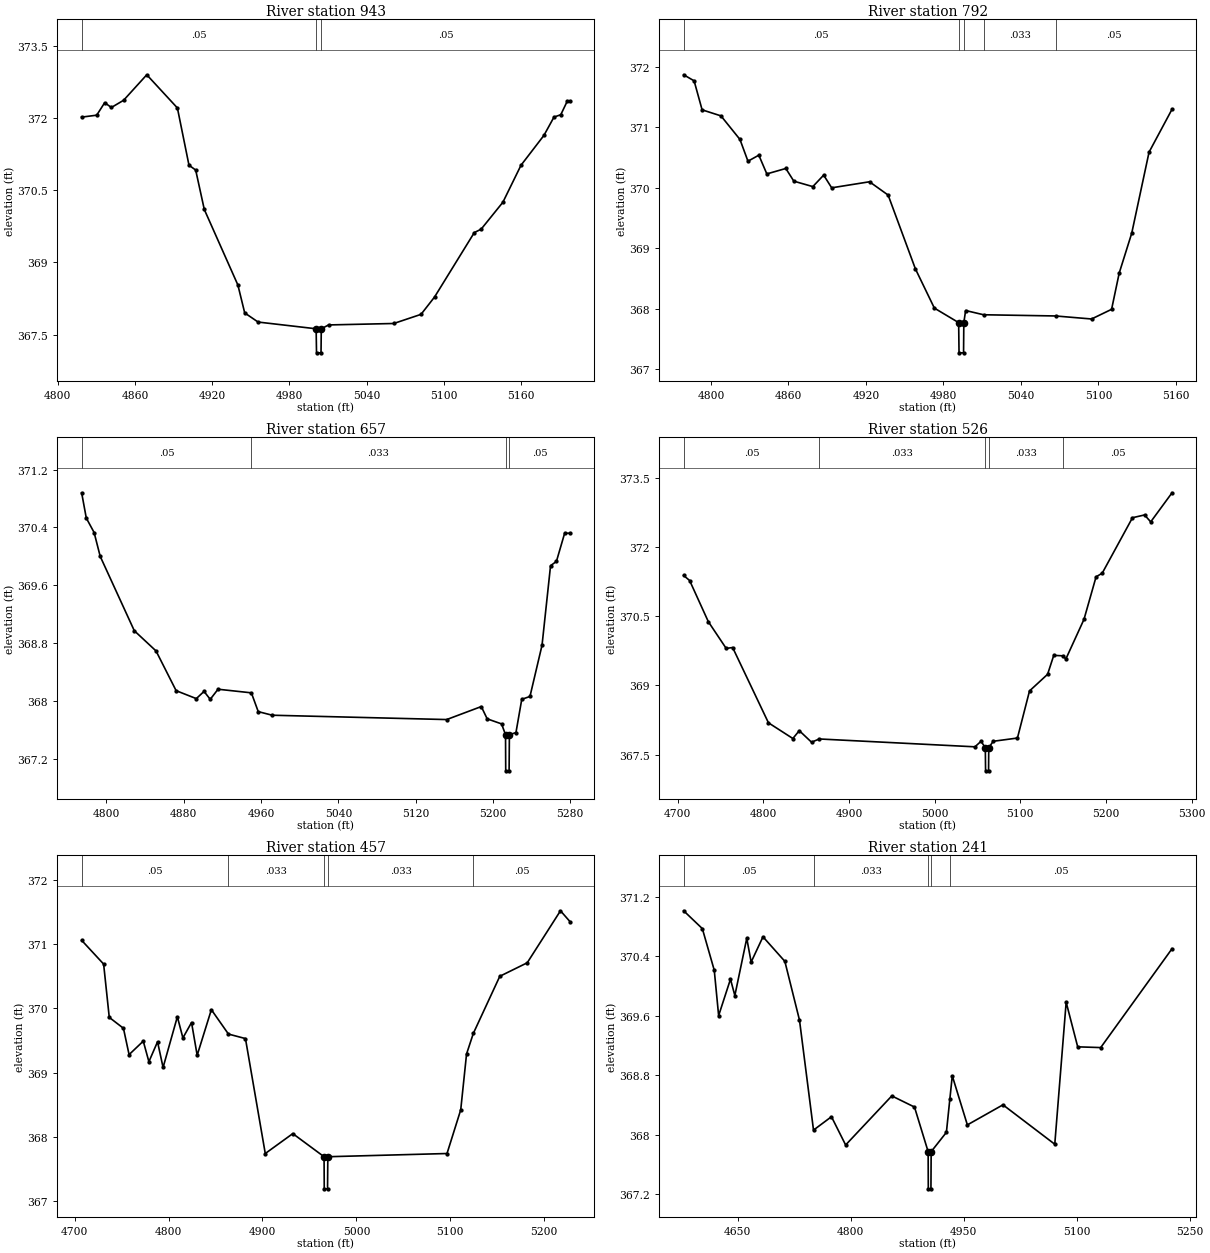
Type RM Length L Ch R = 1,943,151,151,151
BEGIN DESCRIPTION:
Twin Creek145942.73
END DESCRIPTION:
XS GIS Cut Line= 3
      2723707.15      6809861.51      2723530.99      6809807.61
      2723346.81      6809742.70
#Sta/Elev= 30
  4818.6  372.02  4830.3  372.06  4836.5  372.32  4841.7  372.22  4851.2  372.37
  4869.2  372.90  4893.0  372.21  4902.0  371.02  4907.2  370.92  4913.9  370.10
  4940.0  368.53  4945.3  367.95  4955.7  367.76  5000.8  367.62  5001.1  367.12
  5004.6  367.12  5004.8  367.62  5010.5  367.70  5061.1  367.73  5082.3  367.92
  5092.8  368.28  5123.7  369.62  5129.0  369.69  5145.9  370.25  5160.0  371.02
  5177.8  371.64  5185.6  372.02  5190.9  372.07  5195.9  372.35  5198.1  372.35
#Mann=3,-1,0
  4818.6    0.05       0  5000.8    0.05       0  5004.8    0.05       0
Bank Sta=5000.8,5004.8
Exp/Cntr=0.3,0.1

Type RM Length L Ch R = 1,792,135,135,135
BEGIN DESCRIPTION:
Twin Creek145792.16
END DESCRIPTION:
XS GIS Cut Line= 3
      2723803.57      6809823.70      2723625.56      6809692.92
      2723490.77      6809612.00
#Sta/Elev= 30
  4778.9  371.87  4787.0  371.77  4793.2  371.29  4807.8  371.19  4822.5  370.80
  4828.7  370.44  4837.1  370.54  4843.3  370.23  4858.0  370.32  4864.2  370.11
  4878.9  370.02  4887.3  370.21  4893.5  370.00  4922.8  370.10  4937.2  369.88
  4958.3  368.66  4973.0  368.01  4991.8  367.77  4992.1  367.27  4995.6  367.27
  4995.8  367.77  4997.2  367.97  5011.1  367.90  5066.8  367.88  5094.7  367.83
  5110.2  367.99  5116.1  368.59  5125.8  369.25  5139.2  370.59  5157.0  371.30
#Mann=5,-1,0
  4778.9    0.05       0  4991.8    0.05       0  4995.8    0.05       0
  5011.1   0.033       0  5066.8    0.05       0
Bank Sta=4991.8,4995.8
Exp/Cntr=0.3,0.1

Type RM Length L Ch R = 1,657,131,131,131
BEGIN DESCRIPTION:
Twin Creek145657.29
END DESCRIPTION:
XS GIS Cut Line= 3
      2723878.23      6809726.23      2723699.51      6809585.68
      2723541.24      6809356.85
#Sta/Elev= 30
  4774.3  370.88  4779.1  370.53  4787.2  370.33  4793.5  370.00  4828.8  368.97
  4851.3  368.69  4872.1  368.14  4893.0  368.03  4901.0  368.13  4907.4  368.02
  4915.5  368.16  4950.0  368.11  4957.1  367.85  4971.6  367.80  5152.2  367.74
  5188.0  367.92  5194.1  367.75  5209.0  367.68  5213.1  367.53  5213.3  367.03
  5216.8  367.03  5217.1  367.53  5223.9  367.56  5229.9  368.02  5238.4  368.06
  5250.9  368.77  5259.7  369.87  5265.8  369.93  5274.3  370.32  5279.9  370.32
#Mann=4,-1,0
  4774.3    0.05       0  4950.0   0.033       0  5213.1   0.033       0
  5217.1    0.05       0
Bank Sta=5213.1,5217.1
Exp/Cntr=0.3,0.1

Type RM Length L Ch R = 1,526,69,69,69
BEGIN DESCRIPTION:
Twin Creek145525.98
END DESCRIPTION:
XS GIS Cut Line= 3
      2723923.00      6809684.20      2723728.10      6809462.96
      2723535.67      6809266.00
#Sta/Elev= 30
  4706.9  371.38  4713.9  371.27  4735.7  370.38  4756.6  369.80  4764.1  369.82
  4805.9  368.19  4834.4  367.85  4841.9  368.02  4856.2  367.77  4865.3  367.84
  5047.0  367.67  5054.1  367.79  5059.1  367.65  5059.4  367.15  5062.9  367.15
  5063.1  367.65  5068.3  367.79  5096.6  367.86  5110.7  368.88  5131.8  369.24
  5139.0  369.65  5149.8  369.64  5153.1  369.57  5174.3  370.43  5188.4  371.35
  5195.6  371.43  5230.9  372.63  5245.0  372.69  5252.2  372.54  5277.1  373.17
#Mann=5,-1,0
  4706.9    0.05       0  4865.3   0.033       0  5059.1   0.033       0
  5063.1   0.033       0  5149.8    0.05       0
Bank Sta=5059.1,5063.1
Exp/Cntr=0.3,0.1

Type RM Length L Ch R = 1,457,216,216,216
BEGIN DESCRIPTION:
Twin Creek145456.06
END DESCRIPTION:
XS GIS Cut Line= 4
      2723936.97      6809650.70      2723823.07      6809475.32
      2723769.83      6809407.64      2723634.70      6809228.03
#Sta/Elev= 30
  4707.5  371.06  4730.9  370.69  4736.9  369.86  4752.0  369.69  4758.0  369.28
  4773.1  369.49  4779.1  369.17  4788.3  369.48  4794.2  369.08  4809.4  369.87
  4815.3  369.54  4824.5  369.78  4830.5  369.27  4845.6  369.98  4863.8  369.60
  4881.9  369.53  4903.0  367.74  4932.3  368.05  4965.6  367.69  4965.8  367.19
  4969.3  367.19  4969.6  367.69  5096.5  367.74  5111.1  368.42  5117.3  369.29
  5124.5  369.61  5152.7  370.50  5181.9  370.71  5217.3  371.52  5227.5  371.35
#Mann=5,-1,0
  4707.5    0.05       0  4863.8   0.033       0  4965.6   0.033       0
  4969.6   0.033       0  5124.5    0.05       0
Bank Sta=4965.6,4969.6
Exp/Cntr=0.3,0.1

Type RM Length L Ch R = 1,241,22,22,22
BEGIN DESCRIPTION:
Twin Creek145240.58
END DESCRIPTION:
XS GIS Cut Line= 6
      2723943.95      6809636.63      2723878.76      6809524.01
      2723908.45      6809375.43      2723911.74      6809265.54
      2723896.14      6809240.93      2723672.80      6809201.66
#Sta/Elev= 30
  4578.5  371.01  4603.3  370.77  4619.1  370.21  4624.9  369.60  4640.6  370.09
  4646.4  369.87  4662.2  370.64  4668.0  370.32  4683.7  370.66  4712.7  370.33
  4732.1  369.54  4750.7  368.06  4774.5  368.24  4793.3  367.86  4854.5  368.52
  4884.6  368.37  4902.7  367.77  4902.9  367.27  4906.4  367.27  4906.7  367.77
  4926.9  368.03  4931.5  368.48  4934.7  368.79  4954.7  368.13  5001.9  368.40
  5070.6  367.87  5085.7  369.78  5101.0  369.18  5131.5  369.17  5226.1  370.50
#Mann=5,-1,0
  4578.5    0.05       0  4750.7   0.033       0  4902.7    0.05       0
  4906.7   0.033       0  4931.5    0.05       0
Bank Sta=4902.7,4906.7
Exp/Cntr=0.3,0.1

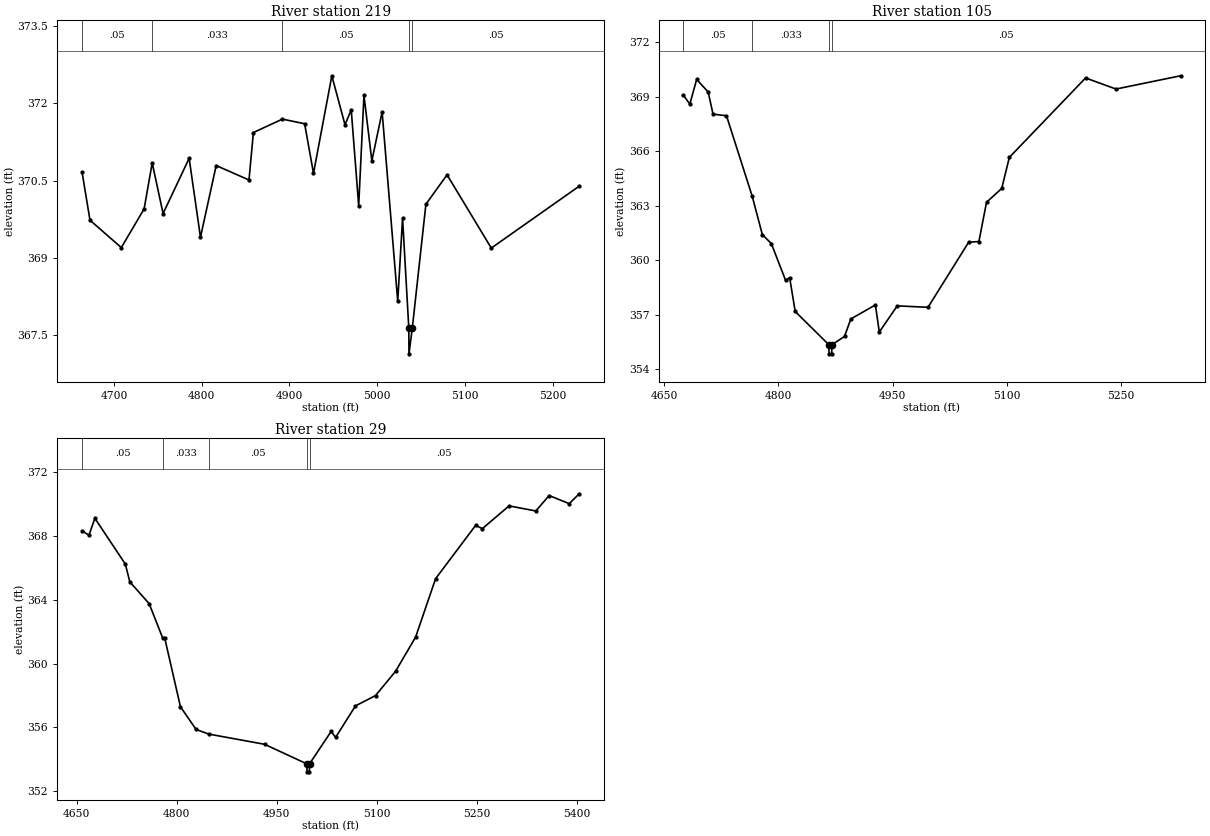
Type RM Length L Ch R = 1,219,114,114,114
BEGIN DESCRIPTION:
Twin Creek145219.19
END DESCRIPTION:
XS GIS Cut Line= 6
      2723900.94      6809539.81      2723936.88      6809385.62
      2723950.50      6809274.24      2723940.15      6809245.42
      2723858.77      6809203.70      2723686.55      6809182.51
#Sta/Elev= 30
  4663.7  370.66  4672.7  369.73  4708.4  369.20  4734.4  369.95  4743.6  370.84
  4756.0  369.86  4785.7  370.93  4798.6  369.40  4816.5  370.79  4853.9  370.51
  4858.9  371.43  4892.0  371.69  4917.3  371.60  4927.4  370.64  4948.3  372.53
  4963.3  371.58  4970.4  371.87  4978.9  370.01  4984.9  372.15  4993.9  370.88
  5005.6  371.83  5023.4  368.16  5028.9  369.77  5036.0  367.64  5036.2  367.14
  5040.0  367.64  5055.5  370.04  5079.6  370.61  5130.0  369.19  5230.2  370.39
#Mann=5,-1,0
  4663.7    0.05       0  4743.6   0.033       0  4892.0    0.05       0
  5036.0    0.05       0  5040.0    0.05       0
Bank Sta=5036,5040
Exp/Cntr=0.3,0.1

Type RM Length L Ch R = 1,105,76,76,76
BEGIN DESCRIPTION:
Mapping XS 4085ad1f
END DESCRIPTION:
XS GIS Cut Line= 6
      2723929.18      6809517.08      2724012.00      6809313.28
      2724027.54      6809252.33      2724020.58      6809210.09
      2723977.11      6809182.58      2723701.32      6809168.37
#Sta/Elev= 30
  4675.1  369.09  4683.5  368.60  4692.5  369.96  4707.6  369.27  4714.0  368.05
  4731.7  367.96  4765.5  363.53  4778.8  361.42  4790.6  360.93  4809.3  358.91
  4814.7  359.05  4822.0  357.19  4866.2  355.36  4866.5  354.86  4870.0  354.86
  4870.2  355.36  4886.8  355.82  4895.1  356.78  4927.4  357.55  4932.5  356.06
  4956.1  357.50  4996.5  357.42  5049.9  361.00  5063.4  361.04  5073.4  363.20
  5093.4  363.96  5103.4  365.67  5203.6  370.04  5243.6  369.43  5328.4  370.16
#Mann=4,-1,0
  4675.1    0.05       0  4765.5   0.033       0  4866.2    0.05       0
  4870.2    0.05       0
Bank Sta=4866.2,4870.2
Exp/Cntr=0.3,0.1

Type RM Length L Ch R = 1,29,0,0,0
BEGIN DESCRIPTION:
Twin Creek14529.11
END DESCRIPTION:
XS GIS Cut Line= 5
      2723951.96      6809520.42      2724043.04      6809310.16
      2724096.89      6809210.98      2724084.46      6809173.45
      2723720.97      6809152.86
#Sta/Elev= 30
  4658.0  368.33  4668.3  368.06  4677.2  369.12  4722.8  366.25  4729.6  365.13
  4758.6  363.76  4778.9  361.60  4782.0  361.59  4805.5  357.29  4829.0  355.86
  4848.1  355.57  4931.7  354.93  4995.1  353.70  4995.4  353.20  4998.9  353.20
  4999.1  353.70  5031.6  355.74  5038.2  355.36  5068.0  357.34  5098.1  357.99
  5128.1  359.51  5158.2  361.66  5188.2  365.33  5248.3  368.68  5258.3  368.47
  5298.4  369.90  5338.5  369.58  5358.5  370.55  5388.6  370.04  5403.6  370.66
#Mann=5,-1,0
  4658.0    0.05       0  4778.9   0.033       0  4848.1    0.05       0
  4995.1    0.05       0  4999.1    0.05       0
Bank Sta=4995.1,4999.1
Exp/Cntr=0.3,0.1

Chan Stop Cuts=-1