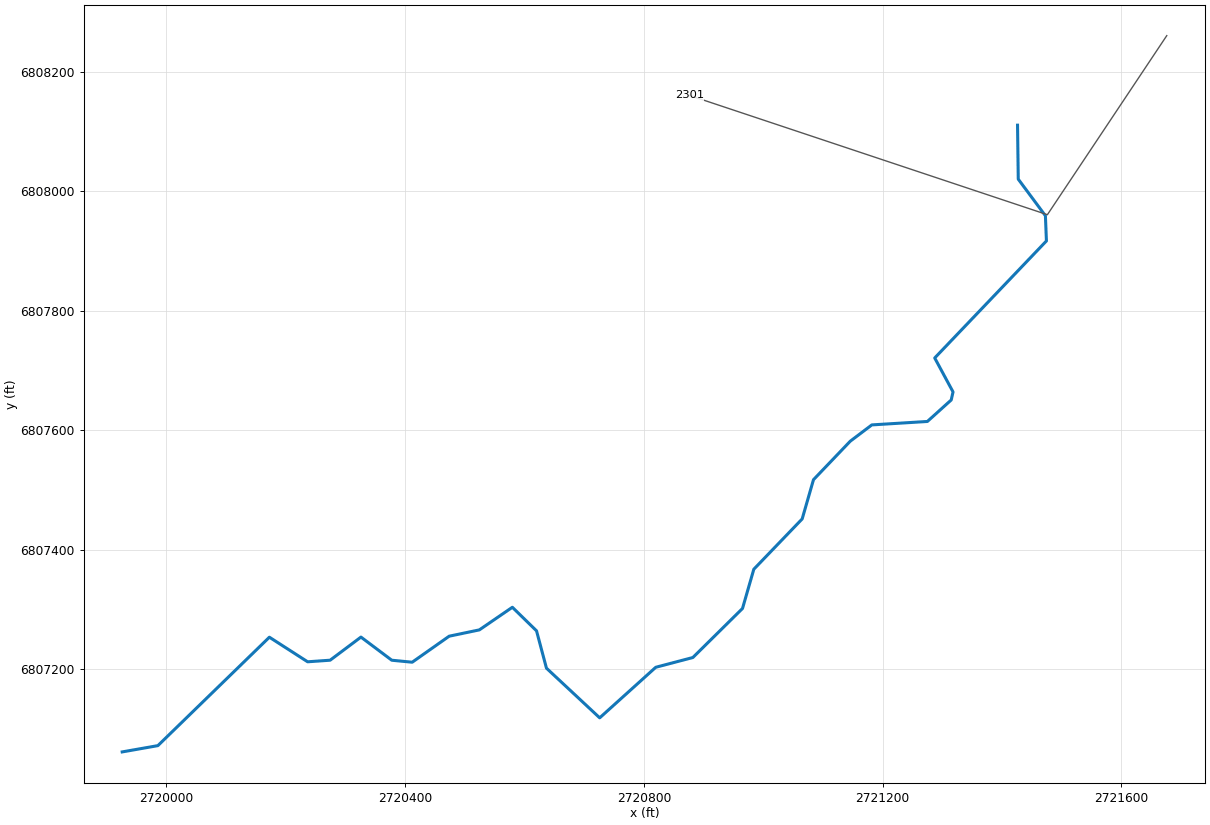
--- Twin Creek147.prj (project) ---

Proj Title=Twin Creek147 Base Level Engineering
Current Plan=p01
Default Exp/Contr=0.3,0.1
English Units
Geom File=g01
Flow File=f01
Plan File=p01
BEGIN DESCRIPTION:
Twin Creek147
END DESCRIPTION:

--- Twin Creek147.p01 (plan) ---

Plan Title=Multiple Run
Short Identifier=Multiple
Geom File=g01
Flow File=f01
Subcritical Flow
K Sum by GR= 0
Std Step Tol= 0.01
Critical Tol= 0.01
Num of Std Step Trials= 20
Max Error Tol= 0.3
Flow Tol Ratio= 0.001
Split Flow NTrial= 30
Split Flow Tol= 0.02
Split Flow Ratio= 0.02
Log Output Level= 0
Friction Slope Method= 1
Unsteady Friction Slope Method= 2
Unsteady Bridges Friction Slope Method= 1
Parabolic Critical Depth
Global Vel Dist=  1 , 1 , 1
Global Log Level= 0
CheckData=True
Encroach Param= -1, 0, 0, 0
BEGIN DESCRIPTION:
Multiple Run
END DESCRIPTION:

--- Twin Creek147.f01 (steady flow) ---

Flow Title=Multiple
Number of Profiles=7
Profile Names=10-year,25-year,50-year,1pct_min,100-year,1pct_plu,500-year
River Rch & RM= Twin Creek147,Reach-1,2301
     271     345     403     234     467     931     625
Boundary for River Rch & Prof#=Twin Creek147,Reach-1,1
Up Type=0
Dn Type=3
Dn Slope=0.005
Boundary for River Rch & Prof#=Twin Creek147,Reach-1,2
Up Type=0
Dn Type=3
Dn Slope=0.005
Boundary for River Rch & Prof#=Twin Creek147,Reach-1,3
Up Type=0
Dn Type=3
Dn Slope=0.005
Boundary for River Rch & Prof#=Twin Creek147,Reach-1,4
Up Type=0
Dn Type=3
Dn Slope=0.005
Boundary for River Rch & Prof#=Twin Creek147,Reach-1,5
Up Type=0
Dn Type=3
Dn Slope=0.005
Boundary for River Rch & Prof#=Twin Creek147,Reach-1,6
Up Type=0
Dn Type=3
Dn Slope=0.005
Boundary for River Rch & Prof#=Twin Creek147,Reach-1,7
Up Type=0
Dn Type=3
Dn Slope=0.005

--- Twin Creek147.g01 (geometry) ---

Geom Title=Existing Conditions

River Reach=Twin Creek147,Reach-1
Reach XY= 30
      2721426.00      6808111.00      2721427.21      6808020.57
      2721472.70      6807959.26      2721474.39      6807917.03
      2721287.25      6807720.99      2721317.93      6807664.13
      2721314.91      6807650.63      2721274.97      6807614.61
      2721181.89      6807608.85      2721145.73      6807581.51
      2721084.15      6807517.07      2721065.20      6807451.33
      2720984.18      6807367.04      2720965.23      6807301.30
      2720882.07      6807219.15      2720819.95      6807202.80
      2720725.98      6807118.08      2720636.78      6807201.31
      2720620.15      6807263.85      2720579.66      6807303.33
      2720524.38      6807265.44      2720473.81      6807254.87
      2720411.88      6807211.28      2720377.64      6807214.60
      2720326.00      6807253.38      2720274.35      6807214.64
      2720236.64      6807211.99      2720172.59      6807253.18
      2719985.79      6807071.52      2719926.00      6807061.00

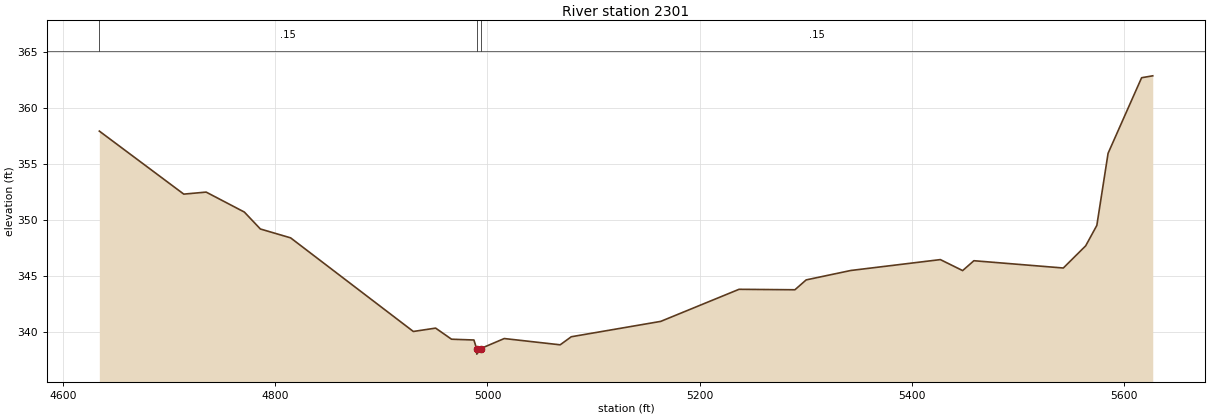
Type RM Length L Ch R = 1,2301,0,0,0
BEGIN DESCRIPTION:
Twin Creek147 1.0
END DESCRIPTION:
XS GIS Cut Line= 3
      2721676.01      6808261.02      2721476.00      6807961.00
      2720876.03      6808160.99
#Sta/Elev= 30
  4634.1  357.92  4713.7  352.30  4734.8  352.48  4770.8  350.70  4785.9  349.19
  4814.4  348.40  4930.1  340.05  4951.1  340.35  4966.1  339.36  4987.2  339.29
  4989.7  338.53  4989.9  338.03  4993.7  338.53  5015.8  339.42  5068.5  338.86
  5079.0  339.58  5163.3  340.95  5237.1  343.81  5289.8  343.77  5300.4  344.65
  5342.5  345.49  5426.9  346.46  5447.9  345.48  5458.5  346.36  5542.8  345.71
  5563.9  347.69  5574.4  349.51  5585.0  355.94  5616.6  362.68  5627.1  362.85
#Mann=3,-1,0
  4634.1    0.15       0  4989.7    0.05       0  4993.7    0.15       0
Bank Sta=4989.7,4993.7
Exp/Cntr=0.3,0.1

Chan Stop Cuts=-1