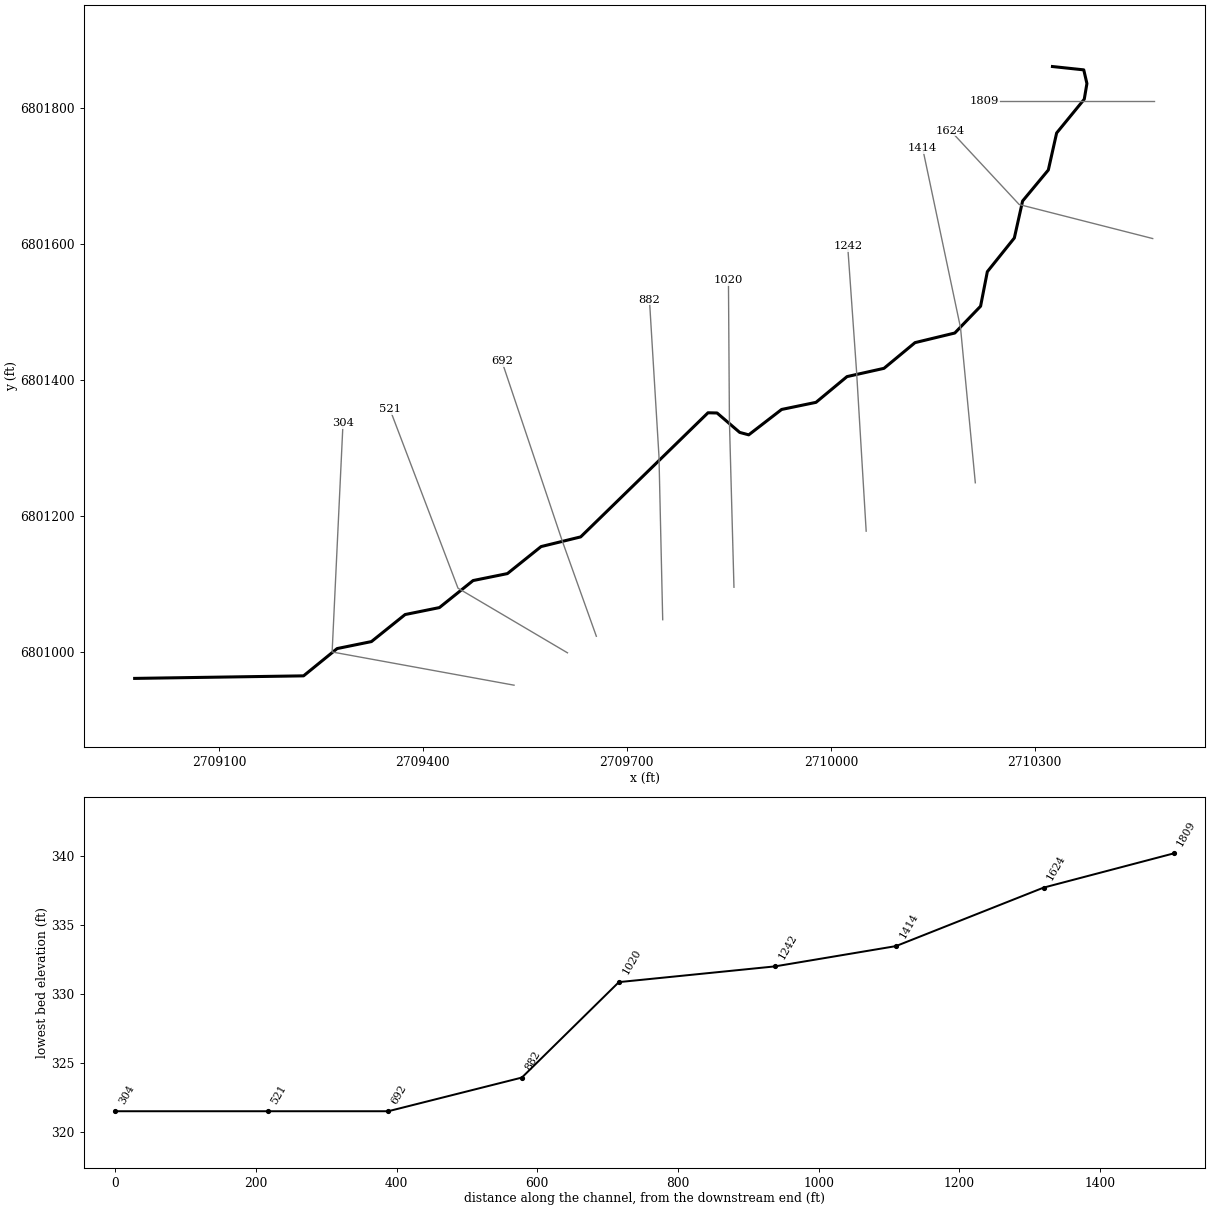
--- Twin Creek151.prj (project) ---

Proj Title=Twin Creek151 Base Level Engineering
Current Plan=p01
Default Exp/Contr=0.3,0.1
English Units
Geom File=g01
Flow File=f01
Plan File=p01
BEGIN DESCRIPTION:
Twin Creek151
END DESCRIPTION:

--- Twin Creek151.p01 (plan) ---

Plan Title=Multiple Run
Short Identifier=Multiple
Geom File=g01
Flow File=f01
Subcritical Flow
K Sum by GR= 0
Std Step Tol= 0.01
Critical Tol= 0.01
Num of Std Step Trials= 20
Max Error Tol= 0.3
Flow Tol Ratio= 0.001
Split Flow NTrial= 30
Split Flow Tol= 0.02
Split Flow Ratio= 0.02
Log Output Level= 0
Friction Slope Method= 1
Unsteady Friction Slope Method= 2
Unsteady Bridges Friction Slope Method= 1
Parabolic Critical Depth
Global Vel Dist=  1 , 1 , 1
Global Log Level= 0
CheckData=True
Encroach Param= -1, 0, 0, 0
BEGIN DESCRIPTION:
Multiple Run
END DESCRIPTION:

--- Twin Creek151.f01 (steady flow) ---

Flow Title=Multiple
Number of Profiles=7
Profile Names=10-year,25-year,50-year,1pct_min,100-year,1pct_plu,500-year
River Rch & RM= Twin Creek151,Reach-1,1809
     144     175     198     112     223     446     282
Boundary for River Rch & Prof#=Twin Creek151,Reach-1,1
Up Type=0
Dn Type=3
Dn Slope=0.005
Boundary for River Rch & Prof#=Twin Creek151,Reach-1,2
Up Type=0
Dn Type=3
Dn Slope=0.005
Boundary for River Rch & Prof#=Twin Creek151,Reach-1,3
Up Type=0
Dn Type=3
Dn Slope=0.005
Boundary for River Rch & Prof#=Twin Creek151,Reach-1,4
Up Type=0
Dn Type=3
Dn Slope=0.005
Boundary for River Rch & Prof#=Twin Creek151,Reach-1,5
Up Type=0
Dn Type=3
Dn Slope=0.005
Boundary for River Rch & Prof#=Twin Creek151,Reach-1,6
Up Type=0
Dn Type=3
Dn Slope=0.005
Boundary for River Rch & Prof#=Twin Creek151,Reach-1,7
Up Type=0
Dn Type=3
Dn Slope=0.005

--- Twin Creek151.g01 (geometry) ---

Geom Title=Existing Conditions

River Reach=Twin Creek151,Reach-1
Reach XY= 30
      2710326.00      6801861.00      2710372.03      6801856.10
      2710376.68      6801835.99      2710372.77      6801812.91
      2710332.13      6801763.23      2710319.92      6801708.81
      2710282.08      6801663.20      2710269.92      6801608.80
      2710230.20      6801559.24      2710220.27      6801508.45
      2710182.34      6801469.02      2710123.84      6801454.89
      2710078.20      6801417.08      2710023.80      6801404.92
      2709978.19      6801367.05      2709927.63      6801356.59
      2709879.23      6801319.25      2709865.95      6801322.84
      2709832.66      6801351.40      2709819.33      6801351.70
      2709632.06      6801169.14      2709573.81      6801154.90
      2709524.28      6801115.16      2709473.80      6801104.92
      2709424.28      6801065.16      2709373.80      6801054.92
      2709324.28      6801015.16      2709273.82      6801004.88
      2709224.45      6800964.75      2708976.00      6800961.00

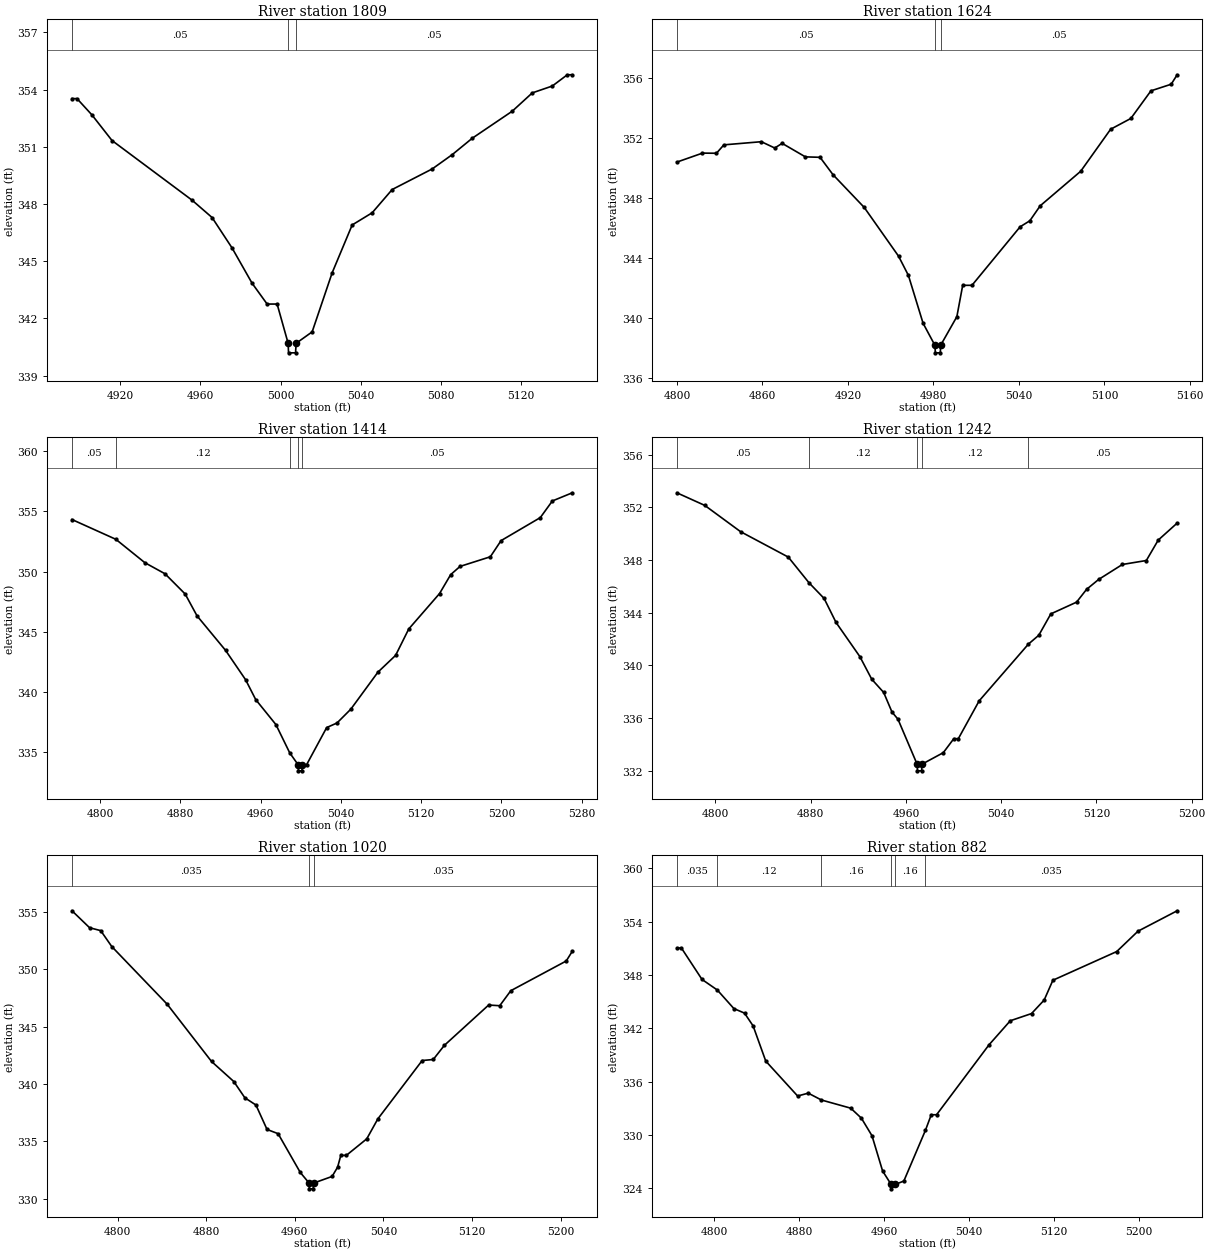
Type RM Length L Ch R = 1,1809,185,185,185
BEGIN DESCRIPTION:
Twin Creek1511808.572
END DESCRIPTION:
XS GIS Cut Line= 3
      2710475.98      6801811.00      2710376.00      6801811.00
      2710225.98      6801811.00
#Sta/Elev= 27
  4895.8  353.53  4898.3  353.53  4905.8  352.67  4915.8  351.33  4955.8  348.20
  4965.8  347.29  4975.8  345.69  4985.8  343.84  4993.3  342.75  4998.3  342.75
  5003.8  340.69  5004.0  340.19  5007.5  340.19  5007.8  340.69  5015.8  341.29
  5025.8  344.39  5035.8  346.90  5045.8  347.54  5055.8  348.76  5075.8  349.84
  5085.8  350.59  5095.8  351.45  5115.8  352.87  5125.8  353.83  5135.8  354.19
  5143.3  354.78  5145.8  354.78
#Mann=3,-1,0
  4895.8    0.05       0  5003.8    0.05       0  5007.8    0.05       0
Bank Sta=5003.8,5007.8
Exp/Cntr=0.3,0.1

Type RM Length L Ch R = 1,1624,210,210,210
BEGIN DESCRIPTION:
Twin Creek1511624.31
END DESCRIPTION:
XS GIS Cut Line= 3
      2710473.43      6801607.98      2710277.07      6801658.03
      2710175.93      6801766.72
#Sta/Elev= 30
  4799.9  350.42  4817.9  351.02  4827.7  351.01  4832.9  351.57  4859.2  351.78
  4868.6  351.36  4873.8  351.67  4890.1  350.77  4900.4  350.74  4909.5  349.58
  4931.4  347.40  4955.5  344.15  4962.4  342.87  4972.7  339.68  4981.0  338.21
  4981.3  337.71  4984.8  337.71  4985.0  338.21  4996.4  340.12  5000.5  342.21
  5007.0  342.21  5040.8  346.11  5047.6  346.51  5054.9  347.51  5083.3  349.81
  5104.3  352.61  5118.5  353.33  5132.6  355.17  5146.8  355.61  5151.0  356.24
#Mann=3,-1,0
  4799.9    0.05       0  4981.0    0.05       0  4985.0    0.05       0
Bank Sta=4981,4985
Exp/Cntr=0.3,0.1

Type RM Length L Ch R = 1,1414,172,172,172
BEGIN DESCRIPTION:
Twin Creek1511414.35
END DESCRIPTION:
XS GIS Cut Line= 3
      2710212.52      6801248.73      2710190.76      6801476.82
      2710135.10      6801740.49
#Sta/Elev= 30
  4772.1  354.32  4815.8  352.68  4844.7  350.74  4864.8  349.82  4884.9  348.14
  4896.7  346.33  4925.1  343.47  4945.1  341.03  4955.2  339.38  4975.3  337.31
  4989.1  334.96  4997.5  333.97  4997.8  333.47  5001.3  333.47  5001.5  333.97
  5005.9  333.98  5025.9  337.06  5036.2  337.44  5050.0  338.59  5077.0  341.66
  5094.6  343.05  5107.7  345.24  5138.4  348.18  5149.5  349.75  5158.8  350.43
  5189.0  351.23  5199.7  352.57  5238.8  354.48  5250.8  355.86  5270.7  356.54
#Mann=5,-1,0
  4772.1    0.05       0  4815.8    0.12       0  4989.1    0.05       0
  4997.5    0.05       0  5001.5    0.05       0
Bank Sta=4997.5,5001.5
Exp/Cntr=0.3,0.1

Type RM Length L Ch R = 1,1242,222,222,222
BEGIN DESCRIPTION:
Twin Creek1511242.12
END DESCRIPTION:
XS GIS Cut Line= 3
      2710051.99      6801177.57      2710037.77      6801413.58
      2710024.80      6801596.88
#Sta/Elev= 30
  4767.6  353.10  4791.1  352.14  4821.1  350.15  4861.2  348.22  4878.6  346.27
  4891.3  345.08  4901.3  343.26  4921.3  340.67  4931.3  338.95  4941.3  337.95
  4948.3  336.46  4953.3  335.92  4969.4  332.50  4969.7  332.00  4973.2  332.00
  4973.4  332.50  4991.4  333.38  5000.2  334.44  5004.0  334.44  5021.5  337.31
  5062.9  341.62  5071.6  342.29  5081.7  343.91  5103.3  344.80  5111.7  345.77
  5121.8  346.52  5141.8  347.66  5161.9  347.96  5171.9  349.51  5187.8  350.80
#Mann=5,-1,0
  4767.6    0.05       0  4878.6    0.12       0  4969.4    0.07       0
  4973.4    0.12       0  5062.9    0.05       0
Bank Sta=4969.4,4973.4
Exp/Cntr=0.3,0.1

Type RM Length L Ch R = 1,1020,138,138,138
BEGIN DESCRIPTION:
Twin Creek1511019.88
END DESCRIPTION:
XS GIS Cut Line= 3
      2709857.52      6801095.10      2709850.84      6801339.17
      2709849.41      6801546.50
#Sta/Elev= 30
  4758.9  355.11  4774.8  353.63  4784.8  353.38  4794.8  351.99  4844.8  346.96
  4884.8  341.97  4904.9  340.22  4914.9  338.80  4924.9  338.17  4934.9  336.04
  4944.9  335.67  4964.9  332.29  4972.9  331.36  4973.1  330.86  4976.6  330.86
  4976.9  331.36  4993.6  331.94  4998.6  332.75  5001.5  333.78  5006.5  333.78
  5024.9  335.22  5034.9  336.96  5074.9  342.05  5084.9  342.14  5094.9  343.37
  5134.9  346.89  5144.9  346.83  5154.9  348.14  5204.9  350.73  5210.4  351.58
#Mann=3,-1,0
  4758.9   0.035       0  4972.9   0.035       0  4976.9   0.035       0
Bank Sta=4972.9,4976.9
Exp/Cntr=0.3,0.1

Type RM Length L Ch R = 1,882,190,190,190
BEGIN DESCRIPTION:
Twin Creek151881.96
END DESCRIPTION:
XS GIS Cut Line= 3
      2709752.71      6801047.32      2709747.23      6801287.45
      2709733.21      6801517.83
#Sta/Elev= 30
  4764.8  351.05  4769.1  351.05  4788.5  347.51  4802.9  346.32  4818.5  344.23
  4828.5  343.72  4836.6  342.28  4848.5  338.32  4878.5  334.39  4888.5  334.71
  4900.9  333.94  4928.5  333.02  4938.5  331.90  4948.5  329.92  4958.5  325.95
  4966.5  324.44  4966.8  323.94  4970.5  324.44  4978.5  324.82  4998.8  330.52
  5004.3  332.28  5009.3  332.28  5058.6  340.14  5078.7  342.86  5098.7  343.67
  5110.6  345.19  5118.8  347.42  5178.9  350.65  5198.9  352.94  5235.8  355.24
#Mann=6,-1,0
  4764.8   0.035       0  4802.9    0.12       0  4900.9    0.16       0
  4966.5   0.035       0  4970.5    0.16       0  4998.8   0.035       0
Bank Sta=4966.5,4970.5
Exp/Cntr=0.3,0.1

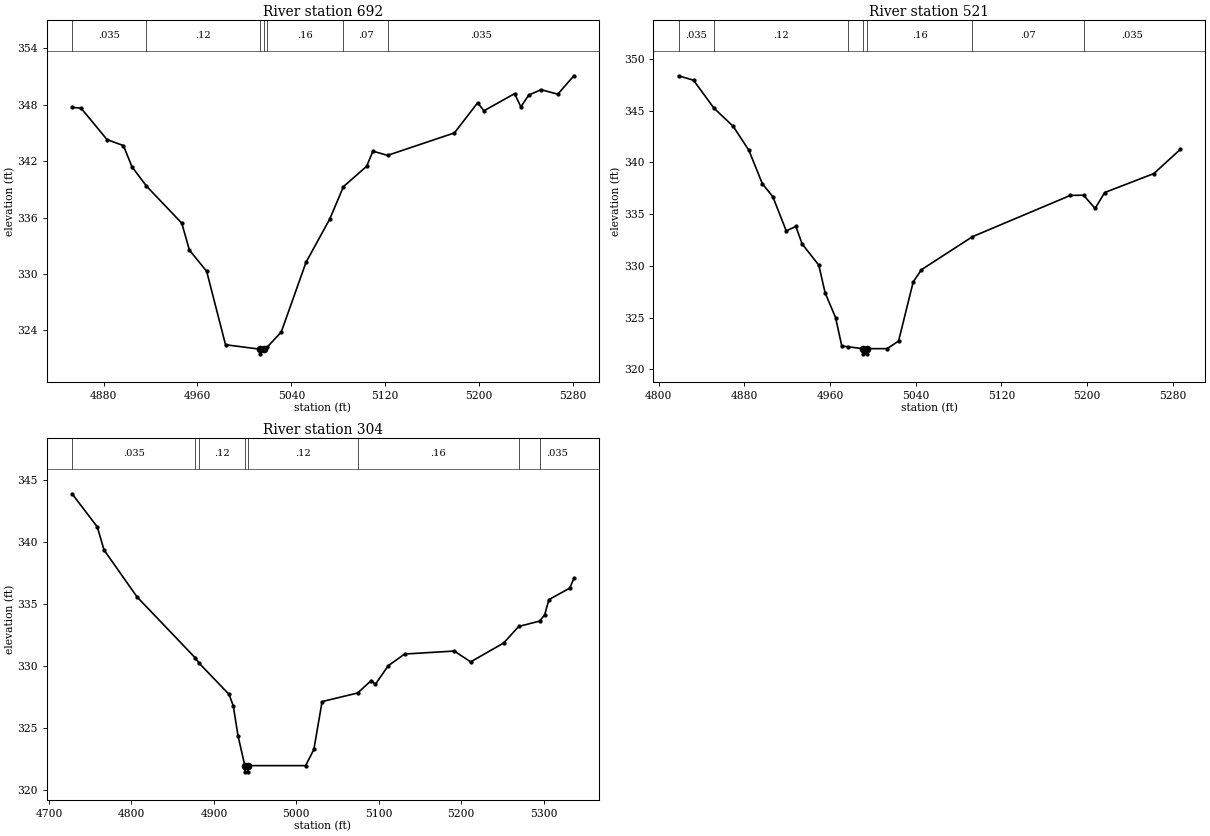
Type RM Length L Ch R = 1,692,171,171,171
BEGIN DESCRIPTION:
Twin Creek151692.3
END DESCRIPTION:
XS GIS Cut Line= 3
      2709655.09      6801022.98      2709604.42      6801164.70
      2709516.15      6801427.46
#Sta/Elev= 30
  4853.1  347.73  4860.8  347.64  4882.9  344.30  4896.9  343.66  4904.1  341.42
  4916.5  339.35  4946.6  335.41  4953.1  332.54  4967.8  330.29  4983.9  322.47
  5012.9  322.00  5013.2  321.50  5016.9  322.00  5019.5  322.23  5031.4  323.82
  5052.5  331.24  5072.7  335.84  5084.4  339.29  5104.2  341.46  5109.5  343.07
  5122.0  342.62  5179.0  345.01  5198.8  348.22  5204.1  347.36  5230.3  349.19
  5235.6  347.78  5242.3  349.03  5252.9  349.61  5267.1  349.13  5280.8  351.09
#Mann=7,-1,0
  4853.1   0.035       0  4916.5    0.12       0  5012.9    0.07       0
  5016.9    0.12       0  5019.5    0.16       0  5084.4    0.07       0
  5122.0   0.035       0
Bank Sta=5012.9,5016.9
Exp/Cntr=0.3,0.1

Type RM Length L Ch R = 1,521,217,217,217
BEGIN DESCRIPTION:
Twin Creek151521.46
END DESCRIPTION:
XS GIS Cut Line= 3
      2709612.60      6800998.65      2709451.61      6801093.67
      2709351.41      6801357.01
#Sta/Elev= 30
  4818.4  348.37  4832.4  347.94  4851.5  345.24  4869.5  343.48  4884.1  341.17
  4896.7  337.94  4906.5  336.68  4919.0  333.38  4928.0  333.81  4933.8  332.13
  4949.4  330.07  4955.3  327.40  4965.1  325.00  4970.9  322.25  4976.3  322.19
  4990.3  322.00  4990.6  321.50  4994.1  321.50  4994.3  322.00  5013.2  322.00
  5023.9  322.73  5037.6  328.45  5045.3  329.63  5092.9  332.82  5184.4  336.81
  5196.7  336.83  5207.5  335.55  5216.5  337.09  5262.4  338.92  5287.1  341.26
#Mann=7,-1,0
  4818.4   0.035       0  4851.5    0.12       0  4976.3    0.16       0
  4990.3    0.07       0  4994.3    0.16       0  5092.9    0.07       0
  5196.7   0.035       0
Bank Sta=4990.3,4994.3
Exp/Cntr=0.3,0.1

Type RM Length L Ch R = 1,304,0,0,0
BEGIN DESCRIPTION:
Twin Creek151303.873
END DESCRIPTION:
XS GIS Cut Line= 3
      2709534.05      6800951.03      2709266.47      6800999.86
      2709282.45      6801335.98
#Sta/Elev= 30
  4728.0  343.90  4758.6  341.23  4766.7  339.38  4806.8  335.59  4877.4  330.68
  4882.1  330.25  4918.4  327.74  4923.5  326.81  4929.3  324.38  4937.5  322.00
  4937.7  321.50  4941.2  321.50  4941.5  322.00  5011.2  322.00  5021.2  323.30
  5031.2  327.16  5074.2  327.85  5090.8  328.85  5095.8  328.55  5111.3  330.04
  5131.3  330.99  5191.4  331.23  5211.4  330.36  5251.4  331.88  5269.6  333.21
  5295.3  333.65  5301.2  334.17  5306.2  335.37  5331.5  336.30  5336.5  337.08
#Mann=8,-1,0
  4728.0   0.035       0  4877.4    0.16       0  4882.1    0.12       0
  4937.5    0.07       0  4941.5    0.12       0  5074.2    0.16       0
  5269.6    0.07       0  5295.3   0.035       0
Bank Sta=4937.5,4941.5
Exp/Cntr=0.3,0.1

Chan Stop Cuts=-1