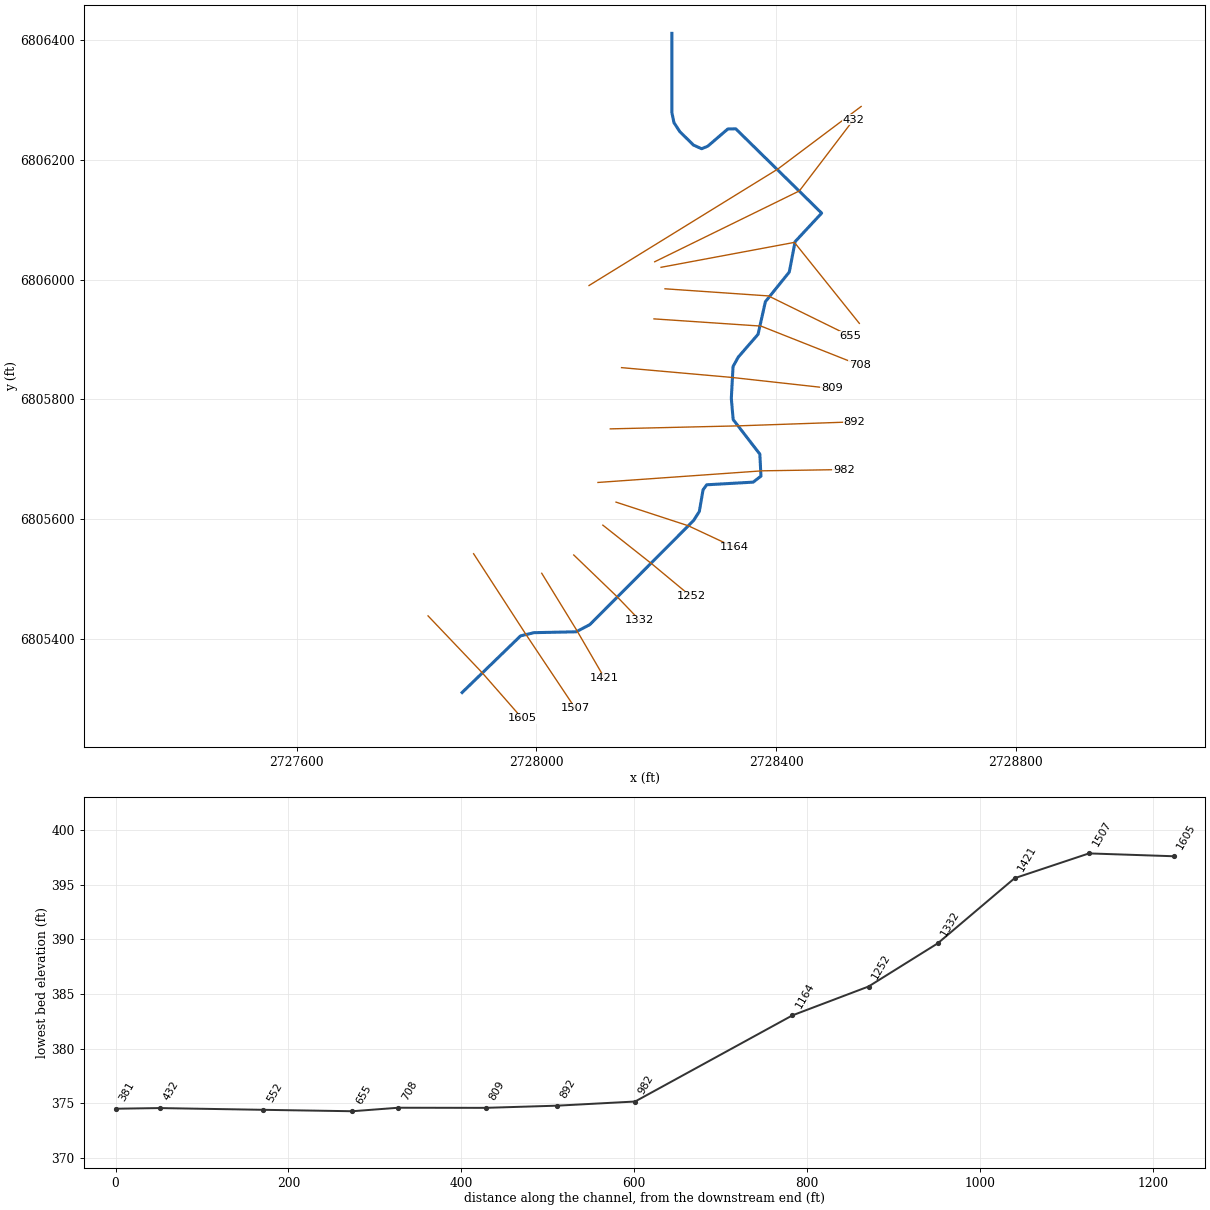
--- Twin Creek153.prj (project) ---

Proj Title=Twin Creek153 Base Level Engineering
Current Plan=p01
Default Exp/Contr=0.3,0.1
English Units
Geom File=g01
Flow File=f01
Plan File=p01
BEGIN DESCRIPTION:
Twin Creek153
END DESCRIPTION:

--- Twin Creek153.p01 (plan) ---

Plan Title=Multiple Run
Short Identifier=Multiple
Geom File=g01
Flow File=f01
Subcritical Flow
K Sum by GR= 0
Std Step Tol= 0.01
Critical Tol= 0.01
Num of Std Step Trials= 20
Max Error Tol= 0.3
Flow Tol Ratio= 0.001
Split Flow NTrial= 30
Split Flow Tol= 0.02
Split Flow Ratio= 0.02
Log Output Level= 0
Friction Slope Method= 1
Unsteady Friction Slope Method= 2
Unsteady Bridges Friction Slope Method= 1
Parabolic Critical Depth
Global Vel Dist=  1 , 1 , 1
Global Log Level= 0
CheckData=True
Encroach Param= -1, 0, 0, 0
BEGIN DESCRIPTION:
Multiple Run
END DESCRIPTION:

--- Twin Creek153.f01 (steady flow) ---

Flow Title=Multiple
Number of Profiles=7
Profile Names=10-year,25-year,50-year,1pct_min,100-year,1pct_plu,500-year
River Rch & RM= Twin Creek153,Reach-1,1605
      53      59      63      34      67     135      77
River Rch & RM= Twin Creek153,Reach-1,432
      92     108     119      66     131     261     158
Boundary for River Rch & Prof#=Twin Creek153,Reach-1,1
Up Type=0
Dn Type=3
Dn Slope=0.005
Boundary for River Rch & Prof#=Twin Creek153,Reach-1,2
Up Type=0
Dn Type=3
Dn Slope=0.005
Boundary for River Rch & Prof#=Twin Creek153,Reach-1,3
Up Type=0
Dn Type=3
Dn Slope=0.005
Boundary for River Rch & Prof#=Twin Creek153,Reach-1,4
Up Type=0
Dn Type=3
Dn Slope=0.005
Boundary for River Rch & Prof#=Twin Creek153,Reach-1,5
Up Type=0
Dn Type=3
Dn Slope=0.005
Boundary for River Rch & Prof#=Twin Creek153,Reach-1,6
Up Type=0
Dn Type=3
Dn Slope=0.005
Boundary for River Rch & Prof#=Twin Creek153,Reach-1,7
Up Type=0
Dn Type=3
Dn Slope=0.005

--- Twin Creek153.g01 (geometry) ---

Geom Title=Existing Conditions

River Reach=Twin Creek153,Reach-1
Reach XY= 30
      2727876.00      6805311.00      2727973.55      6805405.54
      2727996.05      6805410.87      2728066.36      6805412.31
      2728089.30      6805424.40      2728262.27      6805598.05
      2728271.85      6805613.08      2728278.06      6805649.24
      2728284.15      6805657.64      2728361.72      6805662.07
      2728374.68      6805672.05      2728372.83      6805708.82
      2728328.32      6805766.53      2728325.22      6805801.85
      2728328.14      6805855.03      2728336.75      6805870.65
      2728369.88      6805908.82      2728382.07      6805963.20
      2728421.96      6806012.67      2728431.67      6806063.36
      2728476.00      6806111.00      2728332.66      6806251.70
      2728319.31      6806251.38      2728285.85      6806222.64
      2728275.76      6806218.46      2728262.25      6806224.46
      2728239.36      6806246.87      2728229.50      6806261.97
      2728226.02      6806278.94      2728226.00      6806411.00

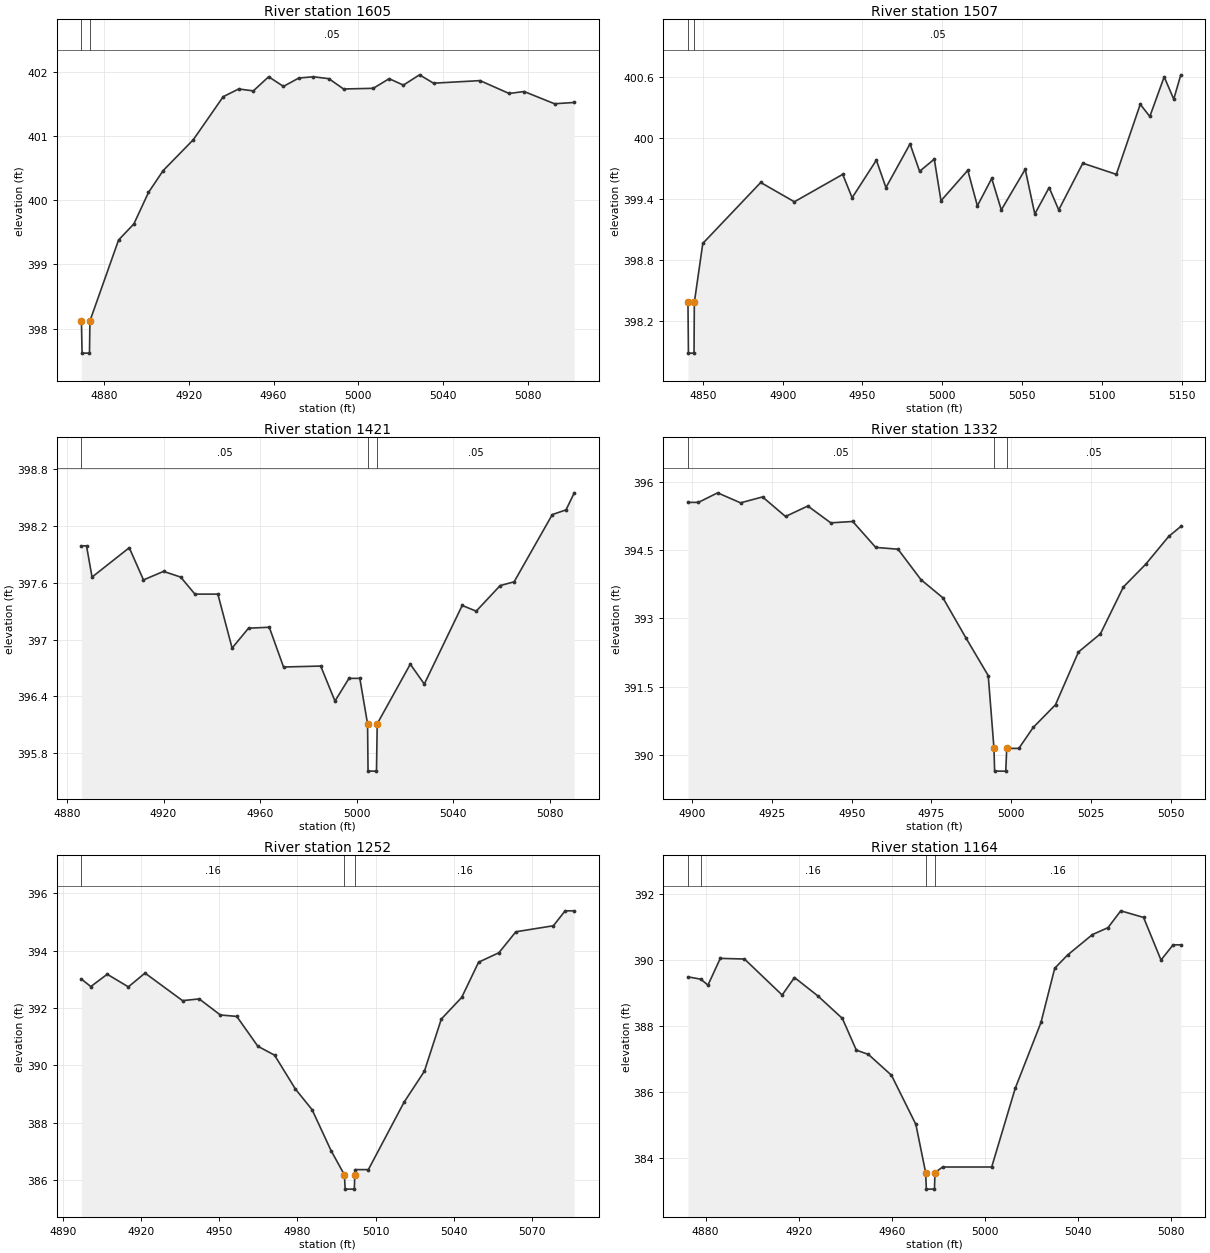
Type RM Length L Ch R = 1,1605,98,98,98
BEGIN DESCRIPTION:
Twin Creek1531120.458
END DESCRIPTION:
XS GIS Cut Line= 3
      2727819.16      6805438.87      2727909.16      6805344.37
      2727976.17      6805267.87
#Sta/Elev= 28
  4869.5  398.12  4869.8  397.62  4873.3  397.62  4873.5  398.12  4887.0  399.38
  4894.2  399.63  4901.1  400.12  4908.0  400.46  4922.2  400.94  4936.3  401.61
  4943.6  401.73  4950.5  401.70  4957.7  401.92  4964.7  401.77  4971.9  401.90
  4978.8  401.92  4986.1  401.89  4993.0  401.73  5007.0  401.74  5014.5  401.89
  5021.2  401.79  5028.8  401.95  5035.4  401.82  5057.3  401.86  5071.0  401.66
  5078.1  401.69  5092.4  401.50  5101.7  401.52
#Mann=2,-1,0
  4869.5    0.05       0  4873.5    0.05       0
Bank Sta=4869.5,4873.5
Exp/Cntr=0.3,0.1

Type RM Length L Ch R = 1,1507,86,86,86
BEGIN DESCRIPTION:
Twin Creek1531025.4
END DESCRIPTION:
XS GIS Cut Line= 3
      2727895.15      6805542.62      2727981.88      6805408.88
      2728064.86      6805284.52
#Sta/Elev= 30
  4840.6  398.38  4840.9  397.88  4844.4  397.88  4844.6  398.38  4849.9  398.96
  4886.2  399.56  4907.3  399.37  4937.6  399.64  4943.5  399.41  4958.7  399.78
  4964.7  399.51  4979.8  399.94  4985.8  399.67  4995.0  399.79  4999.2  399.38
  5016.0  399.68  5022.0  399.33  5031.0  399.60  5037.0  399.29  5052.0  399.69
  5058.0  399.25  5067.0  399.51  5073.0  399.29  5088.1  399.75  5109.1  399.64
  5124.1  400.33  5130.1  400.21  5139.1  400.60  5145.1  400.38  5149.5  400.62
#Mann=2,-1,0
  4840.6    0.05       0  4844.6    0.05       0
Bank Sta=4840.6,4844.6
Exp/Cntr=0.3,0.1

Type RM Length L Ch R = 1,1421,89,89,89
BEGIN DESCRIPTION:
Twin Creek153935.2
END DESCRIPTION:
XS GIS Cut Line= 3
      2728008.85      6805509.97      2728067.14      6805415.01
      2728113.74      6805334.91
#Sta/Elev= 30
  4886.0  397.99  4888.1  397.99  4890.4  397.66  4905.8  397.97  4911.7  397.63
  4920.0  397.72  4927.1  397.66  4933.0  397.48  4942.5  397.48  4948.4  396.91
  4955.2  397.12  4963.8  397.13  4969.7  396.71  4985.1  396.72  4991.0  396.35
  4996.8  396.59  5001.3  396.59  5004.5  396.11  5004.7  395.61  5008.2  395.61
  5008.5  396.11  5022.2  396.74  5028.0  396.53  5043.7  397.36  5049.5  397.30
  5059.4  397.57  5065.2  397.61  5081.0  398.32  5086.7  398.37  5090.1  398.55
#Mann=3,-1,0
  4886.0    0.05       0  5004.5    0.05       0  5008.5    0.05       0
Bank Sta=5004.5,5008.5
Exp/Cntr=0.3,0.1

Type RM Length L Ch R = 1,1332,80,80,80
BEGIN DESCRIPTION:
Twin Creek153846.57
END DESCRIPTION:
XS GIS Cut Line= 3
      2728062.33      6805540.49      2728134.77      6805470.72
      2728172.19      6805431.75
#Sta/Elev= 29
  4898.6  395.55  4901.9  395.55  4907.9  395.76  4915.1  395.54  4922.0  395.67
  4929.2  395.24  4936.2  395.47  4943.4  395.10  4950.3  395.13  4957.5  394.56
  4964.5  394.52  4971.7  393.85  4978.6  393.45  4985.8  392.57  4992.8  391.74
  4994.6  390.14  4994.8  389.64  4998.3  389.64  4998.6  390.14  4999.2  390.14
  5002.4  390.14  5006.9  390.60  5013.9  391.10  5021.1  392.26  5028.0  392.66
  5035.2  393.69  5042.2  394.19  5049.4  394.80  5053.2  395.02
#Mann=3,-1,0
  4898.6    0.05       0  4994.6    0.05       0  4998.6    0.05       0
Bank Sta=4994.6,4998.6
Exp/Cntr=0.3,0.1

Type RM Length L Ch R = 1,1252,88,88,88
BEGIN DESCRIPTION:
Twin Creek153766.99
END DESCRIPTION:
XS GIS Cut Line= 3
      2728110.83      6805590.30      2728193.24      6805525.12
      2728257.90      6805471.45
#Sta/Elev= 30
  4897.1  393.01  4900.7  392.75  4907.0  393.18  4915.1  392.74  4921.5  393.22
  4935.9  392.26  4942.3  392.32  4950.4  391.76  4956.7  391.71  4964.8  390.67
  4971.2  390.36  4979.2  389.18  4985.6  388.46  4992.9  387.03  4998.0  386.19
  4998.3  385.69  5001.8  385.69  5002.0  386.19  5002.2  386.37  5007.2  386.37
  5020.9  388.72  5028.7  389.80  5035.2  391.62  5043.0  392.37  5049.5  393.60
  5057.3  393.93  5063.8  394.66  5078.2  394.87  5082.7  395.39  5086.2  395.39
#Mann=3,-1,0
  4897.1    0.16       0  4998.0    0.07       0  5002.0    0.16       0
Bank Sta=4998,5002
Exp/Cntr=0.3,0.1

Type RM Length L Ch R = 1,1164,182,182,182
BEGIN DESCRIPTION:
Twin Creek153678.58
END DESCRIPTION:
XS GIS Cut Line= 3
      2728132.86      6805628.71      2728253.32      6805589.30
      2728330.46      6805553.23
#Sta/Elev= 30
  4872.4  389.48  4877.9  389.41  4881.0  389.23  4886.3  390.04  4896.7  390.02
  4912.9  388.93  4918.2  389.46  4928.3  388.90  4938.8  388.22  4944.8  387.26
  4950.0  387.13  4959.9  386.50  4970.4  385.01  4974.6  383.55  4974.9  383.05
  4978.4  383.05  4978.6  383.55  4981.9  383.72  5003.0  383.72  5013.1  386.10
  5024.2  388.10  5030.1  389.74  5035.6  390.14  5046.3  390.76  5053.0  390.97
  5058.5  391.48  5068.3  391.28  5075.8  389.99  5081.0  390.45  5084.3  390.45
#Mann=4,-1,0
  4872.4    0.05       0  4877.9    0.16       0  4974.6    0.07       0
  4978.6    0.16       0
Bank Sta=4974.6,4978.6
Exp/Cntr=0.3,0.1

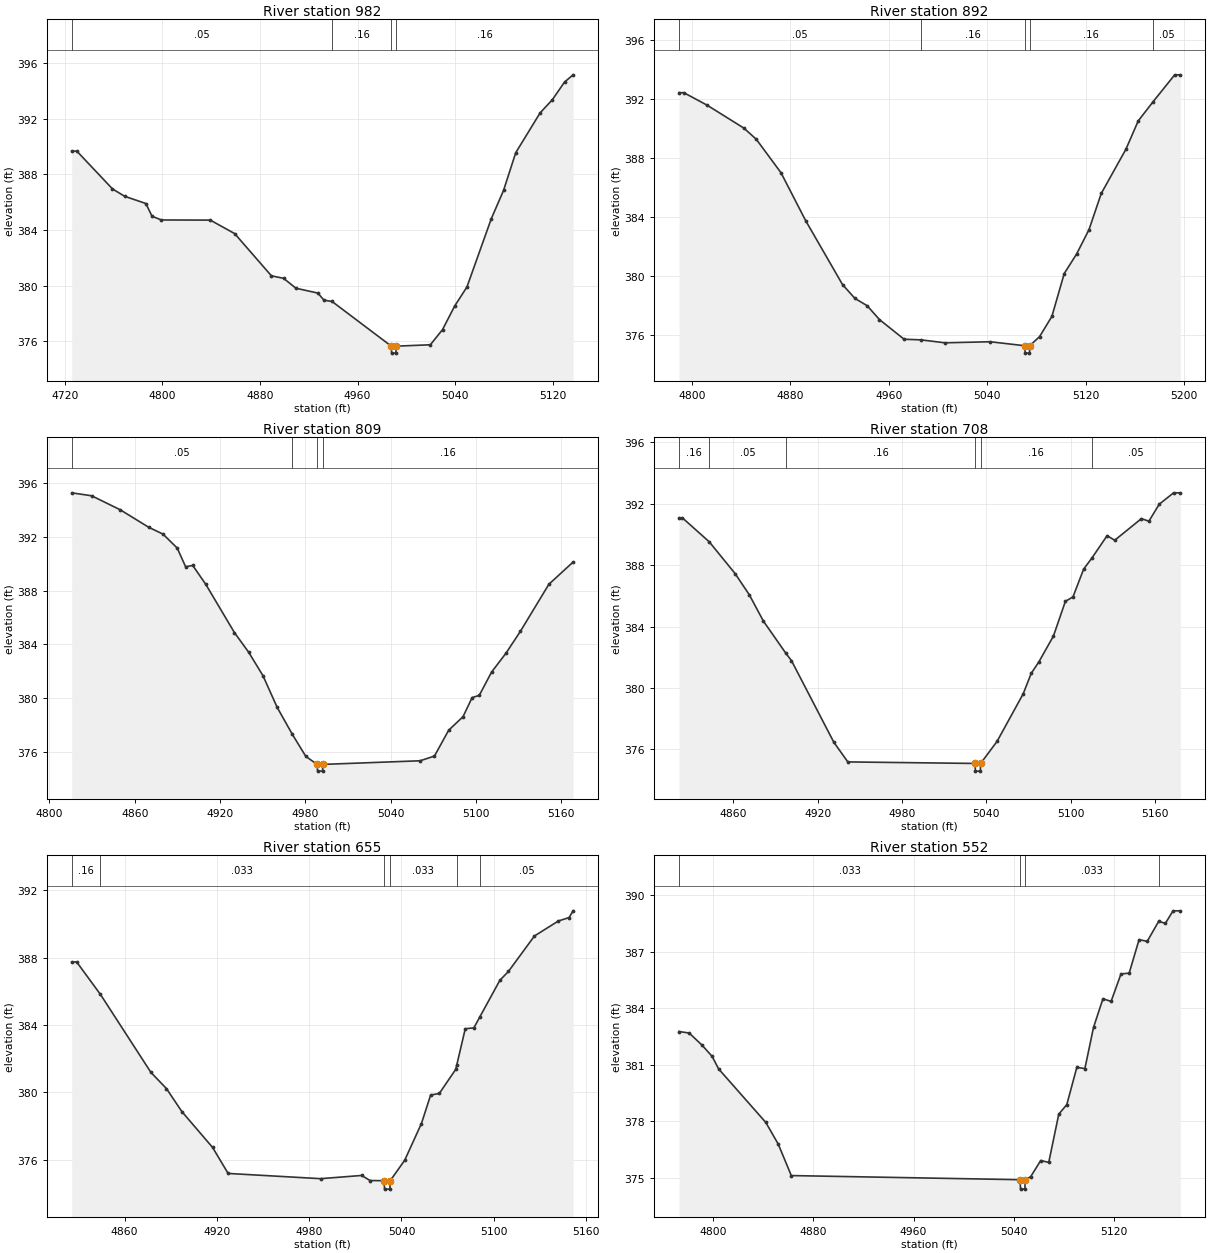
Type RM Length L Ch R = 1,982,90,90,90
BEGIN DESCRIPTION:
Twin Creek153496.57
END DESCRIPTION:
XS GIS Cut Line= 3
      2728102.71      6805661.54      2728377.10      6805680.96
      2728513.00      6805683.07
#Sta/Elev= 30
  4725.7  389.66  4729.9  389.66  4759.1  386.95  4769.1  386.42  4786.5  385.90
  4791.5  384.99  4799.2  384.72  4839.3  384.71  4859.3  383.74  4889.4  380.71
  4899.4  380.53  4909.5  379.82  4927.5  379.47  4932.5  378.96  4939.1  378.87
  4987.7  375.66  4987.9  375.16  4991.4  375.16  4991.7  375.66  5019.7  375.76
  5029.7  376.85  5039.7  378.55  5049.7  379.91  5069.7  384.82  5079.7  386.84
  5089.7  389.55  5109.7  392.41  5119.7  393.35  5129.7  394.62  5136.7  395.14
#Mann=4,-1,0
  4725.7    0.05       0  4939.1    0.16       0  4987.7    0.07       0
  4991.7    0.16       0
Bank Sta=4987.7,4991.7
Exp/Cntr=0.3,0.1

Type RM Length L Ch R = 1,892,83,83,83
BEGIN DESCRIPTION:
Twin Creek153406.62
END DESCRIPTION:
XS GIS Cut Line= 3
      2728123.27      6805750.97      2728335.49      6805755.94
      2728530.20      6805762.67
#Sta/Elev= 30
  4789.7  392.42  4793.6  392.42  4812.4  391.58  4842.4  390.02  4852.4  389.27
  4872.5  387.00  4892.5  383.76  4922.5  379.42  4932.5  378.49  4942.5  377.99
  4952.5  377.05  4972.5  375.72  4986.0  375.68  5005.6  375.48  5042.5  375.55
  5070.5  375.28  5070.8  374.78  5074.3  374.78  5074.5  375.28  5082.5  375.90
  5092.5  377.27  5102.5  380.17  5112.6  381.50  5122.6  383.14  5132.6  385.60
  5152.6  388.59  5162.6  390.51  5174.4  391.78  5192.2  393.63  5196.8  393.63
#Mann=5,-1,0
  4789.7    0.05       0  4986.0    0.16       0  5070.5    0.07       0
  5074.5    0.16       0  5174.4    0.05       0
Bank Sta=5070.5,5074.5
Exp/Cntr=0.3,0.1

Type RM Length L Ch R = 1,809,101,101,101
BEGIN DESCRIPTION:
Twin Creek153324.18
END DESCRIPTION:
XS GIS Cut Line= 3
      2728142.06      6805853.15      2728325.32      6805836.88
      2728492.92      6805818.34
#Sta/Elev= 30
  4815.7  395.28  4829.7  395.06  4849.8  394.02  4869.8  392.72  4879.9  392.21
  4889.9  391.17  4895.8  389.78  4900.8  389.88  4910.0  388.47  4930.1  384.89
  4940.1  383.43  4950.2  381.68  4960.2  379.32  4970.9  377.31  4980.3  375.68
  4988.3  375.08  4988.6  374.58  4992.1  374.58  4992.3  375.08  5060.7  375.35
  5070.8  375.70  5080.8  377.62  5090.9  378.63  5097.3  380.05  5102.3  380.21
  5111.0  381.95  5121.1  383.35  5131.2  384.97  5151.3  388.48  5168.3  390.13
#Mann=4,-1,0
  4815.7    0.05       0  4970.9    0.16       0  4988.3    0.07       0
  4992.3    0.16       0
Bank Sta=4988.3,4992.3
Exp/Cntr=0.3,0.1

Type RM Length L Ch R = 1,708,53,53,53
BEGIN DESCRIPTION:
Twin Creek153222.71
END DESCRIPTION:
XS GIS Cut Line= 3
      2728196.15      6805934.52      2728374.79      6805922.47
      2728539.96      6805857.05
#Sta/Elev= 30
  4821.3  391.09  4823.7  391.09  4842.8  389.53  4861.2  387.46  4871.3  386.08
  4881.3  384.37  4897.3  382.27  4901.3  381.79  4931.4  376.48  4941.4  375.19
  5031.9  375.09  5032.2  374.59  5035.7  374.59  5035.9  375.09  5047.6  376.53
  5066.2  379.63  5071.9  380.96  5077.3  381.70  5087.7  383.39  5096.2  385.65
  5101.6  385.94  5109.2  387.75  5115.2  388.49  5125.9  389.93  5131.3  389.63
  5150.3  391.04  5155.6  390.87  5163.0  391.98  5173.2  392.72  5178.0  392.72
#Mann=6,-1,0
  4821.3    0.16       0  4842.8    0.05       0  4897.3    0.16       0
  5031.9    0.07       0  5035.9    0.16       0  5115.2    0.05       0
Bank Sta=5031.9,5035.9
Exp/Cntr=0.3,0.1

Type RM Length L Ch R = 1,655,103,103,103
BEGIN DESCRIPTION:
Mapping XS 6cf0810d
END DESCRIPTION:
XS GIS Cut Line= 3
      2728214.59      6805984.72      2728387.19      6805972.83
      2728524.51      6805905.39
#Sta/Elev= 30
  4825.6  387.74  4828.8  387.74  4844.3  385.81  4877.1  381.19  4887.2  380.23
  4897.2  378.87  4917.2  376.74  4927.3  375.20  4987.4  374.89  5014.1  375.08
  5019.6  374.78  5028.7  374.77  5029.0  374.27  5032.5  374.27  5032.7  374.77
  5042.1  375.98  5053.0  378.16  5059.0  379.85  5064.6  379.94  5075.3  381.37
  5075.9  381.60  5081.5  383.78  5087.1  383.83  5090.9  384.47  5104.0  386.65
  5109.6  387.18  5126.5  389.28  5142.1  390.17  5149.0  390.37  5151.6  390.77
#Mann=6,-1,0
  4825.6    0.16       0  4844.3   0.033       0  5028.7   0.033       0
  5032.7   0.033       0  5075.9    0.16       0  5090.9    0.05       0
Bank Sta=5028.7,5032.7
Exp/Cntr=0.3,0.1

Type RM Length L Ch R = 1,552,120,120,120
BEGIN DESCRIPTION:
Mapping XS eaaf46ab
END DESCRIPTION:
XS GIS Cut Line= 3
      2728207.99      6806020.59      2728430.54      6806062.17
      2728538.86      6805927.02
#Sta/Elev= 30
  4773.0  382.77  4781.1  382.69  4791.3  382.05  4799.4  381.45  4804.5  380.79
  4842.2  377.94  4852.1  376.79  4862.5  375.12  5044.9  374.90  5045.2  374.40
  5048.7  374.40  5048.9  374.90  5053.3  375.06  5061.3  375.92  5067.7  375.82
  5075.7  378.38  5082.1  378.89  5090.1  380.87  5096.5  380.80  5103.4  382.99
  5110.9  384.51  5117.4  384.37  5125.3  385.83  5131.8  385.87  5139.7  387.65
  5146.2  387.56  5155.4  388.63  5160.6  388.51  5166.8  389.18  5172.6  389.18
#Mann=4,-1,0
  4773.0   0.033       0  5044.9   0.033       0  5048.9   0.033       0
  5155.4    0.05       0
Bank Sta=5044.9,5048.9
Exp/Cntr=0.3,0.1

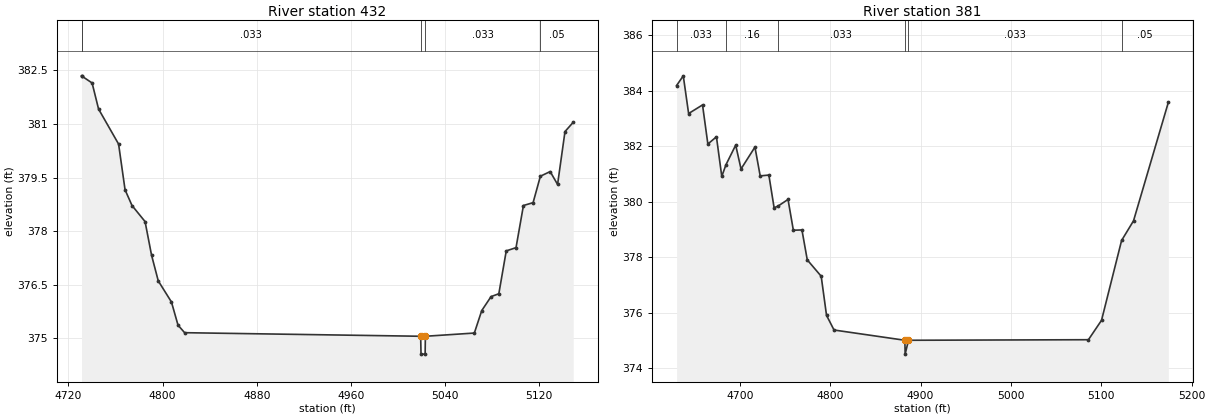
Type RM Length L Ch R = 1,432,51,51,51
BEGIN DESCRIPTION:
Mapping XS dfa81911
END DESCRIPTION:
XS GIS Cut Line= 3
      2728197.43      6806029.85      2728438.82      6806148.09
      2728529.01      6806266.57
#Sta/Elev= 30
  4731.1  382.35  4731.5  382.34  4740.1  382.15  4745.6  381.42  4762.6  380.44
  4768.1  379.16  4774.0  378.72  4785.1  378.27  4790.6  377.33  4796.3  376.61
  4807.5  376.02  4813.1  375.37  4818.7  375.16  5019.2  375.06  5019.5  374.56
  5023.0  374.56  5023.2  375.06  5064.8  375.15  5071.1  375.78  5079.0  376.17
  5085.6  376.25  5091.9  377.45  5100.2  377.54  5106.5  378.72  5114.7  378.80
  5120.9  379.54  5129.2  379.67  5135.5  379.31  5141.8  380.79  5148.8  381.05
#Mann=5,-1,0
  4731.1    0.16       0  4731.5   0.033       0  5019.2   0.033       0
  5023.2   0.033       0  5120.9    0.05       0
Bank Sta=5019.2,5023.2
Exp/Cntr=0.3,0.1

Type RM Length L Ch R = 1,381,0,0,0
BEGIN DESCRIPTION:
Twin Creek15374.283
END DESCRIPTION:
XS GIS Cut Line= 3
      2728087.77      6805990.18      2728402.67      6806184.45
      2728541.89      6806288.98
#Sta/Elev= 30
  4630.0  384.19  4637.4  384.54  4643.3  383.18  4658.7  383.49  4664.6  382.08
  4674.1  382.34  4680.0  380.91  4684.6  381.33  4695.4  382.04  4701.3  381.18
  4716.7  381.97  4722.5  380.93  4732.1  380.96  4737.9  379.78  4742.2  379.84
  4753.3  380.08  4759.2  378.97  4768.7  378.98  4774.6  377.90  4790.0  377.31
  4795.9  375.90  4804.2  375.37  4882.6  375.00  4882.9  374.50  4886.6  375.00
  5085.7  375.02  5100.2  375.72  5122.4  378.60  5135.6  379.31  5174.1  383.58
#Mann=6,-1,0
  4630.0   0.033       0  4684.6    0.16       0  4742.2   0.033       0
  4882.6   0.033       0  4886.6   0.033       0  5122.4    0.05       0
Bank Sta=4882.6,4886.6
Exp/Cntr=0.3,0.1

Chan Stop Cuts=-1