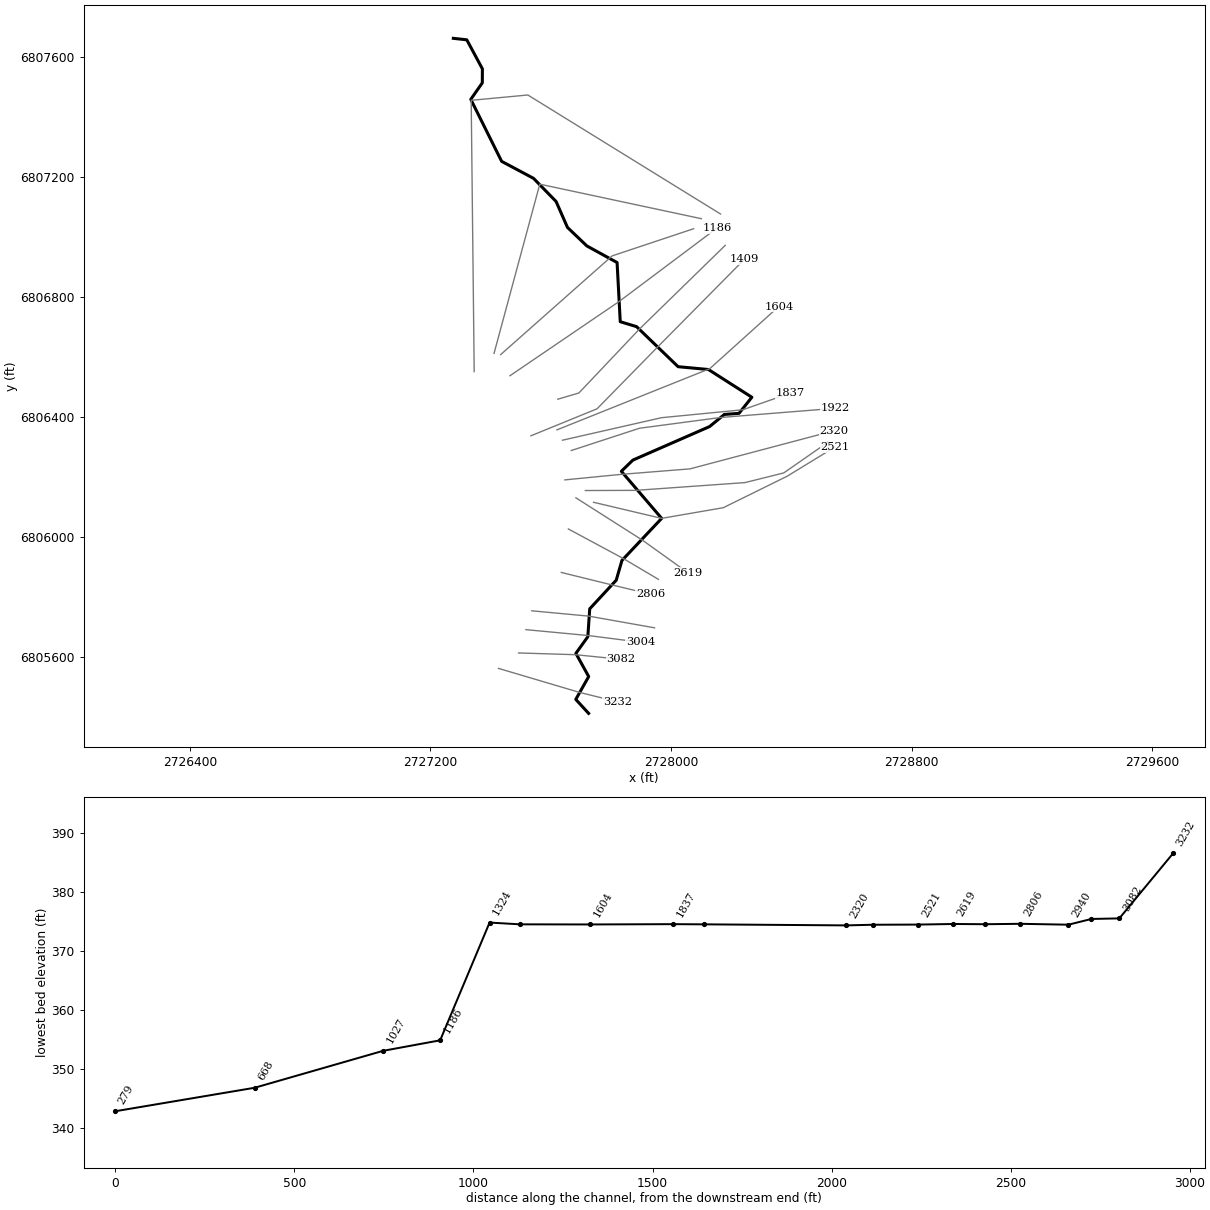
--- Twin Creek154.prj (project) ---

Proj Title=Twin Creek154 Base Level Engineering
Current Plan=p01
Default Exp/Contr=0.3,0.1
English Units
Geom File=g01
Flow File=f01
Plan File=p01
BEGIN DESCRIPTION:
Twin Creek154
END DESCRIPTION:

--- Twin Creek154.p01 (plan) ---

Plan Title=Multiple Run
Short Identifier=Multiple
Geom File=g01
Flow File=f01
Subcritical Flow
K Sum by GR= 0
Std Step Tol= 0.01
Critical Tol= 0.01
Num of Std Step Trials= 20
Max Error Tol= 0.3
Flow Tol Ratio= 0.001
Split Flow NTrial= 30
Split Flow Tol= 0.02
Split Flow Ratio= 0.02
Log Output Level= 0
Friction Slope Method= 1
Unsteady Friction Slope Method= 2
Unsteady Bridges Friction Slope Method= 1
Parabolic Critical Depth
Global Vel Dist=  1 , 1 , 1
Global Log Level= 0
CheckData=True
Encroach Param= -1, 0, 0, 0
BEGIN DESCRIPTION:
Multiple Run
END DESCRIPTION:

--- Twin Creek154.f01 (steady flow) ---

Flow Title=Multiple
Number of Profiles=7
Profile Names=10-year,25-year,50-year,1pct_min,100-year,1pct_plu,500-year
River Rch & RM= Twin Creek154,Reach-1,3232
      87     102     112      61     123     245     146
River Rch & RM= Twin Creek154,Reach-1,2521
      87     102     112      61     123     245     146
River Rch & RM= Twin Creek154,Reach-1,279
     237     299     347     201     401     800     532
Boundary for River Rch & Prof#=Twin Creek154,Reach-1,1
Up Type=0
Dn Type=3
Dn Slope=0.005
Boundary for River Rch & Prof#=Twin Creek154,Reach-1,2
Up Type=0
Dn Type=3
Dn Slope=0.005
Boundary for River Rch & Prof#=Twin Creek154,Reach-1,3
Up Type=0
Dn Type=3
Dn Slope=0.005
Boundary for River Rch & Prof#=Twin Creek154,Reach-1,4
Up Type=0
Dn Type=3
Dn Slope=0.005
Boundary for River Rch & Prof#=Twin Creek154,Reach-1,5
Up Type=0
Dn Type=3
Dn Slope=0.005
Boundary for River Rch & Prof#=Twin Creek154,Reach-1,6
Up Type=0
Dn Type=3
Dn Slope=0.005
Boundary for River Rch & Prof#=Twin Creek154,Reach-1,7
Up Type=0
Dn Type=3
Dn Slope=0.005

--- Twin Creek154.g01 (geometry) ---

Geom Title=Existing Conditions

River Reach=Twin Creek154,Reach-1
Reach XY= 30
      2727726.00      6805411.00      2727683.27      6805457.56
      2727726.25      6805533.80      2727683.59      6805610.99
      2727723.33      6805666.49      2727729.62      6805759.50
      2727817.82      6805854.96      2727836.78      6805920.68
      2727968.93      6806061.00      2727834.84      6806217.95
      2727873.13      6806255.17      2728128.25      6806366.95
      2728177.49      6806407.40      2728226.00      6806411.00
      2728268.89      6806464.67      2728124.42      6806557.17
      2728023.57      6806566.52      2727885.37      6806700.09
      2727831.18      6806716.44      2727820.64      6806913.70
      2727719.96      6806969.16      2727655.58      6807030.77
      2727617.85      6807117.06      2727542.70      6807194.36
      2727436.63      6807251.00      2727334.07      6807457.69
      2727372.40      6807512.64      2727372.67      6807559.29
      2727320.73      6807656.10      2727276.00      6807661.00

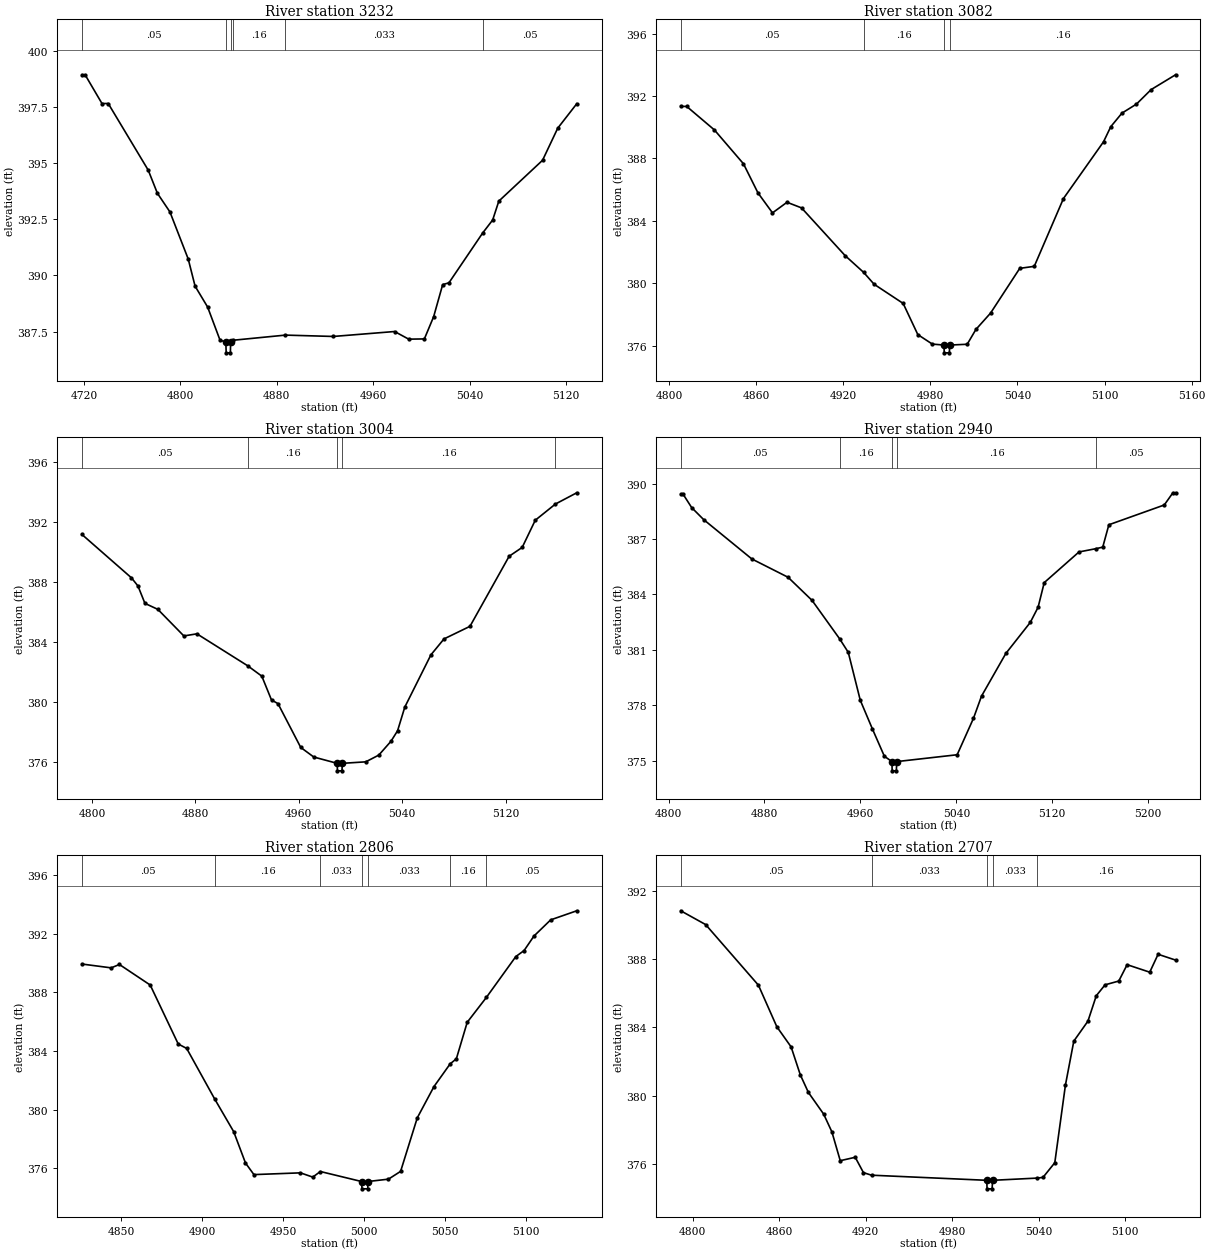
Type RM Length L Ch R = 1,3232,150,150,150
BEGIN DESCRIPTION:
Twin Creek1541377.647
END DESCRIPTION:
XS GIS Cut Line= 3
      2727426.02      6805560.99      2727696.07      6805480.80
      2727821.30      6805449.87
#Sta/Elev= 30
  4718.3  398.94  4720.9  398.94  4734.9  397.66  4740.1  397.66  4773.3  394.69
  4780.9  393.66  4791.3  392.83  4806.5  390.73  4812.2  389.52  4822.6  388.59
  4833.0  387.10  4837.7  387.05  4838.0  386.55  4841.5  386.55  4841.7  387.05
  4843.5  387.11  4887.2  387.34  4926.9  387.28  4977.8  387.50  4989.5  387.16
  5002.5  387.17  5010.2  388.16  5017.7  389.59  5022.9  389.67  5050.9  391.89
  5059.2  392.47  5064.3  393.31  5100.6  395.13  5113.2  396.56  5129.0  397.65
#Mann=6,-1,0
  4718.3    0.05       0  4837.7   0.033       0  4841.7    0.05       0
  4843.5    0.16       0  4887.2   0.033       0  5050.9    0.05       0
Bank Sta=4837.7,4841.7
Exp/Cntr=0.3,0.1

Type RM Length L Ch R = 1,3082,78,78,78
BEGIN DESCRIPTION:
Twin Creek1541227.74
END DESCRIPTION:
XS GIS Cut Line= 3
      2727492.82      6805612.42      2727684.14      6805606.50
      2727832.74      6805591.16
#Sta/Elev= 30
  4808.1  391.34  4812.2  391.34  4831.3  389.83  4851.3  387.66  4861.3  385.79
  4871.3  384.51  4881.3  385.19  4891.3  384.83  4921.3  381.77  4934.1  380.69
  4941.3  379.93  4961.3  378.70  4971.4  376.70  4981.4  376.09  4989.4  376.03
  4989.6  375.53  4993.1  375.53  4993.4  376.03  5005.4  376.08  5011.4  377.03
  5021.5  378.08  5041.6  380.95  5051.6  381.08  5071.7  385.43  5099.3  389.07
  5104.3  390.04  5112.0  390.91  5122.0  391.49  5132.1  392.42  5148.9  393.37
#Mann=4,-1,0
  4808.1    0.05       0  4934.1    0.16       0  4989.4    0.07       0
  4993.4    0.16       0
Bank Sta=4989.4,4993.4
Exp/Cntr=0.3,0.1

Type RM Length L Ch R = 1,3004,64,64,64
BEGIN DESCRIPTION:
Twin Creek1541149.74
END DESCRIPTION:
XS GIS Cut Line= 3
      2727517.52      6805690.06      2727726.40      6805670.27
      2727897.89      6805648.31
#Sta/Elev= 30
  4792.3  391.18  4830.6  388.29  4835.6  387.75  4841.0  386.59  4851.0  386.19
  4871.1  384.42  4881.2  384.56  4920.5  382.43  4931.4  381.74  4938.9  380.15
  4943.9  379.91  4961.5  376.99  4971.6  376.35  4989.7  375.93  4989.9  375.43
  4993.4  375.43  4993.7  375.93  5011.8  376.03  5021.9  376.48  5031.3  377.40
  5036.4  378.10  5042.0  379.68  5062.2  383.16  5072.3  384.22  5092.4  385.06
  5122.7  389.73  5132.8  390.32  5142.9  392.13  5158.5  393.21  5175.0  393.96
#Mann=5,-1,0
  4792.3    0.05       0  4920.5    0.16       0  4989.7    0.07       0
  4993.7    0.16       0  5158.5    0.05       0
Bank Sta=4989.7,4993.7
Exp/Cntr=0.3,0.1

Type RM Length L Ch R = 1,2940,134,134,134
BEGIN DESCRIPTION:
Twin Creek1541084.9
END DESCRIPTION:
XS GIS Cut Line= 3
      2727536.94      6805752.86      2727725.99      6805735.20
      2727945.27      6805696.18
#Sta/Elev= 30
  4810.2  389.41  4812.3  389.41  4819.3  388.70  4829.3  388.05  4869.5  385.92
  4899.7  384.93  4919.7  383.68  4942.7  381.60  4949.9  380.87  4959.9  378.28
  4970.0  376.73  4980.0  375.25  4986.3  374.96  4986.5  374.46  4990.0  374.46
  4990.3  374.96  5040.7  375.33  5054.3  377.30  5061.0  378.50  5081.3  380.81
  5101.7  382.49  5108.2  383.31  5113.3  384.64  5142.3  386.30  5156.7  386.48
  5162.1  386.56  5167.2  387.77  5213.4  388.84  5220.6  389.50  5222.8  389.50
#Mann=5,-1,0
  4810.2    0.05       0  4942.7    0.16       0  4986.3    0.07       0
  4990.3    0.16       0  5156.7    0.05       0
Bank Sta=4986.3,4990.3
Exp/Cntr=0.3,0.1

Type RM Length L Ch R = 1,2806,99,99,99
BEGIN DESCRIPTION:
Twin Creek154950.8
END DESCRIPTION:
XS GIS Cut Line= 3
      2727635.13      6805880.70      2727808.14      6805838.00
      2727931.68      6805808.17
#Sta/Elev= 30
  4825.8  389.93  4843.8  389.67  4848.9  389.90  4867.9  388.50  4885.2  384.48
  4890.4  384.18  4907.7  380.73  4919.4  378.51  4926.7  376.37  4931.9  375.58
  4960.6  375.70  4968.2  375.41  4972.9  375.79  4998.3  375.11  4998.6  374.61
  5002.1  374.61  5002.3  375.11  5014.9  375.27  5022.4  375.80  5032.7  379.45
  5043.0  381.58  5053.0  383.13  5056.8  383.47  5063.5  385.96  5075.3  387.65
  5093.5  390.44  5098.6  390.85  5104.7  391.84  5115.0  392.94  5131.1  393.56
#Mann=7,-1,0
  4825.8    0.05       0  4907.7    0.16       0  4972.9   0.033       0
  4998.3   0.033       0  5002.3   0.033       0  5053.0    0.16       0
  5075.3    0.05       0
Bank Sta=4998.3,5002.3
Exp/Cntr=0.3,0.1

Type RM Length L Ch R = 1,2707,88,88,88
BEGIN DESCRIPTION:
Mapping XS f8153a21
END DESCRIPTION:
XS GIS Cut Line= 3
      2727658.54      6806025.66      2727840.22      6805927.76
      2727958.03      6805857.79
#Sta/Elev= 30
  4791.7  390.84  4809.0  390.03  4845.6  386.48  4858.4  384.04  4868.3  382.86
  4874.7  381.22  4880.3  380.19  4890.9  378.92  4896.6  377.88  4902.4  376.19
  4912.8  376.39  4918.5  375.49  4924.1  375.34  5004.1  375.04  5004.3  374.54
  5007.8  374.54  5008.1  375.04  5039.0  375.17  5043.1  375.21  5051.3  376.07
  5058.7  380.63  5064.5  383.20  5074.3  384.37  5080.1  385.86  5086.2  386.50
  5095.7  386.72  5101.5  387.68  5117.2  387.24  5123.0  388.29  5135.1  387.95
#Mann=5,-1,0
  4791.7    0.05       0  4924.1   0.033       0  5004.1   0.033       0
  5008.1   0.033       0  5039.0    0.16       0
Bank Sta=5004.1,5008.1
Exp/Cntr=0.3,0.1

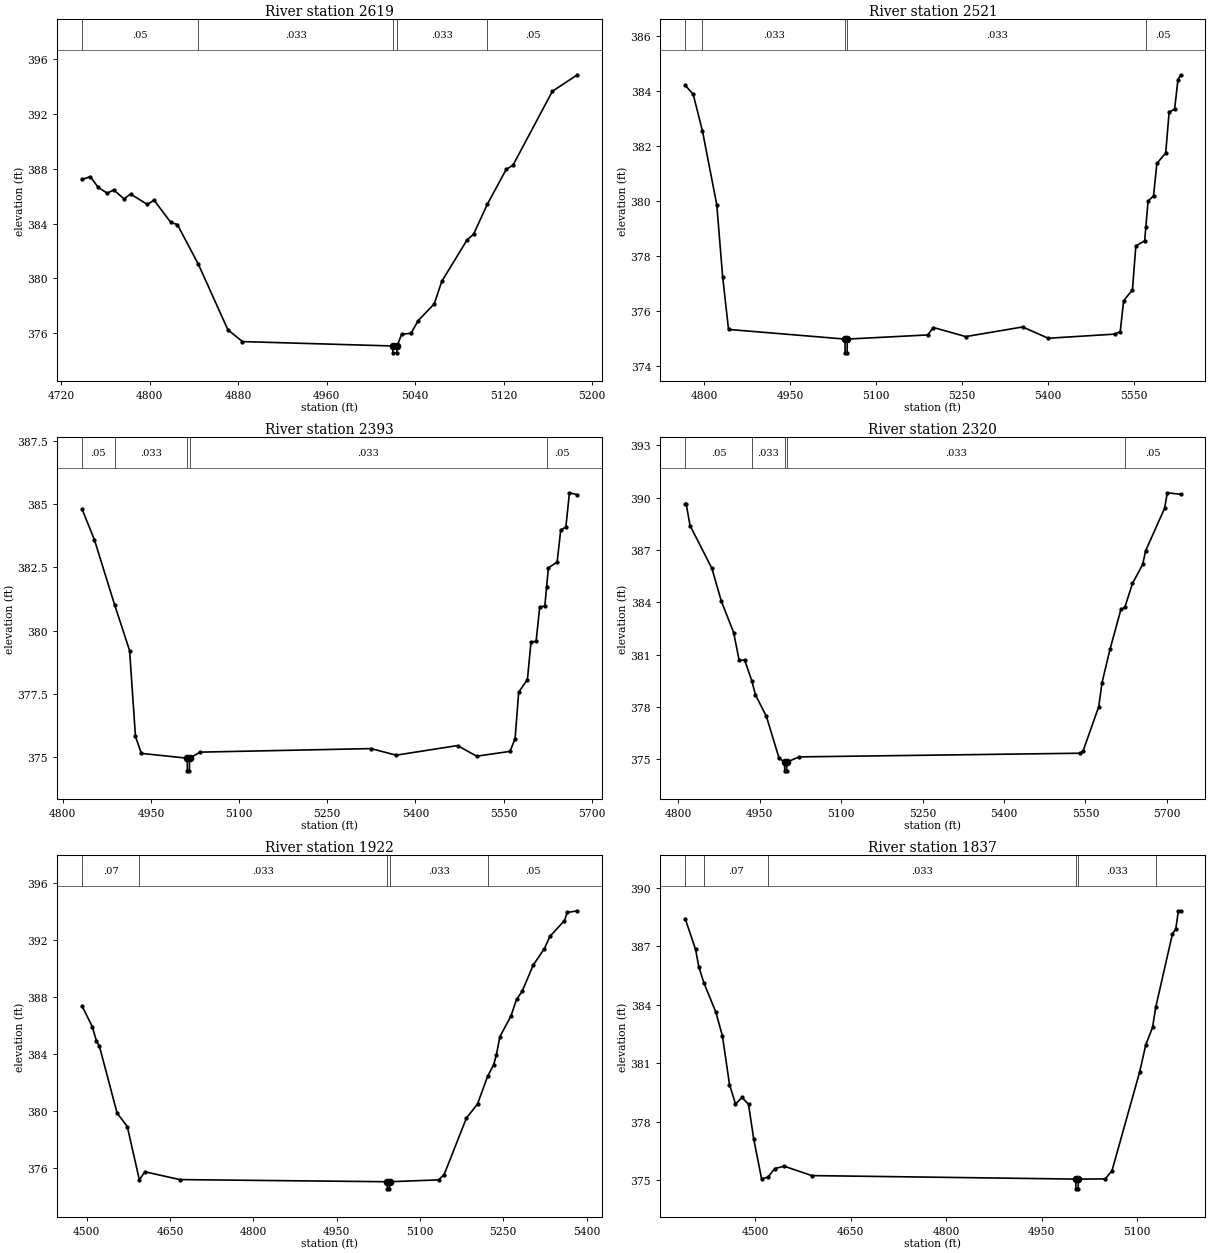
Type RM Length L Ch R = 1,2619,98,98,98
BEGIN DESCRIPTION:
Twin Creek154764.46
END DESCRIPTION:
XS GIS Cut Line= 3
      2727683.71      6806129.47      2727906.12      6805987.50
      2728055.73      6805880.14
#Sta/Elev= 30
  4738.7  387.21  4746.2  387.42  4753.3  386.64  4761.5  386.21  4767.4  386.45
  4776.7  385.80  4782.6  386.15  4797.9  385.39  4803.8  385.71  4819.0  384.08
  4824.9  383.93  4844.0  381.02  4870.6  376.26  4883.8  375.40  5019.6  375.08
  5019.8  374.58  5023.3  374.58  5023.6  375.08  5027.7  375.93  5036.3  376.01
  5042.5  376.91  5057.2  378.15  5064.0  379.79  5086.7  382.79  5092.8  383.23
  5105.2  385.41  5122.3  387.95  5128.4  388.25  5164.0  393.64  5186.7  394.84
#Mann=5,-1,0
  4738.7    0.05       0  4844.0   0.033       0  5019.6   0.033       0
  5023.6   0.033       0  5105.2    0.05       0
Bank Sta=5019.6,5023.6
Exp/Cntr=0.3,0.1

Type RM Length L Ch R = 1,2521,128,128,128
BEGIN DESCRIPTION:
Twin Creek154666.33
END DESCRIPTION:
XS GIS Cut Line= 5
      2727742.38      6806114.59      2727968.64      6806061.01
      2728173.90      6806096.55      2728386.00      6806201.30
      2728544.80      6806298.55
#Sta/Elev= 30
  4767.2  384.20  4781.2  383.87  4797.3  382.54  4822.3  379.86  4832.6  377.23
  4842.8  375.33  5045.8  374.98  5046.0  374.48  5049.5  374.48  5049.8  374.98
  5189.9  375.13  5199.9  375.40  5256.3  375.07  5355.4  375.42  5400.0  375.01
  5515.9  375.16  5525.5  375.25  5531.4  376.37  5546.8  376.77  5552.7  378.36
  5568.1  378.55  5570.1  379.04  5574.0  379.99  5583.5  380.18  5589.4  381.36
  5604.8  381.74  5610.7  383.22  5620.3  383.33  5626.1  384.40  5630.8  384.58
#Mann=5,-1,0
  4767.2    0.05       0  4797.3   0.033       0  5045.8   0.033       0
  5049.8   0.033       0  5570.1    0.05       0
Bank Sta=5045.8,5049.8
Exp/Cntr=0.3,0.1

Type RM Length L Ch R = 1,2393,73,73,73
BEGIN DESCRIPTION:
Twin Creek154538.05
END DESCRIPTION:
XS GIS Cut Line= 5
      2727714.95      6806153.78      2727882.35      6806154.34
      2728246.06      6806180.22      2728375.05      6806212.49
      2728521.29      6806314.50
#Sta/Elev= 30
  4832.6  384.81  4853.6  383.60  4888.2  381.01  4913.6  379.21  4923.6  375.81
  4933.6  375.14  5011.7  374.95  5011.9  374.45  5015.4  374.45  5015.7  374.95
  5033.7  375.19  5324.5  375.33  5367.2  375.07  5471.8  375.45  5504.3  375.03
  5561.0  375.22  5569.7  375.72  5575.8  377.56  5590.7  378.06  5596.8  379.55
  5605.5  379.57  5611.6  380.93  5620.3  380.97  5623.3  381.71  5626.4  382.48
  5641.3  382.71  5647.4  383.98  5656.1  384.09  5662.2  385.45  5675.9  385.37
#Mann=5,-1,0
  4832.6    0.05       0  4888.2   0.033       0  5011.7   0.033       0
  5015.7   0.033       0  5623.3    0.05       0
Bank Sta=5011.7,5015.7
Exp/Cntr=0.3,0.1

Type RM Length L Ch R = 1,2320,398,398,398
BEGIN DESCRIPTION:
Twin Creek154465.507
END DESCRIPTION:
XS GIS Cut Line= 4
      2727647.02      6806189.25      2727831.85      6806207.43
      2728063.31      6806226.01      2728541.82      6806353.03
#Sta/Elev= 30
  4812.5  389.62  4814.5  389.62  4821.5  388.40  4861.7  385.95  4879.1  384.07
  4901.9  382.26  4912.0  380.67  4922.0  380.70  4935.5  379.48  4942.1  378.69
  4962.2  377.46  4985.5  375.07  4995.8  374.84  4996.0  374.34  4999.5  374.34
  4999.8  374.84  5022.4  375.14  5540.3  375.35  5545.5  375.46  5574.6  378.02
  5580.5  379.38  5595.3  381.30  5615.5  383.60  5622.6  383.71  5636.7  385.08
  5655.7  386.18  5660.8  386.94  5695.9  389.39  5701.0  390.28  5725.5  390.19
#Mann=5,-1,0
  4812.5    0.05       0  4935.5   0.033       0  4995.8   0.033       0
  4999.8   0.033       0  5622.6    0.05       0
Bank Sta=4995.8,4999.8
Exp/Cntr=0.3,0.1

Type RM Length L Ch R = 1,1922,85,85,85
BEGIN DESCRIPTION:
Twin Creek154205.836
END DESCRIPTION:
XS GIS Cut Line= 4
      2727668.42      6806287.18      2727895.03      6806361.34
      2728162.93      6806397.02      2728545.40      6806427.80
#Sta/Elev= 30
  4491.3  387.39  4509.8  385.93  4517.4  384.91  4522.6  384.56  4554.5  379.85
  4572.9  378.90  4594.6  375.15  4604.5  375.72  4667.6  375.17  5041.2  375.02
  5041.5  374.52  5045.0  374.52  5045.2  375.02  5133.5  375.15  5143.5  375.52
  5183.7  379.50  5203.7  380.49  5221.8  382.43  5232.7  383.25  5237.7  383.95
  5243.9  385.22  5263.9  386.68  5273.9  387.84  5284.0  388.41  5304.0  390.26
  5324.1  391.42  5334.1  392.28  5360.3  393.39  5365.3  393.96  5383.7  394.08
#Mann=5,-1,0
  4491.3    0.07       0  4594.6   0.033       0  5041.2   0.033       0
  5045.2   0.033       0  5221.8    0.05       0
Bank Sta=5041.2,5045.2
Exp/Cntr=0.3,0.1

Type RM Length L Ch R = 1,1837,233,233,233
BEGIN DESCRIPTION:
Twin Creek1541787.082
END DESCRIPTION:
XS GIS Cut Line= 4
      2727638.97      6806321.49      2727968.48      6806396.56
      2728238.93      6806423.04      2728397.65      6806478.71
#Sta/Elev= 30
  4390.3  388.41  4406.6  386.83  4411.8  385.93  4419.5  385.13  4438.5  383.61
  4448.8  382.39  4459.9  379.90  4469.3  378.90  4479.6  379.24  4489.8  378.88
  4497.8  377.13  4510.3  375.06  4520.4  375.15  4530.8  375.59  4545.9  375.71
  4589.0  375.23  5003.6  375.05  5003.8  374.55  5007.3  374.55  5007.6  375.05
  5049.9  375.06  5060.5  375.49  5103.9  380.55  5113.5  381.94  5124.1  382.83
  5129.2  383.88  5155.3  387.62  5160.6  387.89  5164.7  388.81  5168.2  388.81
#Mann=6,-1,0
  4390.3    0.05       0  4419.5    0.07       0  4520.4   0.033       0
  5003.6   0.033       0  5007.6   0.033       0  5129.2    0.05       0
Bank Sta=5003.6,5007.6
Exp/Cntr=0.3,0.1

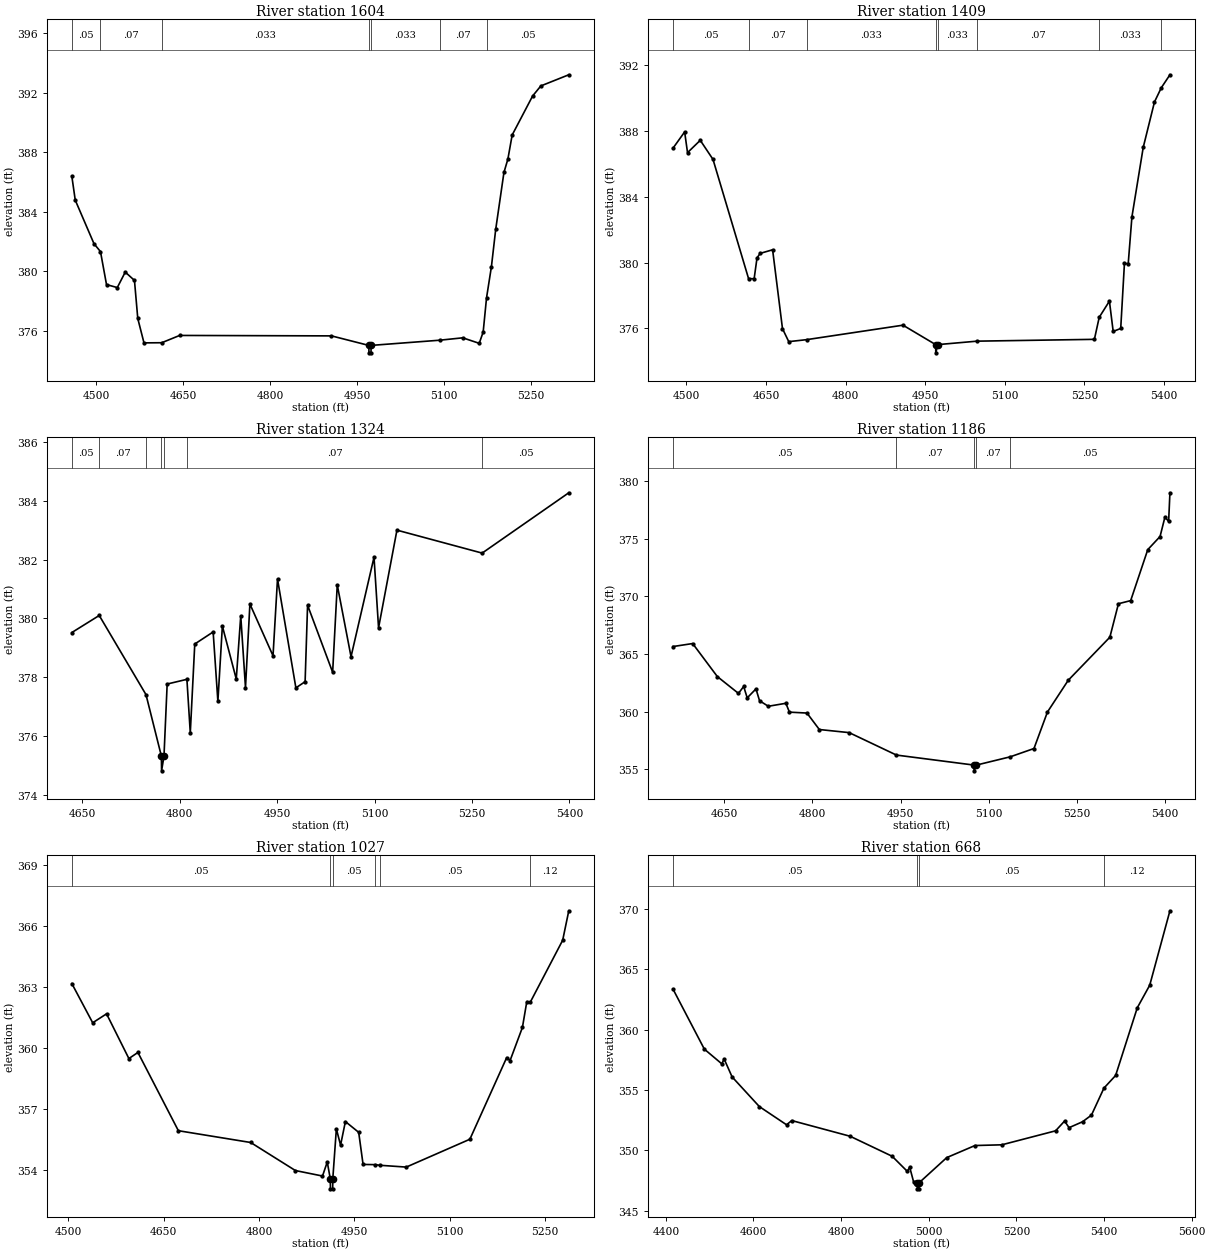
Type RM Length L Ch R = 1,1604,195,195,195
BEGIN DESCRIPTION:
Twin Creek1541603.95
END DESCRIPTION:
XS GIS Cut Line= 3
      2727620.51      6806355.91      2728129.02      6806560.05
      2728358.27      6806767.00
#Sta/Elev= 30
  4458.5  386.38  4464.4  384.77  4496.7  381.84  4507.9  381.31  4518.3  379.09
  4536.9  378.89  4550.6  379.93  4566.5  379.37  4572.2  376.81  4582.9  375.17
  4613.5  375.18  4644.4  375.67  4906.2  375.64  4970.5  375.00  4970.8  374.50
  4974.3  374.50  4974.5  375.00  5092.9  375.35  5132.5  375.51  5160.9  375.14
  5167.7  375.90  5173.5  378.20  5181.9  380.29  5189.3  382.80  5203.5  386.63
  5210.3  387.53  5217.7  389.15  5252.9  391.77  5267.1  392.45  5315.3  393.20
#Mann=7,-1,0
  4458.5    0.05       0  4507.9    0.07       0  4613.5   0.033       0
  4970.5   0.033       0  4974.5   0.033       0  5092.9    0.07       0
  5173.5    0.05       0
Bank Sta=4970.5,4974.5
Exp/Cntr=0.3,0.1

Type RM Length L Ch R = 1,1409,85,85,85
BEGIN DESCRIPTION:
Twin Creek1541408.53
END DESCRIPTION:
XS GIS Cut Line= 4
      2727534.12      6806336.24      2727754.07      6806426.24
      2727955.15      6806631.83      2728243.86      6806924.31
#Sta/Elev= 30
  4474.8  386.95  4496.8  387.94  4502.2  386.68  4526.2  387.43  4550.2  386.27
  4617.2  379.03  4627.7  379.02  4633.1  380.28  4638.9  380.56  4662.5  380.78
  4681.1  375.99  4692.9  375.20  4726.4  375.32  4908.1  376.20  4969.7  375.02
  4969.9  374.52  4973.7  375.02  5047.8  375.23  5268.7  375.34  5277.8  376.68
  5297.0  377.66  5304.1  375.82  5318.3  376.00  5325.3  379.95  5332.4  379.93
  5339.4  382.78  5360.7  387.00  5381.9  389.76  5394.7  390.62  5411.0  391.41
#Mann=8,-1,0
  4474.8    0.05       0  4617.2    0.07       0  4726.4   0.033       0
  4969.7   0.033       0  4973.7   0.033       0  5047.8    0.07       0
  5277.8   0.033       0  5394.7    0.05       0
Bank Sta=4969.7,4973.7
Exp/Cntr=0.3,0.1

Type RM Length L Ch R = 1,1324,138,138,138
BEGIN DESCRIPTION:
Twin Creek1541323.52
END DESCRIPTION:
XS GIS Cut Line= 4
      2727623.57      6806458.18      2727693.65      6806478.94
      2727894.56      6806691.46      2728180.29      6806970.89
#Sta/Elev= 30
  4633.8  379.52  4676.0  380.10  4748.0  377.41  4771.7  375.32  4772.0  374.82
  4775.7  375.32  4780.6  377.77  4811.0  377.93  4816.2  376.11  4823.1  379.13
  4851.4  379.54  4858.7  377.18  4865.6  379.74  4887.0  377.94  4893.9  380.09
  4901.2  377.65  4908.0  380.49  4943.6  378.73  4950.5  381.34  4978.8  377.64
  4993.0  377.85  4996.8  380.45  5035.4  378.17  5042.5  381.14  5063.7  378.70
  5099.1  382.08  5106.1  379.68  5134.4  383.00  5265.6  382.22  5399.0  384.27
#Mann=7,-1,0
  4633.8    0.05       0  4676.0    0.07       0  4748.0    0.05       0
  4771.7    0.07       0  4775.7    0.05       0  4811.0    0.07       0
  5265.6    0.05       0
Bank Sta=4771.7,4775.7
Exp/Cntr=0.3,0.1

Type RM Length L Ch R = 1,1186,159,159,159
BEGIN DESCRIPTION:
Twin Creek1541185.99
END DESCRIPTION:
XS GIS Cut Line= 3
      2727464.40      6806536.38      2727826.24      6806782.95
      2728152.09      6807027.88
#Sta/Elev= 30
  4562.8  365.65  4596.3  365.91  4638.3  363.04  4674.2  361.58  4683.1  362.18
  4689.1  361.19  4704.0  361.97  4710.1  360.94  4725.0  360.46  4754.9  360.72
  4760.9  359.95  4790.8  359.87  4811.8  358.44  4862.6  358.17  4943.0  356.22
  5075.0  355.35  5075.2  354.85  5079.0  355.35  5136.7  356.07  5177.0  356.79
  5199.9  359.96  5235.3  362.72  5306.1  366.46  5320.7  369.37  5341.5  369.64
  5370.6  374.07  5391.5  375.21  5399.8  376.90  5406.1  376.52  5408.3  379.01
#Mann=5,-1,0
  4562.8    0.05       0  4943.0    0.07       0  5075.0    0.07       0
  5079.0    0.07       0  5136.7    0.05       0
Bank Sta=5075,5079
Exp/Cntr=0.3,0.1

Type RM Length L Ch R = 1,1027,359,359,359
BEGIN DESCRIPTION:
Twin Creek1541026.5
END DESCRIPTION:
XS GIS Cut Line= 3
      2727433.45      6806606.89      2727804.43      6806935.95
      2728075.13      6807026.38
#Sta/Elev= 30
  4505.7  363.17  4538.5  361.24  4560.3  361.68  4595.4  359.48  4609.6  359.78
  4673.2  355.93  4786.9  355.35  4857.2  353.97  4899.8  353.70  4907.3  354.39
  4912.0  353.57  4912.3  353.07  4915.8  353.07  4916.0  353.57  4921.6  356.02
  4928.2  355.22  4935.8  356.38  4956.7  355.85  4963.6  354.27  4982.9  354.26
  4989.7  354.23  5031.5  354.14  5131.5  355.51  5189.4  359.53  5194.7  359.38
  5214.1  361.01  5221.0  362.28  5226.6  362.26  5277.4  365.30  5287.0  366.75
#Mann=6,-1,0
  4505.7    0.05       0  4912.0    0.05       0  4916.0    0.05       0
  4982.9    0.07       0  4989.7    0.05       0  5226.6    0.12       0
Bank Sta=4912,4916
Exp/Cntr=0.3,0.1

Type RM Length L Ch R = 1,668,389,389,389
BEGIN DESCRIPTION:
Twin Creek154667.75
END DESCRIPTION:
XS GIS Cut Line= 3
      2727411.31      6806610.73      2727563.55      6807174.93
      2728101.08      6807059.81
#Sta/Elev= 30
  4416.3  363.36  4487.9  358.38  4527.8  357.16  4533.0  357.57  4551.2  356.08
  4613.4  353.62  4675.5  352.11  4687.4  352.46  4820.5  351.16  4916.5  349.50
  4951.3  348.24  4956.4  348.61  4965.5  347.37  4973.9  347.30  4974.1  346.80
  4977.6  346.80  4977.9  347.30  5041.1  349.39  5105.5  350.39  5166.8  350.45
  5289.5  351.61  5310.0  352.42  5320.2  351.87  5350.9  352.36  5371.3  352.91
  5399.8  355.15  5426.5  356.20  5475.9  361.81  5504.3  363.68  5550.4  369.85
#Mann=4,-1,0
  4416.3    0.05       0  4973.9    0.05       0  4977.9    0.05       0
  5399.8    0.12       0
Bank Sta=4973.9,4977.9
Exp/Cntr=0.3,0.1

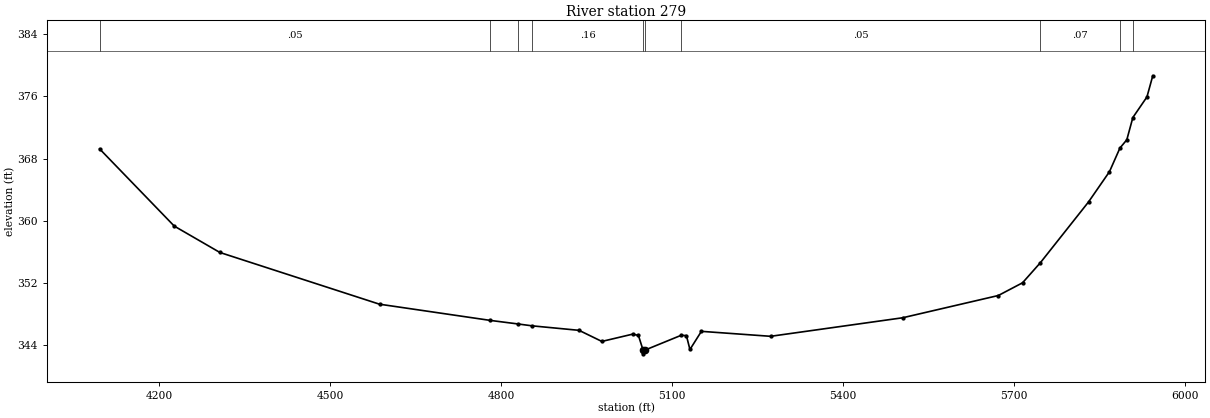
Type RM Length L Ch R = 1,279,0,0,0
BEGIN DESCRIPTION:
Twin Creek154279.129
END DESCRIPTION:
XS GIS Cut Line= 4
      2727345.39      6806550.14      2727335.43      6807454.39
      2727523.82      6807472.16      2728164.67      6807075.50
#Sta/Elev= 30
  4095.7  369.24  4226.6  359.29  4306.6  355.89  4586.6  349.22  4781.0  347.13
  4828.7  346.68  4854.3  346.43  4936.6  345.85  4976.6  344.42  5030.7  345.36
  5040.7  345.20  5048.8  343.32  5049.0  342.82  5052.8  343.32  5115.7  345.21
  5124.9  345.17  5131.1  343.38  5151.2  345.72  5272.6  345.08  5504.2  347.47
  5672.0  350.34  5714.5  351.98  5745.9  354.58  5830.3  362.41  5867.0  366.31
  5885.3  369.35  5897.4  370.42  5908.0  373.29  5932.7  375.94  5942.9  378.67
#Mann=10,-1,0
  4095.7    0.05       0  4781.0    0.16       0  4828.7    0.05       0
  4854.3    0.16       0  5048.8    0.07       0  5052.8    0.16       0
  5115.7    0.05       0  5745.9    0.07       0  5885.3    0.12       0
  5908.0    0.05       0
Bank Sta=5048.8,5052.8
Exp/Cntr=0.3,0.1

Chan Stop Cuts=-1