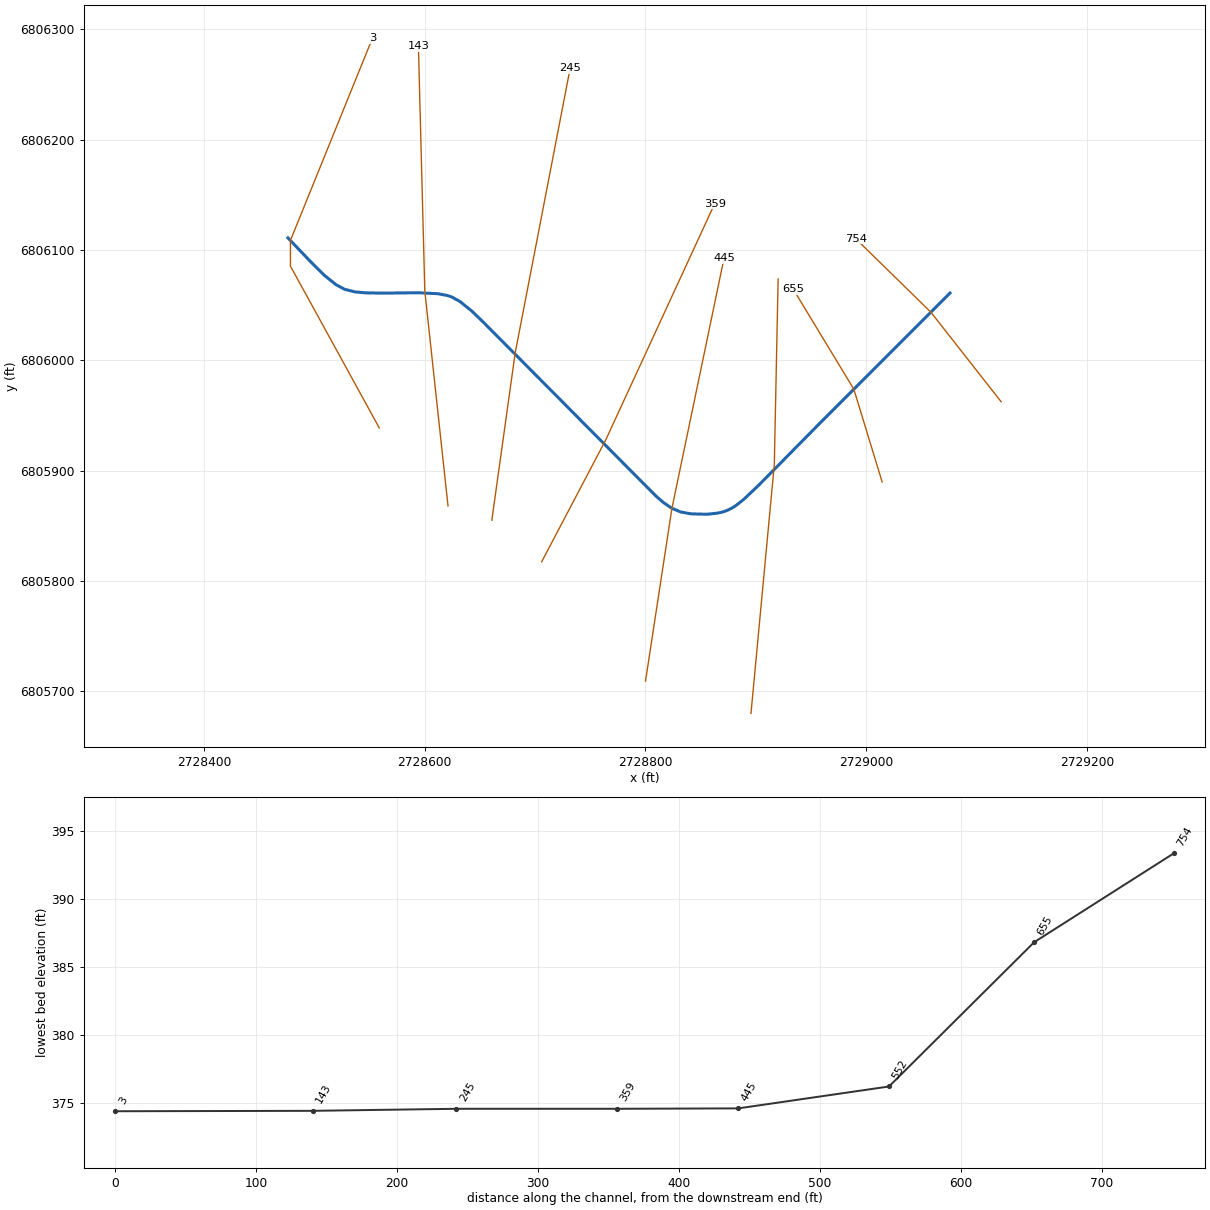
--- Twin Creek157.prj (project) ---

Proj Title=Twin Creek157 Base Level Engineering
Current Plan=p01
Default Exp/Contr=0.3,0.1
English Units
Geom File=g01
Flow File=f01
Plan File=p01
BEGIN DESCRIPTION:
Twin Creek157
END DESCRIPTION:

--- Twin Creek157.p01 (plan) ---

Plan Title=Multiple Run
Short Identifier=Multiple
Geom File=g01
Flow File=f01
Subcritical Flow
K Sum by GR= 0
Std Step Tol= 0.01
Critical Tol= 0.01
Num of Std Step Trials= 20
Max Error Tol= 0.3
Flow Tol Ratio= 0.001
Split Flow NTrial= 30
Split Flow Tol= 0.02
Split Flow Ratio= 0.02
Log Output Level= 0
Friction Slope Method= 1
Unsteady Friction Slope Method= 2
Unsteady Bridges Friction Slope Method= 1
Parabolic Critical Depth
Global Vel Dist=  1 , 1 , 1
Global Log Level= 0
CheckData=True
Encroach Param= -1, 0, 0, 0
BEGIN DESCRIPTION:
Multiple Run
END DESCRIPTION:

--- Twin Creek157.f01 (steady flow) ---

Flow Title=Multiple
Number of Profiles=7
Profile Names=10-year,25-year,50-year,1pct_min,100-year,1pct_plu,500-year
River Rch & RM= Twin Creek157,Reach-1,754
      51      57      61      33      65     130      74
River Rch & RM= Twin Creek157,Reach-1,3
      92     108     119      66     131     261     158
Boundary for River Rch & Prof#=Twin Creek157,Reach-1,1
Up Type=0
Dn Type=3
Dn Slope=0.005
Boundary for River Rch & Prof#=Twin Creek157,Reach-1,2
Up Type=0
Dn Type=3
Dn Slope=0.005
Boundary for River Rch & Prof#=Twin Creek157,Reach-1,3
Up Type=0
Dn Type=3
Dn Slope=0.005
Boundary for River Rch & Prof#=Twin Creek157,Reach-1,4
Up Type=0
Dn Type=3
Dn Slope=0.005
Boundary for River Rch & Prof#=Twin Creek157,Reach-1,5
Up Type=0
Dn Type=3
Dn Slope=0.005
Boundary for River Rch & Prof#=Twin Creek157,Reach-1,6
Up Type=0
Dn Type=3
Dn Slope=0.005
Boundary for River Rch & Prof#=Twin Creek157,Reach-1,7
Up Type=0
Dn Type=3
Dn Slope=0.005

--- Twin Creek157.g01 (geometry) ---

Geom Title=Existing Conditions

River Reach=Twin Creek157,Reach-1
Reach XY= 30
      2729076.00      6806061.00      2728956.02      6805940.95
      2728902.82      6805887.03      2728889.21      6805874.11
      2728882.05      6805868.46      2728878.29      6805866.06
      2728874.35      6805864.10      2728869.95      6805862.58
      2728865.36      6805861.55      2728855.84      6805860.52
      2728841.36      6805860.89      2728832.05      6805862.58
      2728823.71      6805866.06      2728816.32      6805871.17
      2728809.33      6805877.21      2728652.87      6806034.82
      2728642.76      6806044.55      2728632.18      6806053.16
      2728624.52      6806057.42      2728620.53      6806058.77
      2728612.11      6806060.38      2728594.30      6806061.28
      2728560.97      6806060.93      2728546.08      6806061.20
      2728536.46      6806062.11      2728527.41      6806064.39
      2728519.68      6806068.50      2728508.95      6806077.13
      2728496.33      6806089.63      2728476.00      6806111.00

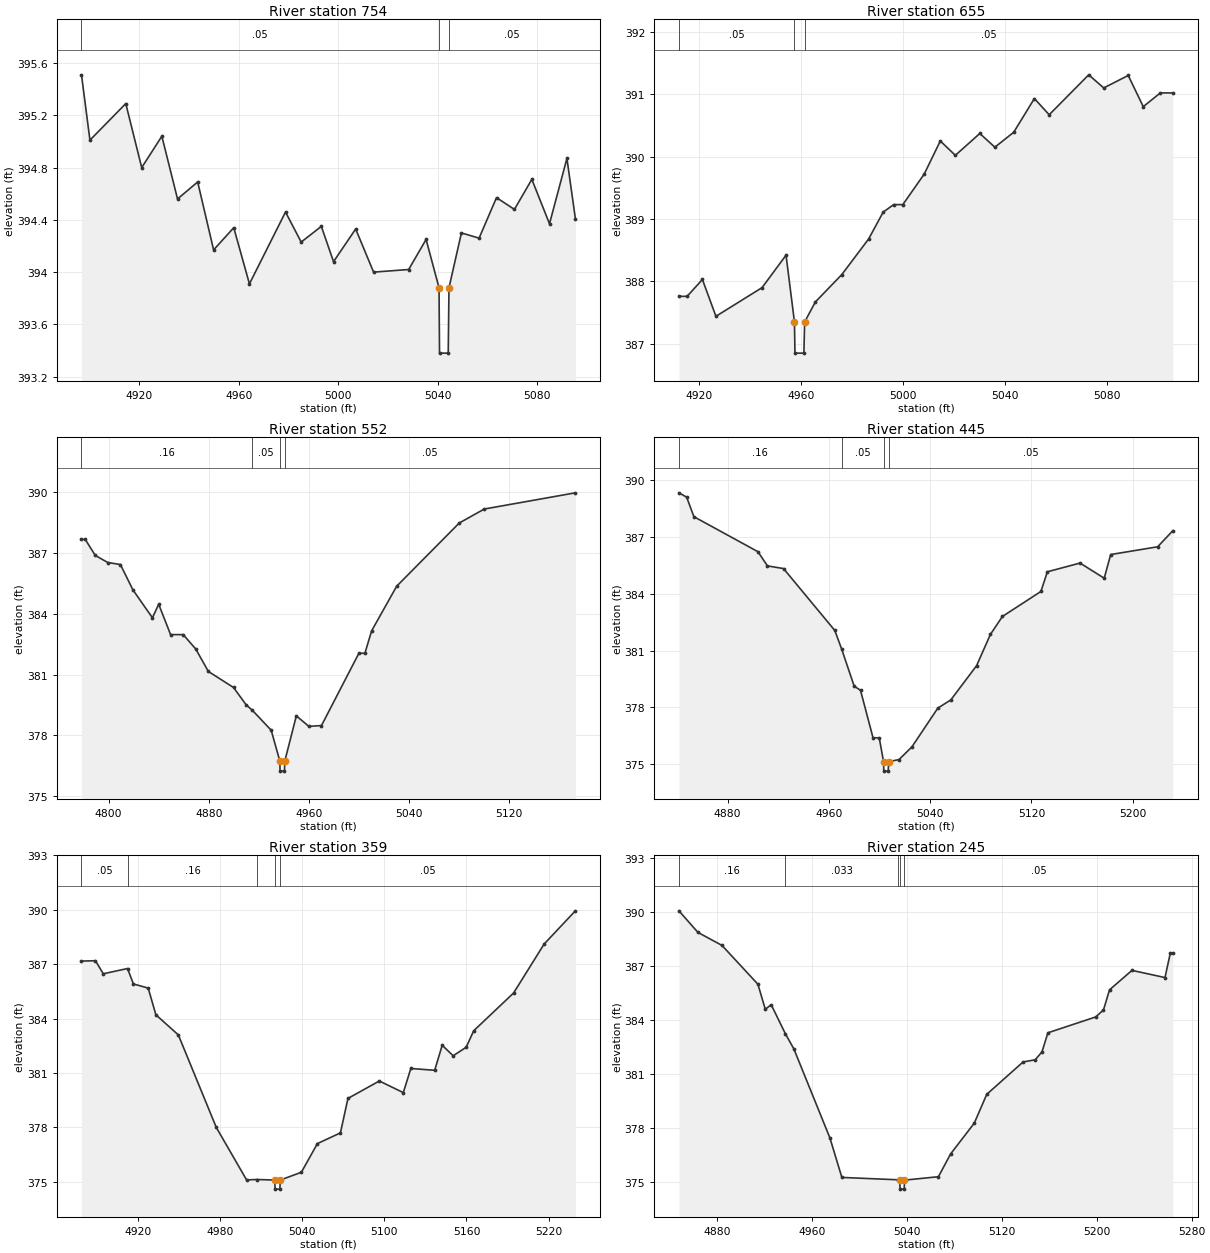
Type RM Length L Ch R = 1,754,99,99,99
BEGIN DESCRIPTION:
Twin Creek157754.151
END DESCRIPTION:
XS GIS Cut Line= 3
      2729122.38      6805962.48      2729058.68      6806043.67
      2728990.56      6806110.32
#Sta/Elev= 30
  4896.8  395.51  4900.2  395.01  4914.6  395.29  4921.0  394.80  4929.1  395.04
  4935.4  394.56  4943.5  394.69  4949.9  394.17  4958.0  394.34  4964.3  393.91
  4978.8  394.46  4985.1  394.23  4993.2  394.35  4998.1  394.08  5007.0  394.33
  5014.2  394.00  5028.3  394.02  5035.3  394.25  5040.5  393.88  5040.7  393.38
  5044.2  393.38  5044.5  393.88  5049.5  394.30  5056.6  394.26  5063.6  394.57
  5070.8  394.48  5077.8  394.71  5084.9  394.37  5091.9  394.87  5095.3  394.41
#Mann=3,-1,0
  4896.8    0.05       0  5040.5    0.05       0  5044.5    0.05       0
Bank Sta=5040.5,5044.5
Exp/Cntr=0.3,0.1

Type RM Length L Ch R = 1,655,103,103,103
BEGIN DESCRIPTION:
Twin Creek157664.16
END DESCRIPTION:
XS GIS Cut Line= 3
      2729014.51      6805889.85      2728988.88      6805973.83
      2728934.03      6806064.42
#Sta/Elev= 30
  4912.2  387.76  4915.4  387.76  4921.4  388.03  4926.7  387.44  4944.8  387.90
  4954.2  388.42  4957.5  387.35  4957.7  386.85  4961.2  386.85  4961.5  387.35
  4965.7  387.67  4976.1  388.11  4986.6  388.68  4992.3  389.11  4996.4  389.23
  5000.0  389.23  5008.4  389.72  5014.7  390.25  5020.6  390.02  5030.2  390.37
  5036.1  390.15  5043.5  390.39  5051.6  390.93  5057.4  390.67  5072.9  391.31
  5078.8  391.10  5088.4  391.30  5094.3  390.80  5101.0  391.02  5105.9  391.02
#Mann=3,-1,0
  4912.2    0.05       0  4957.5    0.05       0  4961.5    0.05       0
Bank Sta=4957.5,4961.5
Exp/Cntr=0.3,0.1

Type RM Length L Ch R = 1,552,107,107,107
BEGIN DESCRIPTION:
Twin Creek157553.84
END DESCRIPTION:
XS GIS Cut Line= 3
      2728895.66      6805680.07      2728916.80      6805905.56
      2728920.26      6806073.75
#Sta/Elev= 30
  4778.3  387.68  4781.3  387.68  4789.3  386.89  4799.3  386.54  4809.4  386.44
  4819.4  385.19  4835.0  383.81  4840.0  384.48  4849.5  382.98  4859.6  382.98
  4869.6  382.27  4879.7  381.16  4899.8  380.37  4909.8  379.52  4914.9  379.24
  4929.9  378.26  4936.8  376.74  4937.0  376.24  4940.5  376.24  4940.8  376.74
  4950.0  378.97  4960.0  378.45  4970.1  378.49  5000.0  382.06  5004.8  382.06
  5010.2  383.17  5030.2  385.37  5080.2  388.49  5100.2  389.18  5173.0  389.98
#Mann=4,-1,0
  4778.3    0.16       0  4914.9    0.05       0  4936.8    0.05       0
  4940.8    0.05       0
Bank Sta=4936.8,4940.8
Exp/Cntr=0.3,0.1

Type RM Length L Ch R = 1,445,86,86,86
BEGIN DESCRIPTION:
Twin Creek157444.8
END DESCRIPTION:
XS GIS Cut Line= 3
      2728800.07      6805709.33      2728823.98      6805865.72
      2728871.28      6806092.74
#Sta/Elev= 30
  4841.6  389.33  4847.7  389.10  4853.4  388.07  4904.0  386.22  4911.5  385.47
  4924.2  385.33  4964.7  382.06  4970.1  381.08  4980.0  379.12  4985.0  378.90
  4994.9  376.39  4999.8  376.39  5003.2  375.13  5003.4  374.63  5006.9  374.63
  5007.2  375.13  5015.4  375.24  5025.6  375.91  5046.1  377.96  5056.3  378.39
  5076.7  380.20  5087.6  381.85  5097.1  382.80  5127.5  384.12  5132.6  385.16
  5158.4  385.62  5177.5  384.82  5182.6  386.07  5219.7  386.48  5231.7  387.33
#Mann=4,-1,0
  4841.6    0.16       0  4970.1    0.05       0  5003.2    0.05       0
  5007.2    0.05       0
Bank Sta=5003.2,5007.2
Exp/Cntr=0.3,0.1

Type RM Length L Ch R = 1,359,114,114,114
BEGIN DESCRIPTION:
Twin Creek157359.47
END DESCRIPTION:
XS GIS Cut Line= 3
      2728705.96      6805817.45      2728764.06      6805927.96
      2728862.72      6806141.97
#Sta/Elev= 30
  4879.0  387.17  4889.2  387.19  4894.9  386.47  4912.6  386.76  4916.9  385.91
  4927.7  385.68  4933.3  384.21  4949.7  383.10  4977.4  378.00  4999.5  375.11
  5007.4  375.13  5020.1  375.10  5020.3  374.60  5023.8  374.60  5024.1  375.10
  5039.5  375.53  5051.2  377.11  5068.0  377.70  5073.5  379.60  5096.4  380.56
  5113.9  379.92  5119.4  381.25  5136.8  381.15  5142.3  382.53  5150.3  381.95
  5159.8  382.42  5165.3  383.33  5194.4  385.41  5216.7  388.11  5239.5  389.94
#Mann=5,-1,0
  4879.0    0.05       0  4912.6    0.16       0  5007.4    0.05       0
  5020.1    0.07       0  5024.1    0.05       0
Bank Sta=5020.1,5024.1
Exp/Cntr=0.3,0.1

Type RM Length L Ch R = 1,245,102,102,102
BEGIN DESCRIPTION:
Twin Creek157245.32
END DESCRIPTION:
XS GIS Cut Line= 3
      2728660.79      6805855.16      2728681.95      6806006.65
      2728731.79      6806264.82
#Sta/Elev= 30
  4848.2  390.07  4864.2  388.87  4884.4  388.15  4914.7  385.99  4920.9  384.60
  4925.9  384.85  4937.8  383.24  4945.0  382.39  4975.3  377.45  4985.4  375.25
  5032.3  375.12  5034.1  375.10  5034.4  374.60  5037.9  374.60  5038.1  375.10
  5066.7  375.29  5076.9  376.55  5096.9  378.27  5107.4  379.87  5138.0  381.67
  5148.2  381.79  5153.9  382.23  5158.9  383.29  5199.1  384.17  5205.7  384.56
  5210.8  385.68  5229.7  386.76  5257.5  386.36  5262.0  387.73  5264.1  387.73
#Mann=5,-1,0
  4848.2    0.16       0  4937.8   0.033       0  5032.3    0.05       0
  5034.1   0.033       0  5038.1    0.05       0
Bank Sta=5034.1,5038.1
Exp/Cntr=0.3,0.1

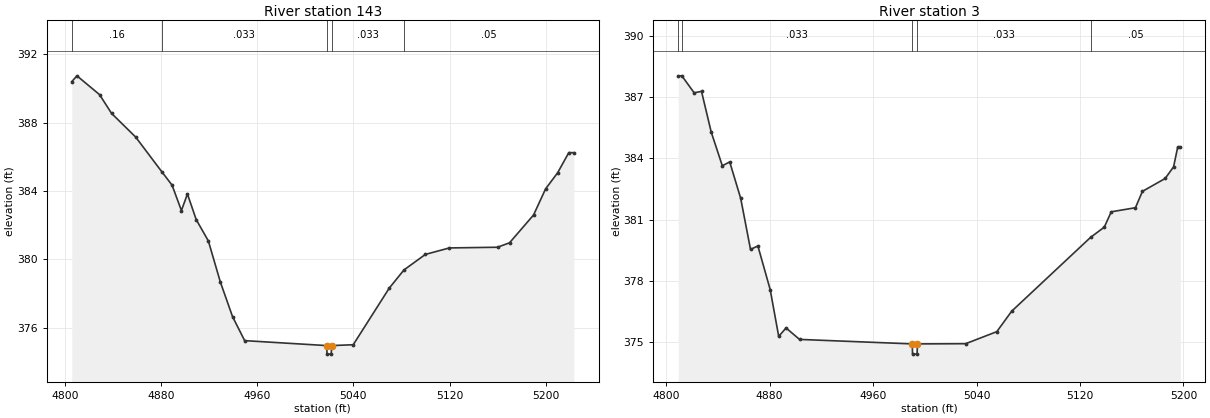
Type RM Length L Ch R = 1,143,140,140,140
BEGIN DESCRIPTION:
Twin Creek157142.98
END DESCRIPTION:
XS GIS Cut Line= 3
      2728621.08      6805868.07      2728600.04      6806062.92
      2728594.26      6806284.46
#Sta/Elev= 30
  4805.8  390.41  4810.1  390.75  4828.9  389.65  4838.9  388.55  4859.0  387.16
  4880.7  385.13  4889.2  384.35  4897.0  382.86  4902.0  383.83  4909.3  382.33
  4919.4  381.08  4929.4  378.67  4939.5  376.65  4949.6  375.24  5017.9  374.95
  5018.1  374.45  5021.6  374.45  5021.9  374.95  5039.9  375.00  5069.9  378.32
  5082.1  379.38  5099.9  380.29  5119.9  380.67  5159.9  380.71  5169.9  380.97
  5189.9  382.60  5199.9  384.13  5209.9  385.07  5219.2  386.25  5223.4  386.25
#Mann=5,-1,0
  4805.8    0.16       0  4880.7   0.033       0  5017.9   0.033       0
  5021.9   0.033       0  5082.1    0.05       0
Bank Sta=5017.9,5021.9
Exp/Cntr=0.3,0.1

Type RM Length L Ch R = 1,3,0,0,0
BEGIN DESCRIPTION:
Twin Creek15717.18
END DESCRIPTION:
XS GIS Cut Line= 4
      2728558.83      6805938.69      2728478.27      6806085.42
      2728478.28      6806108.73      2728552.54      6806291.85
#Sta/Elev= 30
  4809.3  388.03  4812.1  388.03  4821.6  387.20  4827.3  387.27  4834.8  385.28
  4843.4  383.63  4849.1  383.82  4857.6  382.04  4865.2  379.54  4870.9  379.71
  4880.4  377.58  4887.0  375.29  4892.7  375.70  4903.1  375.14  4990.3  374.92
  4990.5  374.42  4994.0  374.42  4994.3  374.92  5031.6  374.93  5055.7  375.52
  5067.2  376.52  5128.2  380.13  5138.8  380.63  5144.2  381.38  5162.9  381.58
  5168.3  382.38  5185.9  383.01  5192.4  383.58  5195.6  384.55  5197.6  384.55
#Mann=5,-1,0
  4809.3    0.05       0  4812.1   0.033       0  4990.3   0.033       0
  4994.3   0.033       0  5128.2    0.05       0
Bank Sta=4990.3,4994.3
Exp/Cntr=0.3,0.1

Chan Stop Cuts=-1