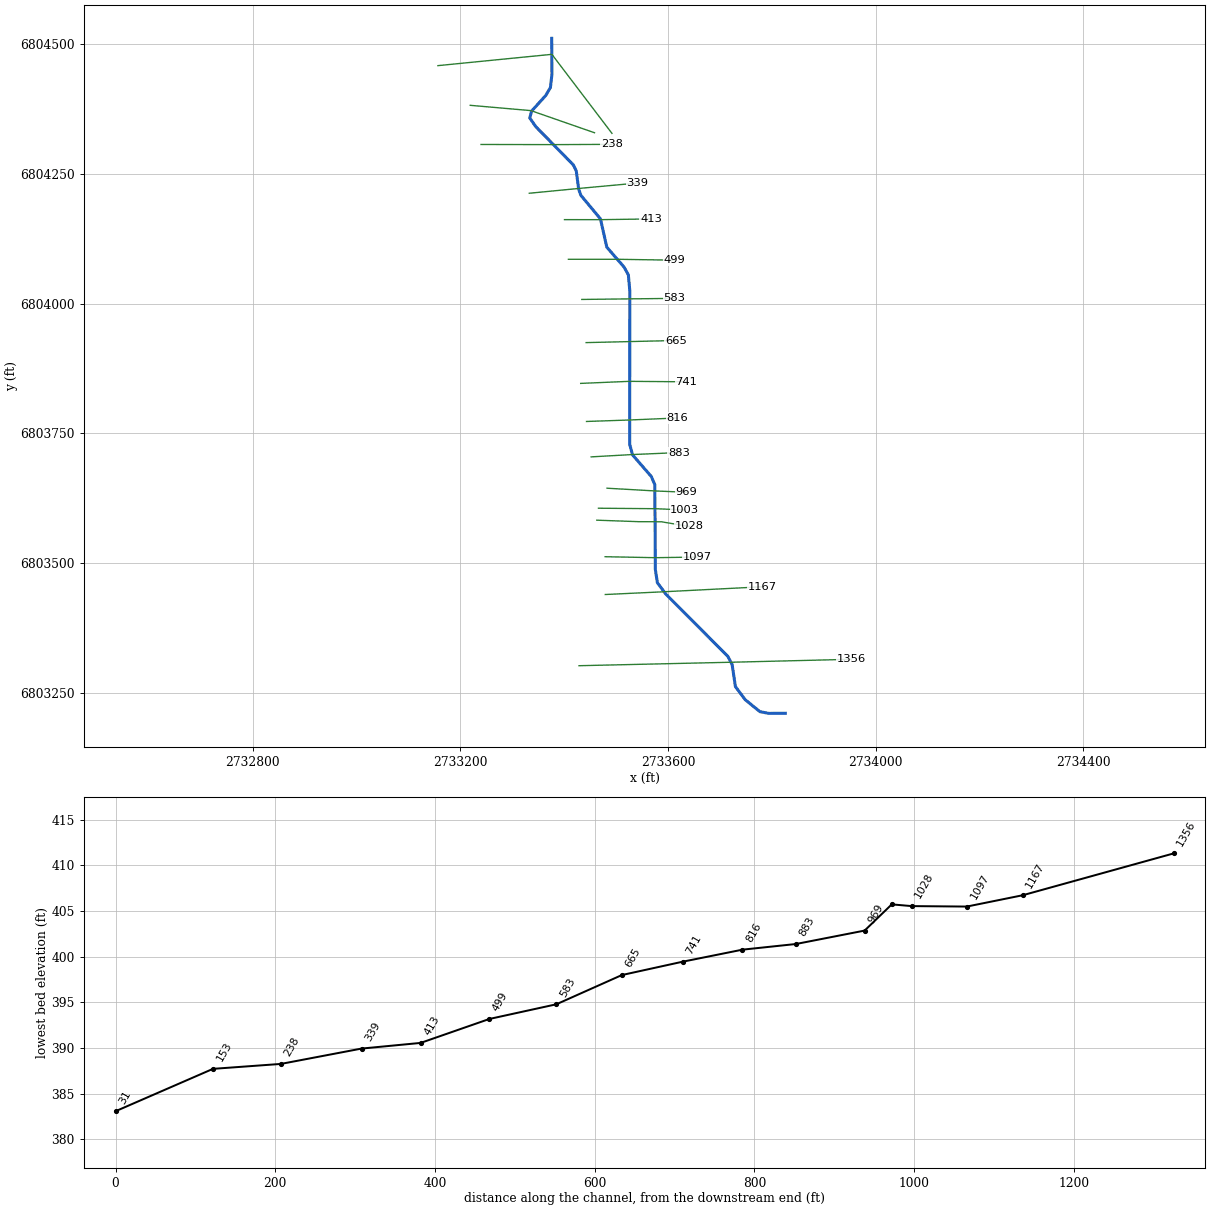
--- Twin Creek159.prj (project) ---

Proj Title=Twin Creek159 Base Level Engineering
Current Plan=p01
Default Exp/Contr=0.3,0.1
English Units
Geom File=g01
Flow File=f01
Plan File=p01
BEGIN DESCRIPTION:
Twin Creek159
END DESCRIPTION:

--- Twin Creek159.p01 (plan) ---

Plan Title=Multiple Run
Short Identifier=Multiple
Geom File=g01
Flow File=f01
Subcritical Flow
K Sum by GR= 0
Std Step Tol= 0.01
Critical Tol= 0.01
Num of Std Step Trials= 20
Max Error Tol= 0.3
Flow Tol Ratio= 0.001
Split Flow NTrial= 30
Split Flow Tol= 0.02
Split Flow Ratio= 0.02
Log Output Level= 0
Friction Slope Method= 1
Unsteady Friction Slope Method= 2
Unsteady Bridges Friction Slope Method= 1
Parabolic Critical Depth
Global Vel Dist=  1 , 1 , 1
Global Log Level= 0
CheckData=True
Encroach Param= -1, 0, 0, 0
BEGIN DESCRIPTION:
Multiple Run
END DESCRIPTION:

--- Twin Creek159.f01 (steady flow) ---

Flow Title=Multiple
Number of Profiles=7
Profile Names=10-year,25-year,50-year,1pct_min,100-year,1pct_plu,500-year
River Rch & RM= Twin Creek159,Reach-1,1356
      86     101     111      62     123     245     148
Boundary for River Rch & Prof#=Twin Creek159,Reach-1,1
Up Type=0
Dn Type=3
Dn Slope=0.005
Boundary for River Rch & Prof#=Twin Creek159,Reach-1,2
Up Type=0
Dn Type=3
Dn Slope=0.005
Boundary for River Rch & Prof#=Twin Creek159,Reach-1,3
Up Type=0
Dn Type=3
Dn Slope=0.005
Boundary for River Rch & Prof#=Twin Creek159,Reach-1,4
Up Type=0
Dn Type=3
Dn Slope=0.005
Boundary for River Rch & Prof#=Twin Creek159,Reach-1,5
Up Type=0
Dn Type=3
Dn Slope=0.005
Boundary for River Rch & Prof#=Twin Creek159,Reach-1,6
Up Type=0
Dn Type=3
Dn Slope=0.005
Boundary for River Rch & Prof#=Twin Creek159,Reach-1,7
Up Type=0
Dn Type=3
Dn Slope=0.005

--- Twin Creek159.g01 (geometry) ---

Geom Title=Existing Conditions

River Reach=Twin Creek159,Reach-1
Reach XY= 30
      2733826.00      6803211.00      2733793.95      6803210.85
      2733777.03      6803214.14      2733748.73      6803237.15
      2733729.86      6803262.46      2733723.49      6803304.94
      2733715.23      6803320.67      2733595.61      6803440.84
      2733579.54      6803462.46      2733575.63      6803488.12
      2733574.62      6803651.34      2733567.86      6803667.06
      2733531.75      6803708.67      2733526.21      6803729.27
      2733526.45      6804024.82      2733523.65      6804055.48
      2733515.20      6804070.67      2733482.12      6804108.82
      2733469.92      6804163.20      2733432.10      6804208.81
      2733427.85      6804220.86      2733423.37      6804255.37
      2733417.82      6804267.06      2733345.33      6804340.98
      2733333.77      6804357.59      2733337.25      6804370.85
      2733364.72      6804401.18      2733373.53      6804416.36
      2733376.57      6804442.50      2733376.00      6804511.00

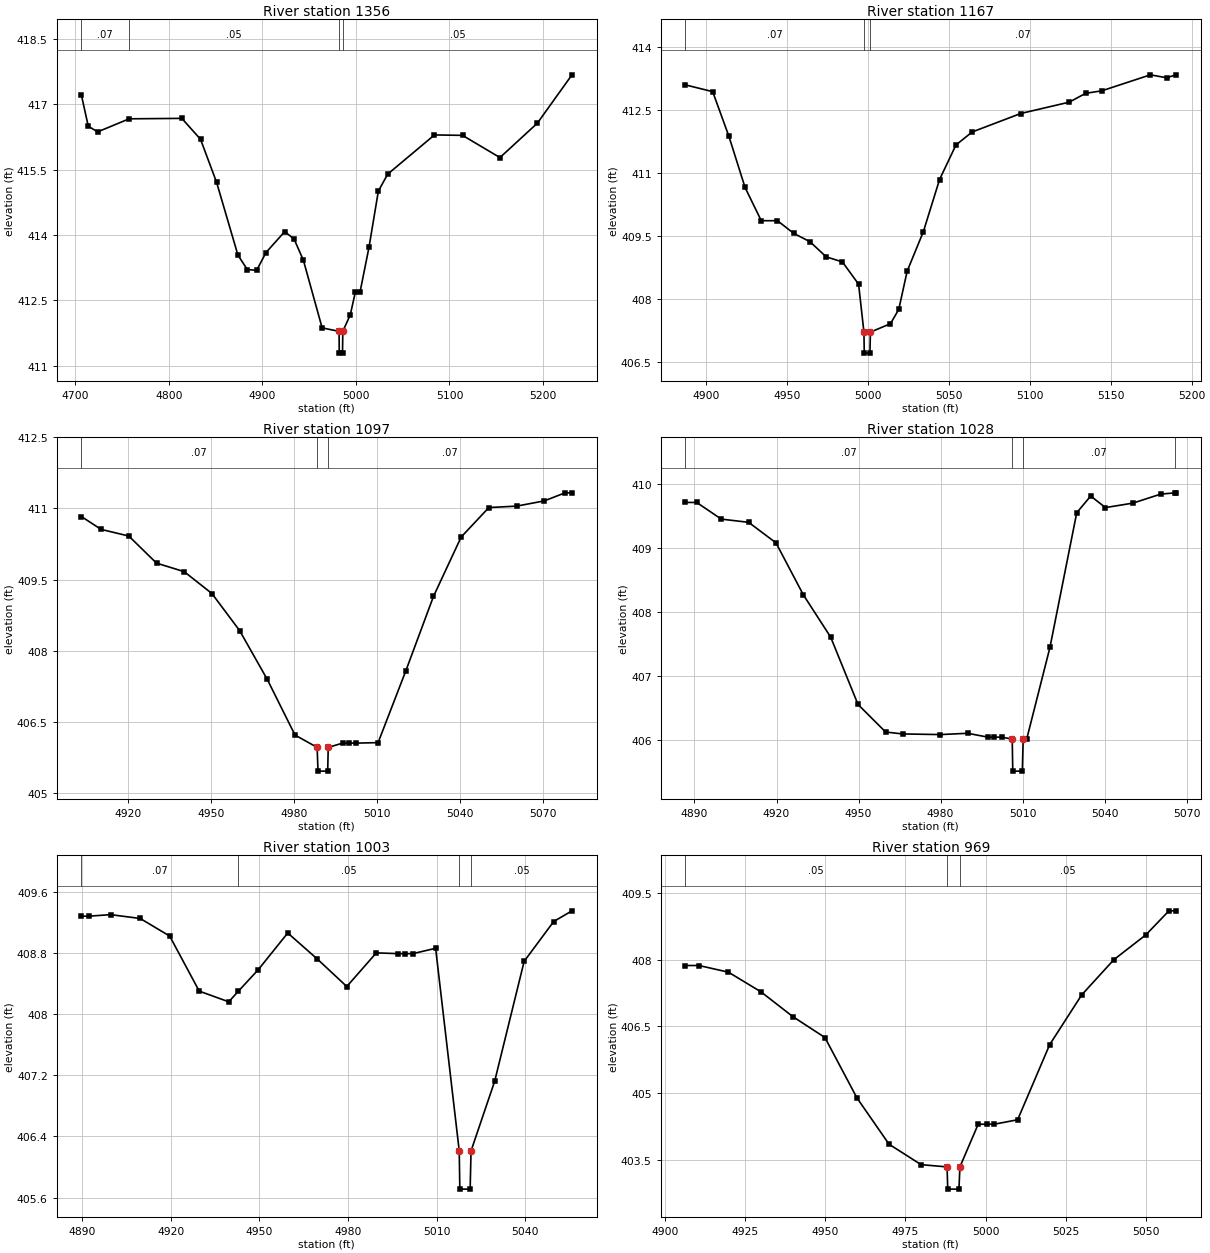
Type RM Length L Ch R = 1,1356,189,189,189
BEGIN DESCRIPTION:
Twin Creek1591355.806
END DESCRIPTION:
XS GIS Cut Line= 3
      2733428.72      6803302.66      2733722.04      6803309.34
      2733952.97      6803315.02
#Sta/Elev= 30
  4706.6  417.21  4713.9  416.50  4723.9  416.37  4757.6  416.67  4813.9  416.68
  4833.9  416.20  4851.1  415.21  4873.9  413.54  4883.9  413.21  4893.9  413.19
  4903.9  413.60  4923.9  414.08  4933.9  413.91  4943.9  413.42  4963.9  411.87
  4982.0  411.79  4982.2  411.29  4985.7  411.29  4986.0  411.79  4994.0  412.17
  4999.5  412.70  5004.5  412.70  5014.0  413.72  5024.0  415.01  5034.0  415.40
  5084.0  416.30  5114.0  416.29  5154.0  415.78  5194.0  416.57  5231.0  417.68
#Mann=4,-1,0
  4706.6    0.07       0  4757.6    0.05       0  4982.0    0.05       0
  4986.0    0.05       0
Bank Sta=4982,4986
Exp/Cntr=0.3,0.1

Type RM Length L Ch R = 1,1167,70,70,70
BEGIN DESCRIPTION:
Twin Creek1591167.21
END DESCRIPTION:
XS GIS Cut Line= 3
      2733479.23      6803439.79      2733591.59      6803445.04
      2733781.77      6803454.70
#Sta/Elev= 29
  4887.4  413.09  4904.2  412.93  4914.2  411.87  4924.2  410.65  4934.2  409.86
  4944.2  409.86  4954.2  409.56  4964.3  409.36  4974.3  409.00  4984.3  408.88
  4994.3  408.35  4997.6  407.21  4997.8  406.71  5001.3  406.71  5001.6  407.21
  5014.0  407.41  5019.1  407.75  5024.3  408.66  5034.3  409.60  5044.3  410.84
  5054.4  411.66  5064.4  411.97  5094.4  412.41  5124.4  412.68  5134.5  412.89
  5144.5  412.95  5174.5  413.33  5184.5  413.26  5190.3  413.33
#Mann=3,-1,0
  4887.4    0.07       0  4997.6    0.07       0  5001.6    0.07       0
Bank Sta=4997.6,5001.6
Exp/Cntr=0.3,0.1

Type RM Length L Ch R = 1,1097,69,69,69
BEGIN DESCRIPTION:
Twin Creek1591097.19
END DESCRIPTION:
XS GIS Cut Line= 3
      2733478.89      6803512.59      2733575.39      6803510.71
      2733655.96      6803511.91
#Sta/Elev= 25
  4903.3  410.83  4910.4  410.56  4920.4  410.42  4930.4  409.85  4940.4  409.67
  4950.4  409.21  4960.4  408.43  4970.4  407.40  4980.4  406.23  4988.4  405.97
  4988.7  405.47  4992.2  405.47  4992.4  405.97  4997.6  406.06  4999.8  406.06
  5002.6  406.06  5010.4  406.07  5020.4  407.58  5030.4  409.15  5040.4  410.40
  5050.4  411.02  5060.4  411.05  5070.4  411.16  5077.9  411.33  5080.4  411.33
#Mann=3,-1,0
  4903.3    0.07       0  4988.4    0.07       0  4992.4    0.07       0
Bank Sta=4988.4,4992.4
Exp/Cntr=0.3,0.1

Type RM Length L Ch R = 1,1028,25,25,25
BEGIN DESCRIPTION:
Twin Creek1591027.93
END DESCRIPTION:
XS GIS Cut Line= 5
      2733462.89      6803582.94      2733543.53      6803580.07
      2733575.89      6803579.97      2733587.66      6803579.81
      2733641.49      6803570.78
#Sta/Elev= 28
  4886.7  409.71  4890.8  409.71  4899.8  409.45  4909.8  409.40  4919.8  409.08
  4929.8  408.27  4939.8  407.61  4949.8  406.56  4959.9  406.13  4966.1  406.10
  4979.9  406.09  4989.9  406.11  4997.3  406.05  4999.7  406.05  5002.3  406.05
  5006.2  406.02  5006.4  405.52  5009.9  405.52  5010.2  406.02  5011.5  406.02
  5020.0  407.45  5029.8  409.55  5034.9  409.81  5040.3  409.63  5050.4  409.70
  5060.5  409.84  5065.9  409.86  5066.1  409.86
#Mann=4,-1,0
  4886.7    0.07       0  5006.2    0.07       0  5010.2    0.07       0
  5065.9    0.05       0
Bank Sta=5006.2,5010.2
Exp/Cntr=0.3,0.1

Type RM Length L Ch R = 1,1003,34,34,34
BEGIN DESCRIPTION:
Twin Creek1591002.85
END DESCRIPTION:
XS GIS Cut Line= 3
      2733466.05      6803605.96      2733575.67      6803605.08
      2733632.20      6803602.60
#Sta/Elev= 25
  4889.7  409.28  4892.2  409.28  4899.6  409.30  4909.6  409.25  4919.6  409.02
  4929.6  408.30  4939.6  408.16  4942.9  408.30  4949.6  408.58  4959.6  409.06
  4969.6  408.72  4979.6  408.36  4989.6  408.80  4997.0  408.79  4999.3  408.79
  5002.0  408.79  5009.7  408.86  5017.7  406.21  5017.9  405.71  5021.4  405.71
  5021.7  406.21  5029.7  407.12  5039.7  408.69  5049.7  409.21  5055.9  409.35
#Mann=4,-1,0
  4889.7    0.07       0  4942.9    0.05       0  5017.7    0.05       0
  5021.7    0.05       0
Bank Sta=5017.7,5021.7
Exp/Cntr=0.3,0.1

Type RM Length L Ch R = 1,969,86,86,86
BEGIN DESCRIPTION:
Mapping XS 2c82fb95
END DESCRIPTION:
XS GIS Cut Line= 3
      2733482.58      6803644.52      2733576.49      6803639.20
      2733635.38      6803636.72
#Sta/Elev= 23
  4906.4  407.87  4910.6  407.87  4919.8  407.72  4929.9  407.28  4939.9  406.72
  4949.9  406.25  4959.9  404.89  4969.9  403.85  4979.9  403.39  4988.0  403.34
  4988.2  402.84  4991.7  402.84  4992.0  403.34  4997.7  404.30  5000.5  404.30
  5002.7  404.30  5010.0  404.40  5020.0  406.09  5030.0  407.21  5040.0  408.00
  5050.0  408.56  5057.2  409.10  5059.4  409.10
#Mann=3,-1,0
  4906.4    0.05       0  4988.0    0.05       0  4992.0    0.05       0
Bank Sta=4988,4992
Exp/Cntr=0.3,0.1

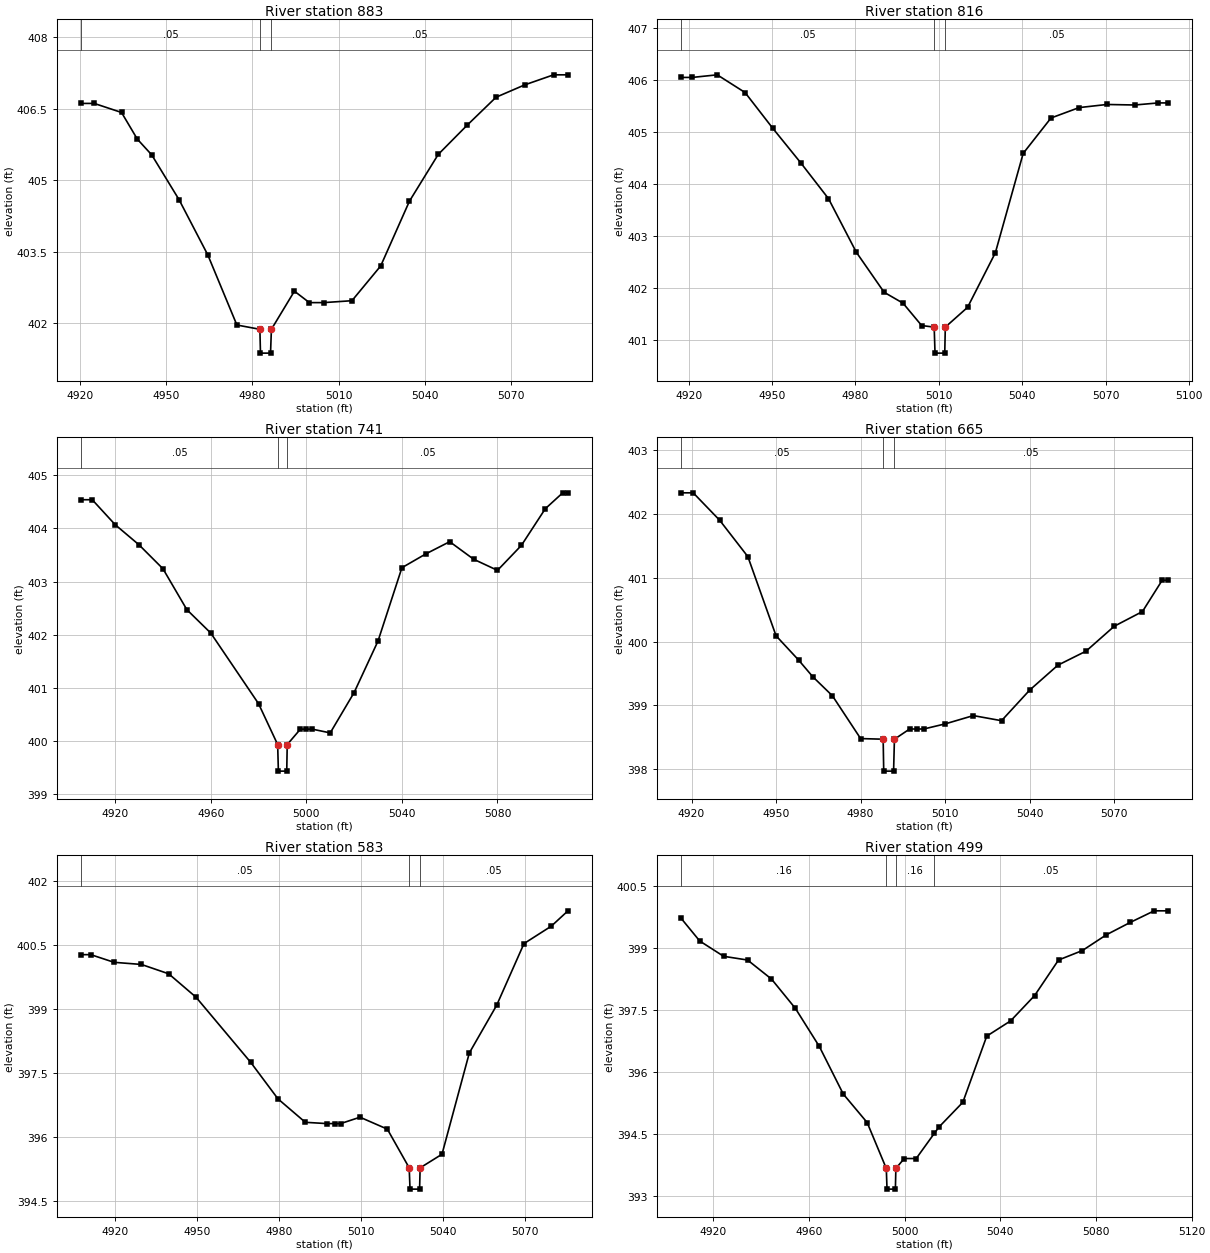
Type RM Length L Ch R = 1,883,67,67,67
BEGIN DESCRIPTION:
Twin Creek159883.26
END DESCRIPTION:
XS GIS Cut Line= 3
      2733452.03      6803704.88      2733531.36      6803709.35
      2733621.02      6803713.19
#Sta/Elev= 24
  4920.5  406.61  4925.0  406.61  4934.5  406.42  4940.0  405.86  4945.0  405.53
  4954.5  404.59  4964.5  403.43  4974.6  401.96  4982.6  401.87  4982.8  401.37
  4986.3  401.37  4986.6  401.87  4994.6  402.67  4999.8  402.43  5004.8  402.43
  5014.6  402.47  5024.6  403.20  5034.6  404.56  5044.6  405.54  5054.6  406.15
  5064.7  406.74  5074.7  407.00  5084.7  407.21  5089.7  407.21
#Mann=3,-1,0
  4920.5    0.05       0  4982.6    0.05       0  4986.6    0.05       0
Bank Sta=4982.6,4986.6
Exp/Cntr=0.3,0.1

Type RM Length L Ch R = 1,816,75,75,75
BEGIN DESCRIPTION:
Twin Creek159815.86
END DESCRIPTION:
XS GIS Cut Line= 3
      2733443.05      6803773.07      2733524.65      6803775.86
      2733617.92      6803779.79
#Sta/Elev= 24
  4917.3  406.05  4921.3  406.05  4930.3  406.10  4940.3  405.76  4950.3  405.07
  4960.3  404.41  4970.3  403.72  4980.3  402.69  4990.3  401.92  4997.1  401.71
  5003.8  401.28  5008.3  401.25  5008.6  400.75  5012.1  400.75  5012.3  401.25
  5020.3  401.63  5030.3  402.68  5040.3  404.59  5050.3  405.27  5060.4  405.47
  5070.4  405.53  5080.4  405.52  5088.9  405.56  5092.3  405.56
#Mann=3,-1,0
  4917.3    0.05       0  5008.3    0.05       0  5012.3    0.05       0
Bank Sta=5008.3,5012.3
Exp/Cntr=0.3,0.1

Type RM Length L Ch R = 1,741,76,76,76
BEGIN DESCRIPTION:
Twin Creek159741.41
END DESCRIPTION:
XS GIS Cut Line= 3
      2733431.84      6803846.41      2733525.83      6803850.36
      2733635.46      6803849.48
#Sta/Elev= 27
  4905.8  404.54  4910.4  404.54  4920.0  404.07  4930.0  403.69  4940.0  403.24
  4950.0  402.47  4960.0  402.03  4980.0  400.70  4988.0  399.93  4988.3  399.43
  4991.8  399.43  4992.0  399.93  4997.5  400.22  4999.9  400.22  5002.5  400.22
  5010.0  400.15  5020.0  400.91  5030.0  401.88  5040.0  403.26  5050.0  403.52
  5060.0  403.75  5070.0  403.42  5080.0  403.21  5090.0  403.68  5100.0  404.37
  5107.3  404.67  5109.5  404.67
#Mann=3,-1,0
  4905.8    0.05       0  4988.0    0.05       0  4992.0    0.05       0
Bank Sta=4988,4992
Exp/Cntr=0.3,0.1

Type RM Length L Ch R = 1,665,82,82,82
BEGIN DESCRIPTION:
Twin Creek159664.84
END DESCRIPTION:
XS GIS Cut Line= 3
      2733442.35      6803924.95      2733525.93      6803926.92
      2733615.00      6803929.02
#Sta/Elev= 26
  4916.3  402.33  4920.6  402.33  4930.0  401.90  4940.0  401.33  4950.0  400.09
  4958.0  399.71  4963.0  399.45  4970.0  399.15  4980.0  398.48  4988.0  398.47
  4988.2  397.97  4991.7  397.97  4992.0  398.47  4997.4  398.63  4999.9  398.63
  5002.4  398.63  5010.0  398.71  5020.0  398.84  5030.0  398.76  5040.0  399.24
  5050.0  399.63  5060.0  399.85  5070.0  400.24  5080.0  400.47  5087.0  400.96
  5089.0  400.96
#Mann=3,-1,0
  4916.3    0.05       0  4988.0    0.05       0  4992.0    0.05       0
Bank Sta=4988,4992
Exp/Cntr=0.3,0.1

Type RM Length L Ch R = 1,583,84,84,84
BEGIN DESCRIPTION:
Twin Creek159582.57
END DESCRIPTION:
XS GIS Cut Line= 3
      2733433.97      6804008.09      2733526.75      6804009.20
      2733612.06      6804010.14
#Sta/Elev= 24
  4907.6  400.28  4911.1  400.28  4919.6  400.10  4929.6  400.05  4939.6  399.83
  4949.6  399.28  4969.6  397.75  4979.6  396.89  4989.6  396.34  4997.5  396.31
  5000.4  396.31  5002.5  396.31  5009.6  396.46  5019.6  396.18  5027.6  395.27
  5027.9  394.77  5031.4  394.77  5031.6  395.27  5039.6  395.59  5049.6  397.97
  5059.6  399.09  5069.6  400.54  5079.6  400.95  5085.7  401.31
#Mann=3,-1,0
  4907.6    0.05       0  5027.6    0.05       0  5031.6    0.05       0
Bank Sta=5027.6,5031.6
Exp/Cntr=0.3,0.1

Type RM Length L Ch R = 1,499,86,86,86
BEGIN DESCRIPTION:
Twin Creek159498.53
END DESCRIPTION:
XS GIS Cut Line= 3
      2733408.18      6804085.42      2733501.97      6804085.46
      2733611.67      6804083.74
#Sta/Elev= 27
  4906.5  399.71  4914.3  399.16  4924.3  398.79  4934.3  398.70  4944.3  398.24
  4954.3  397.53  4964.3  396.61  4974.3  395.46  4984.3  394.77  4992.3  393.66
  4992.6  393.16  4996.1  393.16  4996.3  393.66  4999.8  393.90  5004.8  393.90
  5012.4  394.51  5014.3  394.66  5024.3  395.26  5034.3  396.86  5044.3  397.23
  5054.3  397.84  5064.3  398.70  5074.3  398.93  5084.3  399.31  5094.3  399.61
  5104.3  399.89  5110.0  399.89
#Mann=4,-1,0
  4906.5    0.16       0  4992.3    0.07       0  4996.3    0.16       0
  5012.4    0.05       0
Bank Sta=4992.3,4996.3
Exp/Cntr=0.3,0.1

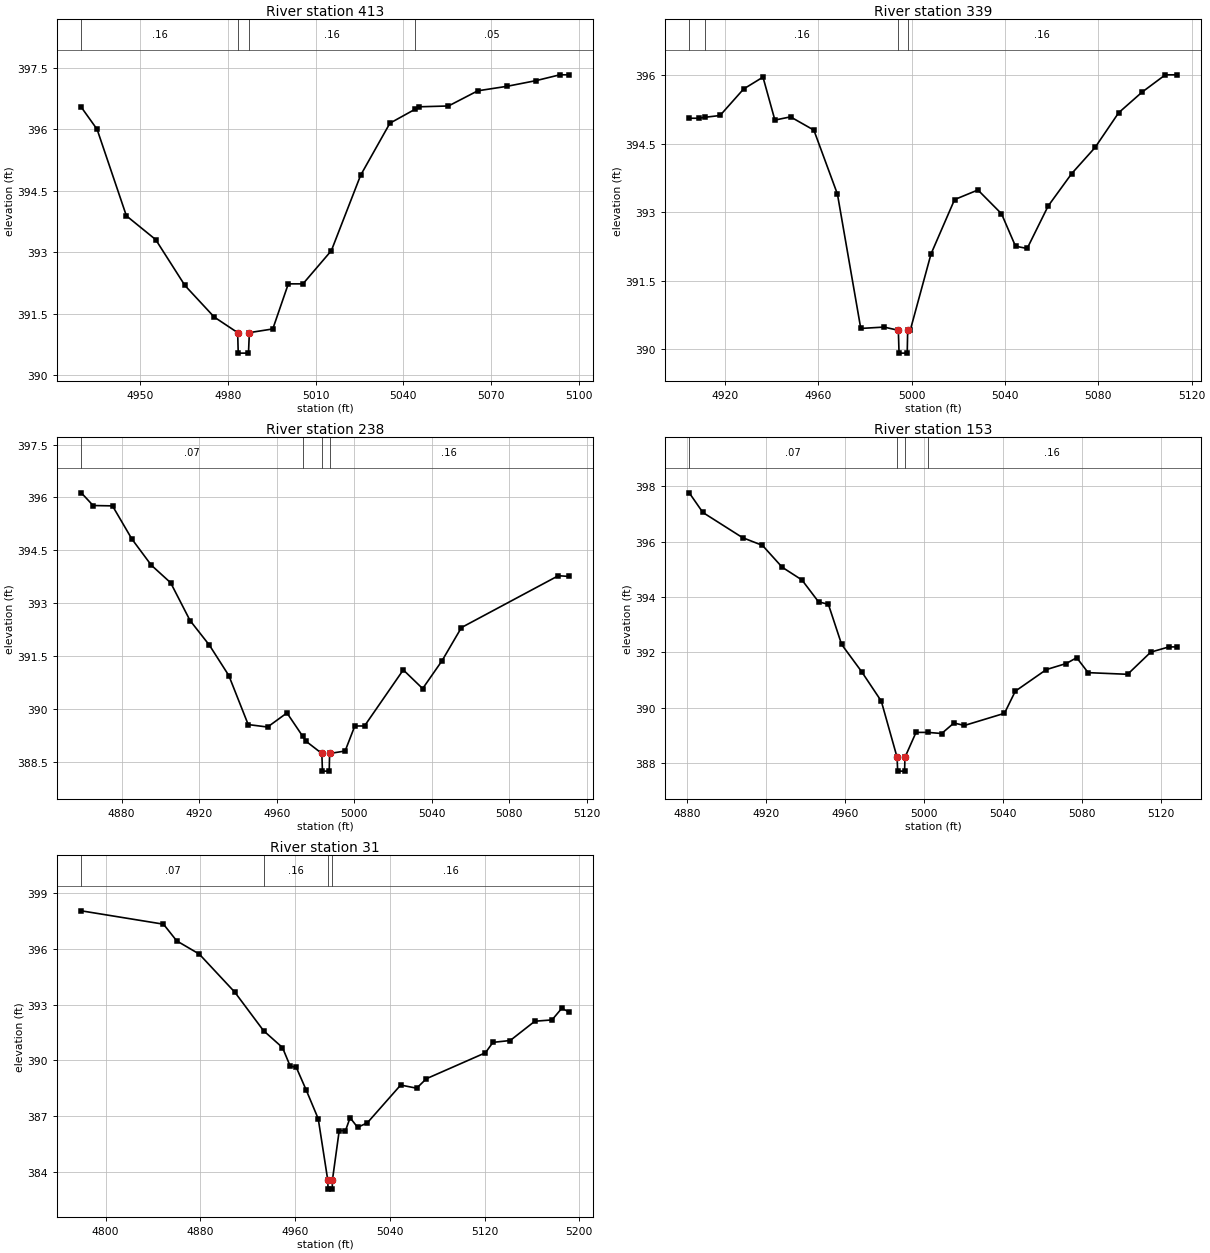
Type RM Length L Ch R = 1,413,74,74,74
BEGIN DESCRIPTION:
Twin Creek159413.38
END DESCRIPTION:
XS GIS Cut Line= 3
      2733400.62      6804161.83      2733471.54      6804161.77
      2733567.11      6804163.16
#Sta/Elev= 24
  4930.0  396.54  4935.4  396.00  4945.4  393.89  4955.4  393.31  4965.4  392.19
  4975.4  391.42  4983.4  391.04  4983.6  390.54  4987.1  390.54  4987.4  391.04
  4995.4  391.13  5000.7  392.23  5005.7  392.23  5015.4  393.04  5025.4  394.88
  5035.4  396.15  5044.0  396.49  5045.4  396.55  5055.4  396.57  5065.4  396.94
  5075.4  397.05  5085.4  397.19  5093.4  397.33  5096.5  397.33
#Mann=4,-1,0
  4930.0    0.16       0  4983.4    0.07       0  4987.4    0.16       0
  5044.0    0.05       0
Bank Sta=4983.4,4987.4
Exp/Cntr=0.3,0.1

Type RM Length L Ch R = 1,339,101,101,101
BEGIN DESCRIPTION:
Twin Creek159338.59
END DESCRIPTION:
XS GIS Cut Line= 3
      2733332.84      6804212.62      2733427.11      6804221.77
      2733540.82      6804232.24
#Sta/Elev= 30
  4904.7  395.06  4908.8  395.06  4911.3  395.08  4917.9  395.12  4928.0  395.70
  4936.3  395.96  4941.4  395.02  4948.1  395.09  4958.1  394.80  4968.2  393.40
  4978.2  390.46  4988.2  390.49  4994.3  390.42  4994.6  389.92  4998.1  389.92
  4998.3  390.42  4999.4  390.42  5008.3  392.09  5018.4  393.28  5028.4  393.49
  5038.5  392.97  5044.5  392.26  5049.5  392.21  5058.5  393.14  5068.6  393.85
  5078.6  394.42  5088.7  395.18  5098.7  395.63  5108.7  396.01  5113.6  396.01
#Mann=4,-1,0
  4904.7    0.05       0  4911.3    0.16       0  4994.3    0.07       0
  4998.3    0.16       0
Bank Sta=4994.3,4998.3
Exp/Cntr=0.3,0.1

Type RM Length L Ch R = 1,238,85,85,85
BEGIN DESCRIPTION:
Twin Creek159237.65
END DESCRIPTION:
XS GIS Cut Line= 3
      2733239.90      6804306.59      2733381.08      6804306.28
      2733491.39      6804306.81
#Sta/Elev= 27
  4859.2  396.13  4865.3  395.77  4875.3  395.76  4885.3  394.82  4895.3  394.08
  4905.3  393.58  4915.3  392.51  4925.3  391.81  4935.3  390.95  4945.3  389.56
  4955.3  389.49  4965.3  389.89  4973.4  389.23  4975.3  389.08  4983.3  388.74
  4983.6  388.24  4987.1  388.24  4987.3  388.74  4995.3  388.81  5000.3  389.52
  5005.3  389.52  5025.3  391.11  5035.3  390.58  5045.3  391.37  5055.3  392.31
  5105.3  393.78  5110.7  393.76
#Mann=4,-1,0
  4859.2    0.07       0  4973.4    0.16       0  4983.3    0.07       0
  4987.3    0.16       0
Bank Sta=4983.3,4987.3
Exp/Cntr=0.3,0.1

Type RM Length L Ch R = 1,153,122,122,122
BEGIN DESCRIPTION:
Twin Creek159153.01
END DESCRIPTION:
XS GIS Cut Line= 3
      2733219.08      6804382.00      2733336.07      6804371.77
      2733458.44      6804329.18
#Sta/Elev= 30
  4881.0  397.76  4887.9  397.05  4908.0  396.14  4918.1  395.86  4928.1  395.07
  4938.1  394.61  4946.5  393.82  4951.5  393.73  4958.2  392.28  4968.3  391.30
  4978.3  390.23  4986.3  388.20  4986.6  387.70  4990.1  387.70  4990.3  388.20
  4995.9  389.10  5001.9  389.10  5008.9  389.06  5015.1  389.44  5020.4  389.35
  5040.7  389.79  5046.2  390.59  5061.9  391.37  5072.0  391.59  5077.3  391.80
  5083.1  391.26  5103.1  391.20  5114.8  392.00  5124.0  392.19  5128.0  392.19
#Mann=4,-1,0
  4881.0    0.07       0  4986.3    0.07       0  4990.3    0.07       0
  5001.9    0.16       0
Bank Sta=4986.3,4990.3
Exp/Cntr=0.3,0.1

Type RM Length L Ch R = 1,31,0,0,0
BEGIN DESCRIPTION:
Twin Creek15930.799
END DESCRIPTION:
XS GIS Cut Line= 3
      2733156.92      6804458.42      2733376.34      6804480.20
      2733492.05      6804327.99
#Sta/Elev= 30
  4779.5  398.06  4848.9  397.34  4860.1  396.44  4879.1  395.73  4909.2  393.67
  4933.4  391.60  4949.4  390.69  4955.9  389.69  4961.0  389.63  4969.5  388.39
  4979.6  386.85  4987.6  383.56  4987.9  383.06  4991.4  383.06  4991.6  383.56
  4997.3  386.21  5002.6  386.21  5006.5  386.91  5012.8  386.39  5021.0  386.63
  5049.2  388.67  5062.7  388.50  5070.9  389.01  5120.8  390.41  5127.1  390.97
  5141.7  391.07  5162.5  392.11  5177.0  392.18  5185.3  392.81  5191.2  392.61
#Mann=4,-1,0
  4779.5    0.07       0  4933.4    0.16       0  4987.6    0.07       0
  4991.6    0.16       0
Bank Sta=4987.6,4991.6
Exp/Cntr=0.3,0.1

Chan Stop Cuts=-1