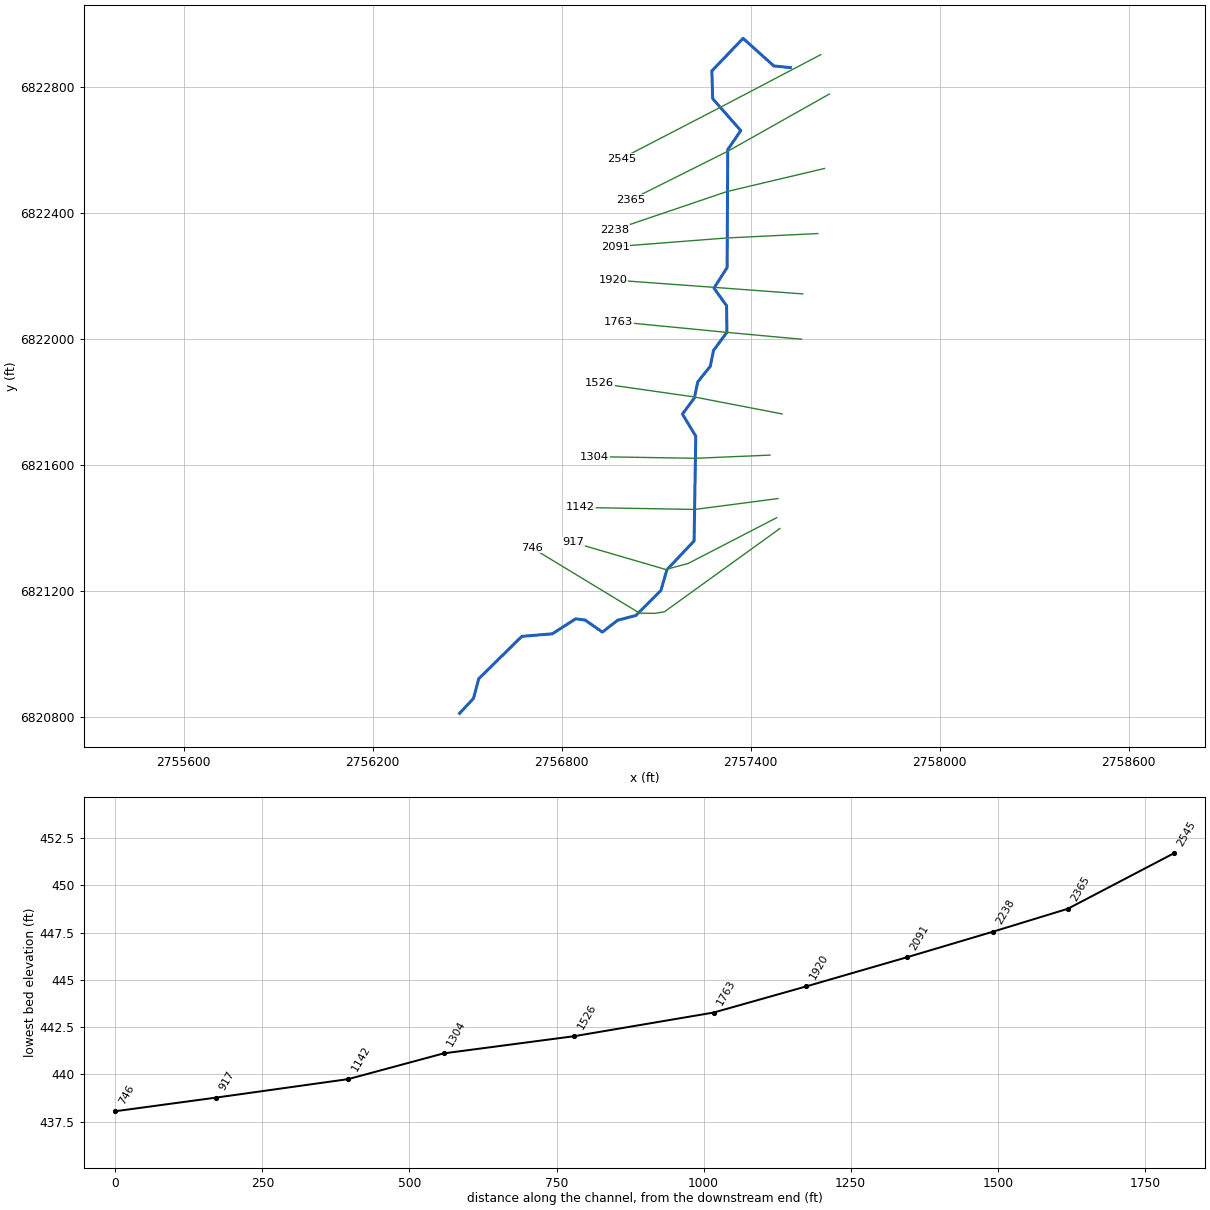
--- Twin Creek164.prj (project) ---

Proj Title=Twin Creek164 Base Level Engineering
Current Plan=p01
Default Exp/Contr=0.3,0.1
English Units
Geom File=g01
Flow File=f01
Plan File=p01
BEGIN DESCRIPTION:
Twin Creek164
END DESCRIPTION:

--- Twin Creek164.p01 (plan) ---

Plan Title=Multiple Run
Short Identifier=Multiple
Geom File=g01
Flow File=f01
Subcritical Flow
K Sum by GR= 0
Std Step Tol= 0.01
Critical Tol= 0.01
Num of Std Step Trials= 20
Max Error Tol= 0.3
Flow Tol Ratio= 0.001
Split Flow NTrial= 30
Split Flow Tol= 0.02
Split Flow Ratio= 0.02
Log Output Level= 0
Friction Slope Method= 1
Unsteady Friction Slope Method= 2
Unsteady Bridges Friction Slope Method= 1
Parabolic Critical Depth
Global Vel Dist=  1 , 1 , 1
Global Log Level= 0
CheckData=True
Encroach Param= -1, 0, 0, 0
BEGIN DESCRIPTION:
Multiple Run
END DESCRIPTION:

--- Twin Creek164.f01 (steady flow) ---

Flow Title=Multiple
Number of Profiles=7
Profile Names=10-year,25-year,50-year,1pct_min,100-year,1pct_plu,500-year
River Rch & RM= Twin Creek164,Reach-1,2545
     165     204     234     134     268     535     351
Boundary for River Rch & Prof#=Twin Creek164,Reach-1,1
Up Type=0
Dn Type=3
Dn Slope=0.005
Boundary for River Rch & Prof#=Twin Creek164,Reach-1,2
Up Type=0
Dn Type=3
Dn Slope=0.005
Boundary for River Rch & Prof#=Twin Creek164,Reach-1,3
Up Type=0
Dn Type=3
Dn Slope=0.005
Boundary for River Rch & Prof#=Twin Creek164,Reach-1,4
Up Type=0
Dn Type=3
Dn Slope=0.005
Boundary for River Rch & Prof#=Twin Creek164,Reach-1,5
Up Type=0
Dn Type=3
Dn Slope=0.005
Boundary for River Rch & Prof#=Twin Creek164,Reach-1,6
Up Type=0
Dn Type=3
Dn Slope=0.005
Boundary for River Rch & Prof#=Twin Creek164,Reach-1,7
Up Type=0
Dn Type=3
Dn Slope=0.005

--- Twin Creek164.g01 (geometry) ---

Geom Title=Existing Conditions

River Reach=Twin Creek164,Reach-1
Reach XY= 30
      2757526.00      6822861.00      2757473.48      6822866.35
      2757375.98      6822953.94      2757276.93      6822850.53
      2757279.48      6822762.50      2757368.67      6822661.10
      2757327.39      6822600.57      2757325.34      6822226.16
      2757283.56      6822161.00      2757323.64      6822105.11
      2757324.75      6822020.70      2757282.12      6821963.18
      2757271.84      6821912.72      2757232.05      6821863.19
      2757221.57      6821812.64      2757183.53      6821761.01
      2757225.82      6821691.02      2757220.53      6821358.55
      2757134.18      6821267.04      2757115.23      6821201.30
      2757035.70      6821121.74      2756977.65      6821106.55
      2756929.31      6821069.07      2756874.36      6821107.39
      2756844.46      6821111.11      2756770.44      6821063.50
      2756673.57      6821055.48      2756536.70      6820920.71
      2756520.29      6820858.65      2756476.00      6820811.00

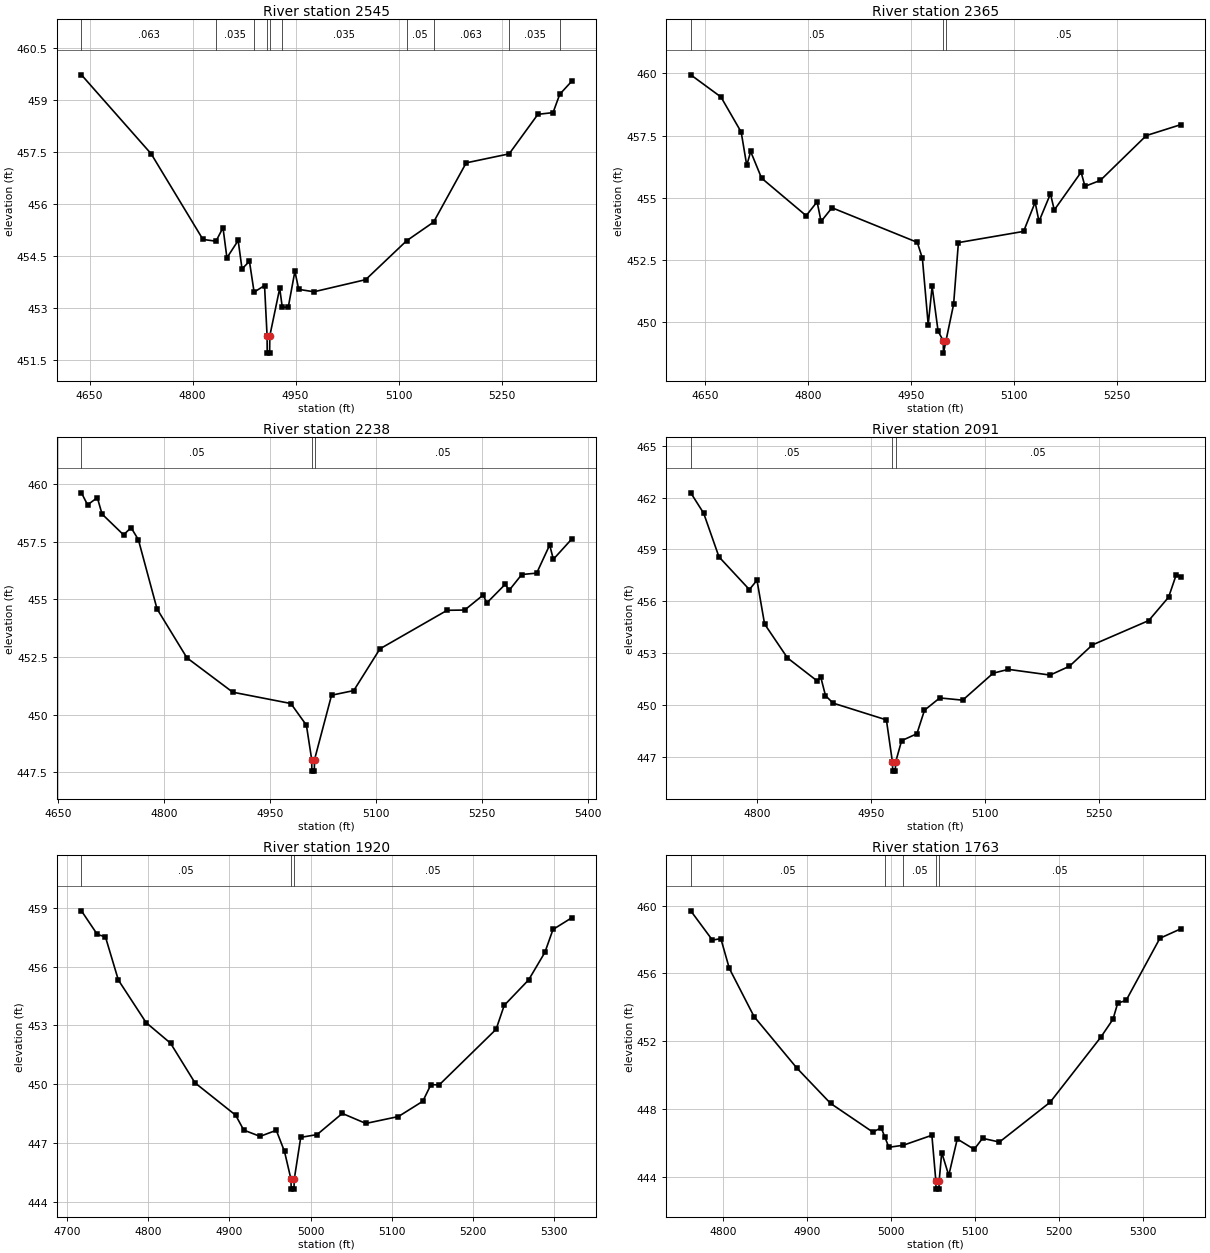
Type RM Length L Ch R = 1,2545,180,180,180
BEGIN DESCRIPTION:
Twin Creek1642545.365
END DESCRIPTION:
XS GIS Cut Line= 3
      2757622.79      6822902.19      2757302.28      6822734.13
      2756989.73      6822572.22
#Sta/Elev= 30
  4638.1  459.72  4739.7  457.44  4815.1  454.97  4834.1  454.92  4844.3  455.31
  4850.0  454.44  4866.4  454.94  4872.0  454.12  4882.8  454.34  4889.6  453.45
  4904.8  453.64  4908.5  452.19  4908.7  451.69  4912.2  451.69  4912.5  452.19
  4926.9  453.56  4930.6  453.02  4939.3  453.01  4949.0  454.05  4954.6  453.53
  4976.7  453.46  5052.1  453.81  5111.6  454.93  5151.0  455.47  5198.5  457.18
  5261.1  457.44  5302.9  458.58  5325.0  458.63  5334.8  459.16  5352.0  459.53
#Mann=10,-1,0
  4638.1   0.063       0  4834.1   0.035       0  4889.6   0.063       0
  4908.5   0.035       0  4912.5   0.063       0  4930.6   0.035       0
  5111.6    0.05       0  5151.0   0.063       0  5261.1   0.035       0
  5334.8    0.05       0
Bank Sta=4908.5,4912.5
Exp/Cntr=0.3,0.1

Type RM Length L Ch R = 1,2365,127,127,127
BEGIN DESCRIPTION:
Twin Creek1642365.46
END DESCRIPTION:
XS GIS Cut Line= 3
      2757650.03      6822777.16      2757327.03      6822595.25
      2757019.85      6822441.52
#Sta/Elev= 30
  4628.8  459.94  4672.8  459.05  4702.3  457.64  4710.4  456.30  4716.1  456.86
  4732.0  455.79  4797.0  454.28  4812.9  454.84  4818.7  454.05  4834.6  454.60
  4958.9  453.21  4966.3  452.57  4974.8  449.90  4980.5  451.44  4989.2  449.64
  4996.7  449.26  4997.0  448.76  5000.7  449.26  5011.8  450.72  5018.8  453.20
  5113.8  453.65  5130.6  454.82  5136.2  454.05  5152.9  455.16  5158.5  454.51
  5197.6  456.03  5203.2  455.46  5225.6  455.70  5292.6  457.50  5343.0  457.94
#Mann=3,-1,0
  4628.8    0.05       0  4996.7    0.05       0  5000.7    0.05       0
Bank Sta=4996.7,5000.7
Exp/Cntr=0.3,0.1

Type RM Length L Ch R = 1,2238,147,147,147
BEGIN DESCRIPTION:
Twin Creek1642238.19
END DESCRIPTION:
XS GIS Cut Line= 3
      2757634.45      6822540.82      2757324.63      6822467.47
      2756969.23      6822346.83
#Sta/Elev= 30
  4683.0  459.61  4691.7  459.09  4705.5  459.40  4712.2  458.69  4742.6  457.79
  4753.3  458.10  4763.6  457.58  4790.0  454.58  4832.3  452.46  4897.2  450.97
  4979.4  450.48  5001.4  449.54  5008.9  448.05  5009.1  447.55  5012.6  447.55
  5012.9  448.05  5037.0  450.84  5068.4  451.04  5105.5  452.85  5200.6  454.52
  5225.4  454.53  5251.5  455.18  5256.8  454.84  5282.9  455.65  5288.2  455.38
  5306.2  456.07  5327.3  456.13  5345.7  457.35  5350.9  456.73  5376.7  457.60
#Mann=3,-1,0
  4683.0    0.05       0  5008.9    0.05       0  5012.9    0.05       0
Bank Sta=5008.9,5012.9
Exp/Cntr=0.3,0.1

Type RM Length L Ch R = 1,2091,171,171,171
BEGIN DESCRIPTION:
Twin Creek1642090.72
END DESCRIPTION:
XS GIS Cut Line= 3
      2757613.02      6822334.21      2757325.27      6822320.28
      2756969.83      6822292.65
#Sta/Elev= 30
  4712.7  462.27  4729.7  461.09  4749.8  458.57  4789.8  456.68  4799.8  457.22
  4809.8  454.69  4839.9  452.73  4878.7  451.41  4883.7  451.62  4889.9  450.55
  4899.9  450.12  4970.0  449.15  4978.0  446.69  4978.3  446.19  4981.8  446.19
  4982.0  446.69  4990.0  447.95  5010.1  448.35  5020.1  449.71  5040.2  450.42
  5070.3  450.29  5110.4  451.85  5130.4  452.07  5185.3  451.74  5210.7  452.25
  5240.8  453.48  5315.0  454.89  5341.1  456.24  5351.1  457.53  5357.3  457.43
#Mann=3,-1,0
  4712.7    0.05       0  4978.0    0.05       0  4982.0    0.05       0
Bank Sta=4978,4982
Exp/Cntr=0.3,0.1

Type RM Length L Ch R = 1,1920,157,157,157
BEGIN DESCRIPTION:
Twin Creek1641919.84
END DESCRIPTION:
XS GIS Cut Line= 3
      2757565.48      6822142.56      2757284.25      6822163.42
      2756963.20      6822186.79
#Sta/Elev= 30
  4717.7  458.84  4737.2  457.64  4747.3  457.51  4763.2  455.31  4797.4  453.14
  4827.5  452.09  4857.6  450.07  4907.7  448.42  4917.7  447.66  4937.8  447.34
  4957.8  447.65  4967.9  446.57  4975.9  445.15  4976.1  444.65  4979.6  444.65
  4979.9  445.15  4987.9  447.29  5008.0  447.43  5039.1  448.51  5068.1  448.00
  5108.2  448.35  5138.3  449.13  5148.3  449.98  5158.4  449.96  5228.6  452.80
  5238.6  454.02  5268.7  455.32  5288.7  456.72  5298.7  457.89  5321.6  458.48
#Mann=3,-1,0
  4717.7    0.05       0  4975.9    0.05       0  4979.9    0.05       0
Bank Sta=4975.9,4979.9
Exp/Cntr=0.3,0.1

Type RM Length L Ch R = 1,1763,237,237,237
BEGIN DESCRIPTION:
Twin Creek1641762.64
END DESCRIPTION:
XS GIS Cut Line= 3
      2757561.69      6821998.72      2757323.00      6822020.63
      2756981.11      6822053.88
#Sta/Elev= 30
  4762.0  459.70  4787.8  457.97  4797.8  458.06  4807.9  456.30  4837.3  453.46
  4888.2  450.42  4928.4  448.33  4978.6  446.64  4988.6  446.89  4992.9  446.35
  4997.7  445.74  5014.8  445.86  5048.9  446.45  5053.6  443.77  5053.8  443.27
  5057.3  443.27  5057.6  443.77  5060.6  445.43  5069.0  444.08  5079.1  446.23
  5099.2  445.62  5109.2  446.27  5129.3  446.05  5189.6  448.40  5249.9  452.24
  5264.4  453.30  5270.0  454.25  5280.0  454.41  5320.2  458.08  5345.2  458.64
#Mann=5,-1,0
  4762.0    0.05       0  4992.9    0.16       0  5014.8    0.05       0
  5053.6    0.07       0  5057.6    0.05       0
Bank Sta=5053.6,5057.6
Exp/Cntr=0.3,0.1

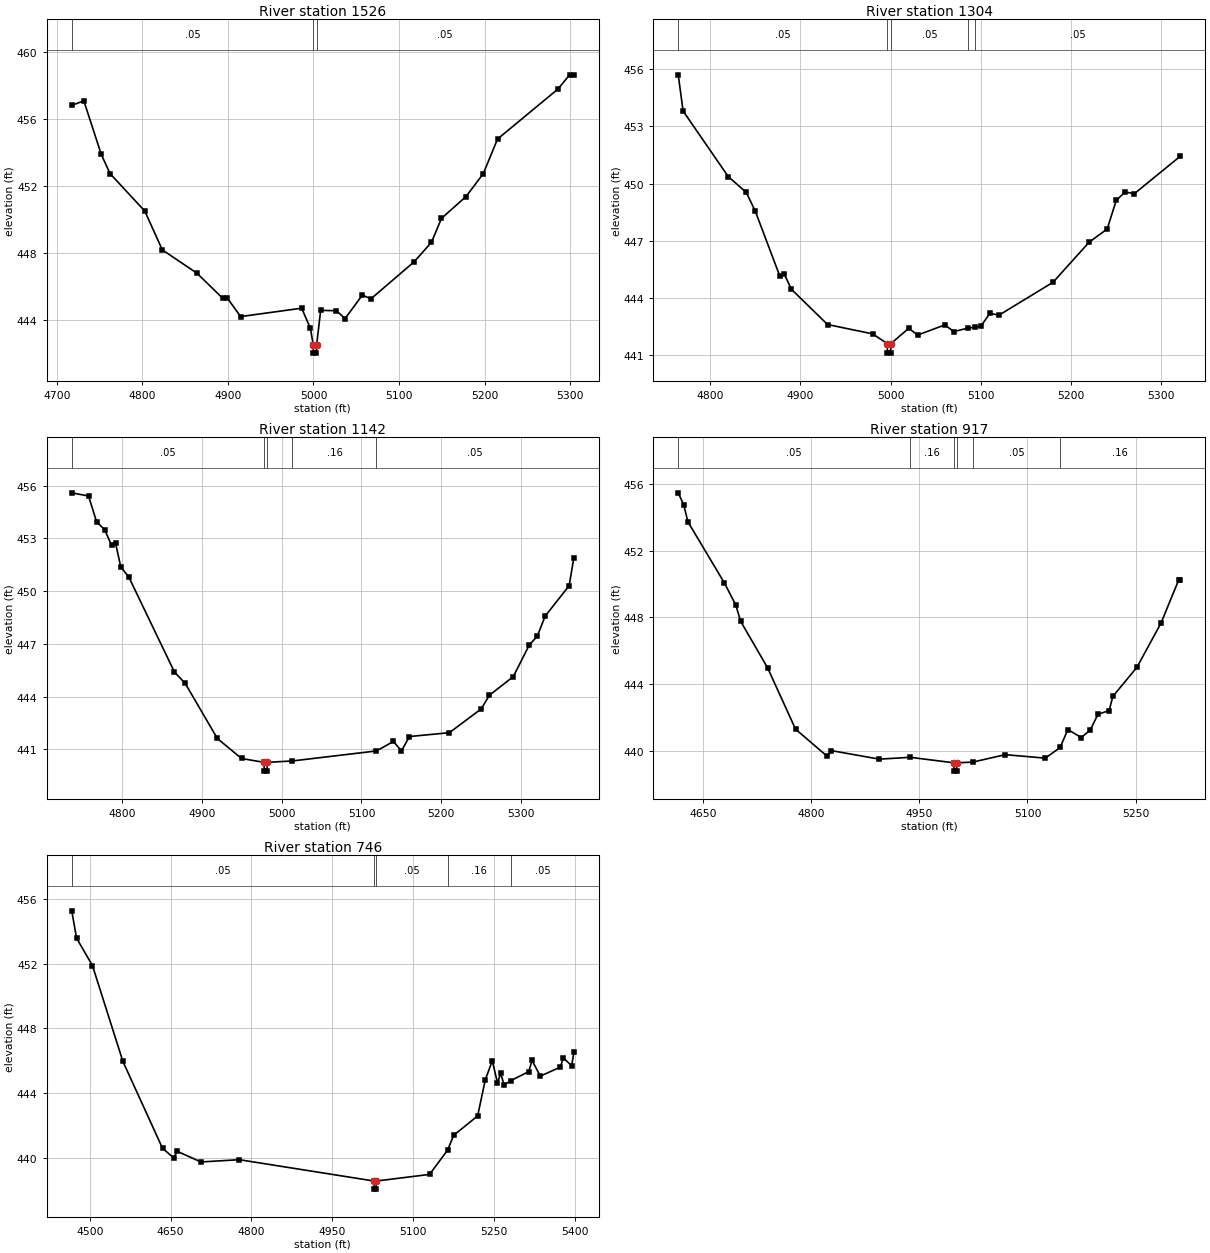
Type RM Length L Ch R = 1,1526,222,222,222
BEGIN DESCRIPTION:
Twin Creek1641525.56
END DESCRIPTION:
XS GIS Cut Line= 3
      2757499.86      6821761.68      2757220.68      6821815.51
      2756921.26      6821858.45
#Sta/Elev= 30
  4717.5  456.80  4731.6  457.07  4752.0  453.87  4762.2  452.73  4802.9  450.49
  4823.3  448.18  4864.0  446.78  4894.1  445.28  4899.2  445.31  4914.9  444.20
  4986.2  444.70  4996.4  443.50  4999.7  442.52  4999.9  442.02  5003.4  442.02
  5003.7  442.52  5008.4  444.57  5026.8  444.55  5036.9  444.08  5057.1  445.48
  5067.2  445.26  5117.7  447.47  5137.9  448.63  5149.6  450.06  5178.3  451.36
  5198.5  452.73  5215.1  454.79  5285.7  457.77  5299.4  458.62  5304.3  458.62
#Mann=3,-1,0
  4717.5    0.05       0  4999.7    0.05       0  5003.7    0.05       0
Bank Sta=4999.7,5003.7
Exp/Cntr=0.3,0.1

Type RM Length L Ch R = 1,1304,162,162,162
BEGIN DESCRIPTION:
Twin Creek1641303.75
END DESCRIPTION:
XS GIS Cut Line= 3
      2757461.42      6821630.87      2757224.68      6821620.78
      2756904.88      6821625.99
#Sta/Elev= 30
  4764.5  455.71  4769.9  453.81  4820.0  450.37  4840.0  449.54  4850.0  448.55
  4877.0  445.17  4882.0  445.27  4890.0  444.46  4930.1  442.61  4980.1  442.12
  4996.3  441.61  4996.5  441.11  5000.0  441.11  5000.3  441.61  5020.1  442.41
  5030.1  442.06  5060.1  442.59  5070.1  442.24  5086.4  442.43  5094.0  442.46
  5100.2  442.53  5110.2  443.20  5120.2  443.10  5180.2  444.83  5220.2  446.93
  5240.2  447.62  5250.2  449.12  5260.2  449.57  5270.2  449.47  5321.3  451.44
#Mann=5,-1,0
  4764.5    0.05       0  4996.3    0.05       0  5000.3    0.05       0
  5086.4    0.16       0  5094.0    0.05       0
Bank Sta=4996.3,5000.3
Exp/Cntr=0.3,0.1

Type RM Length L Ch R = 1,1142,225,225,225
BEGIN DESCRIPTION:
Twin Creek1641141.69
END DESCRIPTION:
XS GIS Cut Line= 3
      2757486.87      6821492.94      2757223.12      6821458.39
      2756860.07      6821464.67
#Sta/Elev= 30
  4737.0  455.60  4758.0  455.42  4768.1  453.95  4778.2  453.50  4786.8  452.62
  4791.9  452.73  4798.4  451.38  4808.5  450.80  4865.7  445.39  4879.1  444.75
  4919.4  441.61  4949.7  440.47  4977.9  440.25  4978.2  439.75  4981.7  439.75
  4981.9  440.25  5013.5  440.33  5118.8  440.90  5140.1  441.44  5150.1  440.90
  5160.1  441.72  5210.2  441.94  5250.2  443.30  5260.2  444.07  5290.2  445.13
  5310.2  446.93  5320.2  447.43  5330.2  448.58  5360.2  450.31  5366.1  451.90
#Mann=5,-1,0
  4737.0    0.05       0  4977.9    0.05       0  4981.9    0.05       0
  5013.5    0.16       0  5118.8    0.05       0
Bank Sta=4977.9,4981.9
Exp/Cntr=0.3,0.1

Type RM Length L Ch R = 1,917,171,171,171
BEGIN DESCRIPTION:
Twin Creek164917.24
END DESCRIPTION:
XS GIS Cut Line= 4
      2757482.81      6821432.22      2757201.56      6821286.84
      2757130.37      6821267.80      2756836.15      6821353.72
#Sta/Elev= 30
  4615.3  455.49  4623.0  454.76  4628.7  453.75  4679.3  450.08  4695.2  448.75
  4701.8  447.78  4739.4  444.97  4778.1  441.29  4822.4  439.65  4828.0  440.00
  4894.5  439.49  4937.2  439.60  4997.8  439.27  4998.0  438.77  5001.5  438.77
  5001.8  439.27  5023.9  439.31  5069.0  439.76  5124.7  439.55  5145.3  440.19
  5156.0  441.27  5174.6  440.79  5187.2  441.24  5197.7  442.18  5213.3  442.41
  5218.5  443.26  5251.9  445.01  5285.4  447.67  5309.6  450.23  5312.1  450.23
#Mann=6,-1,0
  4615.3    0.05       0  4937.2    0.16       0  4997.8    0.07       0
  5001.8    0.16       0  5023.9    0.05       0  5145.3    0.16       0
Bank Sta=4997.8,5001.8
Exp/Cntr=0.3,0.1

Type RM Length L Ch R = 1,746,0,0,0
BEGIN DESCRIPTION:
Twin Creek164745.6
END DESCRIPTION:
XS GIS Cut Line= 5
      2757492.90      6821397.87      2757126.28      6821133.48
      2757095.17      6821128.39      2757047.37      6821129.40
      2756705.48      6821336.76
#Sta/Elev= 30
  4466.7  455.26  4475.6  453.57  4505.1  451.87  4561.5  445.95  4635.1  440.57
  4656.0  439.98  4662.1  440.39  4706.3  439.73  4777.4  439.87  5027.5  438.55
  5027.7  438.05  5031.2  438.05  5031.5  438.55  5130.3  438.96  5163.7  440.46
  5175.1  441.38  5219.5  442.58  5233.6  444.80  5246.6  445.99  5256.3  444.62
  5262.1  445.21  5268.6  444.49  5281.1  444.76  5314.4  445.32  5320.3  446.01
  5335.8  445.04  5372.6  445.59  5378.5  446.16  5393.9  445.68  5397.9  446.51
#Mann=5,-1,0
  4466.7    0.05       0  5027.5    0.05       0  5031.5    0.05       0
  5163.7    0.16       0  5281.1    0.05       0
Bank Sta=5027.5,5031.5
Exp/Cntr=0.3,0.1

Chan Stop Cuts=-1