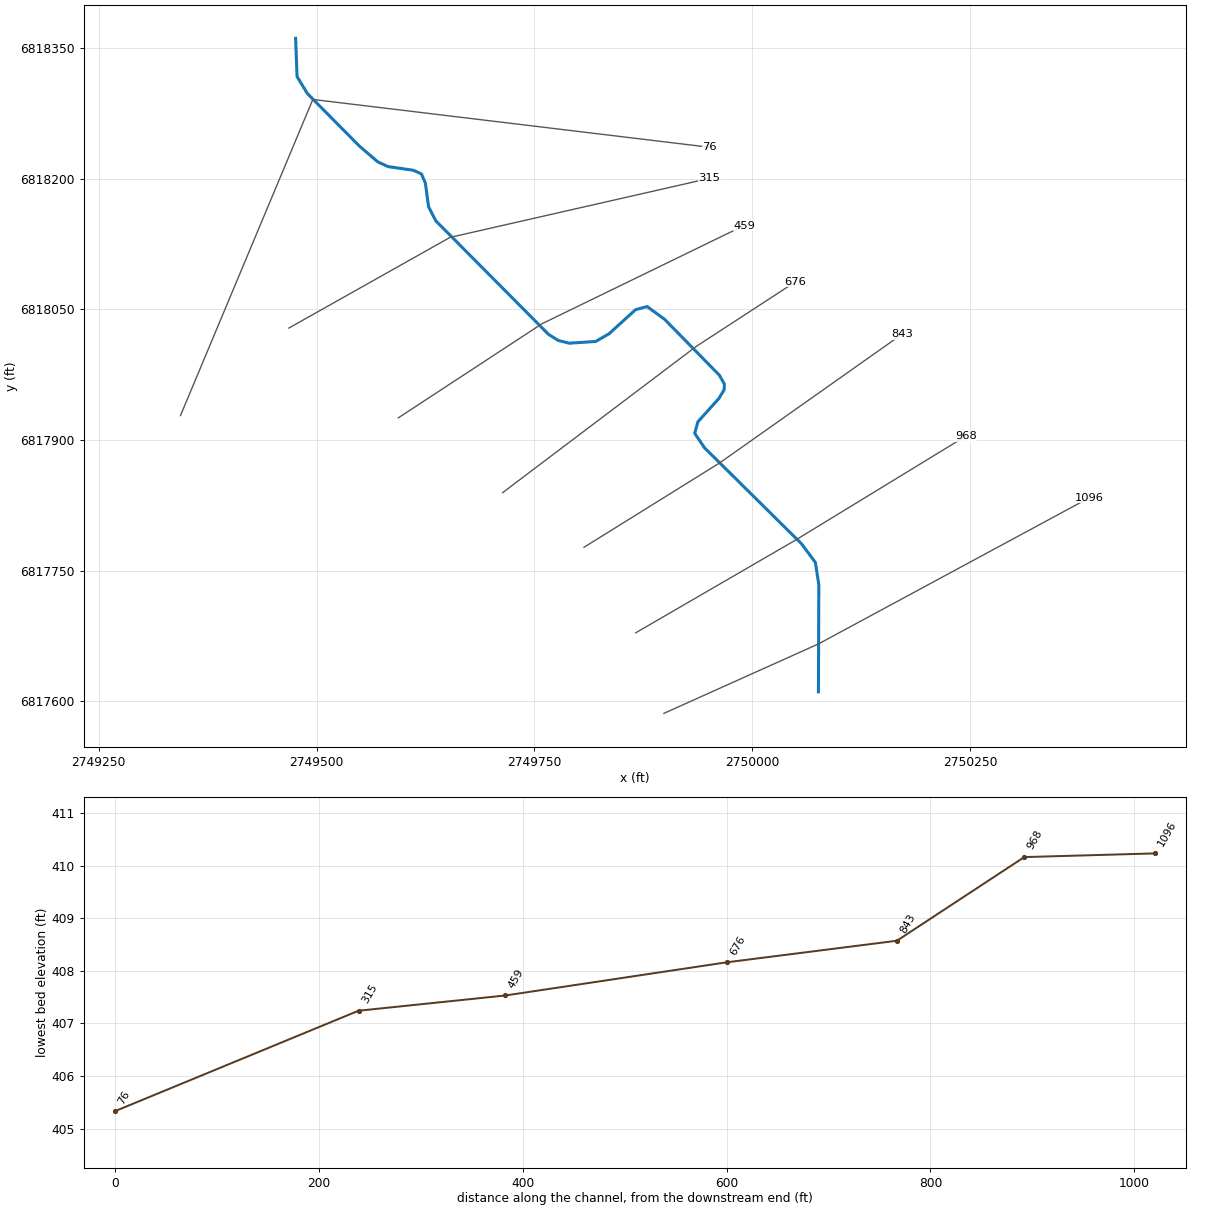
--- Twin Creek168.prj (project) ---

Proj Title=Twin Creek168 Base Level Engineering
Current Plan=p01
Default Exp/Contr=0.3,0.1
English Units
Geom File=g01
Flow File=f01
Plan File=p01
BEGIN DESCRIPTION:
Twin Creek168
END DESCRIPTION:

--- Twin Creek168.p01 (plan) ---

Plan Title=Multiple Run
Short Identifier=Multiple
Geom File=g01
Flow File=f01
Subcritical Flow
K Sum by GR= 0
Std Step Tol= 0.01
Critical Tol= 0.01
Num of Std Step Trials= 20
Max Error Tol= 0.3
Flow Tol Ratio= 0.001
Split Flow NTrial= 30
Split Flow Tol= 0.02
Split Flow Ratio= 0.02
Log Output Level= 0
Friction Slope Method= 1
Unsteady Friction Slope Method= 2
Unsteady Bridges Friction Slope Method= 1
Parabolic Critical Depth
Global Vel Dist=  1 , 1 , 1
Global Log Level= 0
CheckData=True
Encroach Param= -1, 0, 0, 0
BEGIN DESCRIPTION:
Multiple Run
END DESCRIPTION:

--- Twin Creek168.f01 (steady flow) ---

Flow Title=Multiple
Number of Profiles=7
Profile Names=10-year,25-year,50-year,1pct_min,100-year,1pct_plu,500-year
River Rch & RM= Twin Creek168,Reach-1,1096
     244     309     359     208     415     829     555
Boundary for River Rch & Prof#=Twin Creek168,Reach-1,1
Up Type=0
Dn Type=3
Dn Slope=0.005
Boundary for River Rch & Prof#=Twin Creek168,Reach-1,2
Up Type=0
Dn Type=3
Dn Slope=0.005
Boundary for River Rch & Prof#=Twin Creek168,Reach-1,3
Up Type=0
Dn Type=3
Dn Slope=0.005
Boundary for River Rch & Prof#=Twin Creek168,Reach-1,4
Up Type=0
Dn Type=3
Dn Slope=0.005
Boundary for River Rch & Prof#=Twin Creek168,Reach-1,5
Up Type=0
Dn Type=3
Dn Slope=0.005
Boundary for River Rch & Prof#=Twin Creek168,Reach-1,6
Up Type=0
Dn Type=3
Dn Slope=0.005
Boundary for River Rch & Prof#=Twin Creek168,Reach-1,7
Up Type=0
Dn Type=3
Dn Slope=0.005

--- Twin Creek168.g01 (geometry) ---

Geom Title=Existing Conditions

River Reach=Twin Creek168,Reach-1
Reach XY= 30
      2750076.00      6817611.00      2750076.45      6817733.91
      2750072.50      6817759.55      2750056.39      6817781.16
      2749945.37      6817891.00      2749934.00      6817907.67
      2749937.71      6817921.00      2749961.75      6817947.68
      2749967.84      6817957.69      2749968.00      6817964.36
      2749962.35      6817974.39      2749899.46      6818038.54
      2749879.44      6818053.18      2749866.14      6818049.61
      2749835.68      6818021.93      2749820.36      6818013.11
      2749790.06      6818011.15      2749777.65      6818014.16
      2749766.32      6818021.20      2749636.89      6818151.58
      2749628.69      6818167.43      2749624.85      6818194.96
      2749620.38      6818205.38      2749611.09      6818209.62
      2749582.02      6818213.80      2749570.24      6818219.27
      2749549.25      6818237.31      2749489.46      6818297.69
      2749477.67      6818317.13      2749476.00      6818361.00

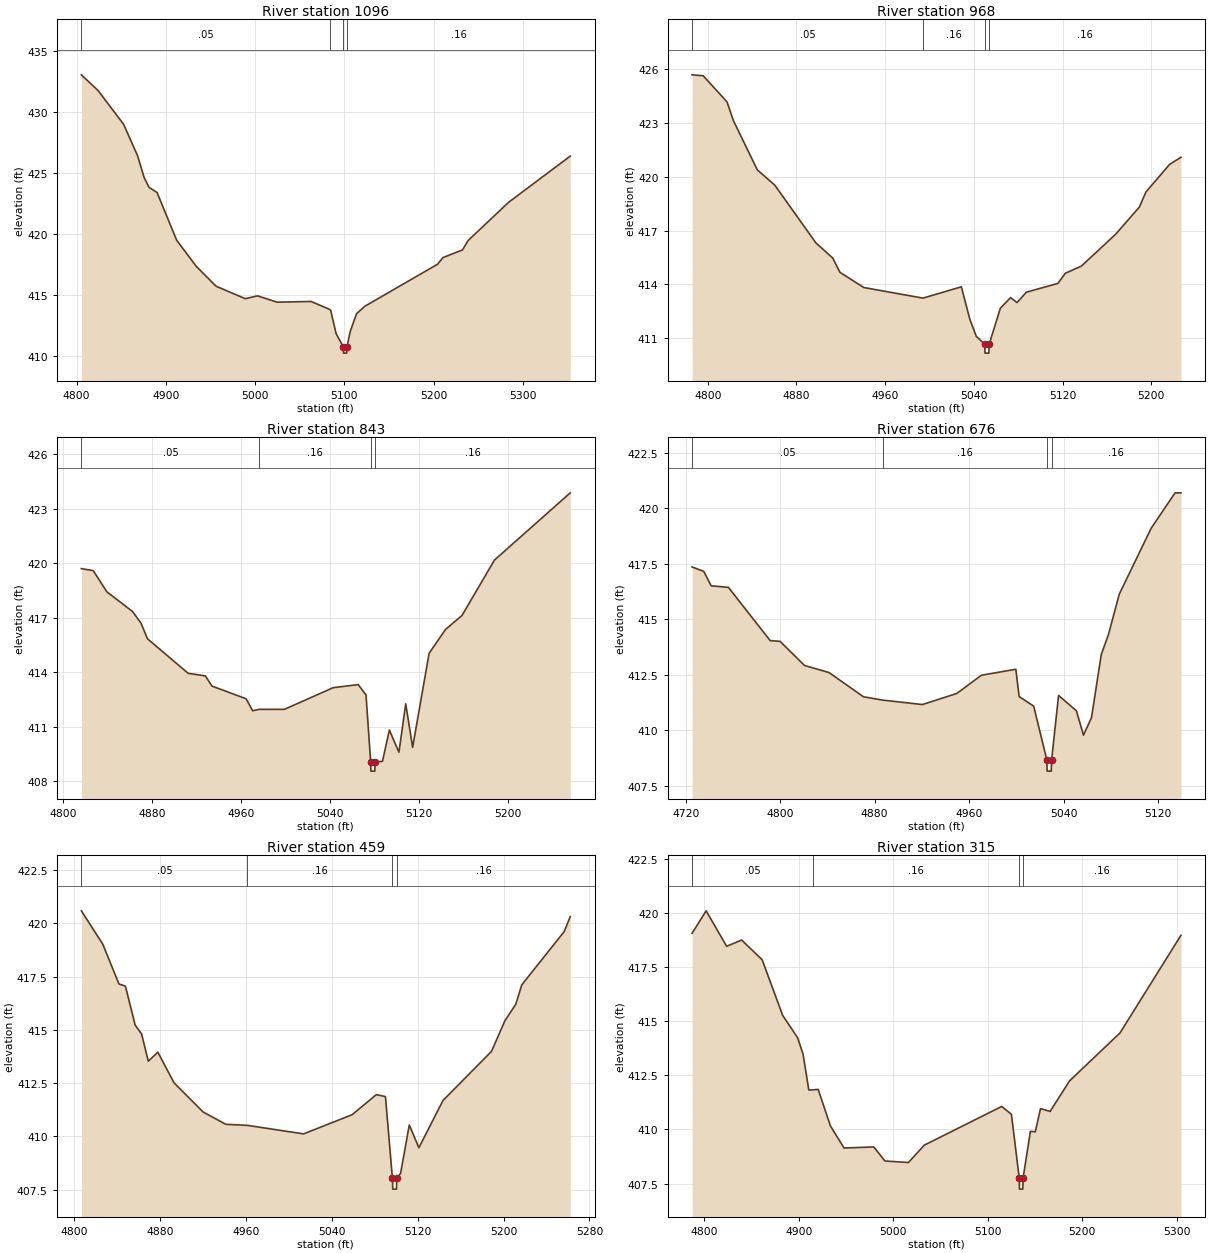
Type RM Length L Ch R = 1,1096,128,128,128
BEGIN DESCRIPTION:
Twin Creek1681096.22
END DESCRIPTION:
XS GIS Cut Line= 3
      2749898.64      6817586.30      2750076.14      6817666.06
      2750386.72      6817833.62
#Sta/Elev= 30
  4805.4  433.07  4824.0  431.79  4852.7  429.01  4868.3  426.44  4875.8  424.62
  4881.3  423.83  4890.2  423.41  4912.1  419.50  4934.1  417.35  4956.3  415.72
  4988.9  414.70  5002.8  414.93  5024.6  414.41  5062.7  414.47  5083.3  413.82
  5084.6  413.74  5090.7  411.83  5098.8  410.73  5099.0  410.23  5102.5  410.23
  5102.8  410.73  5106.5  412.01  5113.5  413.45  5122.7  414.07  5204.4  417.53
  5210.3  418.07  5232.2  418.70  5238.5  419.47  5283.9  422.61  5352.9  426.40
#Mann=4,-1,0
  4805.4    0.05       0  5083.3    0.16       0  5098.8    0.05       0
  5102.8    0.16       0
Bank Sta=5098.8,5102.8
Exp/Cntr=0.3,0.1

Type RM Length L Ch R = 1,968,125,125,125
BEGIN DESCRIPTION:
Twin Creek168968.15
END DESCRIPTION:
XS GIS Cut Line= 3
      2749866.29      6817678.74      2750049.33      6817784.90
      2750244.94      6817904.35
#Sta/Elev= 30
  4785.9  425.69  4795.9  425.64  4817.4  424.18  4823.2  423.13  4844.7  420.39
  4860.4  419.54  4897.7  416.30  4912.7  415.47  4919.2  414.67  4940.8  413.82
  4994.1  413.23  5028.7  413.86  5036.3  412.06  5042.2  411.09  5049.8  410.66
  5050.0  410.16  5053.5  410.16  5053.8  410.66  5063.9  412.67  5073.1  413.26
  5078.9  412.98  5087.3  413.56  5115.7  414.05  5122.5  414.62  5137.0  415.02
  5167.9  416.80  5189.2  418.31  5195.1  419.15  5216.4  420.69  5226.7  421.09
#Mann=4,-1,0
  4785.9    0.05       0  4994.1    0.16       0  5049.8    0.07       0
  5053.8    0.16       0
Bank Sta=5049.8,5053.8
Exp/Cntr=0.3,0.1

Type RM Length L Ch R = 1,843,167,167,167
BEGIN DESCRIPTION:
Twin Creek168843.44
END DESCRIPTION:
XS GIS Cut Line= 3
      2749806.93      6817776.88      2749962.66      6817873.73
      2750171.66      6818021.23
#Sta/Elev= 30
  4816.7  419.71  4827.4  419.60  4839.5  418.44  4862.7  417.35  4870.2  416.72
  4876.1  415.85  4912.7  413.95  4928.1  413.81  4934.0  413.25  4964.7  412.55
  4970.6  411.89  4976.6  411.97  4999.1  411.97  5042.9  413.16  5065.4  413.33
  5072.4  412.76  5076.6  409.07  5076.8  408.57  5080.3  408.57  5080.6  409.07
  5087.2  409.11  5093.4  410.83  5102.0  409.61  5108.1  412.27  5114.3  409.88
  5129.1  415.05  5143.9  416.37  5158.6  417.13  5187.8  420.18  5255.9  423.88
#Mann=4,-1,0
  4816.7    0.05       0  4976.6    0.16       0  5076.6    0.07       0
  5080.6    0.16       0
Bank Sta=5076.6,5080.6
Exp/Cntr=0.3,0.1

Type RM Length L Ch R = 1,676,217,217,217
BEGIN DESCRIPTION:
Twin Creek168675.6
END DESCRIPTION:
XS GIS Cut Line= 3
      2749713.59      6817839.61      2749935.55      6818007.29
      2750049.55      6818081.49
#Sta/Elev= 30
  4725.3  417.36  4735.2  417.16  4741.5  416.51  4756.1  416.44  4791.5  414.04
  4799.8  414.01  4820.6  412.92  4841.4  412.60  4870.5  411.51  4886.8  411.36
  4920.5  411.16  4949.6  411.66  4970.4  412.48  4999.6  412.75  5002.4  411.52
  5014.7  411.09  5025.9  408.66  5026.1  408.16  5029.6  408.16  5029.9  408.66
  5035.8  411.57  5050.9  410.88  5056.9  409.78  5063.7  410.57  5072.0  413.42
  5078.0  414.30  5087.2  416.13  5114.2  419.10  5134.5  420.70  5139.5  420.70
#Mann=4,-1,0
  4725.3    0.05       0  4886.8    0.16       0  5025.9    0.07       0
  5029.9    0.16       0
Bank Sta=5025.9,5029.9
Exp/Cntr=0.3,0.1

Type RM Length L Ch R = 1,459,144,144,144
BEGIN DESCRIPTION:
Twin Creek168458.57
END DESCRIPTION:
XS GIS Cut Line= 3
      2749593.85      6817925.44      2749758.51      6818033.33
      2749990.69      6818146.18
#Sta/Elev= 30
  4807.1  420.58  4827.0  419.02  4842.1  417.15  4848.1  417.05  4857.2  415.22
  4863.2  414.80  4869.4  413.53  4878.3  413.95  4893.4  412.51  4920.4  411.15
  4941.5  410.57  4961.7  410.52  5013.9  410.12  5059.1  411.02  5081.6  411.96
  5090.1  411.87  5096.6  408.03  5096.9  407.53  5100.4  407.53  5100.6  408.03
  5104.2  408.27  5112.3  410.54  5121.2  409.47  5143.7  411.69  5188.8  413.99
  5201.3  415.43  5211.4  416.20  5217.0  417.11  5256.5  419.61  5262.1  420.31
#Mann=4,-1,0
  4807.1    0.05       0  4961.7    0.16       0  5096.6    0.07       0
  5100.6    0.16       0
Bank Sta=5096.6,5100.6
Exp/Cntr=0.3,0.1

Type RM Length L Ch R = 1,315,239,239,239
BEGIN DESCRIPTION:
Twin Creek168315.15
END DESCRIPTION:
XS GIS Cut Line= 3
      2749468.29      6818028.52      2749653.21      6818132.54
      2749951.03      6818200.31
#Sta/Elev= 30
  4787.1  419.06  4802.0  420.10  4823.7  418.46  4839.6  418.75  4861.3  417.84
  4883.0  415.27  4898.9  414.23  4904.6  413.48  4910.7  411.82  4915.6  411.83
  4920.6  411.85  4933.6  410.16  4948.0  409.14  4979.5  409.19  4991.3  408.54
  5016.2  408.47  5032.9  409.27  5114.9  411.06  5125.2  410.70  5133.5  407.74
  5133.7  407.24  5137.2  407.24  5137.5  407.74  5145.3  409.91  5150.5  409.89
  5156.0  410.96  5166.2  410.83  5186.7  412.24  5240.2  414.46  5304.7  418.97
#Mann=4,-1,0
  4787.1    0.05       0  4915.6    0.16       0  5133.5    0.07       0
  5137.5    0.16       0
Bank Sta=5133.5,5137.5
Exp/Cntr=0.3,0.1

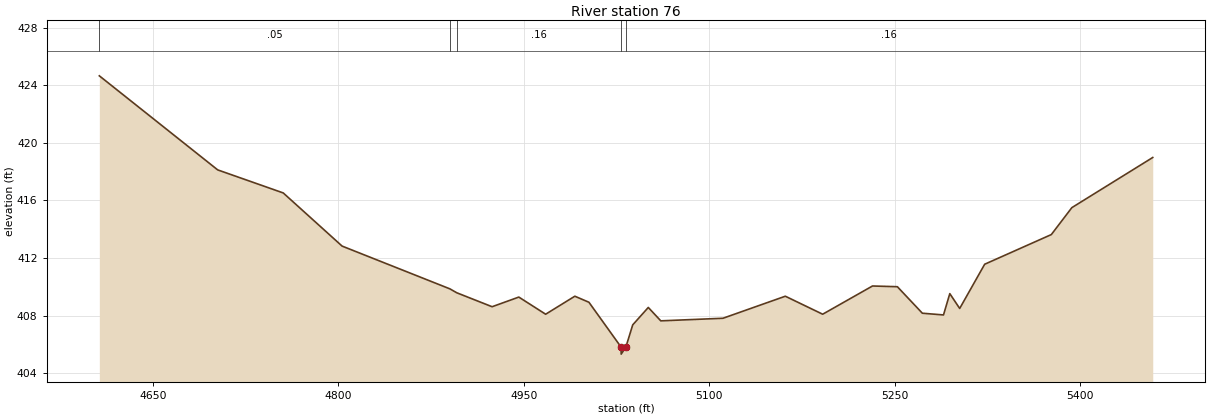
Type RM Length L Ch R = 1,76,0,0,0
BEGIN DESCRIPTION:
Twin Creek16876.277
END DESCRIPTION:
XS GIS Cut Line= 3
      2749343.88      6817928.07      2749495.76      6818290.86
      2749950.97      6818236.00
#Sta/Elev= 30
  4606.7  424.65  4702.4  418.12  4755.4  416.52  4803.0  412.83  4890.2  409.86
  4895.7  409.59  4924.3  408.62  4945.9  409.29  4967.6  408.10  4991.2  409.35
  5002.6  408.93  5028.5  405.83  5028.7  405.33  5032.5  405.83  5038.0  407.36
  5050.6  408.57  5060.7  407.64  5111.0  407.82  5161.4  409.35  5191.6  408.10
  5231.9  410.06  5252.0  410.01  5272.2  408.17  5289.3  408.05  5294.4  409.53
  5302.4  408.50  5322.6  411.57  5376.5  413.63  5393.1  415.50  5458.5  418.98
#Mann=5,-1,0
  4606.7    0.05       0  4890.2    0.12       0  4895.7    0.16       0
  5028.5    0.07       0  5032.5    0.16       0
Bank Sta=5028.5,5032.5
Exp/Cntr=0.3,0.1

Chan Stop Cuts=-1