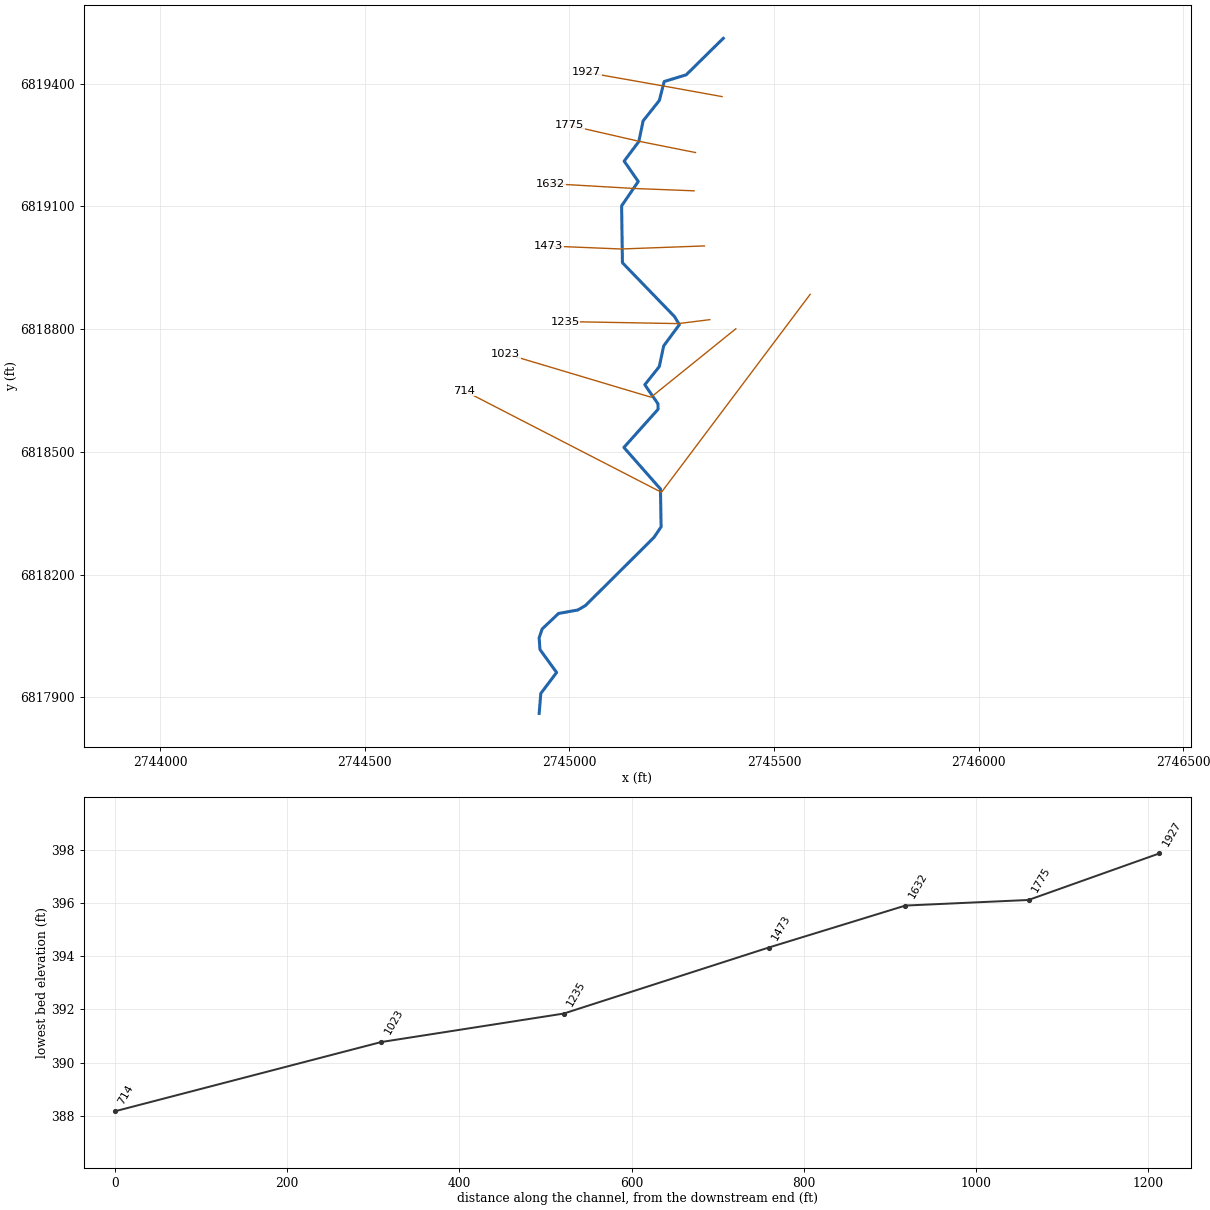
--- Twin Creek170.prj (project) ---

Proj Title=Twin Creek170 Base Level Engineering
Current Plan=p01
Default Exp/Contr=0.3,0.1
English Units
Geom File=g01
Flow File=f01
Plan File=p01
BEGIN DESCRIPTION:
Twin Creek170
END DESCRIPTION:

--- Twin Creek170.p01 (plan) ---

Plan Title=Multiple Run
Short Identifier=Multiple
Geom File=g01
Flow File=f01
Subcritical Flow
K Sum by GR= 0
Std Step Tol= 0.01
Critical Tol= 0.01
Num of Std Step Trials= 20
Max Error Tol= 0.3
Flow Tol Ratio= 0.001
Split Flow NTrial= 30
Split Flow Tol= 0.02
Split Flow Ratio= 0.02
Log Output Level= 0
Friction Slope Method= 1
Unsteady Friction Slope Method= 2
Unsteady Bridges Friction Slope Method= 1
Parabolic Critical Depth
Global Vel Dist=  1 , 1 , 1
Global Log Level= 0
CheckData=True
Encroach Param= -1, 0, 0, 0
BEGIN DESCRIPTION:
Multiple Run
END DESCRIPTION:

--- Twin Creek170.f01 (steady flow) ---

Flow Title=Multiple
Number of Profiles=7
Profile Names=10-year,25-year,50-year,1pct_min,100-year,1pct_plu,500-year
River Rch & RM= Twin Creek170,Reach-1,1927
     226     284     329     189     378     754     500
Boundary for River Rch & Prof#=Twin Creek170,Reach-1,1
Up Type=0
Dn Type=3
Dn Slope=0.005
Boundary for River Rch & Prof#=Twin Creek170,Reach-1,2
Up Type=0
Dn Type=3
Dn Slope=0.005
Boundary for River Rch & Prof#=Twin Creek170,Reach-1,3
Up Type=0
Dn Type=3
Dn Slope=0.005
Boundary for River Rch & Prof#=Twin Creek170,Reach-1,4
Up Type=0
Dn Type=3
Dn Slope=0.005
Boundary for River Rch & Prof#=Twin Creek170,Reach-1,5
Up Type=0
Dn Type=3
Dn Slope=0.005
Boundary for River Rch & Prof#=Twin Creek170,Reach-1,6
Up Type=0
Dn Type=3
Dn Slope=0.005
Boundary for River Rch & Prof#=Twin Creek170,Reach-1,7
Up Type=0
Dn Type=3
Dn Slope=0.005

--- Twin Creek170.g01 (geometry) ---

Geom Title=Existing Conditions

River Reach=Twin Creek170,Reach-1
Reach XY= 30
      2745376.00      6819511.00      2745285.42      6819421.83
      2745231.58      6819405.40      2745219.76      6819359.15
      2745180.12      6819309.29      2745169.62      6819258.70
      2745133.76      6819210.92      2745168.20      6819161.10
      2745127.53      6819101.41      2745129.53      6818962.47
      2745256.72      6818831.03      2745268.71      6818811.09
      2745230.40      6818759.35      2745219.65      6818708.71
      2745184.25      6818664.23      2745216.39      6818617.66
      2745216.67      6818604.33      2745133.11      6818511.01
      2745222.52      6818409.50      2745224.04      6818316.89
      2745206.42      6818290.85      2745039.20      6818124.64
      2745020.32      6818113.66      2744973.39      6818105.25
      2744933.38      6818067.33      2744925.96      6818045.77
      2744927.95      6818017.09      2744968.65      6817960.97
      2744930.00      6817909.64      2744926.00      6817861.00

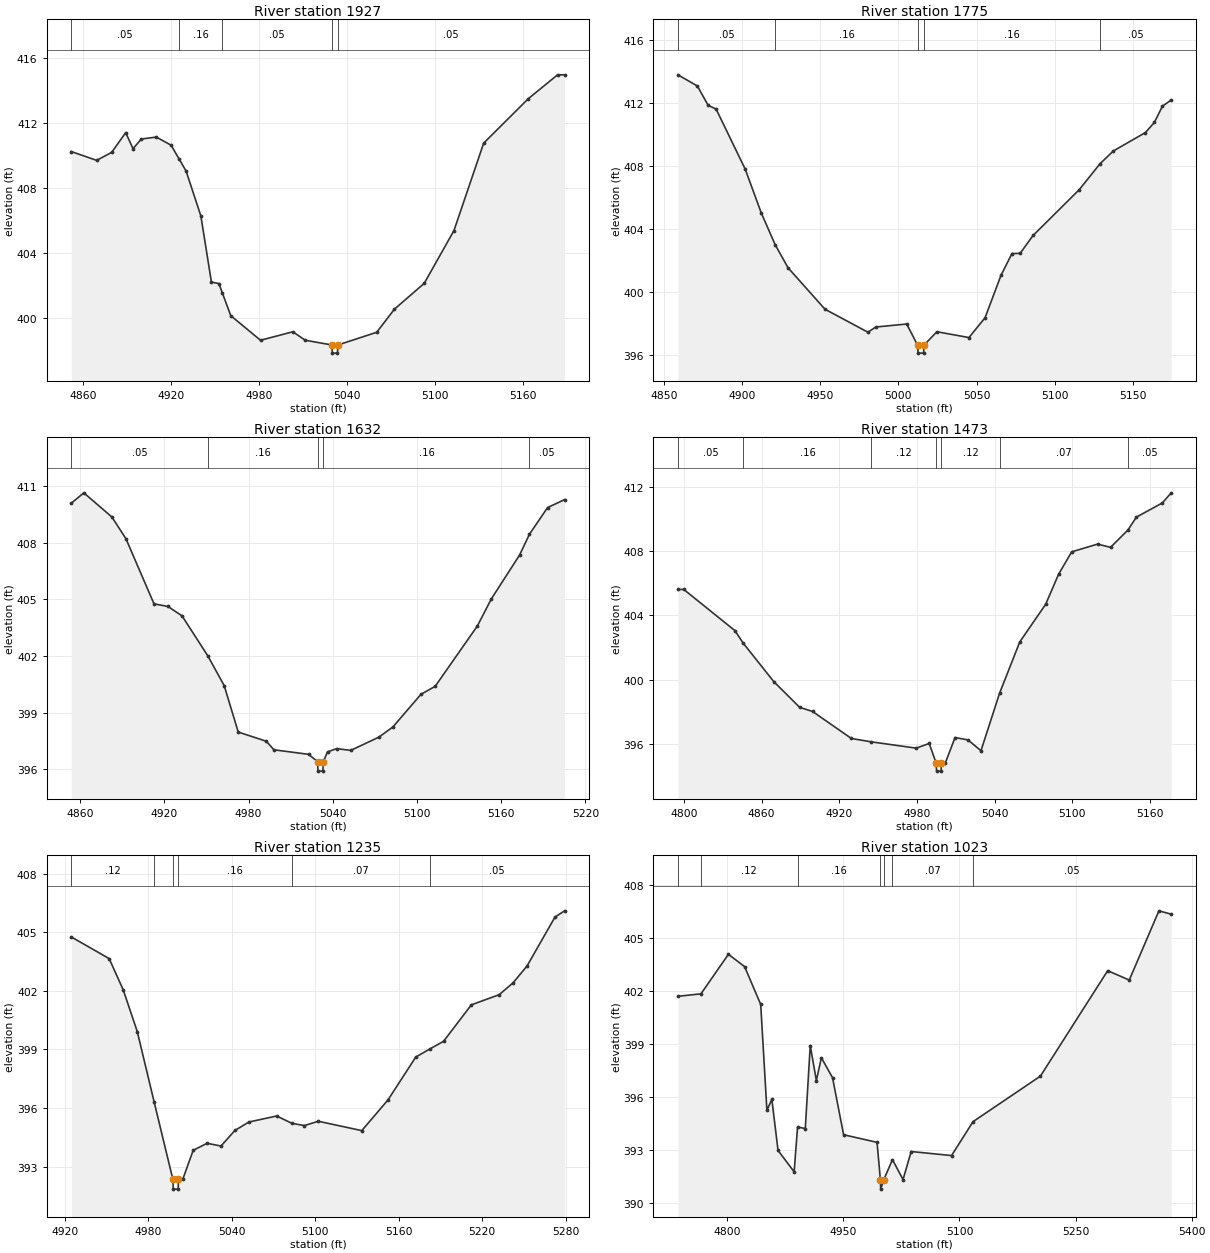
Type RM Length L Ch R = 1,1927,152,152,152
BEGIN DESCRIPTION:
Twin Creek1701927.089
END DESCRIPTION:
XS GIS Cut Line= 3
      2745373.03      6819368.60      2745227.09      6819394.99
      2745041.67      6819427.79
#Sta/Elev= 30
  4851.7  410.23  4869.0  409.69  4879.2  410.18  4888.8  411.39  4893.8  410.41
  4899.5  411.00  4909.7  411.12  4919.8  410.62  4925.2  409.78  4930.0  409.04
  4940.1  406.28  4947.3  402.22  4952.4  402.13  4954.7  401.57  4960.5  400.16
  4980.8  398.65  5002.9  399.17  5011.3  398.65  5029.6  398.36  5029.8  397.86
  5033.3  397.86  5033.6  398.36  5060.1  399.14  5072.2  400.56  5092.5  402.14
  5112.8  405.38  5133.1  410.75  5163.6  413.48  5183.5  414.94  5188.3  414.94
#Mann=5,-1,0
  4851.7    0.05       0  4925.2    0.16       0  4954.7    0.05       0
  5029.6    0.05       0  5033.6    0.05       0
Bank Sta=5029.6,5033.6
Exp/Cntr=0.3,0.1

Type RM Length L Ch R = 1,1775,143,143,143
BEGIN DESCRIPTION:
Twin Creek1701775.12
END DESCRIPTION:
XS GIS Cut Line= 3
      2745308.16      6819231.87      2745168.59      6819259.70
      2744999.96      6819298.27
#Sta/Elev= 30
  4859.1  413.80  4871.5  413.09  4878.4  411.86  4883.5  411.62  4902.1  407.80
  4912.3  405.03  4921.2  403.01  4929.5  401.53  4953.1  398.90  4980.5  397.44
  4985.6  397.77  5005.3  397.96  5012.3  396.61  5012.6  396.11  5016.1  396.11
  5016.3  396.61  5024.6  397.47  5045.1  397.10  5055.4  398.36  5065.6  401.06
  5072.6  402.44  5077.8  402.45  5086.1  403.59  5115.6  406.50  5128.9  408.15
  5137.4  408.96  5157.9  410.13  5163.6  410.77  5168.8  411.81  5174.4  412.20
#Mann=5,-1,0
  4859.1    0.05       0  4921.2    0.16       0  5012.3    0.07       0
  5016.3    0.16       0  5128.9    0.05       0
Bank Sta=5012.3,5016.3
Exp/Cntr=0.3,0.1

Type RM Length L Ch R = 1,1632,159,159,159
BEGIN DESCRIPTION:
Twin Creek1701632.22
END DESCRIPTION:
XS GIS Cut Line= 3
      2745304.86      6819138.28      2745160.33      6819143.90
      2744953.91      6819155.84
#Sta/Elev= 30
  4853.7  410.09  4862.6  410.64  4882.6  409.36  4892.6  408.21  4912.6  404.76
  4922.6  404.62  4932.6  404.12  4950.9  402.01  4962.6  400.43  4972.6  397.97
  4992.7  397.48  4998.0  397.03  5022.7  396.79  5029.2  396.40  5029.4  395.90
  5032.9  395.90  5033.2  396.40  5036.2  396.92  5042.7  397.09  5052.8  397.00
  5072.8  397.70  5082.8  398.24  5102.8  399.97  5112.9  400.39  5142.9  403.58
  5152.9  405.02  5173.0  407.34  5180.1  408.45  5193.0  409.86  5205.1  410.28
#Mann=5,-1,0
  4853.7    0.05       0  4950.9    0.16       0  5029.2    0.07       0
  5033.2    0.16       0  5180.1    0.05       0
Bank Sta=5029.2,5033.2
Exp/Cntr=0.3,0.1

Type RM Length L Ch R = 1,1473,238,238,238
BEGIN DESCRIPTION:
Twin Creek1701473.3
END DESCRIPTION:
XS GIS Cut Line= 3
      2745329.93      6819003.58      2745126.11      6818996.10
      2744949.12      6819003.43
#Sta/Elev= 30
  4795.4  405.62  4799.9  405.62  4839.4  403.06  4845.9  402.27  4869.4  399.89
  4889.4  398.29  4899.4  398.03  4929.4  396.35  4944.9  396.14  4979.5  395.75
  4989.5  396.04  4994.9  394.82  4995.2  394.32  4998.7  394.32  4998.9  394.82
  5001.9  394.82  5009.5  396.41  5019.5  396.26  5029.5  395.59  5043.9  399.17
  5059.5  402.36  5079.5  404.70  5089.5  406.57  5099.6  407.96  5119.6  408.44
  5129.6  408.24  5143.1  409.32  5149.6  410.12  5169.6  411.00  5176.5  411.63
#Mann=7,-1,0
  4795.4    0.05       0  4845.9    0.16       0  4944.9    0.12       0
  4994.9    0.07       0  4998.9    0.12       0  5043.9    0.07       0
  5143.1    0.05       0
Bank Sta=4994.9,4998.9
Exp/Cntr=0.3,0.1

Type RM Length L Ch R = 1,1235,212,212,212
BEGIN DESCRIPTION:
Twin Creek1701235.11
END DESCRIPTION:
XS GIS Cut Line= 3
      2745343.01      6818823.35      2745266.09      6818813.71
      2744989.05      6818818.68
#Sta/Elev= 30
  4924.7  404.77  4951.9  403.66  4962.0  402.06  4972.1  399.92  4984.3  396.29
  4997.7  392.34  4998.0  391.84  5001.5  391.84  5001.7  392.34  5004.8  392.34
  5012.3  393.83  5022.3  394.19  5032.3  394.05  5042.3  394.85  5052.3  395.28
  5072.3  395.59  5083.4  395.21  5092.3  395.10  5102.3  395.32  5133.5  394.84
  5152.3  396.41  5172.3  398.61  5182.5  399.03  5192.3  399.42  5212.3  401.29
  5232.3  401.81  5242.3  402.42  5252.3  403.28  5272.4  405.79  5279.3  406.11
#Mann=6,-1,0
  4924.7    0.12       0  4984.3    0.16       0  4997.7    0.07       0
  5001.7    0.16       0  5083.4    0.07       0  5182.5    0.05       0
Bank Sta=4997.7,5001.7
Exp/Cntr=0.3,0.1

Type RM Length L Ch R = 1,1023,309,309,309
BEGIN DESCRIPTION:
Twin Creek1701022.86
END DESCRIPTION:
XS GIS Cut Line= 3
      2745406.73      6818801.10      2745199.44      6818633.80
      2744844.06      6818740.03
#Sta/Elev= 30
  4736.3  401.69  4766.0  401.83  4801.5  404.07  4822.4  403.37  4843.2  401.23
  4851.2  395.24  4857.6  395.85  4865.6  392.96  4886.4  391.75  4890.8  394.29
  4900.8  394.20  4907.2  398.90  4915.1  396.92  4921.6  398.21  4936.0  397.08
  4950.3  393.85  4993.5  393.42  4997.9  391.27  4998.2  390.77  5001.9  391.27
  5013.4  392.44  5027.1  391.31  5037.6  392.90  5089.8  392.67  5117.5  394.59
  5204.6  397.17  5291.5  403.14  5319.4  402.61  5357.7  406.53  5373.6  406.34
#Mann=7,-1,0
  4736.3    0.05       0  4766.0    0.12       0  4890.8    0.16       0
  4997.9    0.07       0  5001.9    0.16       0  5013.4    0.07       0
  5117.5    0.05       0
Bank Sta=4997.9,5001.9
Exp/Cntr=0.3,0.1

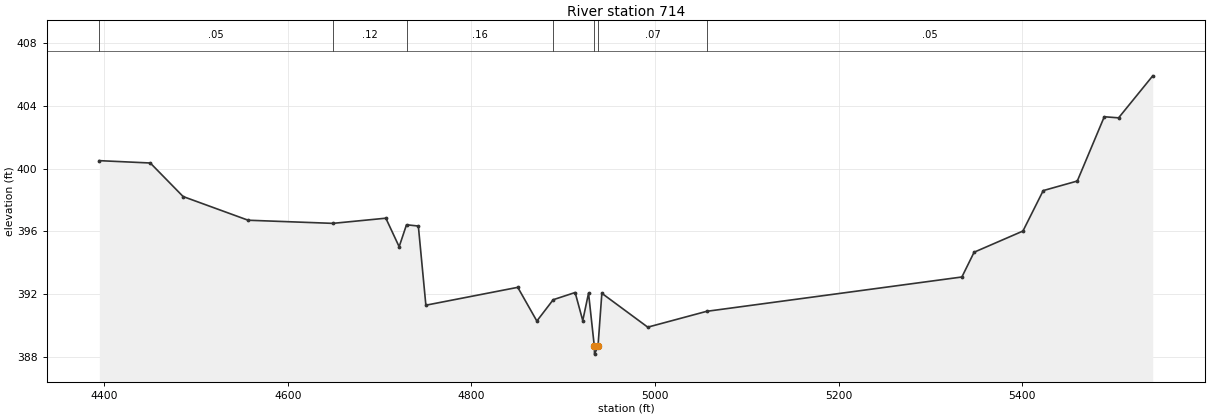
Type RM Length L Ch R = 1,714,0,0,0
BEGIN DESCRIPTION:
Twin Creek170714.211
END DESCRIPTION:
XS GIS Cut Line= 3
      2745588.52      6818885.39      2745224.90      6818401.36
      2744742.96      6818649.57
#Sta/Elev= 30
  4394.6  400.51  4450.1  400.36  4485.9  398.22  4556.7  396.71  4649.0  396.51
  4706.7  396.84  4721.2  395.02  4729.2  396.42  4742.1  396.34  4750.3  391.29
  4850.4  392.43  4871.2  390.28  4889.0  391.64  4912.9  392.10  4921.2  390.31
  4927.5  392.06  4933.8  388.67  4934.0  388.17  4937.8  388.67  4942.0  392.05
  4992.0  389.89  5056.2  390.90  5334.2  393.09  5347.5  394.67  5400.7  396.02
  5422.8  398.60  5459.9  399.21  5489.3  403.31  5504.9  403.24  5542.1  405.92
#Mann=7,-1,0
  4394.6    0.05       0  4649.0    0.12       0  4729.2    0.16       0
  4889.0    0.07       0  4933.8    0.07       0  4937.8    0.07       0
  5056.2    0.05       0
Bank Sta=4933.8,4937.8
Exp/Cntr=0.3,0.1

Chan Stop Cuts=-1