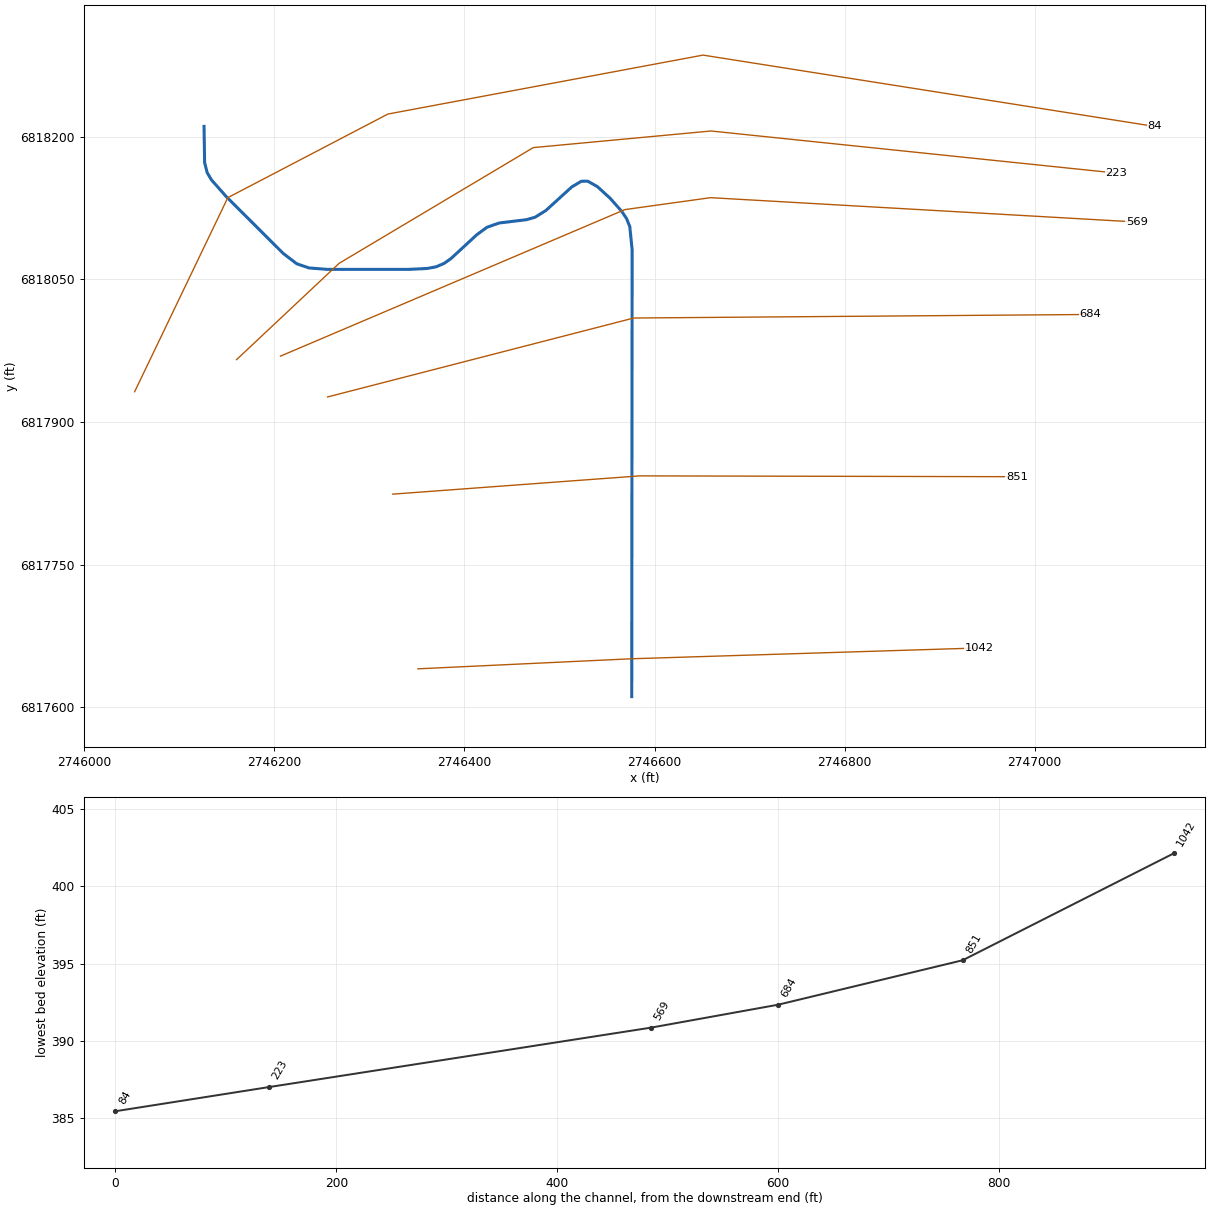
--- Twin Creek172.prj (project) ---

Proj Title=Twin Creek172 Base Level Engineering
Current Plan=p01
Default Exp/Contr=0.3,0.1
English Units
Geom File=g01
Flow File=f01
Plan File=p01
BEGIN DESCRIPTION:
Twin Creek172
END DESCRIPTION:

--- Twin Creek172.p01 (plan) ---

Plan Title=Multiple Run
Short Identifier=Multiple
Geom File=g01
Flow File=f01
Subcritical Flow
K Sum by GR= 0
Std Step Tol= 0.01
Critical Tol= 0.01
Num of Std Step Trials= 20
Max Error Tol= 0.3
Flow Tol Ratio= 0.001
Split Flow NTrial= 30
Split Flow Tol= 0.02
Split Flow Ratio= 0.02
Log Output Level= 0
Friction Slope Method= 1
Unsteady Friction Slope Method= 2
Unsteady Bridges Friction Slope Method= 1
Parabolic Critical Depth
Global Vel Dist=  1 , 1 , 1
Global Log Level= 0
CheckData=True
Encroach Param= -1, 0, 0, 0
BEGIN DESCRIPTION:
Multiple Run
END DESCRIPTION:

--- Twin Creek172.f01 (steady flow) ---

Flow Title=Multiple
Number of Profiles=7
Profile Names=10-year,25-year,50-year,1pct_min,100-year,1pct_plu,500-year
River Rch & RM= Twin Creek172,Reach-1,1042
     134     164     187     106     212     423     274
Boundary for River Rch & Prof#=Twin Creek172,Reach-1,1
Up Type=0
Dn Type=3
Dn Slope=0.005
Boundary for River Rch & Prof#=Twin Creek172,Reach-1,2
Up Type=0
Dn Type=3
Dn Slope=0.005
Boundary for River Rch & Prof#=Twin Creek172,Reach-1,3
Up Type=0
Dn Type=3
Dn Slope=0.005
Boundary for River Rch & Prof#=Twin Creek172,Reach-1,4
Up Type=0
Dn Type=3
Dn Slope=0.005
Boundary for River Rch & Prof#=Twin Creek172,Reach-1,5
Up Type=0
Dn Type=3
Dn Slope=0.005
Boundary for River Rch & Prof#=Twin Creek172,Reach-1,6
Up Type=0
Dn Type=3
Dn Slope=0.005
Boundary for River Rch & Prof#=Twin Creek172,Reach-1,7
Up Type=0
Dn Type=3
Dn Slope=0.005

--- Twin Creek172.g01 (geometry) ---

Geom Title=Existing Conditions

River Reach=Twin Creek172,Reach-1
Reach XY= 30
      2746576.00      6817611.00      2746576.43      6818081.33
      2746573.95      6818105.55      2746570.55      6818114.01
      2746565.53      6818121.54      2746553.16      6818135.48
      2746539.80      6818147.66      2746529.70      6818153.35
      2746522.98      6818153.25      2746512.93      6818147.29
      2746485.71      6818122.53      2746474.38      6818115.44
      2746465.39      6818112.84      2746436.71      6818109.38
      2746423.83      6818104.91      2746412.97      6818096.97
      2746385.67      6818071.79      2746378.35      6818066.70
      2746370.07      6818063.23      2746360.78      6818061.49
      2746341.16      6818060.52      2746255.83      6818060.53
      2746236.43      6818062.03      2746223.53      6818066.44
      2746209.20      6818077.40      2746149.01      6818137.48
      2746133.75      6818154.76      2746129.27      6818162.34
      2746126.59      6818172.83      2746126.00      6818211.00

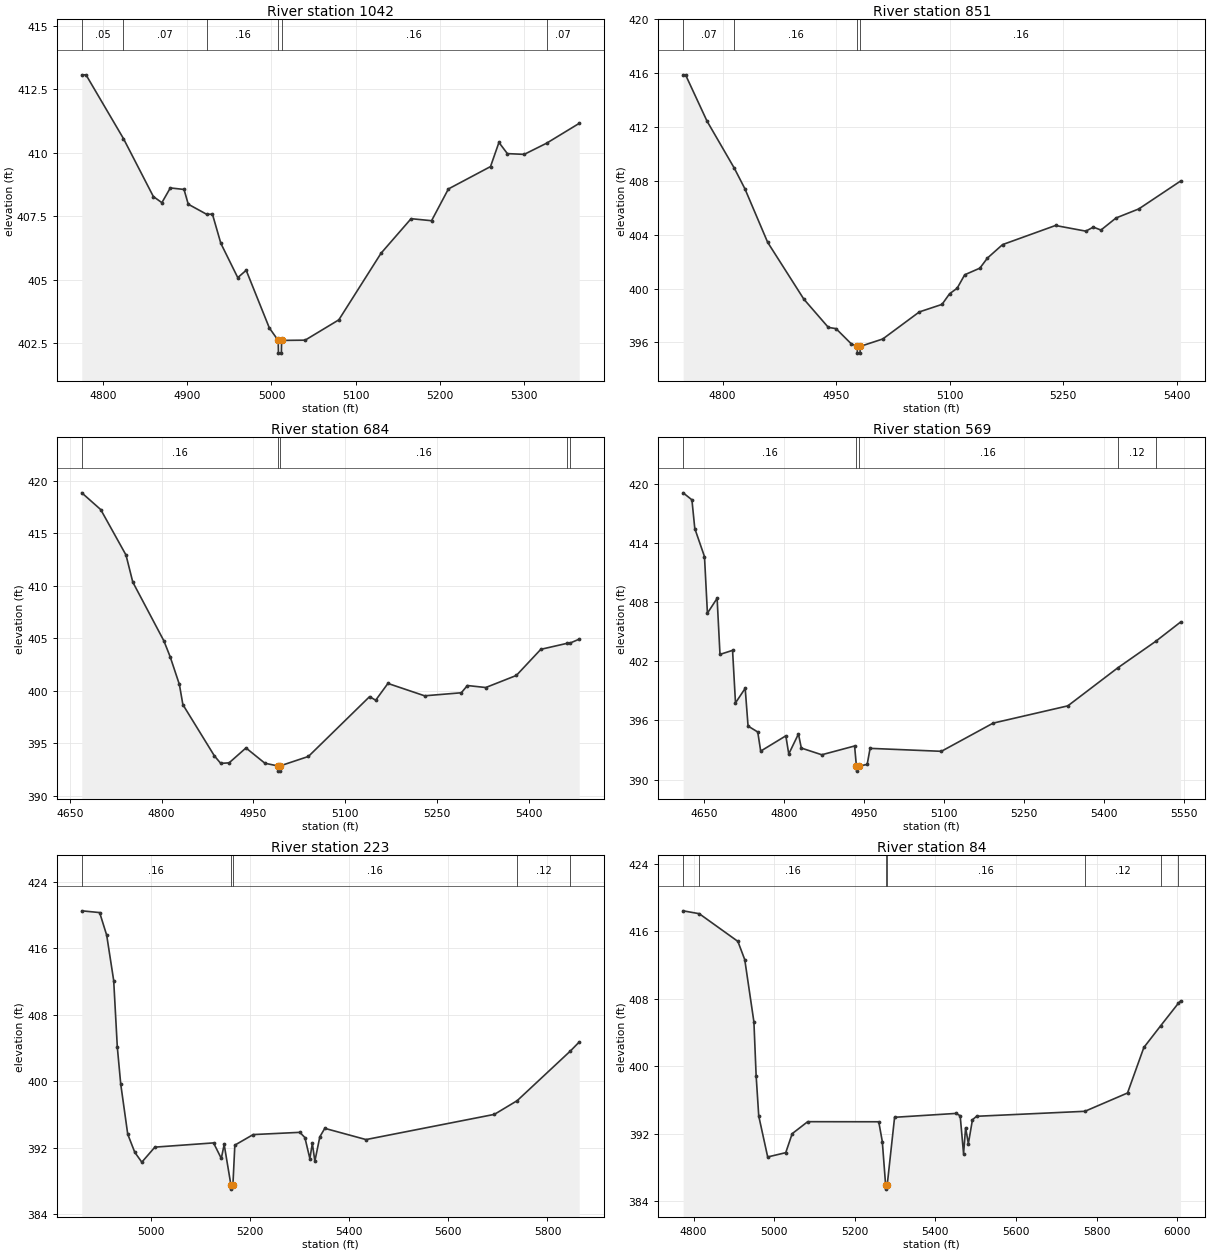
Type RM Length L Ch R = 1,1042,191,191,191
BEGIN DESCRIPTION:
Twin Creek1721042.453
END DESCRIPTION:
XS GIS Cut Line= 3
      2746351.05      6817640.24      2746576.00      6817650.82
      2746941.23      6817662.19
#Sta/Elev= 30
  4774.8  413.06  4779.8  413.06  4824.3  410.55  4859.8  408.27  4869.9  408.03
  4879.9  408.61  4896.2  408.55  4901.2  407.97  4923.2  407.57  4929.9  407.58
  4939.9  406.43  4960.0  405.08  4970.0  405.37  4997.5  403.10  5008.0  402.61
  5008.3  402.11  5011.8  402.11  5012.0  402.61  5040.0  402.62  5080.0  403.42
  5130.1  406.04  5165.8  407.40  5190.1  407.32  5210.1  408.57  5260.1  409.45
  5270.1  410.40  5280.1  409.96  5300.1  409.93  5326.7  410.37  5365.4  411.15
#Mann=6,-1,0
  4774.8    0.05       0  4824.3    0.07       0  4923.2    0.16       0
  5008.0    0.07       0  5012.0    0.16       0  5326.7    0.07       0
Bank Sta=5008,5012
Exp/Cntr=0.3,0.1

Type RM Length L Ch R = 1,851,167,167,167
BEGIN DESCRIPTION:
Twin Creek172850.63
END DESCRIPTION:
XS GIS Cut Line= 3
      2746324.60      6817824.04      2746584.36      6817843.26
      2746981.19      6817842.39
#Sta/Elev= 30
  4747.9  415.88  4751.1  415.88  4779.4  412.45  4815.7  408.93  4829.5  407.42
  4859.6  403.44  4907.4  399.22  4939.8  397.12  4949.9  397.03  4969.9  395.91
  4977.9  395.71  4978.2  395.21  4981.7  395.21  4981.9  395.71  5011.7  396.26
  5060.0  398.27  5090.0  398.83  5100.0  399.62  5110.0  400.03  5120.0  401.03
  5140.0  401.52  5150.0  402.27  5170.0  403.27  5240.0  404.69  5280.0  404.27
  5290.0  404.57  5300.0  404.35  5320.0  405.25  5350.0  405.92  5405.2  407.99
#Mann=4,-1,0
  4747.9    0.07       0  4815.7    0.16       0  4977.9    0.07       0
  4981.9    0.16       0
Bank Sta=4977.9,4981.9
Exp/Cntr=0.3,0.1

Type RM Length L Ch R = 1,684,115,115,115
BEGIN DESCRIPTION:
Twin Creek172684.44
END DESCRIPTION:
XS GIS Cut Line= 3
      2746255.97      6817926.29      2746578.17      6818009.36
      2747058.82      6818013.10
#Sta/Elev= 30
  4669.4  418.87  4700.4  417.27  4741.7  412.94  4752.8  410.36  4803.7  404.75
  4814.0  403.23  4829.0  400.60  4834.7  398.68  4886.3  393.79  4896.6  393.08
  4910.3  393.13  4937.9  394.55  4968.9  393.09  4989.7  392.84  4990.0  392.34
  4993.5  392.34  4993.7  392.84  5040.0  393.74  5140.0  399.44  5150.0  399.10
  5170.0  400.70  5230.0  399.52  5290.0  399.81  5300.0  400.50  5330.0  400.31
  5380.0  401.46  5420.0  403.95  5463.5  404.53  5468.3  404.56  5482.8  404.92
#Mann=5,-1,0
  4669.4    0.16       0  4989.7    0.07       0  4993.7    0.16       0
  5463.5    0.12       0  5468.3    0.16       0
Bank Sta=4989.7,4993.7
Exp/Cntr=0.3,0.1

Type RM Length L Ch R = 1,569,346,346,346
BEGIN DESCRIPTION:
Twin Creek172568.87
END DESCRIPTION:
XS GIS Cut Line= 4
      2746206.45      6817969.27      2746568.82      6818123.44
      2746658.93      6818135.99      2747107.22      6818110.38
#Sta/Elev= 30
  4610.1  419.09  4626.6  418.38  4632.0  415.47  4650.2  412.62  4655.7  406.88
  4673.9  408.39  4679.3  402.70  4702.9  403.11  4708.4  397.78  4726.6  399.26
  4732.0  395.43  4750.2  394.83  4755.7  392.89  4802.9  394.44  4808.4  392.60
  4826.6  394.63  4832.0  393.20  4870.4  392.52  4932.0  393.41  4935.4  391.36
  4935.7  390.86  4939.4  391.36  4955.6  391.54  4961.1  393.17  5094.9  392.87
  5192.1  395.73  5332.3  397.48  5425.9  401.33  5496.9  404.01  5543.9  405.98
#Mann=5,-1,0
  4610.1    0.16       0  4935.4    0.07       0  4939.4    0.16       0
  5425.9    0.12       0  5496.9    0.16       0
Bank Sta=4935.4,4939.4
Exp/Cntr=0.3,0.1

Type RM Length L Ch R = 1,223,139,139,139
BEGIN DESCRIPTION:
Twin Creek172222.7
END DESCRIPTION:
XS GIS Cut Line= 5
      2746160.25      6817965.59      2746268.06      6818066.87
      2746472.43      6818188.67      2746659.45      6818206.14
      2747086.09      6818161.83
#Sta/Elev= 30
  4861.4  420.49  4897.4  420.28  4911.6  417.56  4925.7  412.11  4933.0  404.11
  4939.9  399.65  4954.0  393.63  4968.2  391.45  4982.4  390.26  5008.7  392.07
  5127.0  392.58  5142.6  390.71  5148.4  392.39  5162.0  387.52  5162.2  387.02
  5166.0  387.52  5169.9  392.31  5206.8  393.58  5301.0  393.85  5311.1  393.22
  5321.1  390.69  5326.1  392.52  5331.2  390.39  5341.2  393.31  5351.2  394.33
  5434.3  392.98  5693.0  396.01  5739.0  397.66  5846.2  403.63  5864.0  404.71
#Mann=5,-1,0
  4861.4    0.16       0  5162.0    0.07       0  5166.0    0.16       0
  5739.0    0.12       0  5846.2    0.16       0
Bank Sta=5162,5166
Exp/Cntr=0.3,0.1

Type RM Length L Ch R = 1,84,0,0,0
BEGIN DESCRIPTION:
Twin Creek17283.549
END DESCRIPTION:
XS GIS Cut Line= 5
      2746052.98      6817931.82      2746151.00      6818136.00
      2746319.42      6818223.96      2746651.00      6818286.00
      2747125.99      6818211.00
#Sta/Elev= 30
  4773.9  418.43  4813.9  418.09  4909.8  414.81  4926.9  412.64  4949.6  405.27
  4955.1  398.91  4961.6  394.12  4983.8  389.27  5028.6  389.78  5044.6  392.03
  5083.1  393.45  5259.5  393.44  5268.3  391.10  5276.5  385.96  5276.7  385.46
  5280.5  385.96  5298.8  393.97  5451.4  394.43  5461.6  394.15  5470.0  389.66
  5475.1  392.74  5481.9  390.85  5492.1  393.68  5502.3  394.09  5771.2  394.68
  5877.0  396.85  5917.5  402.24  5959.2  404.81  6003.5  407.50  6008.6  407.75
#Mann=7,-1,0
  4773.9    0.07       0  4813.9    0.16       0  5276.5    0.07       0
  5280.5    0.16       0  5771.2    0.12       0  5959.2    0.16       0
  6003.5    0.07       0
Bank Sta=5276.5,5280.5
Exp/Cntr=0.3,0.1

Chan Stop Cuts=-1