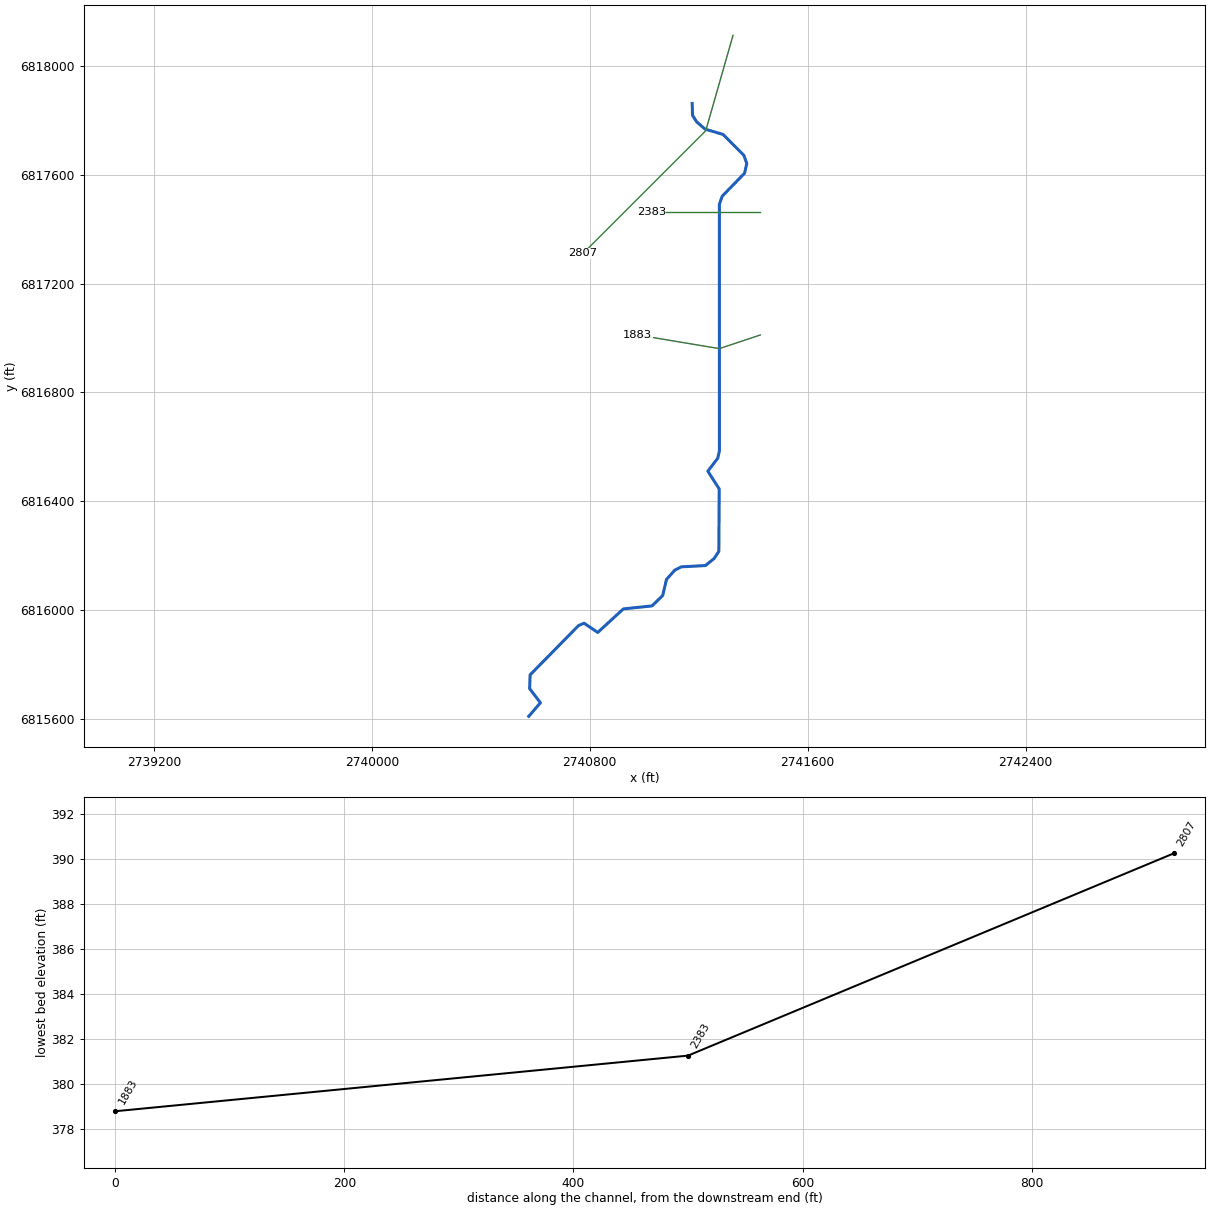
--- Twin Creek174.prj (project) ---

Proj Title=Twin Creek174 Base Level Engineering
Current Plan=p01
Default Exp/Contr=0.3,0.1
English Units
Geom File=g01
Flow File=f01
Plan File=p01
BEGIN DESCRIPTION:
Twin Creek174
END DESCRIPTION:

--- Twin Creek174.p01 (plan) ---

Plan Title=Multiple Run
Short Identifier=Multiple
Geom File=g01
Flow File=f01
Subcritical Flow
K Sum by GR= 0
Std Step Tol= 0.01
Critical Tol= 0.01
Num of Std Step Trials= 20
Max Error Tol= 0.3
Flow Tol Ratio= 0.001
Split Flow NTrial= 30
Split Flow Tol= 0.02
Split Flow Ratio= 0.02
Log Output Level= 0
Friction Slope Method= 1
Unsteady Friction Slope Method= 2
Unsteady Bridges Friction Slope Method= 1
Parabolic Critical Depth
Global Vel Dist=  1 , 1 , 1
Global Log Level= 0
CheckData=True
Encroach Param= -1, 0, 0, 0
BEGIN DESCRIPTION:
Multiple Run
END DESCRIPTION:

--- Twin Creek174.f01 (steady flow) ---

Flow Title=Multiple
Number of Profiles=7
Profile Names=10-year,25-year,50-year,1pct_min,100-year,1pct_plu,500-year
River Rch & RM= Twin Creek174,Reach-1,2807
     233     293     338     195     388     775     512
Boundary for River Rch & Prof#=Twin Creek174,Reach-1,1
Up Type=0
Dn Type=3
Dn Slope=0.005
Boundary for River Rch & Prof#=Twin Creek174,Reach-1,2
Up Type=0
Dn Type=3
Dn Slope=0.005
Boundary for River Rch & Prof#=Twin Creek174,Reach-1,3
Up Type=0
Dn Type=3
Dn Slope=0.005
Boundary for River Rch & Prof#=Twin Creek174,Reach-1,4
Up Type=0
Dn Type=3
Dn Slope=0.005
Boundary for River Rch & Prof#=Twin Creek174,Reach-1,5
Up Type=0
Dn Type=3
Dn Slope=0.005
Boundary for River Rch & Prof#=Twin Creek174,Reach-1,6
Up Type=0
Dn Type=3
Dn Slope=0.005
Boundary for River Rch & Prof#=Twin Creek174,Reach-1,7
Up Type=0
Dn Type=3
Dn Slope=0.005

--- Twin Creek174.g01 (geometry) ---

Geom Title=Existing Conditions

River Reach=Twin Creek174,Reach-1
Reach XY= 30
      2741176.00      6817861.00      2741177.56      6817816.87
      2741192.36      6817793.77      2741223.49      6817766.71
      2741289.24      6817747.39      2741365.84      6817670.70
      2741376.47      6817640.84      2741368.52      6817604.96
      2741286.50      6817520.79      2741275.96      6817491.02
      2741276.11      6816585.88      2741269.98      6816558.55
      2741233.56      6816511.00      2741275.34      6816445.84
      2741274.03      6816216.65      2741256.60      6816190.35
      2741224.75      6816164.51      2741136.34      6816159.89
      2741112.35      6816147.74      2741081.75      6816113.55
      2741067.97      6816054.65      2741028.67      6816016.42
      2740923.58      6816005.45      2740829.33      6815919.02
      2740779.33      6815952.84      2740759.33      6815944.61
      2740581.10      6815763.29      2740579.43      6815712.64
      2740619.05      6815660.88      2740576.00      6815611.00

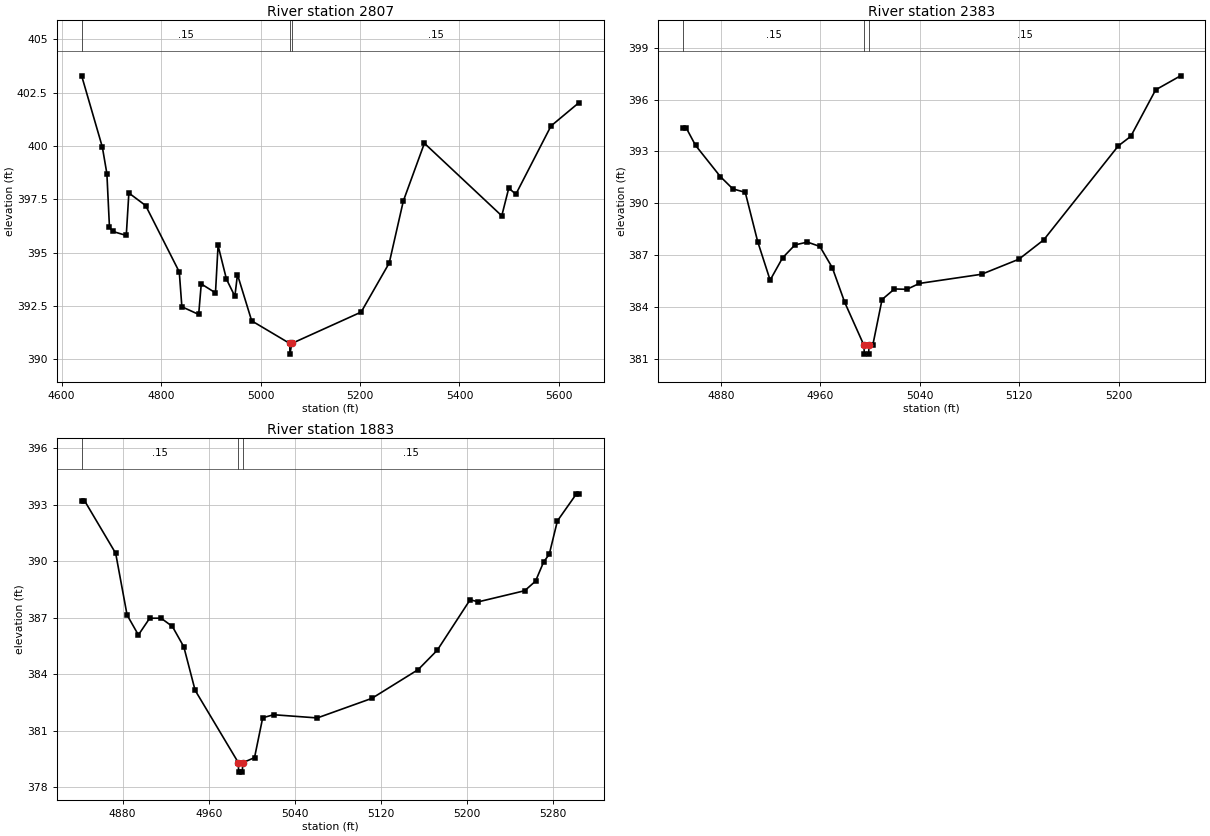
Type RM Length L Ch R = 1,2807,424,424,424
BEGIN DESCRIPTION:
Twin Creek174 3.0
END DESCRIPTION:
XS GIS Cut Line= 3
      2741325.99      6818110.97      2741226.00      6817761.00
      2740775.98      6817310.98
#Sta/Elev= 30
  4640.2  403.29  4681.8  399.95  4690.9  398.71  4696.1  396.20  4702.6  396.00
  4729.9  395.81  4735.1  397.80  4768.9  397.21  4836.5  394.10  4841.7  392.47
  4875.5  392.11  4880.7  393.54  4909.3  393.12  4914.5  395.34  4931.4  393.76
  4948.3  392.96  4953.5  393.98  4982.1  391.81  5058.7  390.75  5059.0  390.25
  5062.7  390.75  5202.2  392.22  5258.7  394.52  5287.0  397.42  5329.4  400.13
  5485.0  396.73  5499.1  398.03  5513.3  397.74  5584.0  400.94  5640.6  402.04
#Mann=3,-1,0
  4640.2    0.15       0  5058.7    0.05       0  5062.7    0.15       0
Bank Sta=5058.7,5062.7
Exp/Cntr=0.3,0.1

Type RM Length L Ch R = 1,2383,500,500,500
BEGIN DESCRIPTION:
Twin Creek174 2.0
END DESCRIPTION:
XS GIS Cut Line= 3
      2741425.98      6817461.00      2741276.00      6817461.00
      2741025.98      6817461.00
#Sta/Elev= 30
  4849.6  394.36  4852.1  394.36  4859.6  393.35  4879.6  391.54  4889.6  390.83
  4899.6  390.63  4909.6  387.78  4919.6  385.55  4929.6  386.84  4939.6  387.59
  4949.6  387.75  4959.6  387.50  4969.6  386.27  4979.6  384.26  4995.1  381.77
  4995.3  381.27  4998.8  381.27  4999.1  381.77  5002.1  381.77  5009.6  384.43
  5019.6  385.04  5029.6  385.02  5039.6  385.36  5089.6  385.89  5119.6  386.76
  5139.6  387.88  5199.6  393.32  5209.6  393.87  5229.6  396.56  5249.6  397.37
#Mann=3,-1,0
  4849.6    0.15       0  4995.1    0.05       0  4999.1    0.15       0
Bank Sta=4995.1,4999.1
Exp/Cntr=0.3,0.1

Type RM Length L Ch R = 1,1883,0,0,0
BEGIN DESCRIPTION:
Twin Creek174 1.0
END DESCRIPTION:
XS GIS Cut Line= 3
      2741425.99      6817011.00      2741276.00      6816961.00
      2740976.04      6817010.99
#Sta/Elev= 30
  4841.9  393.23  4844.5  393.23  4873.5  390.43  4884.1  387.15  4894.6  386.09
  4905.1  386.98  4915.7  386.98  4926.2  386.54  4936.8  385.46  4947.3  383.15
  4987.5  379.30  4987.7  378.80  4991.2  378.80  4991.5  379.30  5002.5  379.57
  5010.1  381.69  5020.3  381.85  5060.8  381.68  5111.5  382.72  5154.6  384.25
  5172.3  385.28  5202.8  387.96  5210.4  387.85  5253.5  388.44  5263.6  388.95
  5271.2  389.98  5276.3  390.37  5283.9  392.15  5301.6  393.59  5304.1  393.59
#Mann=3,-1,0
  4841.9    0.15       0  4987.5    0.05       0  4991.5    0.15       0
Bank Sta=4987.5,4991.5
Exp/Cntr=0.3,0.1

Chan Stop Cuts=-1