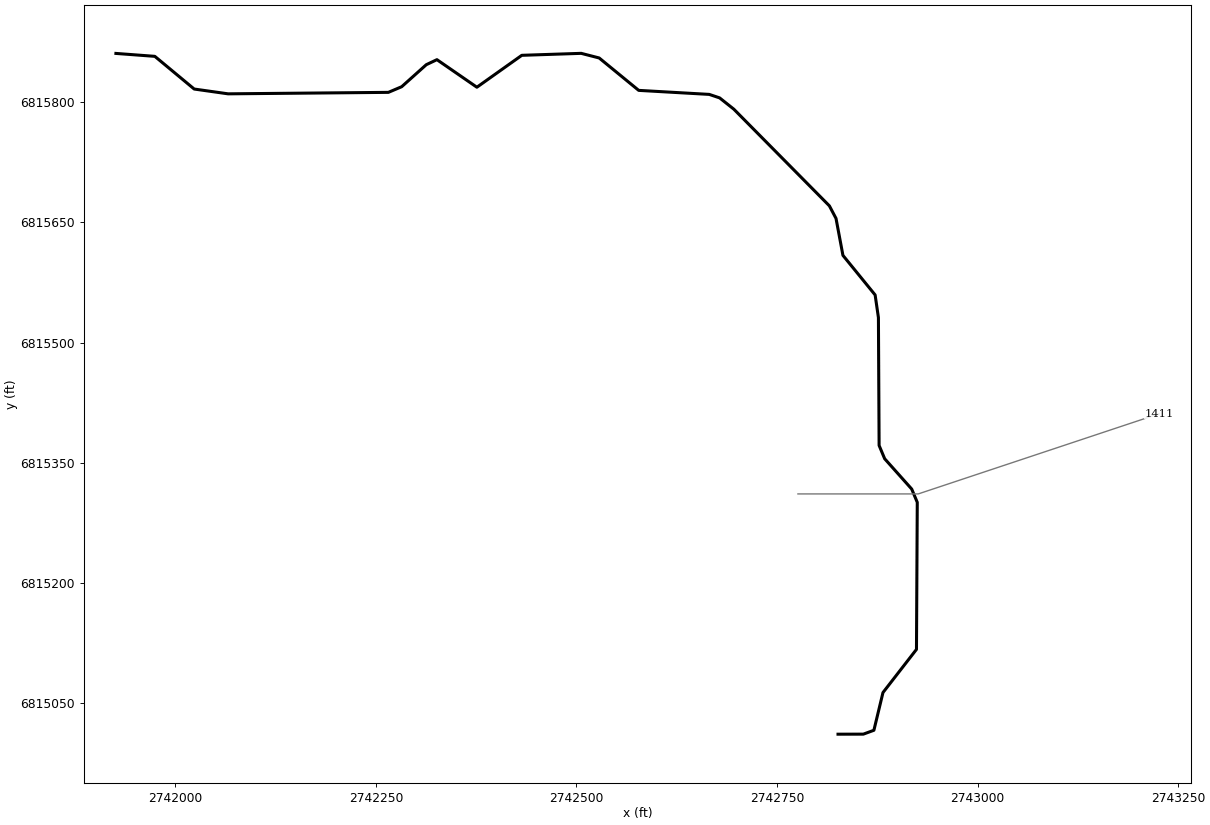
--- Twin Creek176.prj (project) ---

Proj Title=Twin Creek176 Base Level Engineering
Current Plan=p01
Default Exp/Contr=0.3,0.1
English Units
Geom File=g01
Flow File=f01
Plan File=p01
BEGIN DESCRIPTION:
Twin Creek176
END DESCRIPTION:

--- Twin Creek176.p01 (plan) ---

Plan Title=Multiple Run
Short Identifier=Multiple
Geom File=g01
Flow File=f01
Subcritical Flow
K Sum by GR= 0
Std Step Tol= 0.01
Critical Tol= 0.01
Num of Std Step Trials= 20
Max Error Tol= 0.3
Flow Tol Ratio= 0.001
Split Flow NTrial= 30
Split Flow Tol= 0.02
Split Flow Ratio= 0.02
Log Output Level= 0
Friction Slope Method= 1
Unsteady Friction Slope Method= 2
Unsteady Bridges Friction Slope Method= 1
Parabolic Critical Depth
Global Vel Dist=  1 , 1 , 1
Global Log Level= 0
CheckData=True
Encroach Param= -1, 0, 0, 0
BEGIN DESCRIPTION:
Multiple Run
END DESCRIPTION:

--- Twin Creek176.f01 (steady flow) ---

Flow Title=Multiple
Number of Profiles=7
Profile Names=10-year,25-year,50-year,1pct_min,100-year,1pct_plu,500-year
River Rch & RM= Twin Creek176,Reach-1,1411
     164     204     234     135     269     537     354
Boundary for River Rch & Prof#=Twin Creek176,Reach-1,1
Up Type=0
Dn Type=3
Dn Slope=0.005
Boundary for River Rch & Prof#=Twin Creek176,Reach-1,2
Up Type=0
Dn Type=3
Dn Slope=0.005
Boundary for River Rch & Prof#=Twin Creek176,Reach-1,3
Up Type=0
Dn Type=3
Dn Slope=0.005
Boundary for River Rch & Prof#=Twin Creek176,Reach-1,4
Up Type=0
Dn Type=3
Dn Slope=0.005
Boundary for River Rch & Prof#=Twin Creek176,Reach-1,5
Up Type=0
Dn Type=3
Dn Slope=0.005
Boundary for River Rch & Prof#=Twin Creek176,Reach-1,6
Up Type=0
Dn Type=3
Dn Slope=0.005
Boundary for River Rch & Prof#=Twin Creek176,Reach-1,7
Up Type=0
Dn Type=3
Dn Slope=0.005

--- Twin Creek176.g01 (geometry) ---

Geom Title=Existing Conditions

River Reach=Twin Creek176,Reach-1
Reach XY= 30
      2742826.00      6815011.00      2742857.56      6815011.06
      2742870.72      6815015.90      2742882.04      6815063.00
      2742923.79      6815116.90      2742924.78      6815300.49
      2742917.86      6815317.06      2742884.14      6815354.94
      2742877.22      6815371.51      2742876.36      6815531.15
      2742872.25      6815559.45      2742832.14      6815608.83
      2742823.51      6815654.97      2742815.24      6815670.68
      2742696.16      6815791.37      2742678.43      6815805.48
      2742665.52      6815809.84      2742577.60      6815814.86
      2742528.31      6815855.32      2742505.90      6815861.09
      2742431.89      6815858.64      2742375.90      6815818.80
      2742326.10      6815853.21      2742312.84      6815846.93
      2742282.19      6815819.44      2742265.57      6815812.38
      2742065.81      6815810.54      2742023.58      6815816.53
      2741974.49      6815857.35      2741926.00      6815861.00

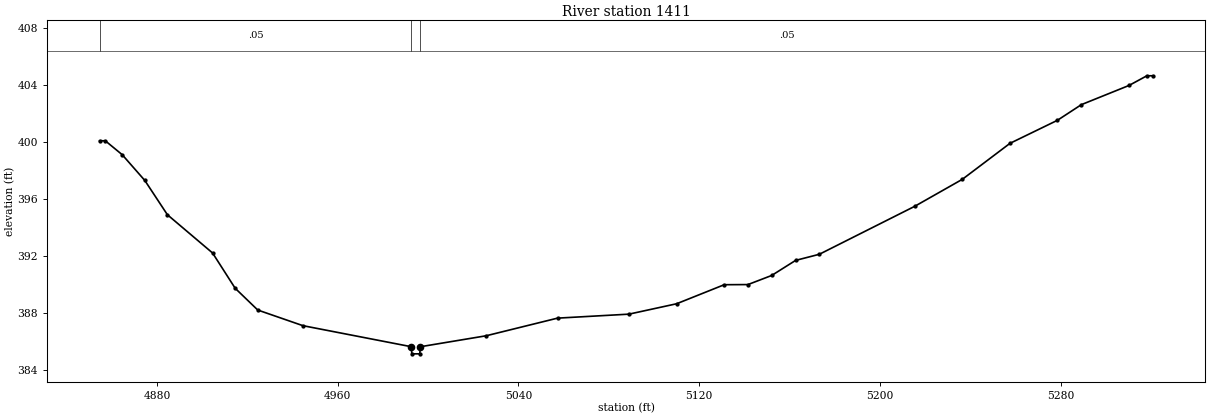
Type RM Length L Ch R = 1,1411,0,0,0
BEGIN DESCRIPTION:
Twin Creek1761411.068
END DESCRIPTION:
XS GIS Cut Line= 3
      2742776.03      6815311.00      2742926.00      6815311.00
      2743226.00      6815411.00
#Sta/Elev= 30
  4854.6  400.10  4857.1  400.10  4864.6  399.12  4874.6  397.31  4884.6  394.90
  4904.6  392.21  4914.6  389.73  4924.6  388.20  4944.6  387.10  4992.6  385.62
  4992.8  385.12  4996.3  385.12  4996.6  385.62  5025.7  386.39  5057.3  387.63
  5088.9  387.91  5110.0  388.64  5131.1  389.98  5141.6  389.99  5152.1  390.63
  5162.7  391.69  5173.2  392.12  5215.4  395.49  5236.5  397.39  5257.6  399.92
  5278.6  401.54  5289.2  402.64  5310.3  403.99  5318.2  404.67  5320.8  404.67
#Mann=3,-1,0
  4854.6    0.05       0  4992.6    0.05       0  4996.6    0.05       0
Bank Sta=4992.6,4996.6
Exp/Cntr=0.3,0.1

Chan Stop Cuts=-1