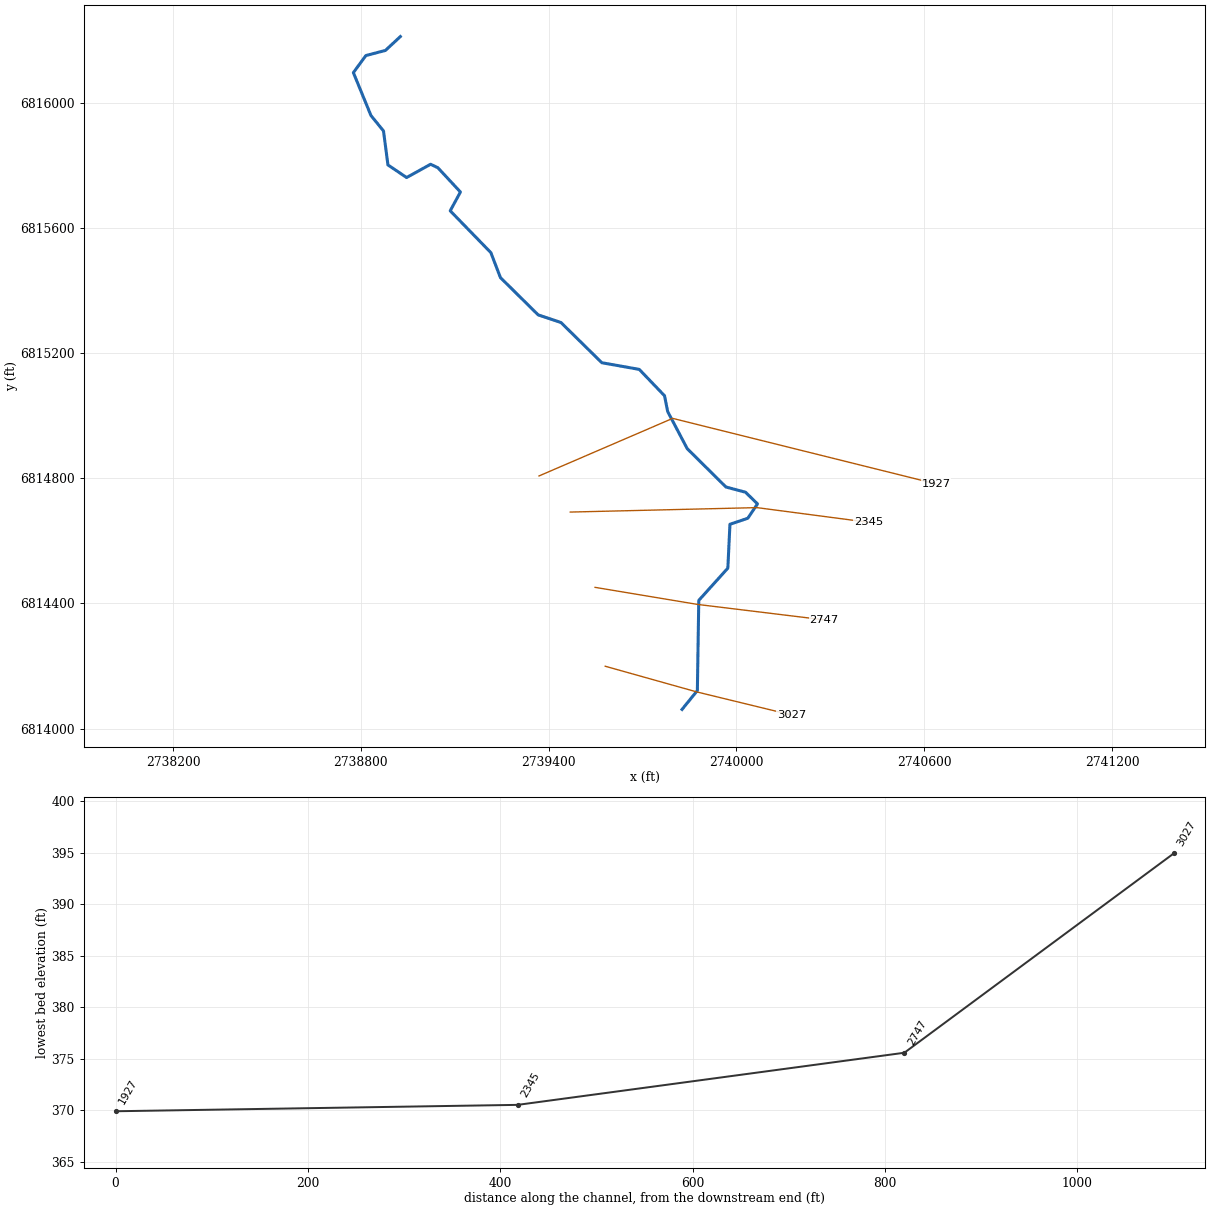
--- Twin Creek178.prj (project) ---

Proj Title=Twin Creek178 Base Level Engineering
Current Plan=p01
Default Exp/Contr=0.3,0.1
English Units
Geom File=g01
Flow File=f01
Plan File=p01
BEGIN DESCRIPTION:
Twin Creek178
END DESCRIPTION:

--- Twin Creek178.p01 (plan) ---

Plan Title=Multiple Run
Short Identifier=Multiple
Geom File=g01
Flow File=f01
Subcritical Flow
K Sum by GR= 0
Std Step Tol= 0.01
Critical Tol= 0.01
Num of Std Step Trials= 20
Max Error Tol= 0.3
Flow Tol Ratio= 0.001
Split Flow NTrial= 30
Split Flow Tol= 0.02
Split Flow Ratio= 0.02
Log Output Level= 0
Friction Slope Method= 1
Unsteady Friction Slope Method= 2
Unsteady Bridges Friction Slope Method= 1
Parabolic Critical Depth
Global Vel Dist=  1 , 1 , 1
Global Log Level= 0
CheckData=True
Encroach Param= -1, 0, 0, 0
BEGIN DESCRIPTION:
Multiple Run
END DESCRIPTION:

--- Twin Creek178.f01 (steady flow) ---

Flow Title=Multiple
Number of Profiles=7
Profile Names=10-year,25-year,50-year,1pct_min,100-year,1pct_plu,500-year
River Rch & RM= Twin Creek178,Reach-1,3027
      87     100     108      59     117     233     135
Boundary for River Rch & Prof#=Twin Creek178,Reach-1,1
Up Type=0
Dn Type=3
Dn Slope=0.005
Boundary for River Rch & Prof#=Twin Creek178,Reach-1,2
Up Type=0
Dn Type=3
Dn Slope=0.005
Boundary for River Rch & Prof#=Twin Creek178,Reach-1,3
Up Type=0
Dn Type=3
Dn Slope=0.005
Boundary for River Rch & Prof#=Twin Creek178,Reach-1,4
Up Type=0
Dn Type=3
Dn Slope=0.005
Boundary for River Rch & Prof#=Twin Creek178,Reach-1,5
Up Type=0
Dn Type=3
Dn Slope=0.005
Boundary for River Rch & Prof#=Twin Creek178,Reach-1,6
Up Type=0
Dn Type=3
Dn Slope=0.005
Boundary for River Rch & Prof#=Twin Creek178,Reach-1,7
Up Type=0
Dn Type=3
Dn Slope=0.005

--- Twin Creek178.g01 (geometry) ---

Geom Title=Existing Conditions

River Reach=Twin Creek178,Reach-1
Reach XY= 30
      2739826.00      6814061.00      2739875.04      6814121.40
      2739879.55      6814409.53      2739972.44      6814512.48
      2739979.13      6814652.70      2740036.14      6814671.93
      2740067.21      6814717.80      2740028.87      6814755.13
      2739966.36      6814771.78      2739842.64      6814894.32
      2739780.19      6815012.74      2739770.17      6815063.31
      2739689.33      6815147.61      2739569.83      6815168.86
      2739439.21      6815297.37      2739366.32      6815321.78
      2739245.79      6815440.91      2739215.22      6815520.68
      2739085.30      6815654.33      2739118.00      6815714.36
      2739046.12      6815791.70      2739022.79      6815803.09
      2738946.05      6815760.63      2738886.39      6815800.78
      2738872.17      6815909.41      2738832.11      6815958.82
      2738775.89      6816095.79      2738815.83      6816150.44
      2738878.31      6816166.72      2738926.00      6816211.00

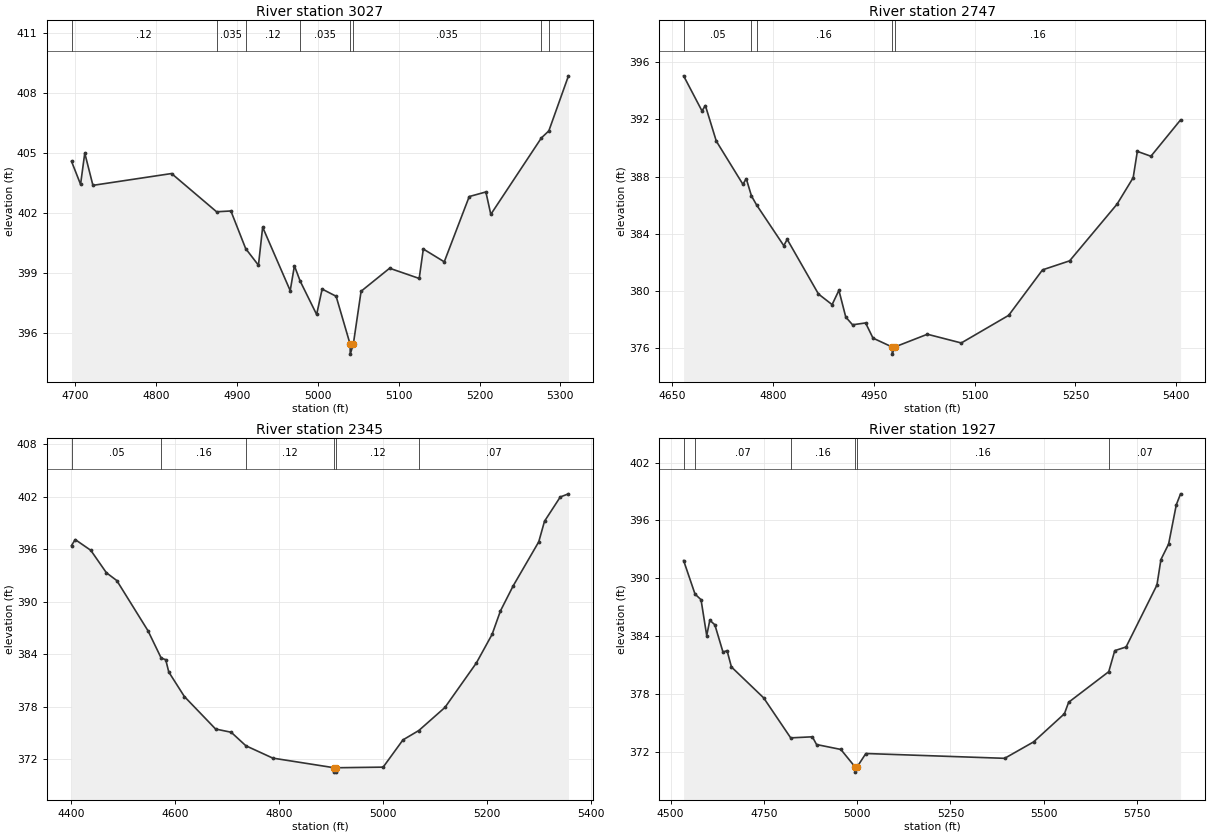
Type RM Length L Ch R = 1,3027,280,280,280
BEGIN DESCRIPTION:
Twin Creek1783026.656
END DESCRIPTION:
XS GIS Cut Line= 3
      2739580.53      6814199.09      2739874.11      6814116.78
      2740175.32      6814043.51
#Sta/Elev= 30
  4695.1  404.58  4706.3  403.43  4711.5  404.99  4721.6  403.38  4818.9  403.97
  4874.6  402.06  4892.3  402.10  4910.6  400.22  4926.4  399.39  4931.6  401.29
  4965.7  398.12  4970.9  399.36  4978.1  398.59  4998.4  396.93  5005.2  398.20
  5022.5  397.84  5039.8  395.45  5040.0  394.95  5043.8  395.45  5053.4  398.09
  5088.7  399.24  5125.3  398.73  5130.4  400.20  5156.3  399.56  5187.2  402.82
  5207.8  403.05  5213.9  401.93  5276.5  405.75  5285.7  406.10  5310.0  408.85
#Mann=8,-1,0
  4695.1    0.12       0  4874.6   0.035       0  4910.6    0.12       0
  4978.1   0.035       0  5039.8   0.035       0  5043.8   0.035       0
  5276.5    0.12       0  5285.7    0.07       0
Bank Sta=5039.8,5043.8
Exp/Cntr=0.3,0.1

Type RM Length L Ch R = 1,2747,402,402,402
BEGIN DESCRIPTION:
Twin Creek1782746.74
END DESCRIPTION:
XS GIS Cut Line= 3
      2739548.10      6814451.15      2739875.81      6814396.59
      2740279.79      6814347.33
#Sta/Elev= 30
  4667.1  395.05  4694.4  392.60  4699.5  392.97  4715.7  390.49  4755.3  387.47
  4760.3  387.86  4768.0  386.66  4775.6  386.03  4816.1  383.18  4821.2  383.62
  4867.7  379.80  4888.0  379.06  4898.1  380.06  4908.3  378.19  4918.4  377.65
  4937.8  377.78  4948.8  376.72  4977.2  376.10  4977.5  375.60  4981.2  376.10
  5029.7  376.99  5080.1  376.38  5150.6  378.31  5201.0  381.49  5241.3  382.12
  5311.8  386.08  5335.8  387.93  5342.0  389.77  5362.2  389.43  5406.3  391.97
#Mann=5,-1,0
  4667.1    0.05       0  4768.0    0.12       0  4775.6    0.16       0
  4977.2    0.07       0  4981.2    0.16       0
Bank Sta=4977.2,4981.2
Exp/Cntr=0.3,0.1

Type RM Length L Ch R = 1,2345,418,418,418
BEGIN DESCRIPTION:
Twin Creek1782344.53
END DESCRIPTION:
XS GIS Cut Line= 3
      2739468.92      6814691.72      2740065.47      6814705.90
      2740421.69      6814659.07
#Sta/Elev= 30
  4401.0  396.41  4408.1  397.09  4438.1  395.86  4468.1  393.30  4488.1  392.41
  4548.1  386.68  4573.6  383.55  4582.2  383.38  4588.1  381.97  4618.1  379.17
  4678.2  375.46  4708.2  375.09  4736.4  373.55  4788.2  372.14  4906.2  371.04
  4906.5  370.54  4910.0  370.54  4910.2  371.04  5000.5  371.11  5038.6  374.22
  5069.1  375.29  5119.3  377.92  5179.8  383.00  5210.1  386.27  5226.1  388.94
  5250.4  391.78  5299.8  396.83  5310.9  399.18  5341.2  401.95  5357.0  402.31
#Mann=6,-1,0
  4401.0    0.05       0  4573.6    0.16       0  4736.4    0.12       0
  4906.2    0.07       0  4910.2    0.12       0  5069.1    0.07       0
Bank Sta=4906.2,4910.2
Exp/Cntr=0.3,0.1

Type RM Length L Ch R = 1,1927,0,0,0
BEGIN DESCRIPTION:
Twin Creek1781927.047
END DESCRIPTION:
XS GIS Cut Line= 3
      2739369.11      6814807.11      2739796.18      6814991.07
      2740637.04      6814781.85
#Sta/Elev= 30
  4535.0  391.85  4565.6  388.37  4581.7  387.79  4596.9  384.07  4605.2  385.66
  4618.7  385.19  4640.5  382.36  4651.4  382.51  4663.1  380.82  4749.4  377.62
  4821.9  373.47  4880.0  373.58  4891.2  372.78  4956.3  372.27  4995.2  370.42
  4995.4  369.92  4999.2  370.42  5023.3  371.85  5395.2  371.35  5472.6  373.05
  5555.3  375.97  5566.6  377.16  5674.1  380.33  5690.2  382.51  5720.5  382.89
  5803.2  389.31  5813.9  391.95  5834.5  393.56  5855.1  397.63  5866.5  398.76
#Mann=6,-1,0
  4535.0    0.05       0  4565.6    0.07       0  4821.9    0.16       0
  4995.2    0.07       0  4999.2    0.16       0  5674.1    0.07       0
Bank Sta=4995.2,4999.2
Exp/Cntr=0.3,0.1

Chan Stop Cuts=-1