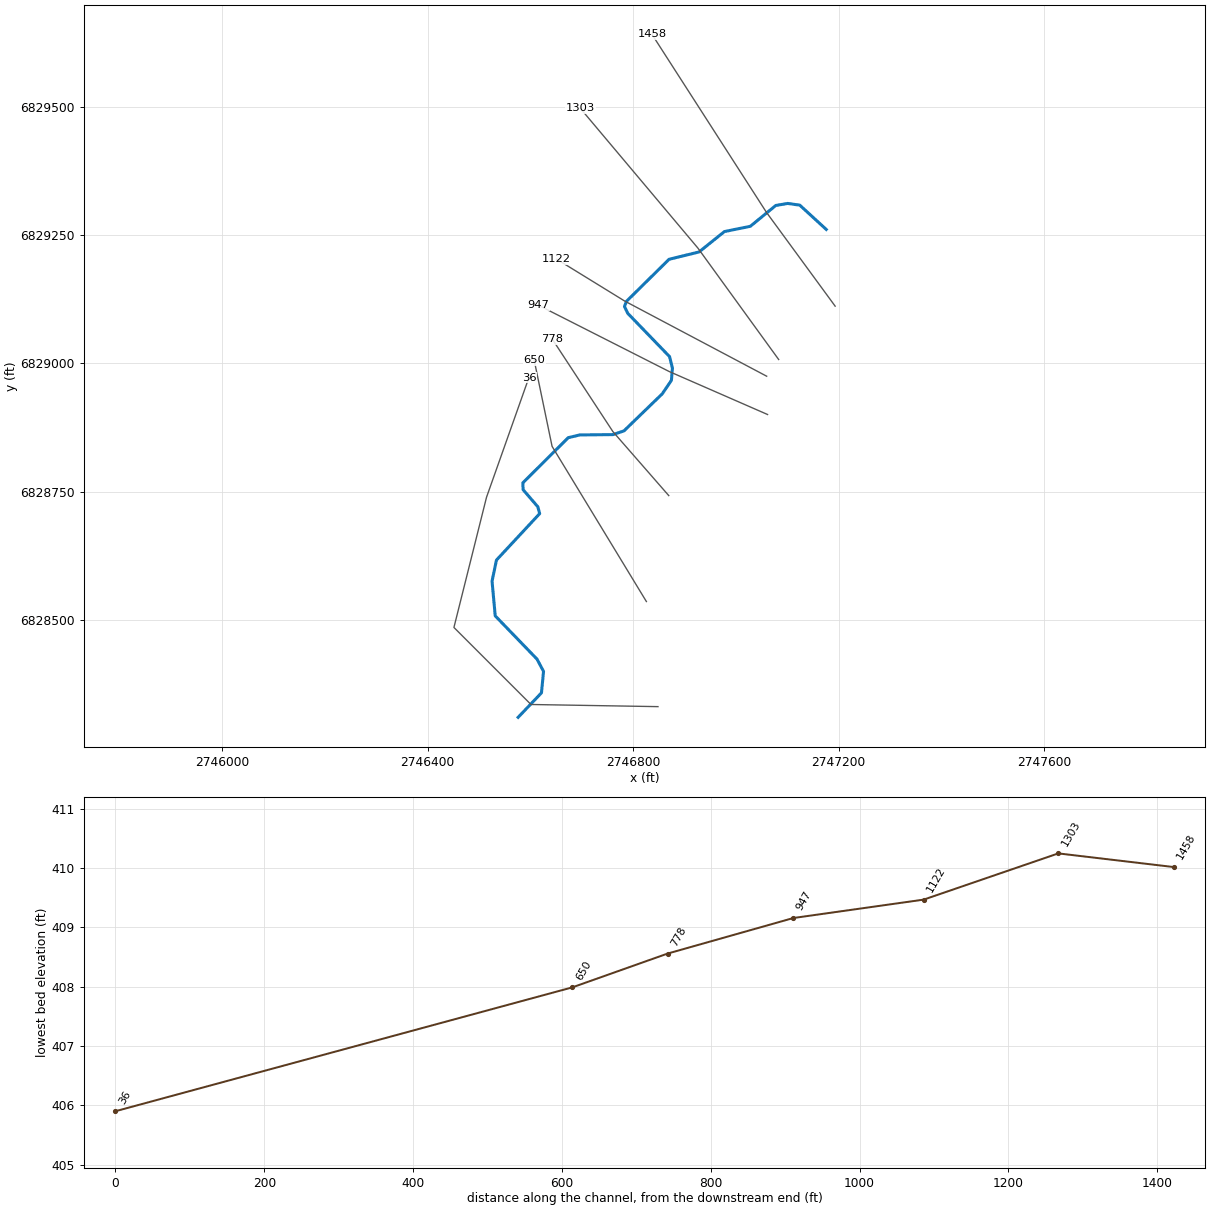
--- Twin Creek180.prj (project) ---

Proj Title=Twin Creek180 Base Level Engineering
Current Plan=p01
Default Exp/Contr=0.3,0.1
English Units
Geom File=g01
Flow File=f01
Plan File=p01
BEGIN DESCRIPTION:
Twin Creek180
END DESCRIPTION:

--- Twin Creek180.p01 (plan) ---

Plan Title=Multiple Run
Short Identifier=Multiple
Geom File=g01
Flow File=f01
Subcritical Flow
K Sum by GR= 0
Std Step Tol= 0.01
Critical Tol= 0.01
Num of Std Step Trials= 20
Max Error Tol= 0.3
Flow Tol Ratio= 0.001
Split Flow NTrial= 30
Split Flow Tol= 0.02
Split Flow Ratio= 0.02
Log Output Level= 0
Friction Slope Method= 1
Unsteady Friction Slope Method= 2
Unsteady Bridges Friction Slope Method= 1
Parabolic Critical Depth
Global Vel Dist=  1 , 1 , 1
Global Log Level= 0
CheckData=True
Encroach Param= -1, 0, 0, 0
BEGIN DESCRIPTION:
Multiple Run
END DESCRIPTION:

--- Twin Creek180.f01 (steady flow) ---

Flow Title=Multiple
Number of Profiles=7
Profile Names=10-year,25-year,50-year,1pct_min,100-year,1pct_plu,500-year
River Rch & RM= Twin Creek180,Reach-1,1458
     147     180     205     116     232     463     297
River Rch & RM= Twin Creek180,Reach-1,36
     267     341     399     232     464     925     627
Boundary for River Rch & Prof#=Twin Creek180,Reach-1,1
Up Type=0
Dn Type=3
Dn Slope=0.005
Boundary for River Rch & Prof#=Twin Creek180,Reach-1,2
Up Type=0
Dn Type=3
Dn Slope=0.005
Boundary for River Rch & Prof#=Twin Creek180,Reach-1,3
Up Type=0
Dn Type=3
Dn Slope=0.005
Boundary for River Rch & Prof#=Twin Creek180,Reach-1,4
Up Type=0
Dn Type=3
Dn Slope=0.005
Boundary for River Rch & Prof#=Twin Creek180,Reach-1,5
Up Type=0
Dn Type=3
Dn Slope=0.005
Boundary for River Rch & Prof#=Twin Creek180,Reach-1,6
Up Type=0
Dn Type=3
Dn Slope=0.005
Boundary for River Rch & Prof#=Twin Creek180,Reach-1,7
Up Type=0
Dn Type=3
Dn Slope=0.005

--- Twin Creek180.g01 (geometry) ---

Geom Title=Existing Conditions

River Reach=Twin Creek180,Reach-1
Reach XY= 30
      2747176.00      6829261.00      2747124.40      6829308.29
      2747100.94      6829311.62      2747077.67      6829307.69
      2747028.20      6829267.14      2746977.72      6829256.85
      2746928.18      6829217.10      2746869.91      6829202.86
      2746786.95      6829121.02      2746783.08      6829111.02
      2746789.44      6829097.68      2746870.91      6829013.29
      2746876.47      6828990.84      2746874.42      6828967.04
      2746856.60      6828940.87      2746782.19      6828868.86
      2746760.79      6828861.52      2746696.05      6828860.87
      2746673.54      6828855.48      2746585.30      6828767.69
      2746585.61      6828754.34      2746614.29      6828721.00
      2746617.98      6828707.67      2746533.79      6828617.17
      2746525.22      6828576.08      2746531.41      6828508.58
      2746612.83      6828424.22      2746625.50      6828400.45
      2746621.43      6828358.65      2746576.00      6828311.00

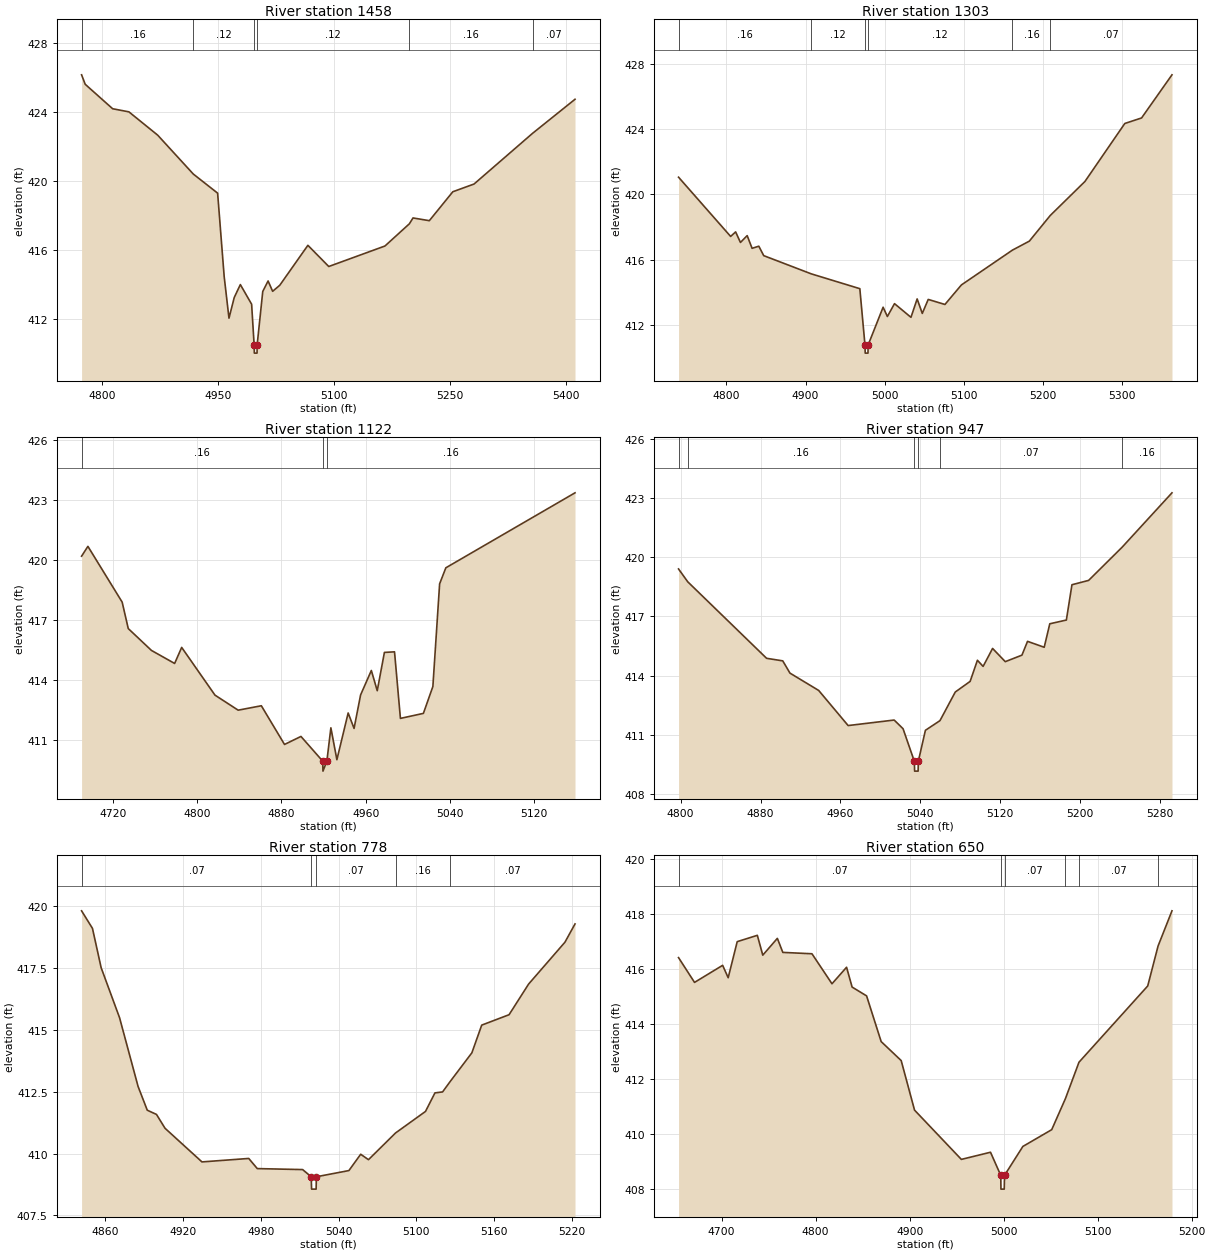
Type RM Length L Ch R = 1,1458,155,155,155
BEGIN DESCRIPTION:
Twin Creek1801457.771
END DESCRIPTION:
XS GIS Cut Line= 3
      2747193.29      6829111.62      2747059.47      6829294.36
      2746836.68      6829640.81
#Sta/Elev= 30
  4773.5  426.18  4778.2  425.63  4813.7  424.21  4834.7  424.03  4871.9  422.68
  4918.0  420.42  4949.5  419.31  4958.0  414.46  4964.2  412.05  4971.0  413.25
  4978.9  414.00  4993.5  412.86  4996.7  410.52  4997.0  410.02  5000.5  410.02
  5000.7  410.52  5007.9  413.60  5014.8  414.21  5020.7  413.61  5029.9  413.96
  5066.3  416.28  5093.3  415.05  5166.0  416.24  5197.6  417.53  5202.3  417.87
  5223.4  417.71  5253.8  419.39  5281.3  419.84  5356.9  422.78  5411.9  424.76
#Mann=6,-1,0
  4773.5    0.16       0  4918.0    0.12       0  4996.7    0.07       0
  5000.7    0.12       0  5197.6    0.16       0  5356.9    0.07       0
Bank Sta=4996.7,5000.7
Exp/Cntr=0.3,0.1

Type RM Length L Ch R = 1,1303,181,181,181
BEGIN DESCRIPTION:
Twin Creek1801303.33
END DESCRIPTION:
XS GIS Cut Line= 3
      2747083.33      6829007.71      2746926.04      6829224.70
      2746697.32      6829496.60
#Sta/Elev= 30
  4739.6  421.06  4805.4  417.42  4811.7  417.70  4817.8  417.05  4826.3  417.47
  4832.5  416.69  4841.0  416.82  4847.2  416.24  4907.3  415.12  4968.6  414.21
  4975.1  410.75  4975.4  410.25  4978.9  410.25  4979.1  410.75  4998.0  413.07
  5003.4  412.50  5012.4  413.29  5033.2  412.45  5041.0  413.58  5047.5  412.69
  5055.0  413.55  5076.1  413.24  5096.9  414.44  5161.4  416.58  5182.7  417.13
  5209.2  418.71  5253.0  420.80  5303.3  424.36  5324.5  424.70  5362.9  427.35
#Mann=6,-1,0
  4739.6    0.16       0  4907.3    0.12       0  4975.1    0.07       0
  4979.1    0.12       0  5161.4    0.16       0  5209.2    0.07       0
Bank Sta=4975.1,4979.1
Exp/Cntr=0.3,0.1

Type RM Length L Ch R = 1,1122,175,175,175
BEGIN DESCRIPTION:
Mapping XS 2f42bd81
END DESCRIPTION:
XS GIS Cut Line= 3
      2747059.98      6828975.18      2746783.14      6829121.78
      2746651.11      6829203.05
#Sta/Elev= 30
  4690.4  420.19  4696.4  420.68  4728.9  417.90  4734.7  416.58  4756.7  415.49
  4778.7  414.84  4785.4  415.64  4817.0  413.26  4839.0  412.51  4861.0  412.73
  4883.0  410.80  4898.6  411.20  4919.2  409.97  4919.5  409.47  4923.2  409.97
  4927.0  411.63  4932.7  410.04  4943.4  412.37  4949.0  411.60  4955.2  413.27
  4965.4  414.49  4971.0  413.48  4977.8  415.39  4987.4  415.42  4993.0  412.10
  5014.8  412.35  5023.8  413.69  5030.2  418.81  5036.1  419.61  5158.7  423.35
#Mann=3,-1,0
  4690.4    0.16       0  4919.2    0.07       0  4923.2    0.16       0
Bank Sta=4919.2,4923.2
Exp/Cntr=0.3,0.1

Type RM Length L Ch R = 1,947,169,169,169
BEGIN DESCRIPTION:
Twin Creek180947.24
END DESCRIPTION:
XS GIS Cut Line= 3
      2747061.67      6828900.65      2746870.08      6828984.37
      2746615.69      6829113.34
#Sta/Elev= 30
  4797.9  419.41  4807.1  418.76  4886.1  414.88  4902.3  414.75  4909.5  414.13
  4938.3  413.25  4967.8  411.47  5013.9  411.75  5022.8  411.31  5034.1  409.66
  5034.4  409.16  5037.9  409.16  5038.1  409.66  5045.2  411.23  5059.8  411.72
  5075.1  413.17  5090.0  413.71  5097.3  414.78  5103.0  414.47  5112.5  415.38
  5125.2  414.71  5141.9  415.04  5147.5  415.74  5164.2  415.44  5169.8  416.63
  5186.4  416.82  5192.0  418.61  5208.7  418.83  5242.4  420.52  5292.2  423.27
#Mann=6,-1,0
  4797.9    0.07       0  4807.1    0.16       0  5034.1    0.07       0
  5038.1    0.16       0  5059.8    0.07       0  5242.4    0.16       0
Bank Sta=5034.1,5038.1
Exp/Cntr=0.3,0.1

Type RM Length L Ch R = 1,778,128,128,128
BEGIN DESCRIPTION:
Twin Creek180778.39
END DESCRIPTION:
XS GIS Cut Line= 3
      2746869.27      6828742.77      2746760.46      6828867.44
      2746642.44      6829047.54
#Sta/Elev= 30
  4841.6  419.81  4850.0  419.10  4856.7  417.51  4870.9  415.49  4885.2  412.71
  4892.3  411.75  4899.4  411.58  4906.0  411.02  4934.5  409.66  4970.6  409.80
  4977.2  409.39  5012.2  409.35  5018.8  409.06  5019.1  408.56  5022.6  408.56
  5022.8  409.06  5047.9  409.31  5057.0  409.97  5063.0  409.75  5083.9  410.83
  5107.0  411.70  5114.3  412.45  5120.2  412.49  5126.2  412.92  5142.8  414.07
  5150.4  415.19  5171.5  415.61  5186.6  416.85  5214.6  418.54  5222.4  419.28
#Mann=5,-1,0
  4841.6    0.07       0  5018.8    0.07       0  5022.8    0.07       0
  5083.9    0.16       0  5126.2    0.07       0
Bank Sta=5018.8,5022.8
Exp/Cntr=0.3,0.1

Type RM Length L Ch R = 1,650,614,614,614
BEGIN DESCRIPTION:
Twin Creek180649.72
END DESCRIPTION:
XS GIS Cut Line= 3
      2746825.74      6828536.47      2746642.11      6828838.62
      2746607.30      6829006.27
#Sta/Elev= 30
  4654.2  416.40  4671.2  415.50  4701.1  416.12  4707.0  415.67  4716.6  416.98
  4738.0  417.21  4743.8  416.49  4759.3  417.10  4765.1  416.59  4796.1  416.54
  4817.4  415.45  4832.9  416.05  4838.8  415.33  4854.2  415.01  4869.7  413.35
  4891.0  412.66  4905.2  410.86  4955.0  409.07  4986.0  409.33  4996.9  408.49
  4997.1  407.99  5000.6  407.99  5000.9  408.49  5020.4  409.54  5051.1  410.15
  5065.7  411.28  5080.1  412.60  5153.2  415.37  5164.2  416.82  5179.0  418.10
#Mann=6,-1,0
  4654.2    0.07       0  4996.9    0.07       0  5000.9    0.07       0
  5065.7    0.16       0  5080.1    0.07       0  5164.2    0.16       0
Bank Sta=4996.9,5000.9
Exp/Cntr=0.3,0.1

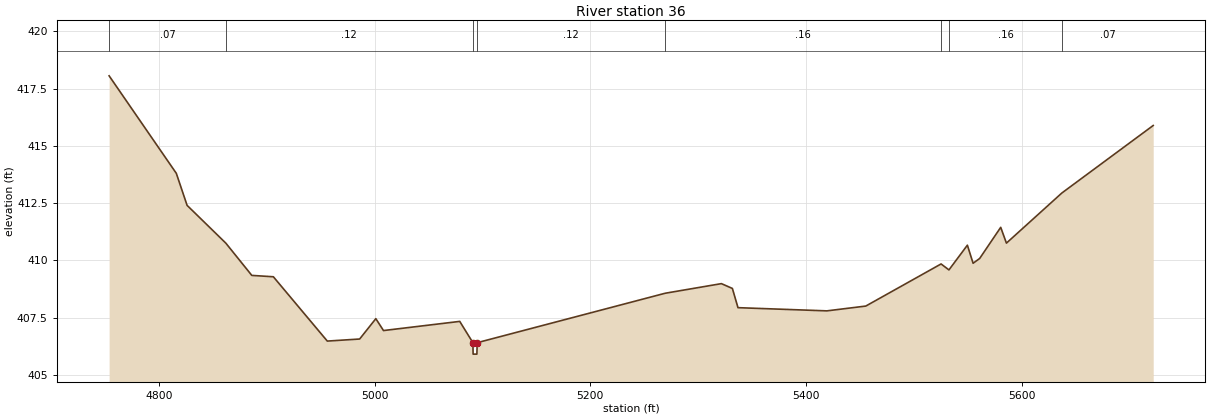
Type RM Length L Ch R = 1,36,0,0,0
BEGIN DESCRIPTION:
Twin Creek18036.229
END DESCRIPTION:
XS GIS Cut Line= 5
      2746848.30      6828331.82      2746601.00      6828336.00
      2746451.00      6828486.00      2746514.43      6828739.44
      2746597.02      6828972.63
#Sta/Elev= 30
  4753.9  418.06  4816.2  413.80  4826.2  412.40  4862.1  410.75  4886.2  409.34
  4906.2  409.28  4956.2  406.47  4986.2  406.56  5001.2  407.45  5008.3  406.93
  5079.0  407.33  5091.2  406.40  5091.4  405.90  5094.9  405.90  5095.2  406.40
  5269.5  408.56  5321.6  408.98  5331.8  408.77  5337.0  407.93  5419.4  407.79
  5455.5  408.00  5525.3  409.84  5532.6  409.58  5549.7  410.66  5555.0  409.87
  5561.1  410.08  5580.6  411.44  5585.9  410.75  5637.3  412.94  5722.0  415.89
#Mann=8,-1,0
  4753.9    0.07       0  4862.1    0.12       0  5091.2    0.07       0
  5095.2    0.12       0  5269.5    0.16       0  5525.3    0.07       0
  5532.6    0.16       0  5637.3    0.07       0
Bank Sta=5091.2,5095.2
Exp/Cntr=0.3,0.1

Chan Stop Cuts=-1