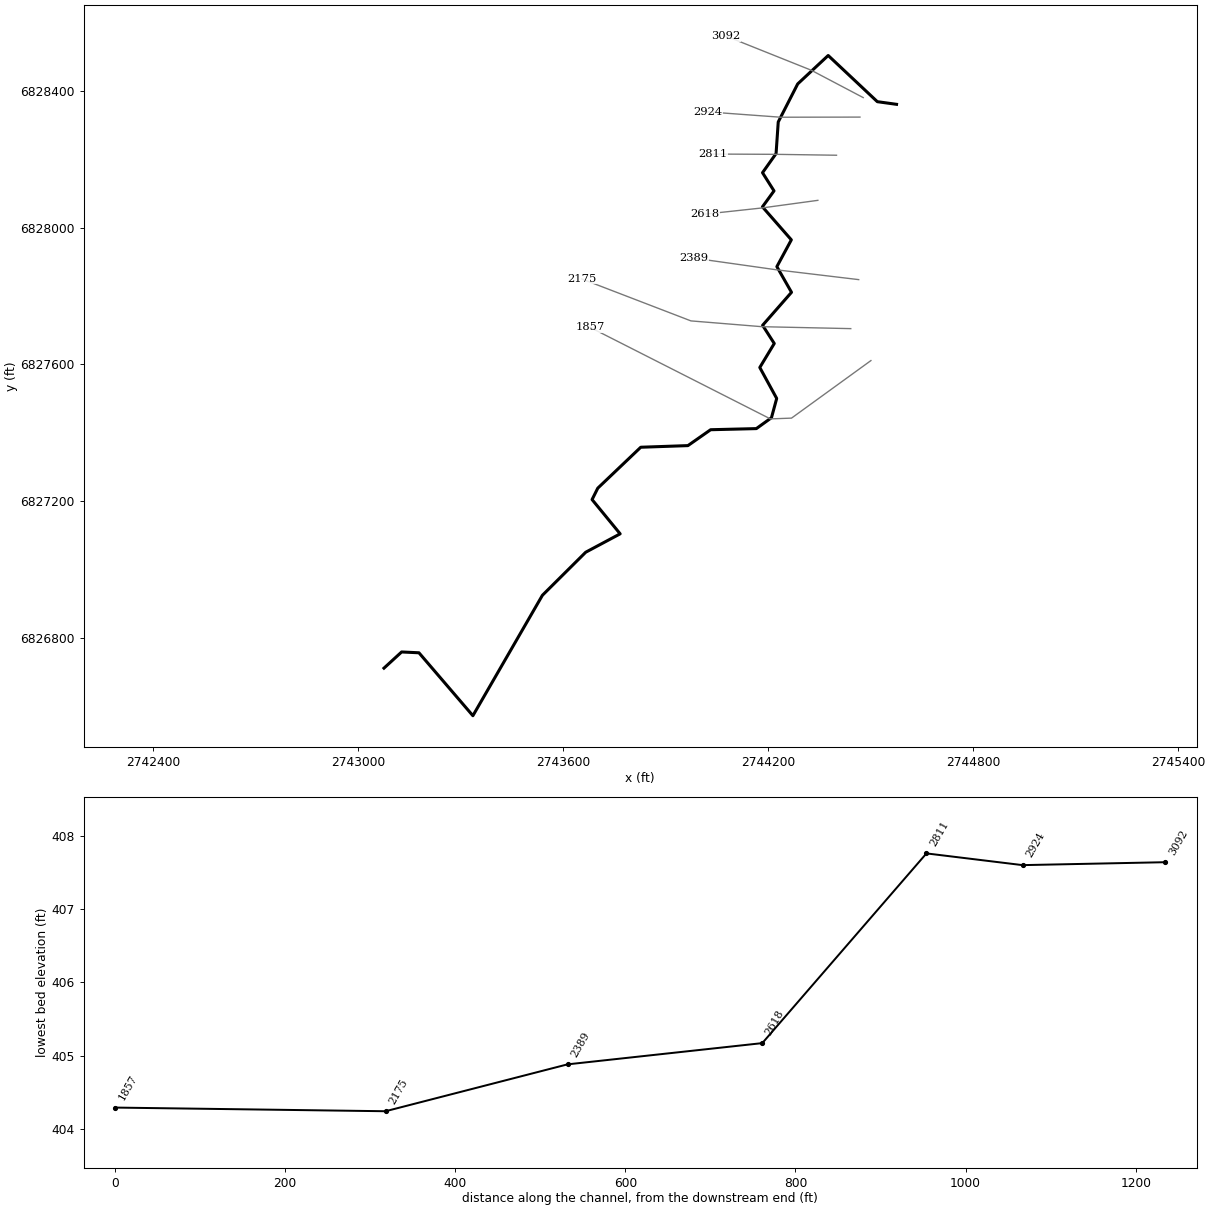
--- Twin Creek181.prj (project) ---

Proj Title=Twin Creek181 Base Level Engineering
Current Plan=p01
Default Exp/Contr=0.3,0.1
English Units
Geom File=g01
Flow File=f01
Plan File=p01
BEGIN DESCRIPTION:
Twin Creek181
END DESCRIPTION:

--- Twin Creek181.p01 (plan) ---

Plan Title=Multiple Run
Short Identifier=Multiple
Geom File=g01
Flow File=f01
Subcritical Flow
K Sum by GR= 0
Std Step Tol= 0.01
Critical Tol= 0.01
Num of Std Step Trials= 20
Max Error Tol= 0.3
Flow Tol Ratio= 0.001
Split Flow NTrial= 30
Split Flow Tol= 0.02
Split Flow Ratio= 0.02
Log Output Level= 0
Friction Slope Method= 1
Unsteady Friction Slope Method= 2
Unsteady Bridges Friction Slope Method= 1
Parabolic Critical Depth
Global Vel Dist=  1 , 1 , 1
Global Log Level= 0
CheckData=True
Encroach Param= -1, 0, 0, 0
BEGIN DESCRIPTION:
Multiple Run
END DESCRIPTION:

--- Twin Creek181.f01 (steady flow) ---

Flow Title=Multiple
Number of Profiles=7
Profile Names=10-year,25-year,50-year,1pct_min,100-year,1pct_plu,500-year
River Rch & RM= Twin Creek181,Reach-1,3092
     243     307     356     206     411     820     546
Boundary for River Rch & Prof#=Twin Creek181,Reach-1,1
Up Type=0
Dn Type=3
Dn Slope=0.005
Boundary for River Rch & Prof#=Twin Creek181,Reach-1,2
Up Type=0
Dn Type=3
Dn Slope=0.005
Boundary for River Rch & Prof#=Twin Creek181,Reach-1,3
Up Type=0
Dn Type=3
Dn Slope=0.005
Boundary for River Rch & Prof#=Twin Creek181,Reach-1,4
Up Type=0
Dn Type=3
Dn Slope=0.005
Boundary for River Rch & Prof#=Twin Creek181,Reach-1,5
Up Type=0
Dn Type=3
Dn Slope=0.005
Boundary for River Rch & Prof#=Twin Creek181,Reach-1,6
Up Type=0
Dn Type=3
Dn Slope=0.005
Boundary for River Rch & Prof#=Twin Creek181,Reach-1,7
Up Type=0
Dn Type=3
Dn Slope=0.005

--- Twin Creek181.g01 (geometry) ---

Geom Title=Existing Conditions

River Reach=Twin Creek181,Reach-1
Reach XY= 30
      2744576.00      6828361.00      2744519.79      6828368.76
      2744375.99      6828503.93      2744286.76      6828420.73
      2744229.82      6828309.41      2744223.46      6828216.89
      2744183.78      6828160.90      2744217.43      6828107.66
      2744183.56      6828061.00      2744268.15      6827964.41
      2744225.79      6827886.00      2744268.63      6827810.91
      2744184.02      6827714.34      2744218.16      6827661.09
      2744175.83      6827590.87      2744225.28      6827500.25
      2744209.97      6827443.86      2744165.75      6827412.00
      2744031.94      6827408.73      2743965.49      6827362.23
      2743827.47      6827357.46      2743701.67      6827237.67
      2743684.99      6827204.33      2743767.15      6827104.05
      2743666.36      6827050.22      2743539.63      6826924.21
      2743336.19      6826571.77      2743178.36      6826755.95
      2743127.62      6826758.33      2743076.00      6826711.00

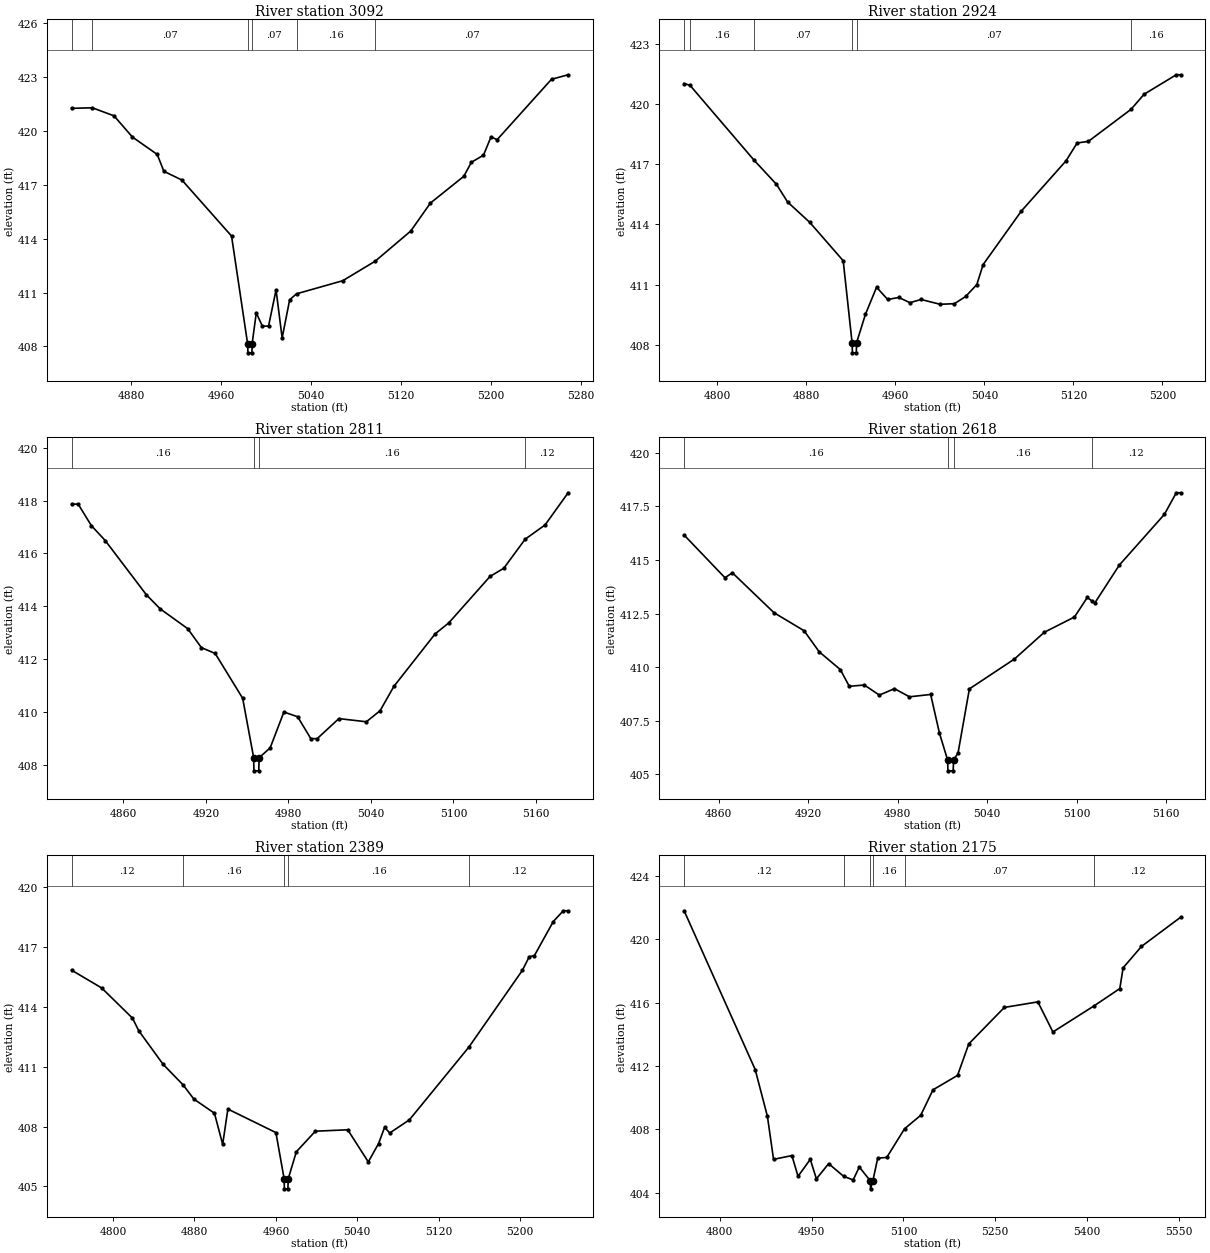
Type RM Length L Ch R = 1,3092,168,168,168
BEGIN DESCRIPTION:
Twin Creek1813092.047
END DESCRIPTION:
XS GIS Cut Line= 3
      2744478.53      6828380.67      2744326.00      6828461.00
      2744076.05      6828560.98
#Sta/Elev= 30
  4827.0  421.27  4845.4  421.30  4864.7  420.85  4881.0  419.67  4903.1  418.70
  4909.0  417.76  4925.1  417.27  4969.2  414.15  4983.5  408.14  4983.8  407.64
  4987.3  407.64  4987.5  408.14  4991.2  409.87  4996.6  409.13  5002.1  409.13
  5008.8  411.15  5014.2  408.47  5020.9  410.60  5027.0  410.93  5068.1  411.66
  5097.0  412.75  5128.6  414.43  5146.1  415.99  5175.8  417.48  5182.5  418.26
  5193.3  418.66  5200.0  419.68  5205.4  419.52  5253.8  422.89  5268.6  423.14
#Mann=6,-1,0
  4827.0    0.16       0  4845.4    0.07       0  4983.5    0.07       0
  4987.5    0.07       0  5027.0    0.16       0  5097.0    0.07       0
Bank Sta=4983.5,4987.5
Exp/Cntr=0.3,0.1

Type RM Length L Ch R = 1,2924,113,113,113
BEGIN DESCRIPTION:
Twin Creek1812923.7
END DESCRIPTION:
XS GIS Cut Line= 3
      2744469.02      6828323.63      2744236.79      6828323.27
      2744023.29      6828338.95
#Sta/Elev= 30
  4770.0  421.02  4775.2  420.94  4832.6  417.22  4853.0  416.00  4863.0  415.12
  4883.0  414.10  4913.0  412.19  4921.0  408.10  4921.3  407.60  4924.8  407.60
  4925.0  408.10  4933.0  409.52  4943.0  410.87  4953.0  410.26  4963.0  410.36
  4973.0  410.10  4983.0  410.26  5000.1  410.02  5013.0  410.05  5023.1  410.41
  5033.1  411.00  5038.8  412.00  5073.2  414.67  5113.3  417.17  5123.3  418.06
  5133.4  418.14  5171.8  419.74  5183.5  420.49  5212.4  421.46  5216.3  421.46
#Mann=6,-1,0
  4770.0    0.07       0  4775.2    0.16       0  4832.6    0.07       0
  4921.0    0.07       0  4925.0    0.07       0  5171.8    0.16       0
Bank Sta=4921,4925
Exp/Cntr=0.3,0.1

Type RM Length L Ch R = 1,2811,193,193,193
BEGIN DESCRIPTION:
Twin Creek1812811.49
END DESCRIPTION:
XS GIS Cut Line= 3
      2744400.36      6828212.02      2744221.75      6828214.67
      2744039.18      6828215.45
#Sta/Elev= 30
  4822.3  417.87  4827.0  417.87  4836.7  417.05  4846.7  416.49  4876.7  414.43
  4886.7  413.90  4906.7  413.15  4916.7  412.43  4926.7  412.21  4946.7  410.51
  4954.7  408.26  4954.9  407.76  4958.4  407.76  4958.7  408.26  4966.7  408.63
  4976.7  409.99  4986.7  409.81  4996.3  408.98  5000.9  408.98  5016.7  409.74
  5036.7  409.62  5046.7  410.04  5056.7  410.96  5086.7  412.95  5096.7  413.37
  5126.7  415.13  5136.7  415.44  5152.2  416.54  5166.7  417.08  5183.5  418.30
#Mann=4,-1,0
  4822.3    0.16       0  4954.7    0.07       0  4958.7    0.16       0
  5152.2    0.12       0
Bank Sta=4954.7,4958.7
Exp/Cntr=0.3,0.1

Type RM Length L Ch R = 1,2618,229,229,229
BEGIN DESCRIPTION:
Twin Creek1812617.78
END DESCRIPTION:
XS GIS Cut Line= 3
      2744345.78      6828080.02      2744181.92      6828057.70
      2744015.16      6828039.64
#Sta/Elev= 30
  4836.7  416.16  4864.1  414.17  4869.1  414.40  4897.0  412.54  4917.2  411.70
  4927.3  410.72  4941.5  409.89  4947.5  409.11  4957.6  409.17  4967.7  408.70
  4977.8  409.00  4987.9  408.62  5002.1  408.73  5008.0  406.93  5013.5  405.67
  5013.7  405.17  5017.2  405.17  5017.5  405.67  5020.5  406.01  5028.1  408.99
  5058.3  410.38  5078.4  411.63  5098.6  412.34  5107.2  413.25  5110.1  413.10
  5112.2  412.99  5128.7  414.76  5158.9  417.12  5166.9  418.13  5169.8  418.13
#Mann=4,-1,0
  4836.7    0.16       0  5013.5    0.07       0  5017.5    0.16       0
  5110.1    0.12       0
Bank Sta=5013.5,5017.5
Exp/Cntr=0.3,0.1

Type RM Length L Ch R = 1,2389,214,214,214
BEGIN DESCRIPTION:
Twin Creek1812388.88
END DESCRIPTION:
XS GIS Cut Line= 3
      2744465.27      6827848.00      2744223.90      6827876.86
      2743981.50      6827911.12
#Sta/Elev= 30
  4759.3  415.84  4788.8  414.95  4819.0  413.44  4825.3  412.80  4849.2  411.12
  4868.8  410.09  4879.4  409.38  4899.6  408.67  4907.7  407.11  4912.8  408.88
  4960.0  407.70  4968.1  405.38  4968.3  404.88  4971.8  404.88  4972.1  405.38
  4980.1  406.74  4998.8  407.77  5030.6  407.84  5050.8  406.23  5060.9  407.15
  5066.8  407.96  5071.9  407.68  5091.2  408.34  5149.7  411.99  5202.3  415.84
  5209.0  416.52  5214.0  416.57  5232.6  418.28  5242.4  418.82  5247.2  418.82
#Mann=5,-1,0
  4759.3    0.12       0  4868.8    0.16       0  4968.1    0.07       0
  4972.1    0.16       0  5149.7    0.12       0
Bank Sta=4968.1,4972.1
Exp/Cntr=0.3,0.1

Type RM Length L Ch R = 1,2175,318,318,318
BEGIN DESCRIPTION:
Twin Creek1812175.01
END DESCRIPTION:
XS GIS Cut Line= 4
      2744442.05      6827704.58      2744181.96      6827710.26
      2743974.38      6827727.20      2743654.51      6827850.13
#Sta/Elev= 30
  4741.6  421.79  4857.7  411.77  4877.7  408.81  4887.7  406.10  4917.7  406.34
  4927.7  405.03  4947.7  406.10  4957.7  404.87  4977.7  405.83  5002.2  405.03
  5017.8  404.80  5027.8  405.62  5045.9  404.74  5046.1  404.24  5049.9  404.74
  5057.9  406.18  5072.6  406.22  5101.7  408.03  5128.1  408.88  5148.2  410.49
  5188.3  411.40  5206.7  413.39  5264.8  415.69  5319.5  416.04  5344.1  414.14
  5411.8  415.80  5453.4  416.88  5458.8  418.19  5488.8  419.54  5552.7  421.38
#Mann=6,-1,0
  4741.6    0.12       0  5002.2    0.16       0  5045.9    0.07       0
  5049.9    0.16       0  5101.7    0.07       0  5411.8    0.12       0
Bank Sta=5045.9,5049.9
Exp/Cntr=0.3,0.1

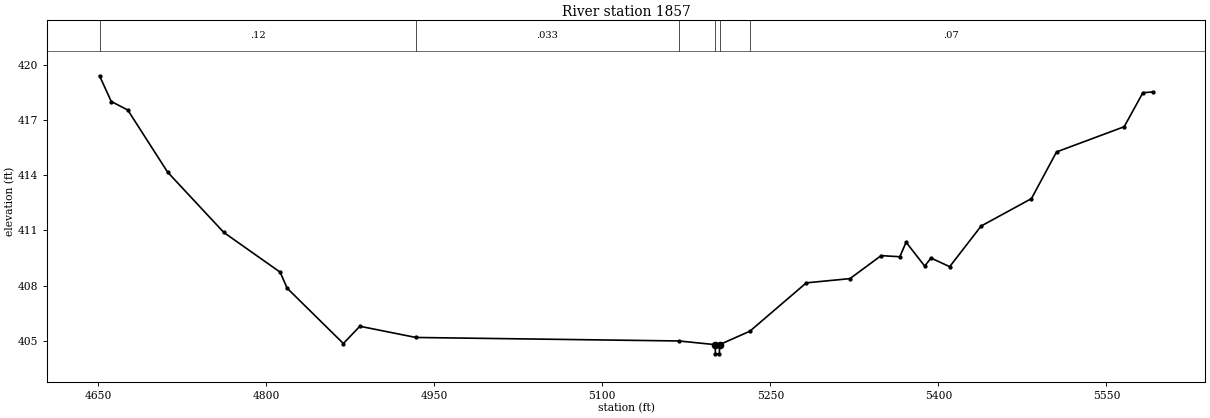
Type RM Length L Ch R = 1,1857,0,0,0
BEGIN DESCRIPTION:
Twin Creek1811856.837
END DESCRIPTION:
XS GIS Cut Line= 4
      2744501.04      6827611.08      2744268.68      6827442.69
      2744206.78      6827440.42      2743679.44      6827708.12
#Sta/Elev= 30
  4651.1  419.41  4661.6  418.01  4676.3  417.55  4711.9  414.17  4762.1  410.89
  4812.4  408.73  4818.6  407.86  4868.8  404.85  4883.5  405.79  4933.6  405.18
  5168.3  404.99  5200.7  404.79  5201.0  404.29  5204.5  404.29  5204.7  404.79
  5231.7  405.52  5282.1  408.15  5321.1  408.38  5348.9  409.63  5365.6  409.57
  5371.2  410.36  5387.8  409.06  5393.4  409.50  5410.1  409.03  5438.2  411.24
  5483.1  412.73  5505.5  415.27  5565.9  416.64  5582.6  418.49  5591.4  418.53
#Mann=6,-1,0
  4651.1    0.12       0  4933.6   0.033       0  5168.3    0.12       0
  5200.7   0.033       0  5204.7    0.12       0  5231.7    0.07       0
Bank Sta=5200.7,5204.7
Exp/Cntr=0.3,0.1

Chan Stop Cuts=-1