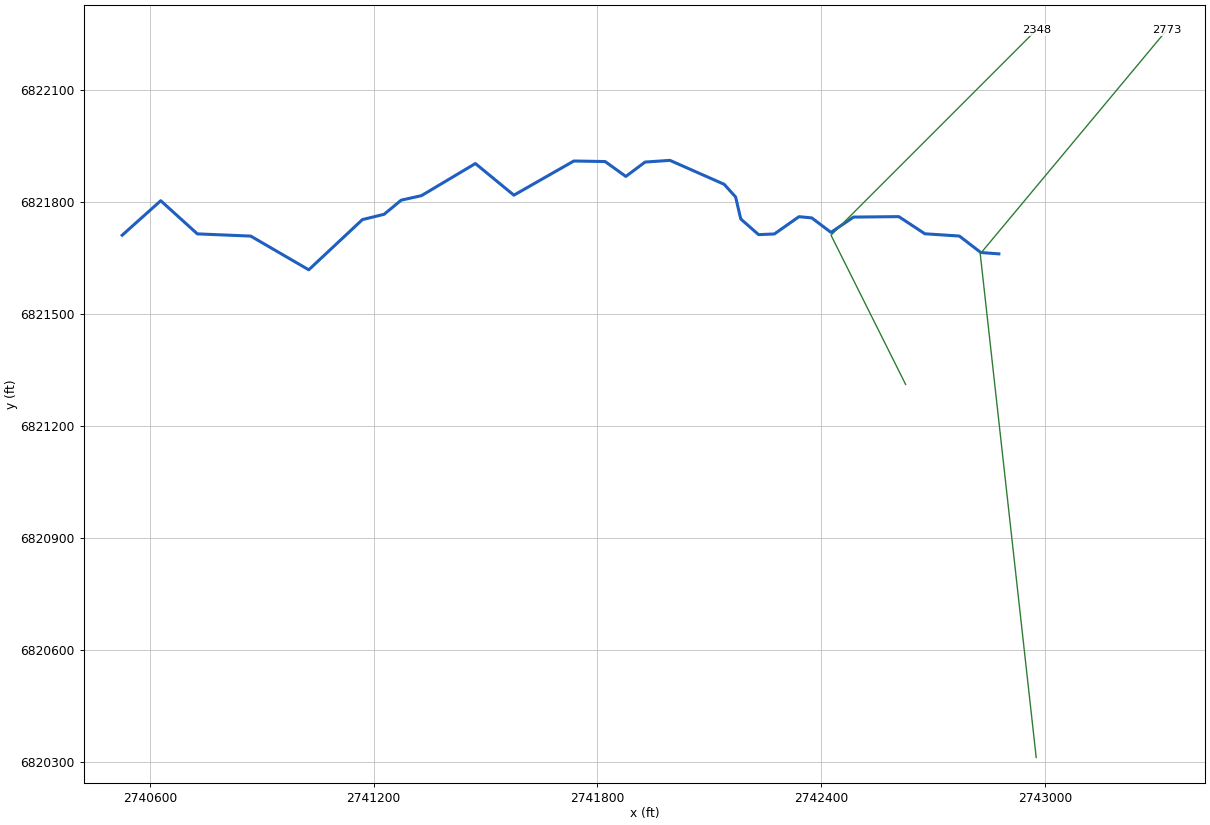
--- Twin Creek182.prj (project) ---

Proj Title=Twin Creek182 Base Level Engineering
Current Plan=p01
Default Exp/Contr=0.3,0.1
English Units
Geom File=g01
Flow File=f01
Plan File=p01
BEGIN DESCRIPTION:
Twin Creek182
END DESCRIPTION:

--- Twin Creek182.p01 (plan) ---

Plan Title=Multiple Run
Short Identifier=Multiple
Geom File=g01
Flow File=f01
Subcritical Flow
K Sum by GR= 0
Std Step Tol= 0.01
Critical Tol= 0.01
Num of Std Step Trials= 20
Max Error Tol= 0.3
Flow Tol Ratio= 0.001
Split Flow NTrial= 30
Split Flow Tol= 0.02
Split Flow Ratio= 0.02
Log Output Level= 0
Friction Slope Method= 1
Unsteady Friction Slope Method= 2
Unsteady Bridges Friction Slope Method= 1
Parabolic Critical Depth
Global Vel Dist=  1 , 1 , 1
Global Log Level= 0
CheckData=True
Encroach Param= -1, 0, 0, 0
BEGIN DESCRIPTION:
Multiple Run
END DESCRIPTION:

--- Twin Creek182.f01 (steady flow) ---

Flow Title=Multiple
Number of Profiles=7
Profile Names=10-year,25-year,50-year,1pct_min,100-year,1pct_plu,500-year
River Rch & RM= Twin Creek182,Reach-1,2773
      37      40      42      22      44      89      49
Boundary for River Rch & Prof#=Twin Creek182,Reach-1,1
Up Type=0
Dn Type=3
Dn Slope=0.005
Boundary for River Rch & Prof#=Twin Creek182,Reach-1,2
Up Type=0
Dn Type=3
Dn Slope=0.005
Boundary for River Rch & Prof#=Twin Creek182,Reach-1,3
Up Type=0
Dn Type=3
Dn Slope=0.005
Boundary for River Rch & Prof#=Twin Creek182,Reach-1,4
Up Type=0
Dn Type=3
Dn Slope=0.005
Boundary for River Rch & Prof#=Twin Creek182,Reach-1,5
Up Type=0
Dn Type=3
Dn Slope=0.005
Boundary for River Rch & Prof#=Twin Creek182,Reach-1,6
Up Type=0
Dn Type=3
Dn Slope=0.005
Boundary for River Rch & Prof#=Twin Creek182,Reach-1,7
Up Type=0
Dn Type=3
Dn Slope=0.005

--- Twin Creek182.g01 (geometry) ---

Geom Title=Existing Conditions

River Reach=Twin Creek182,Reach-1
Reach XY= 30
      2742876.00      6821661.00      2742827.51      6821664.64
      2742770.08      6821708.77      2742677.60      6821714.85
      2742607.72      6821760.81      2742486.44      6821759.63
      2742425.99      6821718.59      2742374.36      6821757.39
      2742340.12      6821760.68      2742274.24      6821714.36
      2742231.85      6821712.55      2742184.05      6821754.59
      2742170.24      6821813.51      2742139.56      6821847.52
      2741994.24      6821911.64      2741927.50      6821907.06
      2741876.00      6821868.57      2741820.51      6821908.51
      2741736.55      6821909.91      2741575.91      6821818.31
      2741472.77      6821903.15      2741328.20      6821817.08
      2741273.80      6821804.92      2741228.19      6821767.10
      2741169.94      6821752.86      2741026.09      6821618.29
      2740870.48      6821708.64      2740727.47      6821714.57
      2740629.33      6821803.47      2740526.00      6821711.00

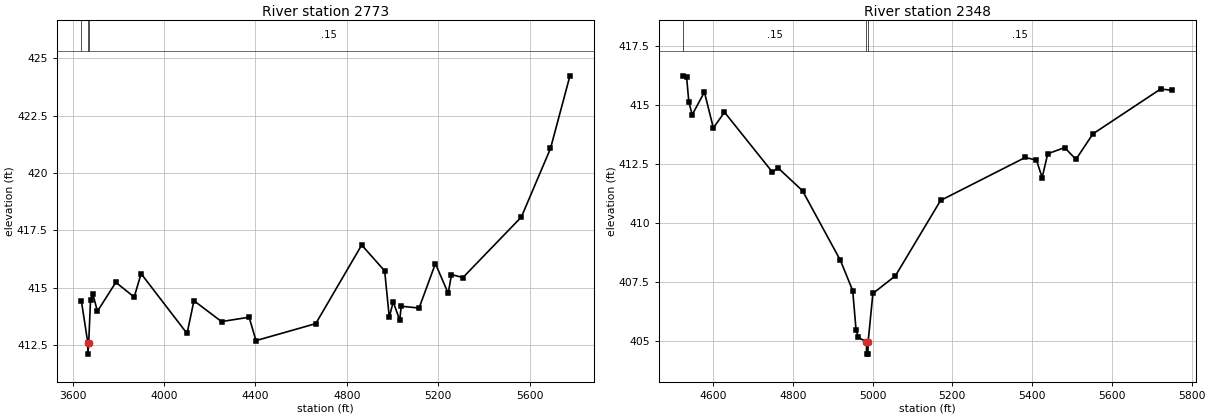
Type RM Length L Ch R = 1,2773,425,425,425
BEGIN DESCRIPTION:
Twin Creek182 2.0
END DESCRIPTION:
XS GIS Cut Line= 3
      2742976.00      6820311.00      2742826.00      6821661.00
      2743325.98      6822260.98
#Sta/Elev= 30
  3637.5  414.43  3665.7  412.60  3665.9  412.10  3669.7  412.60  3677.7  414.45
  3687.8  414.72  3707.9  413.97  3788.4  415.23  3868.9  414.59  3899.1  415.61
  4100.3  413.00  4130.5  414.43  4251.3  413.52  4372.0  413.71  4402.2  412.69
  4663.8  413.43  4865.0  416.86  4965.6  415.73  4985.7  413.71  5003.0  414.38
  5031.6  413.58  5038.1  414.19  5116.2  414.11  5187.8  416.05  5243.8  414.75
  5258.1  415.57  5308.2  415.44  5564.0  418.08  5691.6  421.07  5776.8  424.24
#Mann=3,-1,0
  3637.5    0.15       0  3665.7    0.05       0  3669.7    0.15       0
Bank Sta=3665.7,3669.7
Exp/Cntr=0.3,0.1

Type RM Length L Ch R = 1,2348,0,0,0
BEGIN DESCRIPTION:
Twin Creek182 1.0
END DESCRIPTION:
XS GIS Cut Line= 3
      2742626.00      6821310.99      2742426.00      6821711.00
      2742975.97      6822260.97
#Sta/Elev= 30
  4525.3  416.23  4533.7  416.18  4539.3  415.13  4547.7  414.58  4578.4  415.54
  4600.8  414.02  4628.7  414.69  4748.9  412.15  4762.9  412.33  4824.4  411.36
  4919.4  408.41  4950.2  407.13  4958.5  405.48  4964.1  405.16  4984.7  404.94
  4984.9  404.44  4988.4  404.44  4988.7  404.94  5000.8  407.01  5057.4  407.76
  5170.5  410.95  5382.6  412.77  5410.9  412.66  5425.1  411.92  5439.2  412.93
  5481.6  413.19  5509.9  412.69  5552.4  413.77  5722.1  415.67  5750.3  415.62
#Mann=3,-1,0
  4525.3    0.15       0  4984.7    0.05       0  4988.7    0.15       0
Bank Sta=4984.7,4988.7
Exp/Cntr=0.3,0.1

Chan Stop Cuts=-1