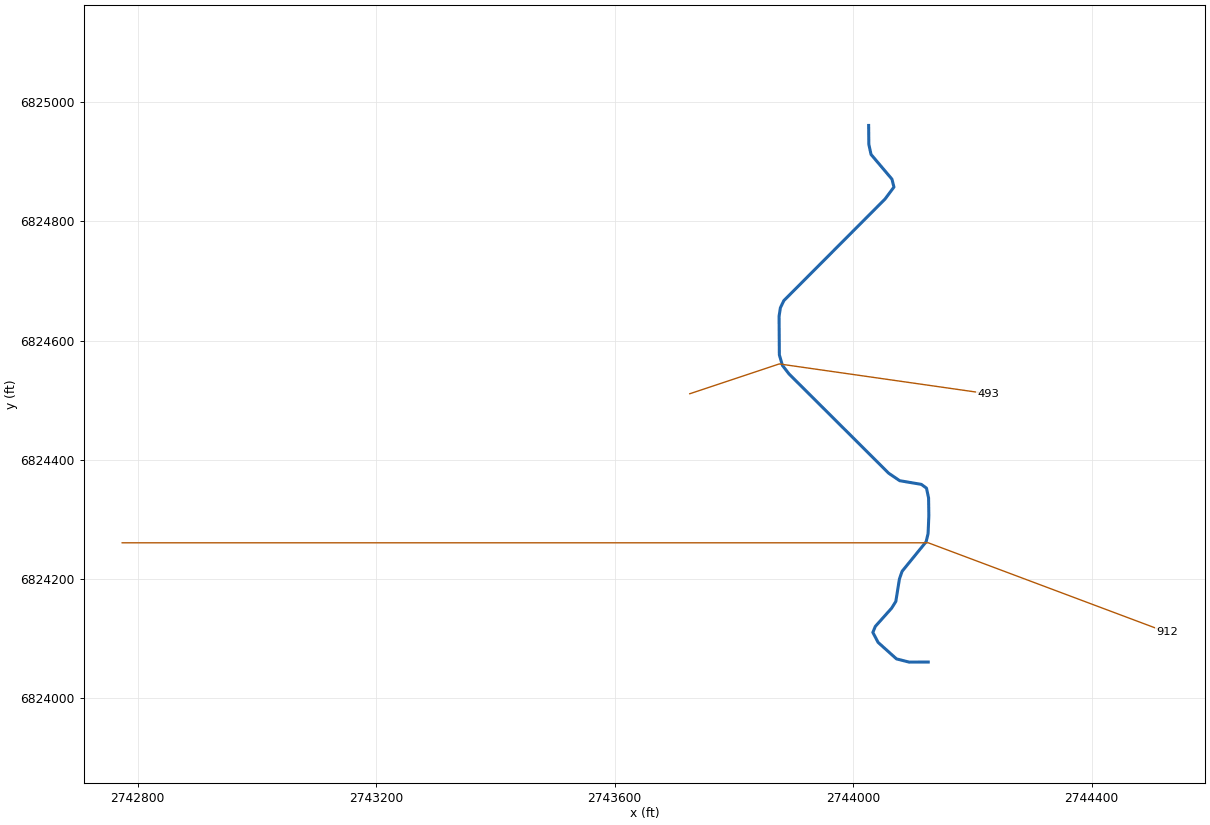
--- Twin Creek190.prj (project) ---

Proj Title=Twin Creek190 Base Level Engineering
Current Plan=p01
Default Exp/Contr=0.3,0.1
English Units
Geom File=g01
Flow File=f01
Plan File=p01
BEGIN DESCRIPTION:
Twin Creek190
END DESCRIPTION:

--- Twin Creek190.p01 (plan) ---

Plan Title=Multiple Run
Short Identifier=Multiple
Geom File=g01
Flow File=f01
Subcritical Flow
K Sum by GR= 0
Std Step Tol= 0.01
Critical Tol= 0.01
Num of Std Step Trials= 20
Max Error Tol= 0.3
Flow Tol Ratio= 0.001
Split Flow NTrial= 30
Split Flow Tol= 0.02
Split Flow Ratio= 0.02
Log Output Level= 0
Friction Slope Method= 1
Unsteady Friction Slope Method= 2
Unsteady Bridges Friction Slope Method= 1
Parabolic Critical Depth
Global Vel Dist=  1 , 1 , 1
Global Log Level= 0
CheckData=True
Encroach Param= -1, 0, 0, 0
BEGIN DESCRIPTION:
Multiple Run
END DESCRIPTION:

--- Twin Creek190.f01 (steady flow) ---

Flow Title=Multiple
Number of Profiles=7
Profile Names=10-year,25-year,50-year,1pct_min,100-year,1pct_plu,500-year
River Rch & RM= Twin Creek190,Reach-1,912
     109     130     145      81     162     323     200
Boundary for River Rch & Prof#=Twin Creek190,Reach-1,1
Up Type=0
Dn Type=3
Dn Slope=0.005
Boundary for River Rch & Prof#=Twin Creek190,Reach-1,2
Up Type=0
Dn Type=3
Dn Slope=0.005
Boundary for River Rch & Prof#=Twin Creek190,Reach-1,3
Up Type=0
Dn Type=3
Dn Slope=0.005
Boundary for River Rch & Prof#=Twin Creek190,Reach-1,4
Up Type=0
Dn Type=3
Dn Slope=0.005
Boundary for River Rch & Prof#=Twin Creek190,Reach-1,5
Up Type=0
Dn Type=3
Dn Slope=0.005
Boundary for River Rch & Prof#=Twin Creek190,Reach-1,6
Up Type=0
Dn Type=3
Dn Slope=0.005
Boundary for River Rch & Prof#=Twin Creek190,Reach-1,7
Up Type=0
Dn Type=3
Dn Slope=0.005

--- Twin Creek190.g01 (geometry) ---

Geom Title=Existing Conditions

River Reach=Twin Creek190,Reach-1
Reach XY= 30
      2744126.00      6824061.00      2744093.74      6824060.92
      2744072.65      6824066.30      2744041.81      6824093.99
      2744033.05      6824110.74      2744037.19      6824120.76
      2744064.50      6824151.29      2744071.58      6824162.62
      2744077.62      6824200.29      2744082.10      6824213.17
      2744122.36      6824262.66      2744125.69      6824276.40
      2744126.97      6824306.31      2744126.53      6824336.12
      2744123.02      6824352.66      2744114.36      6824359.00
      2744078.09      6824365.15      2744059.55      6824377.74
      2743892.40      6824544.25      2743881.40      6824558.57
      2743876.24      6824576.22      2743875.78      6824640.94
      2743877.96      6824655.11      2743883.76      6824667.17
      2744053.56      6824837.65      2744068.41      6824857.61
      2744065.11      6824870.90      2744030.02      6824912.36
      2744026.32      6824929.12      2744026.00      6824961.00

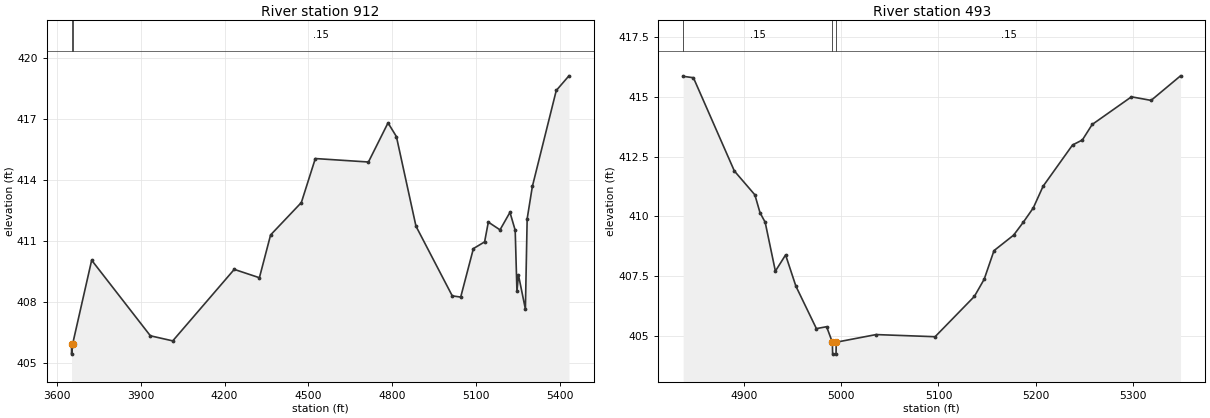
Type RM Length L Ch R = 1,912,419,419,419
BEGIN DESCRIPTION:
Twin Creek190 2.0
END DESCRIPTION:
XS GIS Cut Line= 3
      2742774.02      6824261.00      2744126.00      6824261.00
      2744526.02      6824110.99
#Sta/Elev= 30
  3652.5  405.96  3652.7  405.46  3656.5  405.96  3724.5  410.07  3934.5  406.36
  4014.5  406.11  4234.5  409.62  4324.5  409.21  4364.5  411.31  4474.5  412.90
  4524.5  415.06  4714.5  414.89  4784.5  416.81  4814.5  416.14  4884.5  411.74
  5014.3  408.32  5044.5  408.26  5089.9  410.64  5130.0  410.97  5143.3  411.94
  5185.1  411.56  5220.7  412.42  5239.4  411.54  5245.7  408.54  5251.0  409.35
  5275.9  407.67  5282.2  412.10  5300.8  413.69  5386.3  418.40  5431.7  419.12
#Mann=2,-1,0
  3652.5    0.05       0  3656.5    0.15       0
Bank Sta=3652.5,3656.5
Exp/Cntr=0.3,0.1

Type RM Length L Ch R = 1,493,0,0,0
BEGIN DESCRIPTION:
Twin Creek190 1.0
END DESCRIPTION:
XS GIS Cut Line= 3
      2743725.98      6824510.99      2743876.00      6824561.00
      2744226.01      6824511.00
#Sta/Elev= 30
  4837.3  415.87  4847.9  415.81  4890.0  411.90  4911.1  410.90  4916.4  410.15
  4921.7  409.75  4932.2  407.70  4942.7  408.38  4953.3  407.07  4974.4  405.29
  4984.9  405.37  4990.8  404.72  4991.1  404.22  4994.6  404.22  4994.8  404.72
  5035.8  405.04  5096.5  404.95  5136.9  406.64  5147.0  407.36  5157.1  408.56
  5177.3  409.21  5187.4  409.76  5197.5  410.35  5207.6  411.26  5237.9  412.99
  5248.0  413.20  5258.1  413.85  5298.5  415.01  5318.7  414.86  5349.0  415.89
#Mann=3,-1,0
  4837.3    0.15       0  4990.8    0.05       0  4994.8    0.15       0
Bank Sta=4990.8,4994.8
Exp/Cntr=0.3,0.1

Chan Stop Cuts=-1