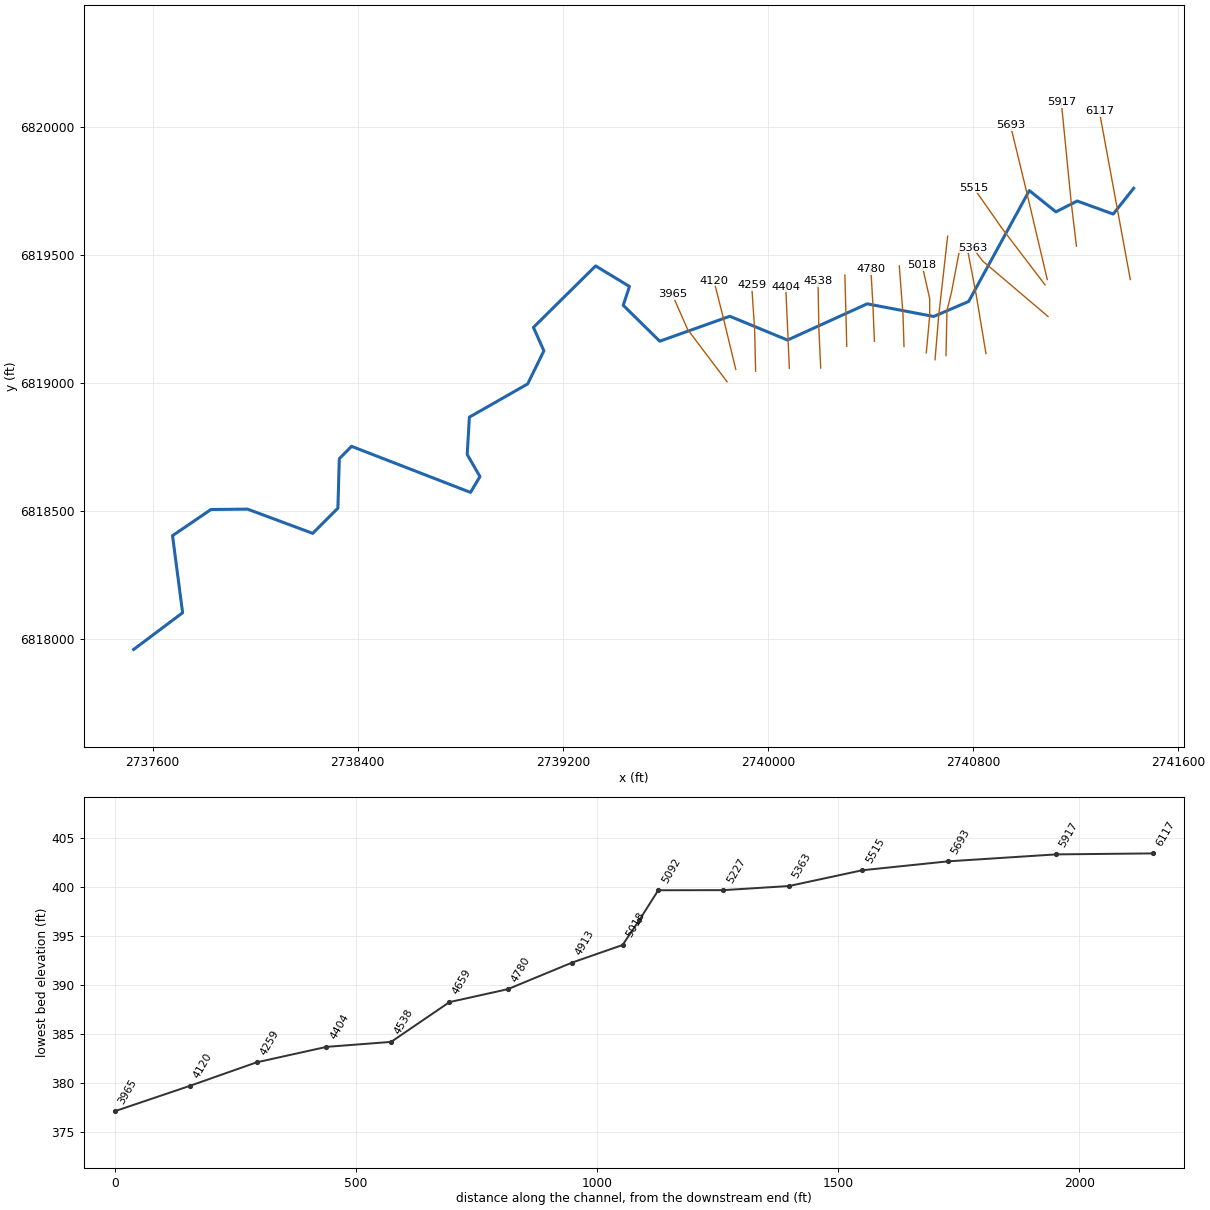
--- Twin Creek198.prj (project) ---

Proj Title=Twin Creek198 Base Level Engineering
Current Plan=p01
Default Exp/Contr=0.3,0.1
English Units
Geom File=g01
Flow File=f01
Plan File=p01
BEGIN DESCRIPTION:
Twin Creek198
END DESCRIPTION:

--- Twin Creek198.p01 (plan) ---

Plan Title=Multiple Run
Short Identifier=Multiple
Geom File=g01
Flow File=f01
Subcritical Flow
K Sum by GR= 0
Std Step Tol= 0.01
Critical Tol= 0.01
Num of Std Step Trials= 20
Max Error Tol= 0.3
Flow Tol Ratio= 0.001
Split Flow NTrial= 30
Split Flow Tol= 0.02
Split Flow Ratio= 0.02
Log Output Level= 0
Friction Slope Method= 1
Unsteady Friction Slope Method= 2
Unsteady Bridges Friction Slope Method= 1
Parabolic Critical Depth
Global Vel Dist=  1 , 1 , 1
Global Log Level= 0
CheckData=True
Encroach Param= -1, 0, 0, 0
BEGIN DESCRIPTION:
Multiple Run
END DESCRIPTION:

--- Twin Creek198.f01 (steady flow) ---

Flow Title=Multiple
Number of Profiles=7
Profile Names=10-year,25-year,50-year,1pct_min,100-year,1pct_plu,500-year
River Rch & RM= Twin Creek198,Reach-1,6117
     193     238     271     154     307     612     392
Boundary for River Rch & Prof#=Twin Creek198,Reach-1,1
Up Type=0
Dn Type=3
Dn Slope=0.005
Boundary for River Rch & Prof#=Twin Creek198,Reach-1,2
Up Type=0
Dn Type=3
Dn Slope=0.005
Boundary for River Rch & Prof#=Twin Creek198,Reach-1,3
Up Type=0
Dn Type=3
Dn Slope=0.005
Boundary for River Rch & Prof#=Twin Creek198,Reach-1,4
Up Type=0
Dn Type=3
Dn Slope=0.005
Boundary for River Rch & Prof#=Twin Creek198,Reach-1,5
Up Type=0
Dn Type=3
Dn Slope=0.005
Boundary for River Rch & Prof#=Twin Creek198,Reach-1,6
Up Type=0
Dn Type=3
Dn Slope=0.005
Boundary for River Rch & Prof#=Twin Creek198,Reach-1,7
Up Type=0
Dn Type=3
Dn Slope=0.005

--- Twin Creek198.g01 (geometry) ---

Geom Title=Existing Conditions

River Reach=Twin Creek198,Reach-1
Reach XY= 30
      2741426.00      6819761.00      2741346.13      6819660.30
      2741205.79      6819711.21      2741122.59      6819668.85
      2741019.05      6819752.15      2740782.38      6819319.00
      2740646.14      6819260.60      2740386.54      6819309.91
      2740076.00      6819168.56      2739851.00      6819261.40
      2739577.63      6819164.13      2739435.30      6819304.33
      2739459.62      6819377.71      2739327.65      6819457.90
      2739085.08      6819218.00      2739125.86      6819126.41
      2739062.56      6818997.37      2738835.29      6818867.69
      2738826.83      6818721.70      2738876.52      6818635.86
      2738839.71      6818573.98      2738375.67      6818753.82
      2738328.05      6818705.55      2738322.47      6818512.45
      2738224.38      6818414.12      2737970.06      6818508.75
      2737827.56      6818507.26      2737677.55      6818405.15
      2737716.86      6818104.25      2737526.00      6817961.00

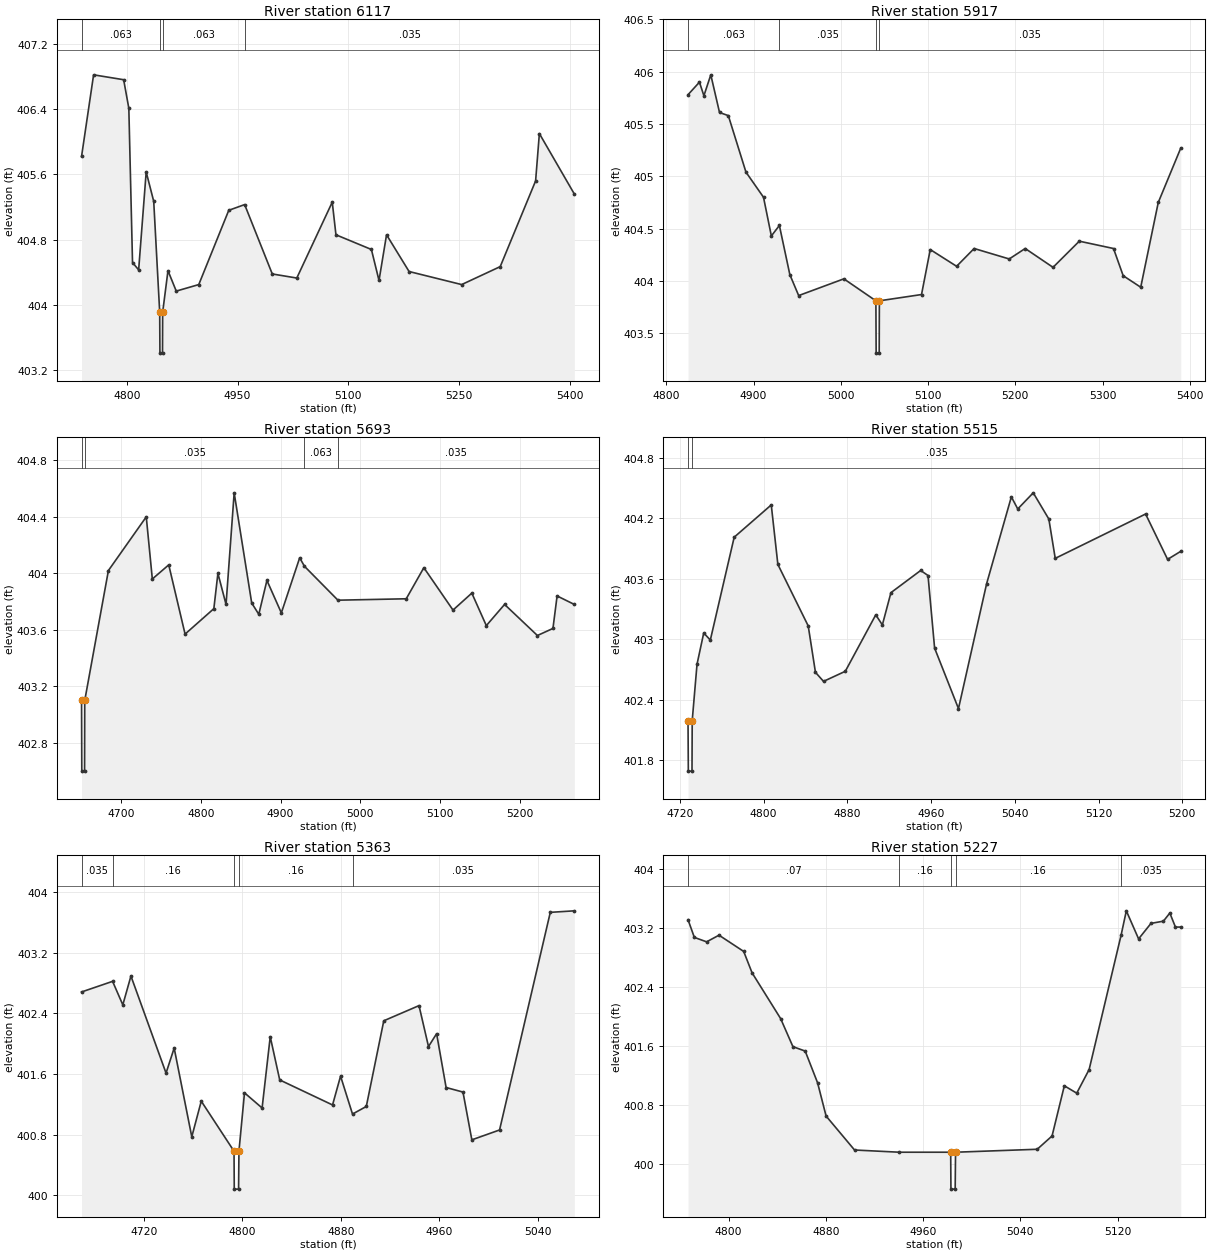
Type RM Length L Ch R = 1,6117,200,200,200
BEGIN DESCRIPTION:
Twin Creek1986116.768
END DESCRIPTION:
XS GIS Cut Line= 3
      2741412.91      6819404.95      2741365.65      6819661.83
      2741292.17      6820061.03
#Sta/Elev= 30
  4738.8  405.82  4755.1  406.82  4795.8  406.76  4802.8  406.41  4807.8  404.52
  4816.1  404.43  4826.3  405.63  4836.5  405.27  4844.6  403.91  4844.9  403.41
  4848.4  403.41  4848.6  403.91  4855.8  404.42  4867.0  404.17  4897.5  404.25
  4938.1  405.16  4959.6  405.23  4997.0  404.38  5030.2  404.33  5078.2  405.26
  5083.2  404.86  5131.2  404.68  5141.5  404.30  5151.7  404.86  5182.2  404.41
  5253.4  404.25  5305.6  404.47  5353.5  405.52  5358.6  406.10  5405.9  405.36
#Mann=4,-1,0
  4738.8   0.063       0  4844.6   0.035       0  4848.6   0.063       0
  4959.6   0.035       0
Bank Sta=4844.6,4848.6
Exp/Cntr=0.3,0.1

Type RM Length L Ch R = 1,5917,224,224,224
BEGIN DESCRIPTION:
Twin Creek1985920.24
END DESCRIPTION:
XS GIS Cut Line= 3
      2741202.81      6819535.11      2741182.03      6819708.97
      2741143.83      6820096.69
#Sta/Elev= 30
  4824.9  405.78  4838.0  405.90  4843.1  405.77  4851.0  405.97  4861.0  405.61
  4871.1  405.58  4891.3  405.04  4911.4  404.80  4920.4  404.43  4929.6  404.53
  4941.6  404.06  4951.7  403.86  5003.5  404.02  5040.2  403.81  5040.5  403.31
  5044.0  403.31  5044.2  403.81  5092.5  403.87  5102.5  404.30  5132.7  404.14
  5152.8  404.31  5193.0  404.21  5211.3  404.31  5243.2  404.13  5273.3  404.38
  5312.5  404.31  5323.6  404.05  5343.7  403.94  5363.8  404.75  5389.6  405.27
#Mann=4,-1,0
  4824.9   0.063       0  4929.6   0.035       0  5040.2   0.035       0
  5044.2   0.035       0
Bank Sta=5040.2,5044.2
Exp/Cntr=0.3,0.1

Type RM Length L Ch R = 1,5693,178,178,178
BEGIN DESCRIPTION:
Twin Creek1985686.81
END DESCRIPTION:
XS GIS Cut Line= 3
      2741089.03      6819404.55      2741008.96      6819744.96
      2740945.66      6820005.99
#Sta/Elev= 30
  4650.3  403.10  4650.6  402.60  4654.1  402.60  4654.3  403.10  4684.0  404.02
  4731.5  404.40  4739.1  403.96  4759.7  404.06  4780.2  403.57  4816.3  403.75
  4821.4  404.00  4831.6  403.78  4841.8  404.57  4863.8  403.79  4872.7  403.71
  4882.9  403.95  4901.0  403.72  4924.0  404.11  4930.0  404.05  4972.0  403.81
  5057.7  403.82  5079.8  404.04  5116.4  403.74  5140.0  403.86  5158.2  403.63
  5181.1  403.78  5222.3  403.56  5241.8  403.61  5247.0  403.84  5268.6  403.78
#Mann=4,-1,0
  4650.3   0.035       0  4654.3   0.035       0  4930.0   0.063       0
  4972.0   0.035       0
Bank Sta=4650.3,4654.3
Exp/Cntr=0.3,0.1

Type RM Length L Ch R = 1,5515,152,152,152
BEGIN DESCRIPTION:
Twin Creek1985514.17
END DESCRIPTION:
XS GIS Cut Line= 3
      2741080.17      6819384.13      2740912.19      6819605.01
      2740801.68      6819763.36
#Sta/Elev= 30
  4727.9  402.19  4728.2  401.69  4731.7  401.69  4731.9  402.19  4736.5  402.75
  4742.9  403.06  4749.2  402.99  4772.0  404.01  4807.4  404.33  4813.7  403.74
  4842.7  403.13  4849.6  402.67  4857.3  402.58  4878.1  402.68  4907.2  403.24
  4913.5  403.14  4921.7  403.46  4950.1  403.68  4957.1  403.63  4963.4  402.91
  4986.2  402.31  5013.1  403.55  5036.7  404.41  5042.8  404.29  5057.6  404.45
  5072.5  404.19  5078.6  403.80  5164.9  404.24  5185.9  403.79  5198.5  403.87
#Mann=2,-1,0
  4727.9   0.035       0  4731.9   0.035       0
Bank Sta=4727.9,4731.9
Exp/Cntr=0.3,0.1

Type RM Length L Ch R = 1,5363,136,136,136
BEGIN DESCRIPTION:
Twin Creek1985362.83
END DESCRIPTION:
XS GIS Cut Line= 3
      2741092.04      6819260.49      2740837.33      6819476.81
      2740797.55      6819529.38
#Sta/Elev= 30
  4669.4  402.68  4694.6  402.82  4702.9  402.51  4709.5  402.89  4738.0  401.61
  4744.6  401.94  4758.9  400.77  4766.6  401.24  4793.2  400.58  4793.4  400.08
  4796.9  400.08  4797.2  400.58  4801.7  401.35  4816.0  401.15  4822.6  402.09
  4830.3  401.52  4873.2  401.19  4879.7  401.57  4889.4  401.07  4900.6  401.17
  4914.8  402.30  4943.4  402.50  4951.1  401.96  4957.7  402.13  4965.4  401.42
  4979.1  401.36  4986.3  400.73  5008.8  400.86  5050.0  403.73  5069.5  403.75
#Mann=5,-1,0
  4669.4   0.035       0  4694.6    0.16       0  4793.2   0.035       0
  4797.2    0.16       0  4889.4   0.035       0
Bank Sta=4793.2,4797.2
Exp/Cntr=0.3,0.1

Type RM Length L Ch R = 1,5227,135,135,135
BEGIN DESCRIPTION:
Twin Creek1985227.03
END DESCRIPTION:
XS GIS Cut Line= 3
      2740849.96      6819115.87      2740811.22      6819348.73
      2740779.34      6819515.04
#Sta/Elev= 30
  4766.6  403.31  4771.8  403.07  4781.9  403.01  4792.1  403.10  4812.4  402.88
  4819.3  402.59  4842.8  401.97  4852.9  401.59  4863.0  401.53  4873.2  401.10
  4880.2  400.65  4903.6  400.19  4940.5  400.16  4982.7  400.16  4982.9  399.66
  4986.4  399.66  4986.7  400.16  5053.9  400.20  5066.1  400.38  5076.2  401.06
  5086.4  400.96  5096.6  401.28  5122.9  403.10  5127.2  403.43  5137.3  403.05
  5147.5  403.26  5157.7  403.29  5163.0  403.40  5167.6  403.21  5172.0  403.21
#Mann=5,-1,0
  4766.6    0.07       0  4940.5    0.16       0  4982.7    0.07       0
  4986.7    0.16       0  5122.9   0.035       0
Bank Sta=4982.7,4986.7
Exp/Cntr=0.3,0.1

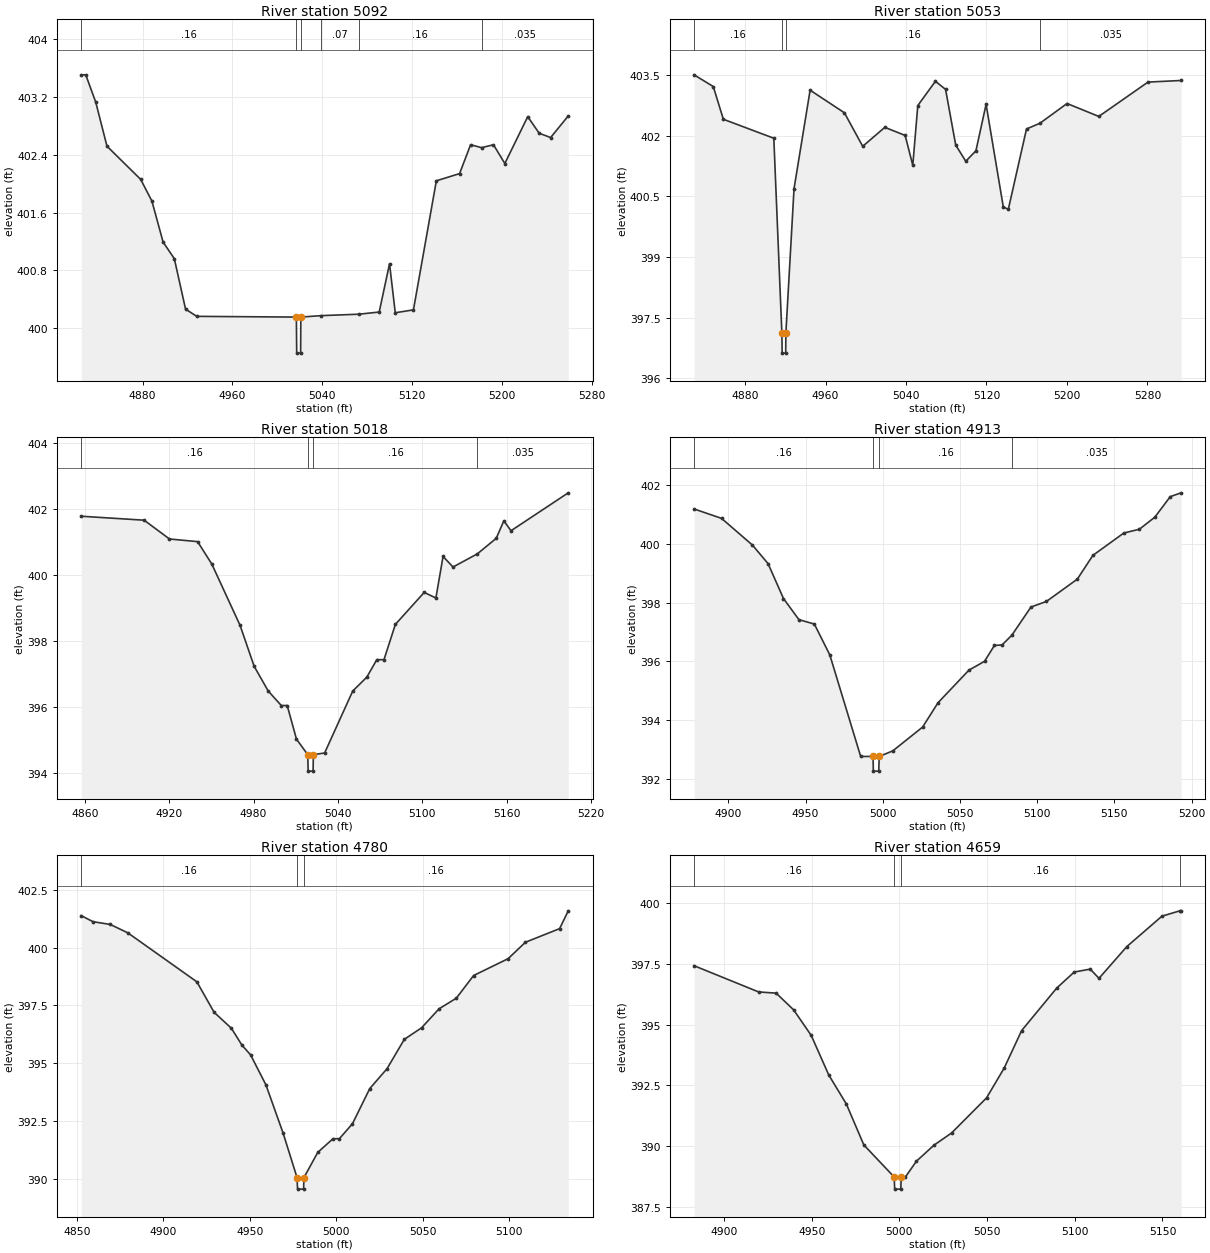
Type RM Length L Ch R = 1,5092,39,39,39
BEGIN DESCRIPTION:
Twin Creek1985091.83
END DESCRIPTION:
XS GIS Cut Line= 4
      2740694.16      6819108.11      2740697.77      6819283.28
      2740715.20      6819353.83      2740750.00      6819536.46
#Sta/Elev= 30
  4825.4  403.51  4829.4  403.51  4838.3  403.13  4848.3  402.52  4878.3  402.06
  4888.3  401.76  4898.3  401.19  4908.3  400.96  4918.3  400.26  4928.3  400.16
  5017.0  400.15  5017.3  399.65  5020.8  399.65  5021.0  400.15  5039.0  400.17
  5072.8  400.19  5090.8  400.22  5100.0  400.89  5105.1  400.21  5121.3  400.25
  5141.7  402.04  5162.4  402.14  5172.2  402.54  5182.0  402.50  5192.6  402.54
  5202.7  402.28  5223.1  402.93  5233.3  402.70  5243.5  402.64  5259.2  402.94
#Mann=6,-1,0
  4825.4    0.16       0  5017.0    0.07       0  5021.0    0.16       0
  5039.0    0.07       0  5072.8    0.16       0  5182.0   0.035       0
Bank Sta=5017,5021
Exp/Cntr=0.3,0.1

Type RM Length L Ch R = 1,5053,35,35,35
BEGIN DESCRIPTION:
Twin Creek1985052.78
END DESCRIPTION:
XS GIS Cut Line= 3
      2740651.36      6819091.97      2740665.50      6819262.19
      2740700.53      6819573.72
#Sta/Elev= 30
  4829.2  403.51  4848.3  403.22  4858.3  402.41  4908.5  401.94  4916.5  397.12
  4916.8  396.62  4920.3  396.62  4920.5  397.12  4928.6  400.69  4944.6  403.13
  4978.7  402.57  4996.9  401.74  5018.9  402.21  5039.1  402.01  5046.7  401.27
  5051.7  402.75  5069.2  403.35  5079.3  403.15  5089.4  401.77  5099.4  401.37
  5109.5  401.63  5119.6  402.78  5136.7  400.24  5141.7  400.18  5159.8  402.17
  5173.1  402.31  5200.1  402.80  5231.7  402.48  5280.6  403.33  5313.5  403.37
#Mann=4,-1,0
  4829.2    0.16       0  4916.5    0.07       0  4920.5    0.16       0
  5173.1   0.035       0
Bank Sta=4916.5,4920.5
Exp/Cntr=0.3,0.1

Type RM Length L Ch R = 1,5018,105,105,105
BEGIN DESCRIPTION:
Twin Creek1985017.63
END DESCRIPTION:
XS GIS Cut Line= 4
      2740617.17      6819118.61      2740630.60      6819264.36
      2740630.50      6819330.17      2740600.97      6819460.90
#Sta/Elev= 30
  4857.5  401.79  4902.2  401.67  4920.2  401.10  4940.2  401.02  4950.3  400.34
  4970.4  398.48  4980.4  397.24  4990.4  396.49  4999.7  396.05  5003.9  396.05
  5010.5  395.03  5018.5  394.56  5018.8  394.06  5022.3  394.06  5022.5  394.56
  5030.5  394.61  5050.5  396.49  5060.5  396.91  5067.6  397.44  5072.7  397.44
  5080.8  398.51  5101.3  399.48  5109.6  399.31  5114.7  400.57  5121.8  400.25
  5139.1  400.65  5152.5  401.12  5157.9  401.65  5163.0  401.35  5203.7  402.50
#Mann=4,-1,0
  4857.5    0.16       0  5018.5    0.07       0  5022.5    0.16       0
  5139.1   0.035       0
Bank Sta=5018.5,5022.5
Exp/Cntr=0.3,0.1

Type RM Length L Ch R = 1,4913,133,133,133
BEGIN DESCRIPTION:
Twin Creek1984913.3
END DESCRIPTION:
XS GIS Cut Line= 3
      2740530.32      6819143.17      2740526.44      6819267.52
      2740511.90      6819457.95
#Sta/Elev= 30
  4877.8  401.19  4895.6  400.87  4915.6  399.96  4925.7  399.33  4935.7  398.14
  4945.7  397.42  4955.7  397.27  4965.7  396.22  4985.7  392.76  4993.7  392.76
  4993.9  392.26  4997.4  392.26  4997.7  392.76  5006.5  392.95  5025.8  393.76
  5035.8  394.59  5055.8  395.70  5065.9  396.00  5072.3  396.54  5077.3  396.56
  5083.6  396.89  5096.0  397.85  5106.0  398.04  5126.0  398.80  5136.1  399.61
  5156.1  400.37  5166.2  400.50  5176.2  400.91  5186.2  401.61  5193.2  401.74
#Mann=4,-1,0
  4877.8    0.16       0  4993.7    0.07       0  4997.7    0.16       0
  5083.6   0.035       0
Bank Sta=4993.7,4997.7
Exp/Cntr=0.3,0.1

Type RM Length L Ch R = 1,4780,121,121,121
BEGIN DESCRIPTION:
Twin Creek1984779.92
END DESCRIPTION:
XS GIS Cut Line= 3
      2740414.97      6819164.17      2740408.66      6819313.43
      2740400.98      6819445.72
#Sta/Elev= 30
  4852.4  401.38  4859.2  401.12  4869.2  401.00  4879.3  400.64  4919.3  398.52
  4929.3  397.20  4939.3  396.51  4945.4  395.78  4950.4  395.36  4959.3  394.06
  4969.3  391.96  4977.3  390.05  4977.6  389.55  4981.1  389.55  4981.3  390.05
  4989.3  391.14  4998.1  391.73  5001.8  391.73  5009.4  392.38  5019.4  393.90
  5029.4  394.76  5039.4  396.03  5049.4  396.53  5059.5  397.35  5069.5  397.81
  5079.5  398.79  5099.5  399.52  5109.5  400.23  5129.3  400.82  5134.3  401.59
#Mann=3,-1,0
  4852.4    0.16       0  4977.3    0.07       0  4981.3    0.16       0
Bank Sta=4977.3,4981.3
Exp/Cntr=0.3,0.1

Type RM Length L Ch R = 1,4659,121,121,121
BEGIN DESCRIPTION:
Twin Creek1984659.36
END DESCRIPTION:
XS GIS Cut Line= 3
      2740306.88      6819144.24      2740304.01      6819264.68
      2740299.69      6819421.85
#Sta/Elev= 27
  4882.9  397.43  4919.7  396.35  4929.7  396.30  4939.7  395.61  4949.7  394.56
  4959.7  392.93  4969.7  391.74  4979.7  390.05  4997.0  388.73  4997.3  388.23
  5000.8  388.23  5001.0  388.73  5003.4  388.73  5009.7  389.38  5019.7  390.04
  5029.7  390.54  5049.7  391.99  5059.7  393.21  5069.7  394.76  5089.7  396.51
  5099.7  397.17  5108.8  397.29  5113.8  396.91  5129.7  398.22  5149.7  399.47
  5159.9  399.69  5160.6  399.69
#Mann=4,-1,0
  4882.9    0.16       0  4997.0    0.07       0  5001.0    0.16       0
  5159.9   0.035       0
Bank Sta=4997,5001
Exp/Cntr=0.3,0.1

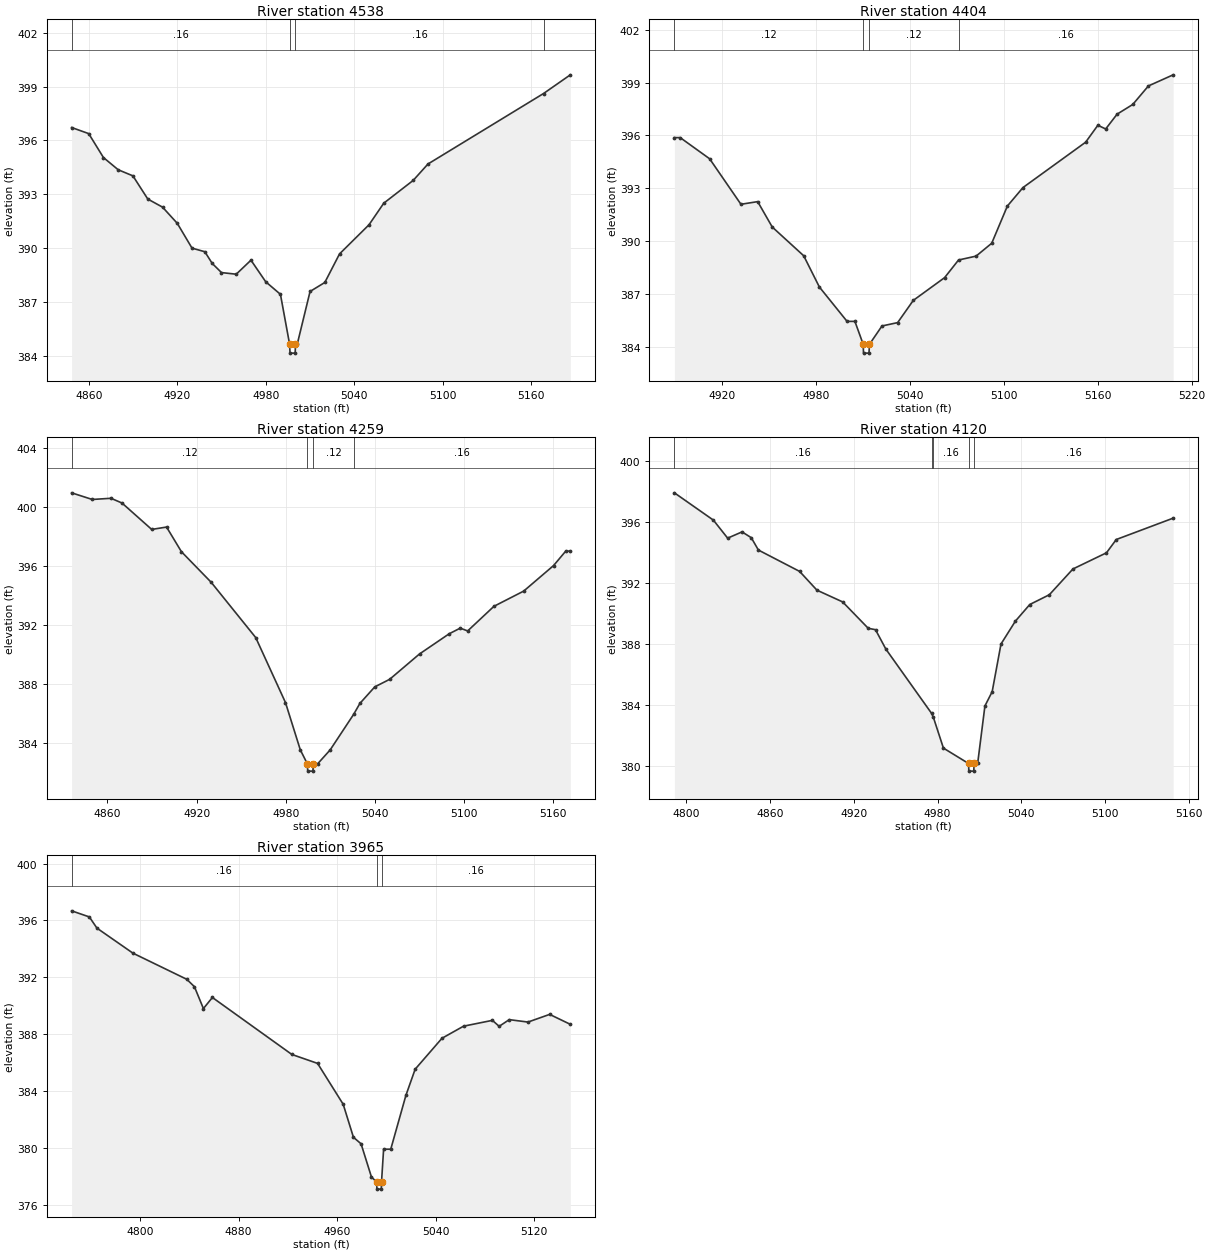
Type RM Length L Ch R = 1,4538,134,134,134
BEGIN DESCRIPTION:
Twin Creek1984537.76
END DESCRIPTION:
XS GIS Cut Line= 3
      2740205.41      6819059.41      2740198.24      6819212.29
      2740195.00      6819397.61
#Sta/Elev= 30
  4848.3  396.72  4859.9  396.38  4869.9  395.05  4879.9  394.37  4889.9  394.03
  4900.0  392.74  4910.0  392.29  4920.0  391.39  4930.0  390.01  4938.7  389.81
  4943.7  389.16  4950.0  388.65  4960.0  388.56  4970.0  389.34  4980.0  388.14
  4990.0  387.44  4996.2  384.67  4996.5  384.17  5000.0  384.17  5000.2  384.67
  5001.4  384.67  5010.1  387.60  5020.1  388.10  5030.1  389.69  5050.1  391.31
  5060.1  392.51  5080.1  393.78  5090.1  394.69  5168.5  398.61  5186.7  399.65
#Mann=4,-1,0
  4848.3    0.16       0  4996.2    0.07       0  5000.2    0.16       0
  5168.5   0.035       0
Bank Sta=4996.2,5000.2
Exp/Cntr=0.3,0.1

Type RM Length L Ch R = 1,4404,145,145,145
BEGIN DESCRIPTION:
Twin Creek1984403.85
END DESCRIPTION:
XS GIS Cut Line= 3
      2740083.12      6819058.53      2740078.23      6819171.42
      2740068.95      6819376.81
#Sta/Elev= 30
  4889.5  395.88  4893.2  395.88  4912.0  394.68  4932.0  392.10  4942.7  392.25
  4952.0  390.81  4972.1  389.18  4982.1  387.41  4999.8  385.46  5004.8  385.46
  5010.1  384.16  5010.3  383.66  5013.8  383.66  5014.1  384.16  5022.1  385.20
  5032.1  385.39  5042.1  386.65  5062.1  387.94  5071.0  388.94  5082.2  389.16
  5092.2  389.89  5102.2  392.00  5112.2  393.05  5152.2  395.62  5160.0  396.58
  5165.0  396.37  5172.3  397.21  5182.3  397.76  5192.3  398.81  5208.1  399.44
#Mann=4,-1,0
  4889.5    0.12       0  5010.1    0.07       0  5014.1    0.12       0
  5071.0    0.16       0
Bank Sta=5010.1,5014.1
Exp/Cntr=0.3,0.1

Type RM Length L Ch R = 1,4259,139,139,139
BEGIN DESCRIPTION:
Mapping XS 7c43e98f
END DESCRIPTION:
XS GIS Cut Line= 3
      2739951.57      6819047.12      2739947.71      6819209.41
      2739936.25      6819382.29
#Sta/Elev= 30
  4835.9  400.94  4849.8  400.49  4862.4  400.57  4869.8  400.25  4889.8  398.46
  4899.8  398.62  4909.8  396.95  4929.8  394.88  4959.8  391.13  4979.8  386.73
  4989.8  383.52  4994.5  382.58  4994.8  382.08  4998.3  382.08  4998.5  382.58
  5001.5  382.58  5009.9  383.52  5025.7  385.93  5029.9  386.67  5039.9  387.79
  5049.9  388.30  5070.0  390.02  5090.0  391.39  5097.4  391.77  5102.4  391.58
  5120.1  393.25  5140.1  394.28  5160.2  396.01  5168.4  396.99  5171.5  396.99
#Mann=4,-1,0
  4835.9    0.12       0  4994.5    0.07       0  4998.5    0.12       0
  5025.7    0.16       0
Bank Sta=4994.5,4998.5
Exp/Cntr=0.3,0.1

Type RM Length L Ch R = 1,4120,155,155,155
BEGIN DESCRIPTION:
Mapping XS d7c17ad7
END DESCRIPTION:
XS GIS Cut Line= 3
      2739874.24      6819053.92      2739823.28      6819264.90
      2739788.82      6819400.44
#Sta/Elev= 30
  4791.7  397.91  4819.6  396.12  4829.8  394.94  4840.1  395.35  4846.7  394.97
  4851.8  394.16  4881.3  392.76  4893.7  391.53  4912.1  390.76  4930.4  389.03
  4935.6  388.94  4943.0  387.67  4975.7  383.46  4977.0  383.20  4984.2  381.18
  5002.2  380.17  5002.4  379.67  5005.9  379.67  5006.2  380.17  5008.7  380.17
  5013.9  383.94  5019.1  384.88  5025.4  388.00  5035.7  389.50  5046.0  390.59
  5060.0  391.23  5076.9  392.92  5100.9  393.98  5107.9  394.85  5148.6  396.25
#Mann=5,-1,0
  4791.7    0.16       0  4975.7    0.12       0  4977.0    0.16       0
  5002.2    0.07       0  5006.2    0.16       0
Bank Sta=5002.2,5006.2
Exp/Cntr=0.3,0.1

Type RM Length L Ch R = 1,3965,0,0,0
BEGIN DESCRIPTION:
Twin Creek1984260.96
END DESCRIPTION:
XS GIS Cut Line= 3
      2739840.44      6819005.57      2739686.54      6819209.65
      2739626.71      6819346.43
#Sta/Elev= 30
  4744.4  396.68  4758.8  396.25  4765.0  395.46  4794.2  393.70  4837.9  391.86
  4844.1  391.34  4851.4  389.80  4858.7  390.58  4923.2  386.57  4944.1  385.94
  4964.9  383.06  4973.2  380.74  4979.4  380.28  4987.8  377.95  4992.0  377.59
  4992.3  377.09  4995.8  377.09  4996.0  377.59  4997.7  379.90  5003.5  379.90
  5015.8  383.69  5023.3  385.53  5045.1  387.71  5062.6  388.56  5086.0  388.97
  5091.5  388.55  5099.7  389.02  5114.9  388.85  5132.5  389.39  5149.3  388.69
#Mann=3,-1,0
  4744.4    0.16       0  4992.0    0.07       0  4996.0    0.16       0
Bank Sta=4992,4996
Exp/Cntr=0.3,0.1

Chan Stop Cuts=-1