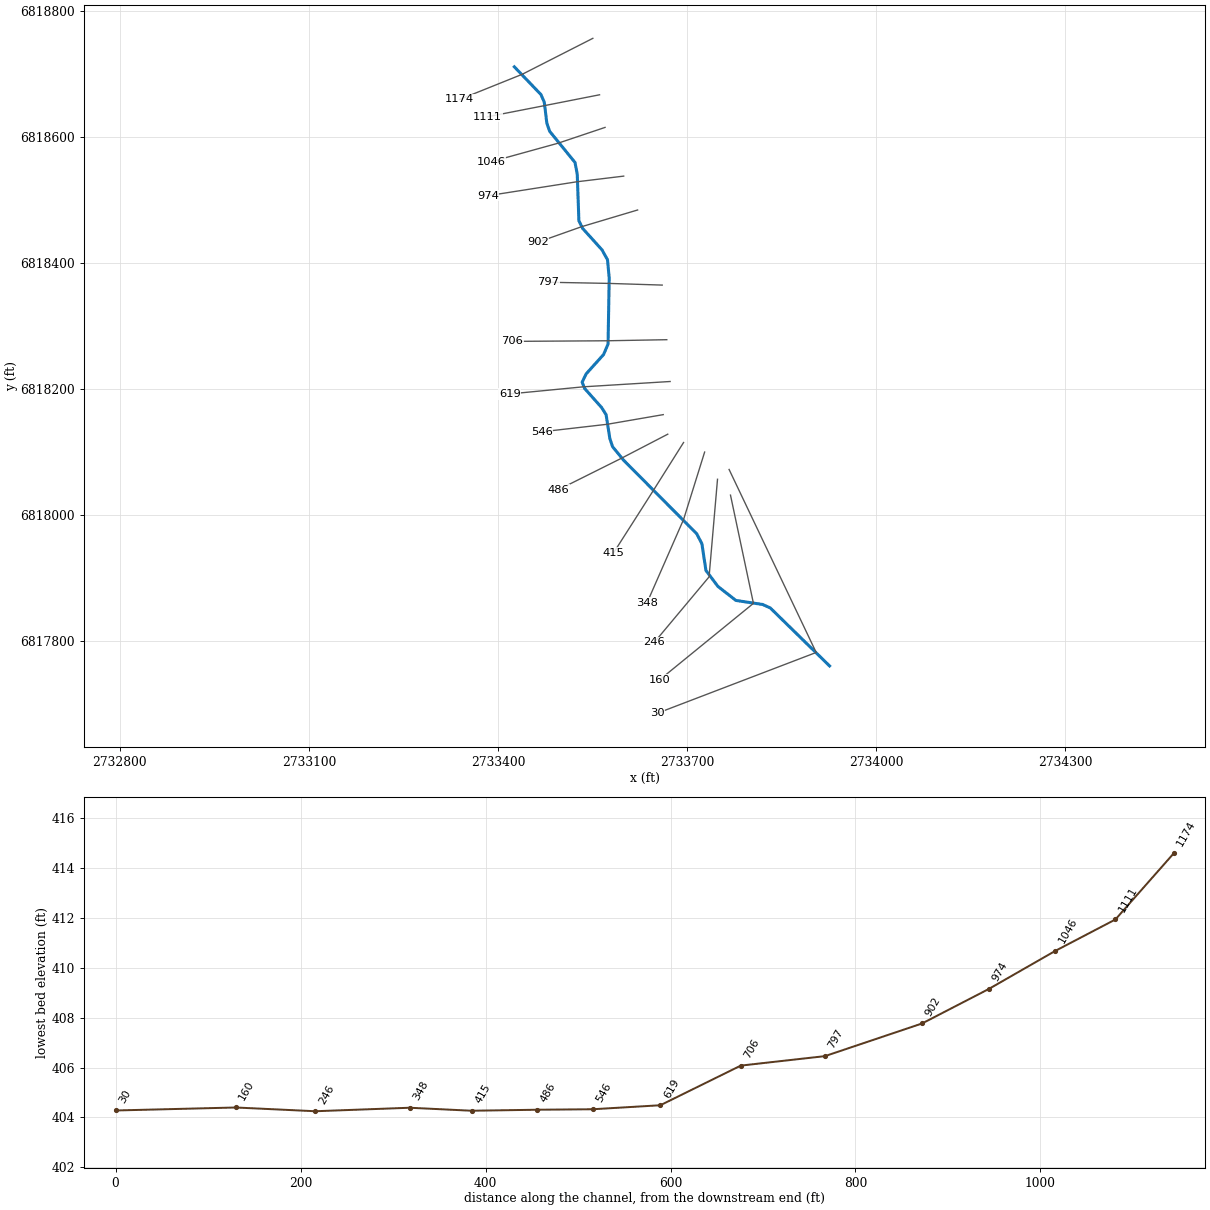
--- Twin Creek199.prj (project) ---

Proj Title=Twin Creek199 Base Level Engineering
Current Plan=p01
Default Exp/Contr=0.3,0.1
English Units
Geom File=g01
Flow File=f01
Plan File=p01
BEGIN DESCRIPTION:
Twin Creek199
END DESCRIPTION:

--- Twin Creek199.p01 (plan) ---

Plan Title=Multiple Run
Short Identifier=Multiple
Geom File=g01
Flow File=f01
Subcritical Flow
K Sum by GR= 0
Std Step Tol= 0.01
Critical Tol= 0.01
Num of Std Step Trials= 20
Max Error Tol= 0.3
Flow Tol Ratio= 0.001
Split Flow NTrial= 30
Split Flow Tol= 0.02
Split Flow Ratio= 0.02
Log Output Level= 0
Friction Slope Method= 1
Unsteady Friction Slope Method= 2
Unsteady Bridges Friction Slope Method= 1
Parabolic Critical Depth
Global Vel Dist=  1 , 1 , 1
Global Log Level= 0
CheckData=True
Encroach Param= -1, 0, 0, 0
BEGIN DESCRIPTION:
Multiple Run
END DESCRIPTION:

--- Twin Creek199.f01 (steady flow) ---

Flow Title=Multiple
Number of Profiles=7
Profile Names=10-year,25-year,50-year,1pct_min,100-year,1pct_plu,500-year
River Rch & RM= Twin Creek199,Reach-1,1174
      64      73      79      43      86     171      99
River Rch & RM= Twin Creek199,Reach-1,30
     308     394     461     268     535    1067     718
Boundary for River Rch & Prof#=Twin Creek199,Reach-1,1
Up Type=0
Dn Type=3
Dn Slope=0.005
Boundary for River Rch & Prof#=Twin Creek199,Reach-1,2
Up Type=0
Dn Type=3
Dn Slope=0.005
Boundary for River Rch & Prof#=Twin Creek199,Reach-1,3
Up Type=0
Dn Type=3
Dn Slope=0.005
Boundary for River Rch & Prof#=Twin Creek199,Reach-1,4
Up Type=0
Dn Type=3
Dn Slope=0.005
Boundary for River Rch & Prof#=Twin Creek199,Reach-1,5
Up Type=0
Dn Type=3
Dn Slope=0.005
Boundary for River Rch & Prof#=Twin Creek199,Reach-1,6
Up Type=0
Dn Type=3
Dn Slope=0.005
Boundary for River Rch & Prof#=Twin Creek199,Reach-1,7
Up Type=0
Dn Type=3
Dn Slope=0.005

--- Twin Creek199.g01 (geometry) ---

Geom Title=Existing Conditions

River Reach=Twin Creek199,Reach-1
Reach XY= 30
      2733426.00      6818711.00      2733468.09      6818667.15
      2733473.49      6818654.96      2733477.51      6818621.63
      2733482.03      6818608.78      2733522.18      6818559.42
      2733525.77      6818540.91      2733528.36      6818466.98
      2733534.19      6818454.97      2733565.16      6818420.65
      2733573.75      6818405.06      2733576.47      6818376.16
      2733574.63      6818271.44      2733567.55      6818254.82
      2733539.94      6818224.20      2733533.53      6818210.99
      2733537.42      6818201.07      2733564.49      6818170.67
      2733571.55      6818159.35      2733577.45      6818121.64
      2733581.81      6818108.71      2733599.00      6818087.54
      2733715.21      6817970.66      2733723.45      6817954.91
      2733729.89      6817912.43      2733748.86      6817887.16
      2733777.43      6817864.87      2733819.92      6817858.46
      2733832.05      6817852.88      2733926.00      6817761.00

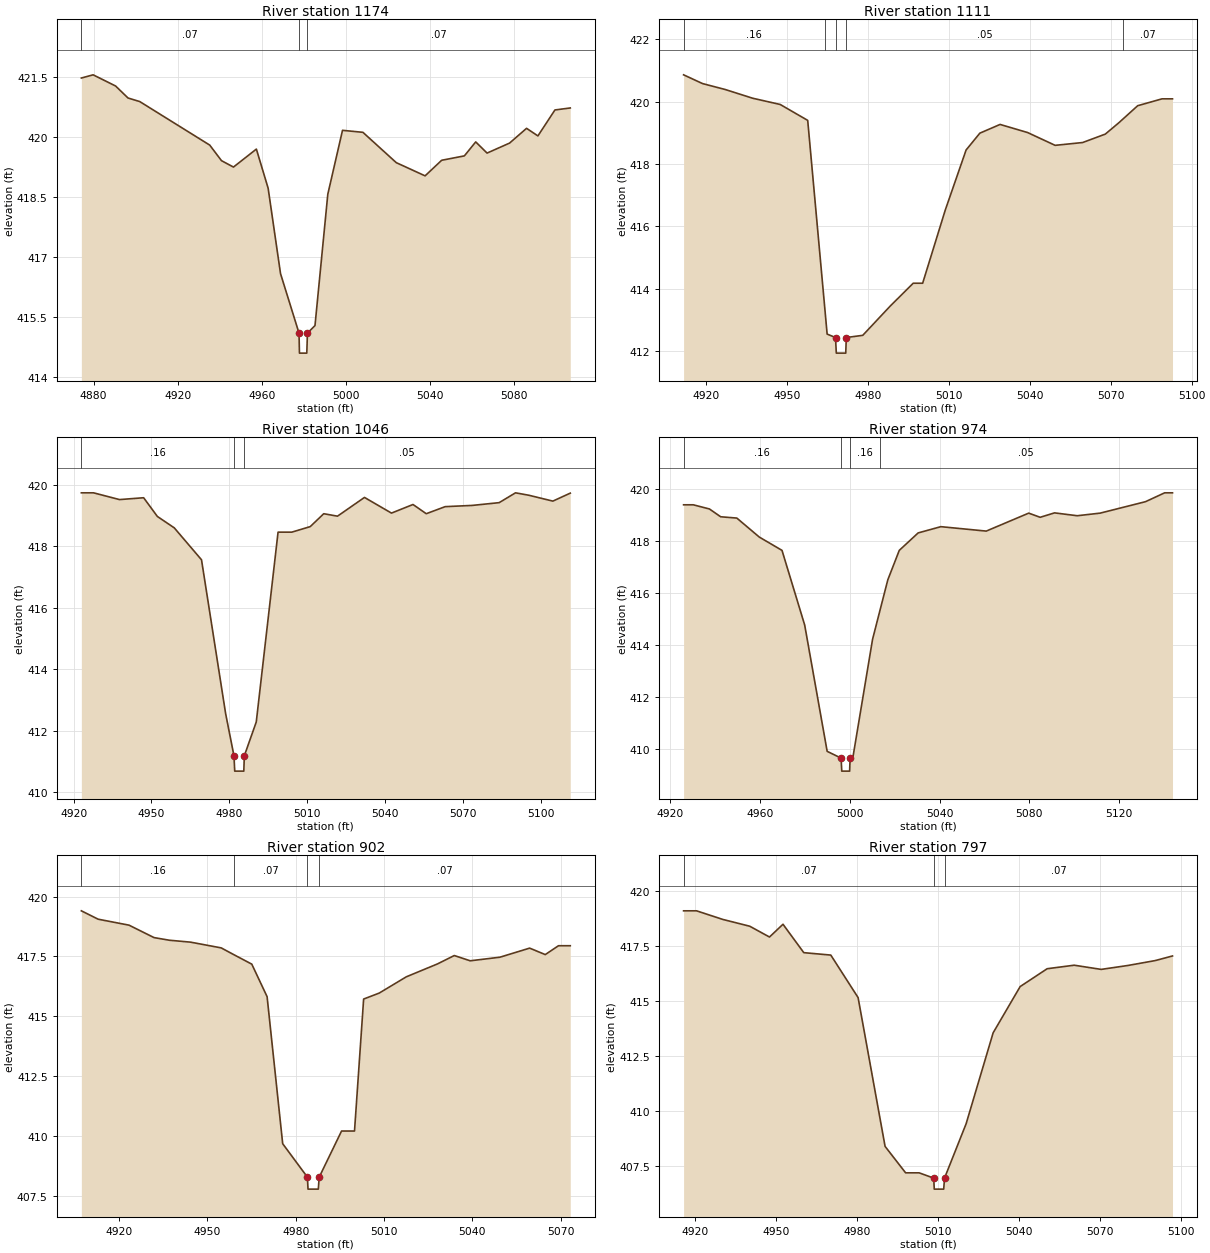
Type RM Length L Ch R = 1,1174,63,63,63
BEGIN DESCRIPTION:
Twin Creek1991173.619
END DESCRIPTION:
XS GIS Cut Line= 3
      2733550.50      6818756.21      2733438.39      6818699.15
      2733339.21      6818659.25
#Sta/Elev= 30
  4874.2  421.48  4879.8  421.56  4890.5  421.28  4896.4  420.98  4902.0  420.89
  4935.3  419.80  4940.9  419.41  4946.6  419.25  4957.5  419.70  4963.1  418.72
  4969.0  416.58  4977.8  415.09  4978.0  414.59  4981.5  414.59  4981.8  415.09
  4985.4  415.28  4991.5  418.57  4998.5  420.17  5008.2  420.12  5024.1  419.36
  5037.8  419.03  5045.7  419.42  5056.5  419.53  5061.9  419.88  5067.3  419.60
  5078.0  419.85  5086.1  420.22  5091.5  420.03  5099.6  420.68  5106.9  420.73
#Mann=3,-1,0
  4874.2    0.07       0  4977.8    0.07       0  4981.8    0.07       0
Bank Sta=4977.8,4981.8
Exp/Cntr=0.3,0.1

Type RM Length L Ch R = 1,1111,65,65,65
BEGIN DESCRIPTION:
Twin Creek1991111.07
END DESCRIPTION:
XS GIS Cut Line= 3
      2733561.14      6818666.70      2733474.23      6818649.59
      2733383.32      6818631.85
#Sta/Elev= 29
  4911.7  420.86  4918.7  420.58  4927.1  420.39  4937.3  420.11  4947.5  419.91
  4957.7  419.40  4964.0  413.41  4964.9  412.55  4968.0  412.44  4968.3  411.94
  4971.8  411.94  4972.0  412.44  4978.1  412.51  4988.3  413.45  4996.8  414.18
  5000.3  414.18  5008.7  416.53  5016.4  418.45  5021.5  418.99  5029.0  419.27
  5039.2  419.01  5049.4  418.60  5059.6  418.69  5068.0  418.96  5073.1  419.33
  5074.5  419.44  5080.0  419.87  5089.0  420.09  5092.9  420.09
#Mann=5,-1,0
  4911.7    0.16       0  4964.0    0.05       0  4968.0    0.05       0
  4972.0    0.05       0  5074.5    0.07       0
Bank Sta=4968,4972
Exp/Cntr=0.3,0.1

Type RM Length L Ch R = 1,1046,72,72,72
BEGIN DESCRIPTION:
Twin Creek1991045.53
END DESCRIPTION:
XS GIS Cut Line= 3
      2733569.90      6818614.97      2733495.05      6818589.82
      2733389.56      6818560.67
#Sta/Elev= 30
  4923.0  419.74  4927.7  419.74  4937.7  419.52  4947.0  419.58  4952.3  418.97
  4958.8  418.60  4969.3  417.56  4978.6  412.55  4981.8  411.18  4982.1  410.68
  4985.6  410.68  4985.8  411.18  4990.4  412.28  4998.8  418.46  5002.0  418.46
  5004.1  418.46  5011.2  418.64  5016.4  419.06  5021.7  418.98  5032.1  419.59
  5042.5  419.08  5050.8  419.36  5055.9  419.06  5063.2  419.29  5073.6  419.33
  5084.0  419.42  5090.3  419.74  5095.5  419.66  5104.7  419.47  5111.4  419.73
#Mann=3,-1,0
  4923.0    0.16       0  4981.8    0.05       0  4985.8    0.05       0
Bank Sta=4981.8,4985.8
Exp/Cntr=0.3,0.1

Type RM Length L Ch R = 1,974,72,72,72
BEGIN DESCRIPTION:
Twin Creek199974.33
END DESCRIPTION:
XS GIS Cut Line= 3
      2733599.48      6818537.73      2733524.72      6818528.69
      2733384.14      6818506.68
#Sta/Elev= 29
  4926.1  419.38  4930.4  419.38  4937.6  419.22  4942.6  418.92  4949.8  418.87
  4959.8  418.14  4969.9  417.63  4980.0  414.76  4990.0  409.91  4996.2  409.65
  4996.5  409.15  5000.0  409.15  5000.2  409.65  5001.4  409.65  5010.2  414.21
  5013.4  415.29  5017.0  416.50  5022.1  417.63  5030.5  418.30  5040.6  418.54
  5060.8  418.37  5079.7  419.06  5084.8  418.90  5091.2  419.07  5101.3  418.96
  5111.5  419.06  5131.7  419.50  5140.2  419.84  5143.7  419.84
#Mann=4,-1,0
  4926.1    0.16       0  4996.2    0.07       0  5000.2    0.16       0
  5013.4    0.05       0
Bank Sta=4996.2,5000.2
Exp/Cntr=0.3,0.1

Type RM Length L Ch R = 1,902,105,105,105
BEGIN DESCRIPTION:
Twin Creek199901.83
END DESCRIPTION:
XS GIS Cut Line= 3
      2733621.51      6818484.02      2733532.63      6818457.51
      2733463.49      6818433.01
#Sta/Elev= 28
  4907.2  419.41  4912.9  419.06  4923.4  418.81  4931.9  418.29  4937.1  418.18
  4944.3  418.10  4954.7  417.86  4959.1  417.57  4965.1  417.18  4970.3  415.82
  4975.6  409.67  4984.0  408.27  4984.2  407.77  4987.7  407.77  4988.0  408.27
  4995.6  410.20  5000.0  410.20  5003.1  415.72  5008.4  415.97  5017.6  416.65
  5028.2  417.19  5033.9  417.54  5039.3  417.32  5049.4  417.47  5059.5  417.85
  5064.8  417.58  5069.3  417.95  5073.3  417.95
#Mann=4,-1,0
  4907.2    0.16       0  4959.1    0.07       0  4984.0    0.07       0
  4988.0    0.07       0
Bank Sta=4984,4988
Exp/Cntr=0.3,0.1

Type RM Length L Ch R = 1,797,91,91,91
BEGIN DESCRIPTION:
Twin Creek199796.98
END DESCRIPTION:
XS GIS Cut Line= 3
      2733660.52      6818364.93      2733575.76      6818367.60
      2733479.58      6818369.44
#Sta/Elev= 26
  4915.9  419.10  4920.7  419.10  4930.4  418.71  4940.4  418.40  4947.7  417.91
  4952.7  418.49  4960.4  417.20  4970.4  417.09  4980.5  415.16  4990.5  408.40
  4998.1  407.20  5000.7  407.20  5003.1  407.20  5008.5  406.96  5008.7  406.46
  5012.2  406.46  5012.5  406.96  5020.5  409.43  5030.5  413.56  5040.5  415.66
  5050.5  416.47  5060.5  416.63  5070.5  416.44  5080.5  416.62  5090.5  416.84
  5096.9  417.05
#Mann=3,-1,0
  4915.9    0.07       0  5008.5    0.07       0  5012.5    0.07       0
Bank Sta=5008.5,5012.5
Exp/Cntr=0.3,0.1

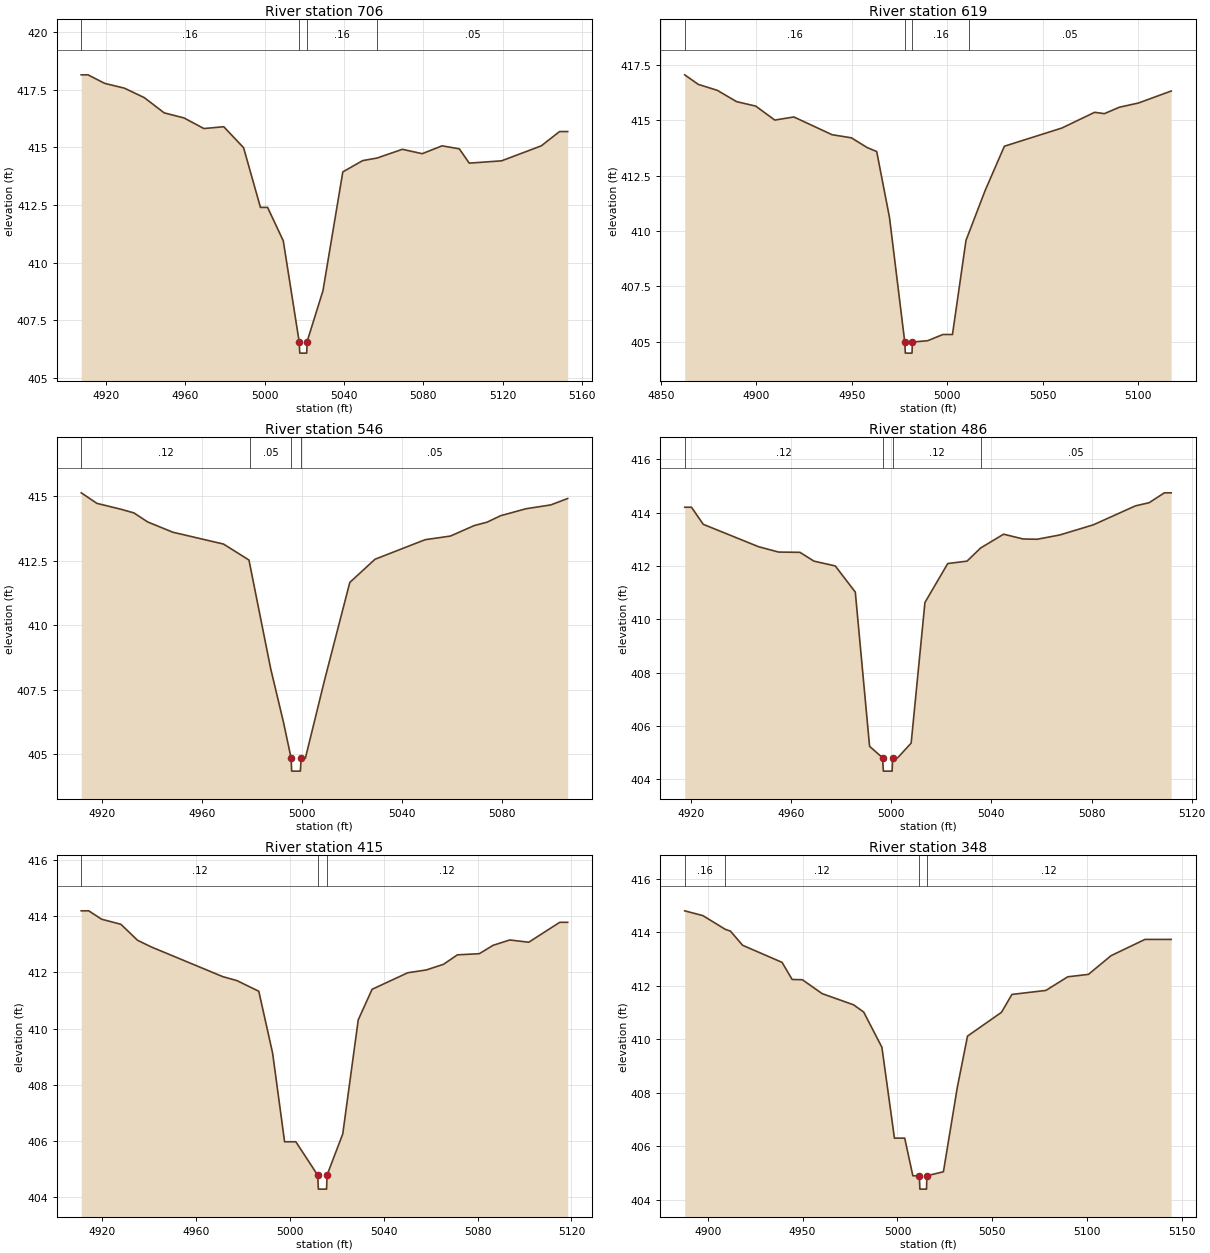
Type RM Length L Ch R = 1,706,87,87,87
BEGIN DESCRIPTION:
Twin Creek199706.03
END DESCRIPTION:
XS GIS Cut Line= 3
      2733667.79      6818278.34      2733573.94      6818276.64
      2733422.71      6818275.67
#Sta/Elev= 30
  4907.6  418.15  4911.0  418.15  4919.4  417.78  4929.4  417.57  4939.4  417.16
  4949.4  416.50  4959.4  416.28  4969.4  415.82  4979.4  415.90  4989.4  414.99
  4997.9  412.40  5001.5  412.40  5009.4  410.95  5017.4  406.58  5017.7  406.08
  5021.2  406.08  5021.4  406.58  5029.4  408.79  5039.4  413.94  5049.4  414.43
  5056.6  414.54  5069.4  414.92  5079.4  414.73  5089.4  415.07  5098.1  414.94
  5103.1  414.32  5119.4  414.42  5139.4  415.07  5148.6  415.69  5152.7  415.69
#Mann=4,-1,0
  4907.6    0.16       0  5017.4    0.07       0  5021.4    0.16       0
  5056.6    0.05       0
Bank Sta=5017.4,5021.4
Exp/Cntr=0.3,0.1

Type RM Length L Ch R = 1,619,73,73,73
BEGIN DESCRIPTION:
Twin Creek199618.55
END DESCRIPTION:
XS GIS Cut Line= 3
      2733673.10      6818212.05      2733535.16      6818203.60
      2733419.00      6818192.34
#Sta/Elev= 29
  4862.5  417.04  4869.6  416.61  4879.6  416.34  4889.7  415.83  4899.7  415.63
  4909.7  415.00  4919.7  415.14  4939.7  414.34  4949.8  414.20  4958.1  413.76
  4963.1  413.58  4969.8  410.61  4977.8  404.99  4978.1  404.49  4981.6  404.49
  4981.8  404.99  4989.8  405.05  4997.8  405.33  5002.8  405.33  5009.9  409.58
  5011.3  409.89  5019.9  411.82  5030.0  413.82  5060.1  414.64  5077.3  415.35
  5082.4  415.29  5090.3  415.58  5100.3  415.77  5117.4  416.31
#Mann=4,-1,0
  4862.5    0.16       0  4977.8    0.07       0  4981.8    0.16       0
  5011.3    0.05       0
Bank Sta=4977.8,4981.8
Exp/Cntr=0.3,0.1

Type RM Length L Ch R = 1,546,60,60,60
BEGIN DESCRIPTION:
Twin Creek199546.12
END DESCRIPTION:
XS GIS Cut Line= 3
      2733662.19      6818159.52      2733573.72      6818144.27
      2733469.29      6818132.26
#Sta/Elev= 27
  4911.5  415.14  4917.8  414.73  4927.5  414.50  4932.6  414.36  4938.1  414.01
  4948.2  413.61  4968.5  413.15  4978.7  412.53  4979.3  412.24  4987.4  408.31
  4992.5  406.24  4995.6  404.83  4995.8  404.33  4999.3  404.33  4999.6  404.83
  5001.3  404.83  5009.0  407.87  5019.1  411.66  5029.2  412.56  5049.3  413.32
  5059.4  413.46  5069.0  413.87  5074.1  414.00  5079.5  414.25  5089.6  414.52
  5099.6  414.67  5106.4  414.92
#Mann=4,-1,0
  4911.5    0.12       0  4979.3    0.05       0  4995.6    0.05       0
  4999.6    0.05       0
Bank Sta=4995.6,4999.6
Exp/Cntr=0.3,0.1

Type RM Length L Ch R = 1,486,71,71,71
BEGIN DESCRIPTION:
Twin Creek199486.21
END DESCRIPTION:
XS GIS Cut Line= 3
      2733669.32      6818128.49      2733593.84      6818089.32
      2733496.16      6818040.59
#Sta/Elev= 29
  4917.6  414.20  4920.3  414.20  4925.0  413.56  4947.1  412.72  4955.1  412.52
  4963.6  412.51  4969.2  412.18  4977.7  412.00  4985.7  411.02  4991.4  405.24
  4996.6  404.81  4996.9  404.31  5000.4  404.31  5000.6  404.81  5002.6  404.81
  5008.0  405.36  5013.5  410.63  5022.6  412.09  5030.3  412.18  5035.7  412.67
  5044.9  413.19  5052.7  413.01  5058.3  413.00  5067.3  413.16  5080.7  413.54
  5097.5  414.25  5103.0  414.37  5109.1  414.74  5111.8  414.74
#Mann=4,-1,0
  4917.6    0.12       0  4996.6    0.07       0  5000.6    0.12       0
  5035.7    0.05       0
Bank Sta=4996.6,5000.6
Exp/Cntr=0.3,0.1

Type RM Length L Ch R = 1,415,67,67,67
BEGIN DESCRIPTION:
Twin Creek199414.57
END DESCRIPTION:
XS GIS Cut Line= 3
      2733694.39      6818115.29      2733645.62      6818037.90
      2733583.26      6817940.17
#Sta/Elev= 29
  4911.0  414.20  4914.2  414.20  4919.7  413.90  4927.9  413.72  4935.0  413.15
  4940.9  412.91  4971.4  411.85  4977.4  411.71  4986.7  411.33  4992.6  409.12
  4997.7  405.96  5002.5  405.96  5011.8  404.77  5012.1  404.27  5015.6  404.27
  5015.8  404.77  5022.5  406.24  5029.1  410.31  5035.0  411.40  5050.2  411.99
  5058.1  412.09  5065.4  412.29  5071.4  412.63  5080.7  412.67  5086.6  412.97
  5093.7  413.16  5101.8  413.08  5115.0  413.79  5118.4  413.79
#Mann=3,-1,0
  4911.0    0.12       0  5011.8    0.07       0  5015.8    0.12       0
Bank Sta=5011.8,5015.8
Exp/Cntr=0.3,0.1

Type RM Length L Ch R = 1,348,102,102,102
BEGIN DESCRIPTION:
Twin Creek199347.91
END DESCRIPTION:
XS GIS Cut Line= 3
      2733727.82      6818100.14      2733694.48      6817993.40
      2733636.44      6817861.09
#Sta/Elev= 30
  4887.9  414.81  4897.5  414.63  4909.2  414.12  4912.0  414.05  4918.4  413.52
  4939.2  412.88  4944.5  412.24  4949.9  412.23  4960.3  411.71  4976.9  411.29
  4982.2  411.02  4991.8  409.70  4998.4  406.30  5003.8  406.30  5008.1  404.89
  5011.5  404.89  5011.8  404.39  5015.3  404.39  5015.5  404.89  5024.2  405.04
  5031.5  408.19  5036.9  410.12  5054.8  411.01  5060.3  411.68  5078.2  411.83
  5089.7  412.34  5100.6  412.43  5112.5  413.13  5130.4  413.74  5144.2  413.74
#Mann=4,-1,0
  4887.9    0.16       0  4909.2    0.12       0  5011.5    0.07       0
  5015.5    0.12       0
Bank Sta=5011.5,5015.5
Exp/Cntr=0.3,0.1

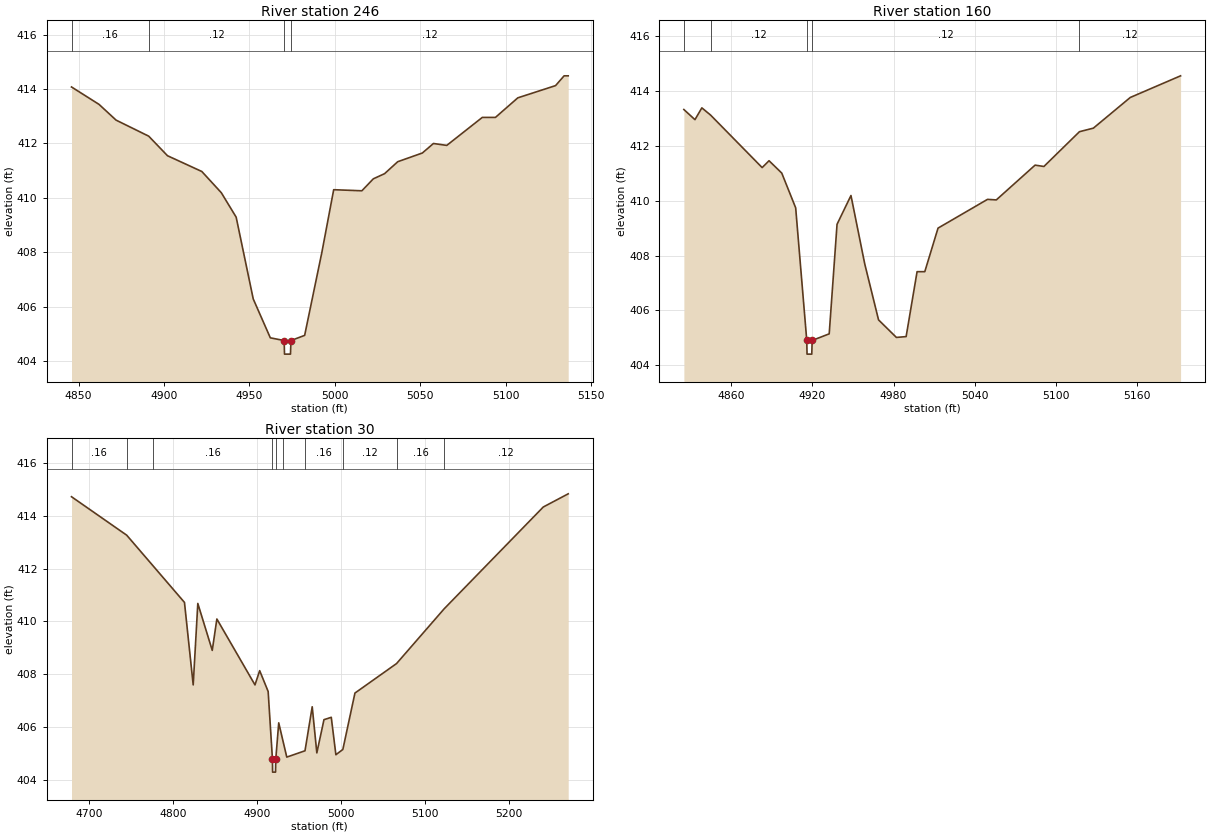
Type RM Length L Ch R = 1,246,86,86,86
BEGIN DESCRIPTION:
Twin Creek199245.86
END DESCRIPTION:
XS GIS Cut Line= 3
      2733748.25      6818057.01      2733734.85      6817902.22
      2733647.94      6817798.36
#Sta/Elev= 30
  4845.8  414.08  4861.9  413.44  4871.9  412.86  4891.0  412.27  4902.0  411.55
  4922.1  410.97  4933.5  410.19  4942.2  409.29  4952.2  406.28  4962.2  404.85
  4970.3  404.75  4970.5  404.25  4974.0  404.25  4974.3  404.75  4982.3  404.94
  4992.4  408.00  4999.3  410.30  5015.8  410.26  5022.5  410.70  5029.1  410.89
  5036.8  411.33  5051.2  411.65  5057.7  412.00  5065.5  411.93  5086.3  412.96
  5094.0  412.96  5107.1  413.68  5129.2  414.13  5134.2  414.49  5136.6  414.49
#Mann=4,-1,0
  4845.8    0.16       0  4891.0    0.12       0  4970.3    0.07       0
  4974.3    0.12       0
Bank Sta=4970.3,4974.3
Exp/Cntr=0.3,0.1

Type RM Length L Ch R = 1,160,130,130,130
BEGIN DESCRIPTION:
Twin Creek199159.85
END DESCRIPTION:
XS GIS Cut Line= 3
      2733768.84      6818031.87      2733805.23      6817860.24
      2733656.41      6817739.00
#Sta/Elev= 30
  4824.9  413.33  4833.1  412.96  4838.2  413.39  4844.6  413.13  4882.8  411.21
  4887.9  411.46  4897.3  411.01  4907.6  409.74  4915.8  404.90  4916.0  404.40
  4919.5  404.40  4919.8  404.90  4932.4  405.14  4938.2  409.14  4948.5  410.19
  4958.7  407.69  4968.9  405.65  4982.1  405.01  4989.3  405.04  4997.4  407.41
  5003.1  407.41  5012.9  409.00  5049.5  410.05  5056.0  410.03  5084.7  411.30
  5091.2  411.25  5117.5  412.52  5127.8  412.65  5155.1  413.77  5192.3  414.56
#Mann=5,-1,0
  4824.9    0.16       0  4844.6    0.12       0  4915.8    0.07       0
  4919.8    0.12       0  5117.5    0.12       0
Bank Sta=4915.8,4919.8
Exp/Cntr=0.3,0.1

Type RM Length L Ch R = 1,30,0,0,0
BEGIN DESCRIPTION:
Twin Creek19930.128
END DESCRIPTION:
XS GIS Cut Line= 3
      2733766.62      6818072.56      2733904.75      6817782.36
      2733652.18      6817685.79
#Sta/Elev= 30
  4678.6  414.73  4744.4  413.27  4775.7  412.11  4813.2  410.72  4823.6  407.59
  4829.1  410.68  4846.3  408.90  4851.8  410.09  4897.2  407.59  4902.8  408.13
  4912.9  407.34  4918.0  404.78  4918.2  404.28  4921.7  404.28  4922.0  404.78
  4925.5  406.15  4930.5  405.47  4935.1  404.85  4956.8  405.09  4965.4  406.76
  4970.9  405.01  4979.4  406.27  4988.1  406.36  4993.6  404.94  5001.9  405.14
  5016.3  407.28  5065.9  408.40  5122.7  410.48  5240.7  414.34  5270.4  414.84
#Mann=10,-1,0
  4678.6    0.16       0  4744.4    0.12       0  4775.7    0.16       0
  4918.0    0.07       0  4922.0    0.16       0  4930.5    0.12       0
  4956.8    0.16       0  5001.9    0.12       0  5065.9    0.16       0
  5122.7    0.12       0
Bank Sta=4918,4922
Exp/Cntr=0.3,0.1

Chan Stop Cuts=-1