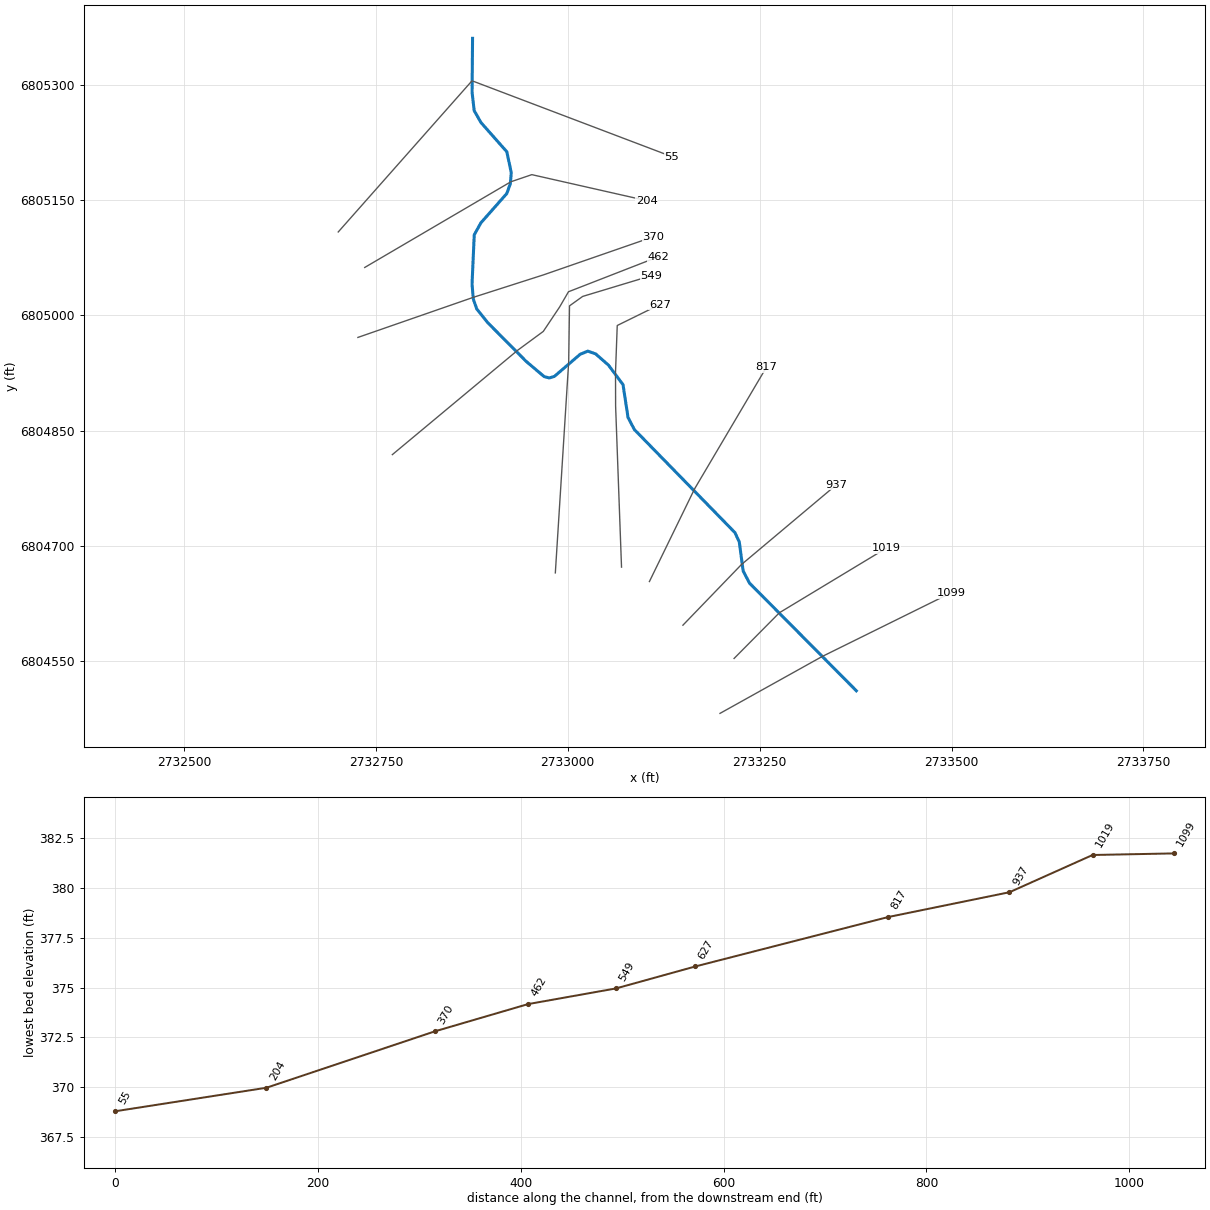
--- Twin Creek200.prj (project) ---

Proj Title=Twin Creek200 Base Level Engineering
Current Plan=p01
Default Exp/Contr=0.3,0.1
English Units
Geom File=g01
Flow File=f01
Plan File=p01
BEGIN DESCRIPTION:
Twin Creek200
END DESCRIPTION:

--- Twin Creek200.p01 (plan) ---

Plan Title=Multiple Run
Short Identifier=Multiple
Geom File=g01
Flow File=f01
Subcritical Flow
K Sum by GR= 0
Std Step Tol= 0.01
Critical Tol= 0.01
Num of Std Step Trials= 20
Max Error Tol= 0.3
Flow Tol Ratio= 0.001
Split Flow NTrial= 30
Split Flow Tol= 0.02
Split Flow Ratio= 0.02
Log Output Level= 0
Friction Slope Method= 1
Unsteady Friction Slope Method= 2
Unsteady Bridges Friction Slope Method= 1
Parabolic Critical Depth
Global Vel Dist=  1 , 1 , 1
Global Log Level= 0
CheckData=True
Encroach Param= -1, 0, 0, 0
BEGIN DESCRIPTION:
Multiple Run
END DESCRIPTION:

--- Twin Creek200.f01 (steady flow) ---

Flow Title=Multiple
Number of Profiles=7
Profile Names=10-year,25-year,50-year,1pct_min,100-year,1pct_plu,500-year
River Rch & RM= Twin Creek200,Reach-1,1099
     215     270     313     181     360     719     476
Boundary for River Rch & Prof#=Twin Creek200,Reach-1,1
Up Type=0
Dn Type=3
Dn Slope=0.005
Boundary for River Rch & Prof#=Twin Creek200,Reach-1,2
Up Type=0
Dn Type=3
Dn Slope=0.005
Boundary for River Rch & Prof#=Twin Creek200,Reach-1,3
Up Type=0
Dn Type=3
Dn Slope=0.005
Boundary for River Rch & Prof#=Twin Creek200,Reach-1,4
Up Type=0
Dn Type=3
Dn Slope=0.005
Boundary for River Rch & Prof#=Twin Creek200,Reach-1,5
Up Type=0
Dn Type=3
Dn Slope=0.005
Boundary for River Rch & Prof#=Twin Creek200,Reach-1,6
Up Type=0
Dn Type=3
Dn Slope=0.005
Boundary for River Rch & Prof#=Twin Creek200,Reach-1,7
Up Type=0
Dn Type=3
Dn Slope=0.005

--- Twin Creek200.g01 (geometry) ---

Geom Title=Existing Conditions

River Reach=Twin Creek200,Reach-1
Reach XY= 30
      2733376.00      6804511.00      2733236.77      6804651.32
      2733228.53      6804667.05      2733223.47      6804704.95
      2733217.84      6804717.05      2733086.78      6804851.36
      2733078.54      6804867.13      2733072.02      6804909.82
      2733052.98      6804935.36      2733036.32      6804949.89
      2733026.21      6804953.53      2733016.13      6804949.35
      2732982.68      6804920.62      2732976.00      6804918.56
      2732969.32      6804920.30      2732945.92      6804940.07
      2732895.58      6804990.76      2732881.40      6805008.54
      2732876.93      6805021.47      2732875.33      6805040.91
      2732878.19      6805105.03      2732886.87      6805120.65
      2732920.62      6805158.82      2732925.24      6805171.69
      2732926.41      6805186.00      2732920.67      6805213.19
      2732886.92      6805251.33      2732878.13      6805266.86
      2732875.38      6805290.73      2732876.00      6805361.00

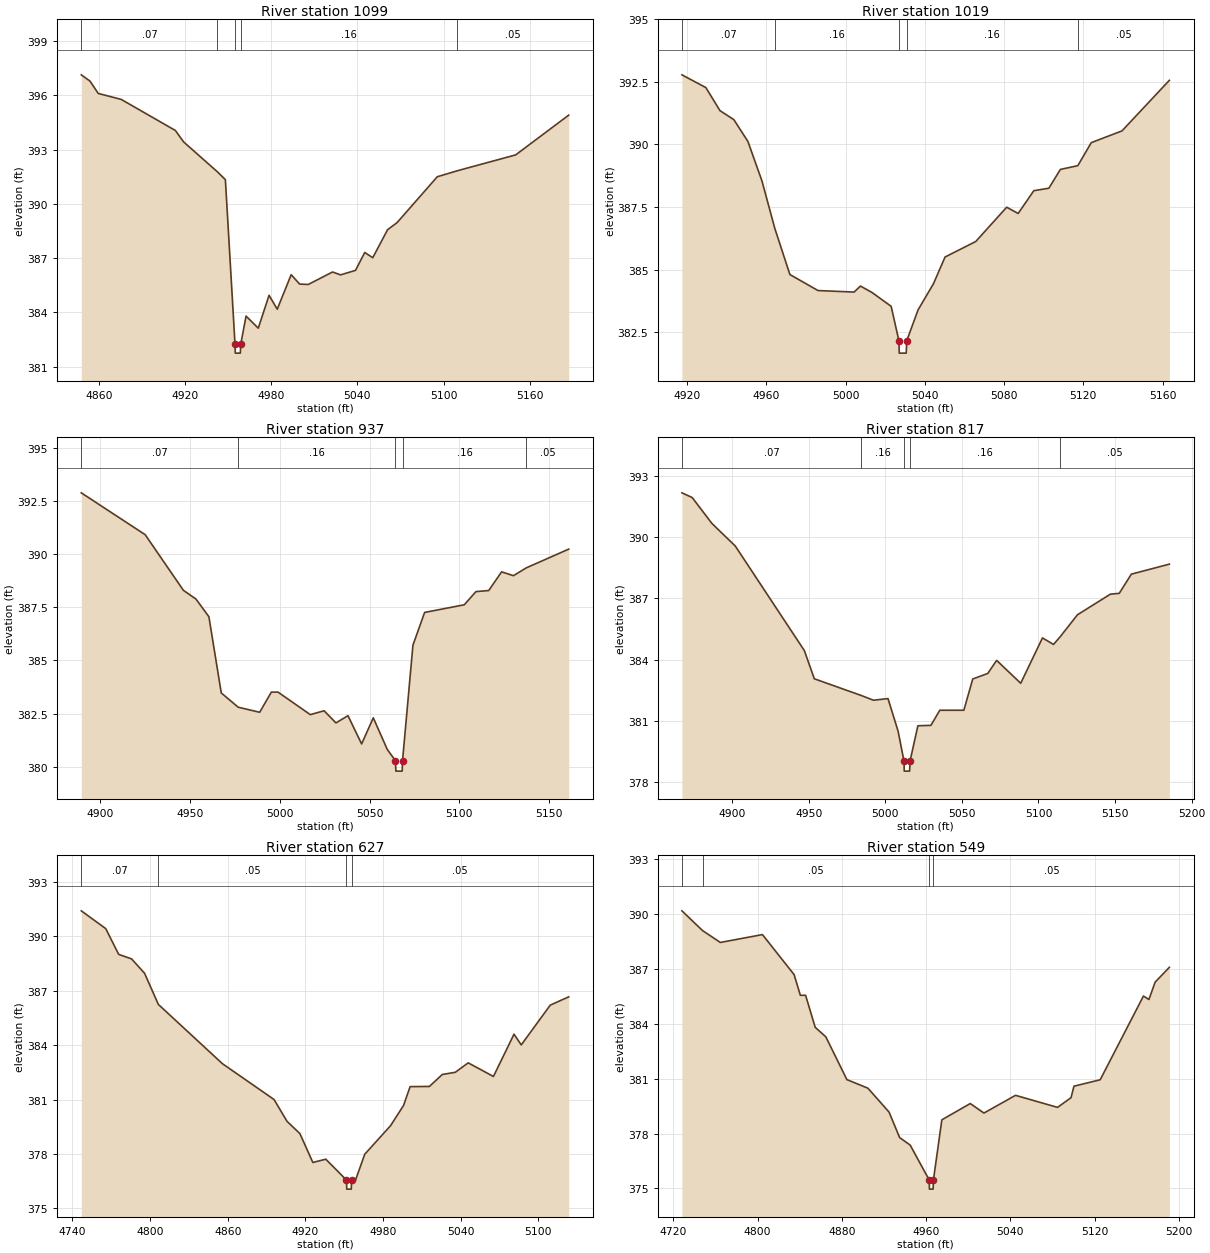
Type RM Length L Ch R = 1,1099,80,80,80
BEGIN DESCRIPTION:
Twin Creek2001120.641
END DESCRIPTION:
XS GIS Cut Line= 3
      2733198.36      6804481.58      2733331.34      6804555.61
      2733499.09      6804638.47
#Sta/Elev= 30
  4847.8  397.14  4853.9  396.79  4859.6  396.11  4875.6  395.78  4913.3  394.06
  4919.0  393.43  4942.6  391.77  4948.1  391.34  4954.8  382.24  4955.0  381.74
  4958.5  381.74  4958.8  382.24  4962.5  383.79  4971.0  383.12  4978.5  384.94
  4984.2  384.17  4993.9  386.08  4999.8  385.56  5005.8  385.54  5022.7  386.23
  5028.3  386.07  5038.7  386.32  5045.1  387.31  5050.7  387.02  5061.0  388.57
  5067.6  388.96  5095.6  391.50  5109.5  391.83  5150.2  392.71  5187.1  394.91
#Mann=5,-1,0
  4847.8    0.07       0  4942.6    0.16       0  4954.8    0.07       0
  4958.8    0.16       0  5109.5    0.05       0
Bank Sta=4954.8,4958.8
Exp/Cntr=0.3,0.1

Type RM Length L Ch R = 1,1019,82,82,82
BEGIN DESCRIPTION:
Mapping XS 57d1f772
END DESCRIPTION:
XS GIS Cut Line= 3
      2733216.72      6804553.13      2733275.74      6804612.69
      2733414.54      6804696.52
#Sta/Elev= 30
  4917.4  392.78  4929.5  392.27  4936.6  391.35  4943.6  390.99  4950.7  390.12
  4957.8  388.54  4964.3  386.64  4971.9  384.80  4986.1  384.16  5004.3  384.10
  5007.5  384.34  5013.4  384.08  5023.0  383.53  5026.9  382.16  5027.1  381.66
  5030.6  381.66  5030.9  382.16  5036.6  383.39  5044.4  384.44  5050.2  385.50
  5065.7  386.12  5081.3  387.49  5087.1  387.24  5095.0  388.15  5102.6  388.25
  5108.4  389.00  5117.2  389.15  5124.0  390.07  5139.5  390.54  5163.4  392.56
#Mann=5,-1,0
  4917.4    0.07       0  4964.3    0.16       0  5026.9    0.07       0
  5030.9    0.16       0  5117.2    0.05       0
Bank Sta=5026.9,5030.9
Exp/Cntr=0.3,0.1

Type RM Length L Ch R = 1,937,120,120,120
BEGIN DESCRIPTION:
Twin Creek200937.09
END DESCRIPTION:
XS GIS Cut Line= 3
      2733150.06      6804596.47      2733226.16      6804675.34
      2733350.18      6804779.57
#Sta/Elev= 30
  4889.4  392.89  4925.0  390.92  4946.3  388.30  4953.3  387.89  4960.5  387.06
  4967.4  383.47  4976.8  382.80  4988.8  382.56  4995.3  383.51  4999.0  383.51
  5017.0  382.45  5024.7  382.63  5031.3  382.06  5038.0  382.40  5045.6  381.07
  5052.1  382.30  5059.9  380.81  5064.4  380.29  5064.7  379.79  5068.2  379.79
  5068.4  380.29  5074.2  385.72  5080.7  387.26  5102.8  387.62  5109.3  388.24
  5116.4  388.29  5123.6  389.17  5130.2  388.99  5137.4  389.36  5161.0  390.24
#Mann=5,-1,0
  4889.4    0.07       0  4976.8    0.16       0  5064.4    0.07       0
  5068.4    0.16       0  5137.4    0.05       0
Bank Sta=5064.4,5068.4
Exp/Cntr=0.3,0.1

Type RM Length L Ch R = 1,817,190,190,190
BEGIN DESCRIPTION:
Twin Creek200817.41
END DESCRIPTION:
XS GIS Cut Line= 3
      2733106.41      6804653.34      2733165.34      6804774.23
      2733258.71      6804932.33
#Sta/Elev= 30
  4867.3  392.16  4874.0  391.93  4886.9  390.66  4902.1  389.56  4947.2  384.44
  4953.7  383.06  4984.4  382.24  4992.3  382.01  5001.8  382.09  5008.4  380.49
  5012.2  379.04  5012.4  378.54  5015.9  378.54  5016.2  379.04  5021.3  380.76
  5029.8  380.78  5035.6  381.52  5051.3  381.52  5057.1  383.05  5066.9  383.32
  5072.7  383.96  5088.4  382.84  5102.6  385.06  5109.8  384.74  5114.2  385.12
  5125.4  386.19  5146.9  387.20  5152.7  387.24  5160.6  388.18  5185.4  388.67
#Mann=5,-1,0
  4867.3    0.07       0  4984.4    0.16       0  5012.2    0.07       0
  5016.2    0.16       0  5114.2    0.05       0
Bank Sta=5012.2,5016.2
Exp/Cntr=0.3,0.1

Type RM Length L Ch R = 1,627,78,78,78
BEGIN DESCRIPTION:
Twin Creek200627.23
END DESCRIPTION:
XS GIS Cut Line= 5
      2733070.07      6804672.08      2733062.37      6804881.85
      2733062.24      6804926.22      2733064.49      6804986.89
      2733119.95      6805014.18
#Sta/Elev= 30
  4746.8  391.40  4765.7  390.42  4775.7  389.00  4785.7  388.75  4795.7  387.96
  4806.4  386.24  4855.8  382.98  4895.8  381.00  4905.8  379.80  4915.8  379.12
  4925.8  377.53  4935.8  377.71  4951.8  376.56  4952.0  376.06  4955.5  376.06
  4955.8  376.56  4958.8  376.56  4965.9  377.98  4985.9  379.56  4995.9  380.67
  5001.0  381.71  5015.9  381.72  5025.9  382.38  5035.9  382.50  5045.9  383.02
  5065.4  382.27  5081.3  384.60  5086.9  384.01  5109.3  386.20  5123.6  386.66
#Mann=4,-1,0
  4746.8    0.07       0  4806.4    0.05       0  4951.8    0.05       0
  4955.8    0.05       0
Bank Sta=4951.8,4955.8
Exp/Cntr=0.3,0.1

Type RM Length L Ch R = 1,549,87,87,87
BEGIN DESCRIPTION:
Twin Creek200549.15
END DESCRIPTION:
XS GIS Cut Line= 5
      2732983.84      6804664.61      2733001.25      6804939.94
      2733002.30      6805012.48      2733019.48      6805024.79
      2733108.93      6805051.80
#Sta/Elev= 30
  4728.1  390.18  4747.7  389.10  4764.6  388.45  4804.6  388.88  4834.7  386.69
  4840.6  385.56  4845.6  385.56  4854.7  383.81  4864.8  383.29  4884.8  380.95
  4904.8  380.48  4924.9  379.17  4934.9  377.78  4944.9  377.37  4963.0  375.46
  4963.2  374.96  4966.7  374.96  4967.0  375.46  4975.0  378.75  5002.0  379.64
  5015.0  379.12  5045.0  380.09  5084.9  379.43  5097.7  379.96  5100.5  380.59
  5125.4  380.94  5166.5  385.52  5171.7  385.33  5177.6  386.28  5191.1  387.09
#Mann=4,-1,0
  4728.1    0.07       0  4747.7    0.05       0  4963.0    0.05       0
  4967.0    0.05       0
Bank Sta=4963,4967
Exp/Cntr=0.3,0.1

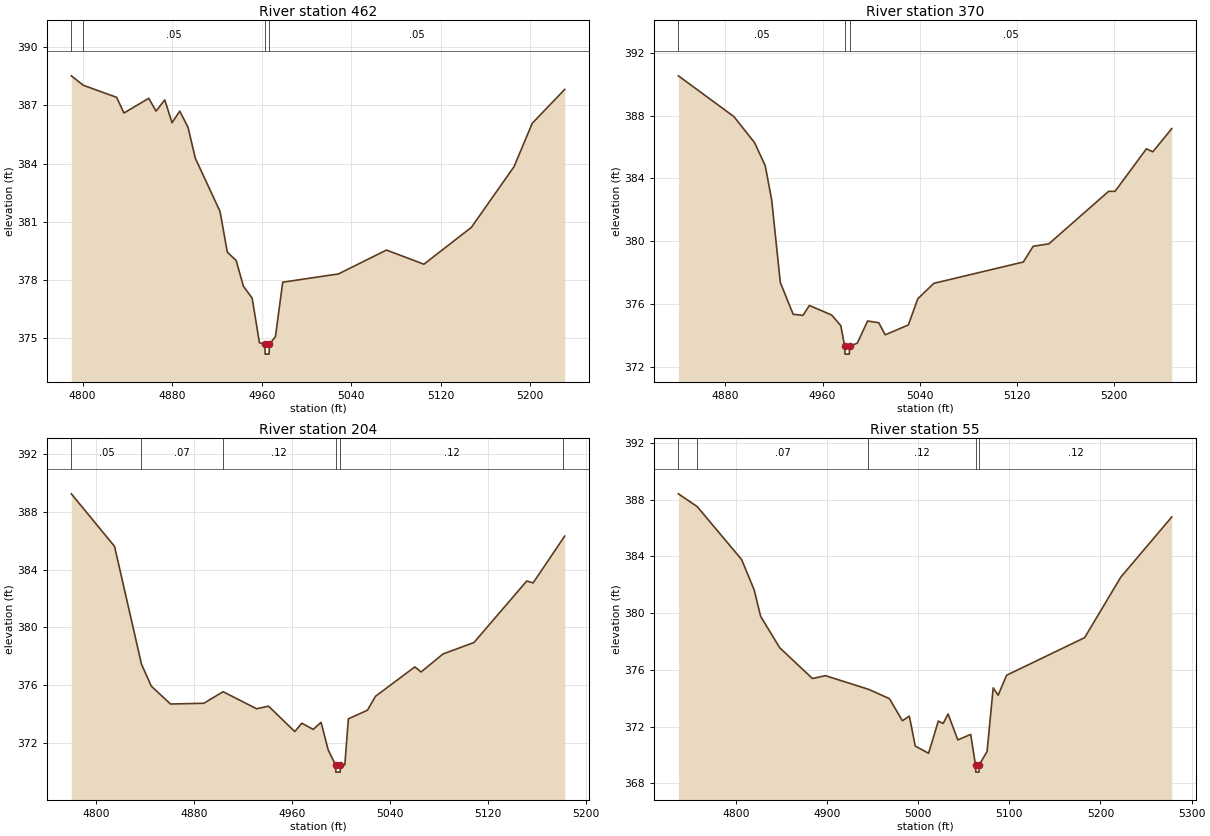
Type RM Length L Ch R = 1,462,92,92,92
BEGIN DESCRIPTION:
Twin Creek200462.05
END DESCRIPTION:
XS GIS Cut Line= 6
      2732771.53      6804818.69      2732934.73      6804954.60
      2732968.16      6804979.20      2732989.47      6805011.09
      2733000.95      6805030.85      2733118.19      6805076.48
#Sta/Elev= 30
  4789.9  388.53  4800.7  388.04  4830.4  387.42  4836.9  386.61  4859.1  387.37
  4865.6  386.71  4873.4  387.29  4879.9  386.11  4886.8  386.71  4894.2  385.87
  4900.7  384.28  4922.8  381.53  4929.3  379.43  4937.2  379.00  4943.7  377.67
  4951.5  377.06  4958.0  374.76  4962.9  374.67  4963.1  374.17  4966.6  374.17
  4966.9  374.67  4972.3  375.07  4978.8  377.88  5028.7  378.31  5071.5  379.54
  5105.0  378.81  5147.4  380.71  5185.5  383.84  5201.8  386.08  5230.8  387.83
#Mann=4,-1,0
  4789.9   0.035       0  4800.7    0.05       0  4962.9    0.05       0
  4966.9    0.05       0
Bank Sta=4962.9,4966.9
Exp/Cntr=0.3,0.1

Type RM Length L Ch R = 1,370,166,166,166
BEGIN DESCRIPTION:
Twin Creek200370.46
END DESCRIPTION:
XS GIS Cut Line= 4
      2732726.63      6804971.36      2732877.03      6805023.60
      2732968.26      6805052.81      2733111.68      6805102.53
#Sta/Elev= 30
  4841.2  390.53  4887.0  387.93  4904.0  386.27  4912.8  384.80  4918.1  382.62
  4925.2  377.37  4935.8  375.34  4943.9  375.27  4949.2  375.90  4967.6  375.29
  4975.1  374.61  4978.3  373.30  4978.6  372.80  4982.1  372.80  4982.3  373.30
  4988.7  373.50  4997.2  374.91  5006.4  374.80  5011.7  374.03  5030.8  374.66
  5038.6  376.33  5051.8  377.31  5125.6  378.67  5133.7  379.67  5146.7  379.83
  5195.9  383.17  5201.2  383.17  5227.1  385.88  5232.4  385.69  5248.0  387.17
#Mann=3,-1,0
  4841.2    0.05       0  4978.3    0.05       0  4982.3    0.05       0
Bank Sta=4978.3,4982.3
Exp/Cntr=0.3,0.1

Type RM Length L Ch R = 1,204,149,149,149
BEGIN DESCRIPTION:
Twin Creek200203.58
END DESCRIPTION:
XS GIS Cut Line= 4
      2732735.52      6805062.50      2732925.88      6805174.12
      2732953.23      6805183.42      2733102.88      6805149.54
#Sta/Elev= 30
  4779.7  389.25  4815.0  385.61  4837.0  377.45  4845.0  375.93  4860.7  374.69
  4887.9  374.74  4903.7  375.54  4931.0  374.36  4940.8  374.54  4962.2  372.78
  4968.0  373.36  4977.3  372.93  4983.7  373.42  4989.5  371.51  4995.5  370.47
  4995.8  369.97  4999.3  369.97  4999.5  370.47  5003.1  370.47  5006.0  373.66
  5021.6  374.26  5028.1  375.22  5060.3  377.26  5065.4  376.91  5083.4  378.16
  5108.6  378.95  5151.7  383.21  5156.9  383.08  5181.5  386.17  5182.7  386.32
#Mann=6,-1,0
  4779.7    0.05       0  4837.0    0.07       0  4903.7    0.12       0
  4995.5    0.07       0  4999.5    0.12       0  5181.5    0.05       0
Bank Sta=4995.5,4999.5
Exp/Cntr=0.3,0.1

Type RM Length L Ch R = 1,55,0,0,0
BEGIN DESCRIPTION:
Twin Creek20055.296
END DESCRIPTION:
XS GIS Cut Line= 3
      2732701.02      6805108.75      2732875.31      6805305.71
      2733135.40      6805206.98
#Sta/Elev= 30
  4737.0  388.41  4757.6  387.51  4806.3  383.78  4820.1  381.64  4827.2  379.77
  4848.1  377.56  4884.0  375.39  4898.3  375.59  4945.5  374.63  4968.5  373.97
  4982.7  372.41  4990.3  372.74  4996.8  370.63  5011.4  370.12  5022.1  372.39
  5027.4  372.22  5032.8  372.89  5043.5  371.06  5057.6  371.45  5062.9  369.29
  5063.2  368.79  5066.7  368.79  5066.9  369.29  5075.6  370.25  5082.3  374.73
  5087.7  374.21  5097.0  375.62  5182.6  378.27  5222.3  382.54  5278.2  386.78
#Mann=5,-1,0
  4737.0    0.05       0  4757.6    0.07       0  4945.5    0.12       0
  5062.9    0.07       0  5066.9    0.12       0
Bank Sta=5062.9,5066.9
Exp/Cntr=0.3,0.1

Chan Stop Cuts=-1