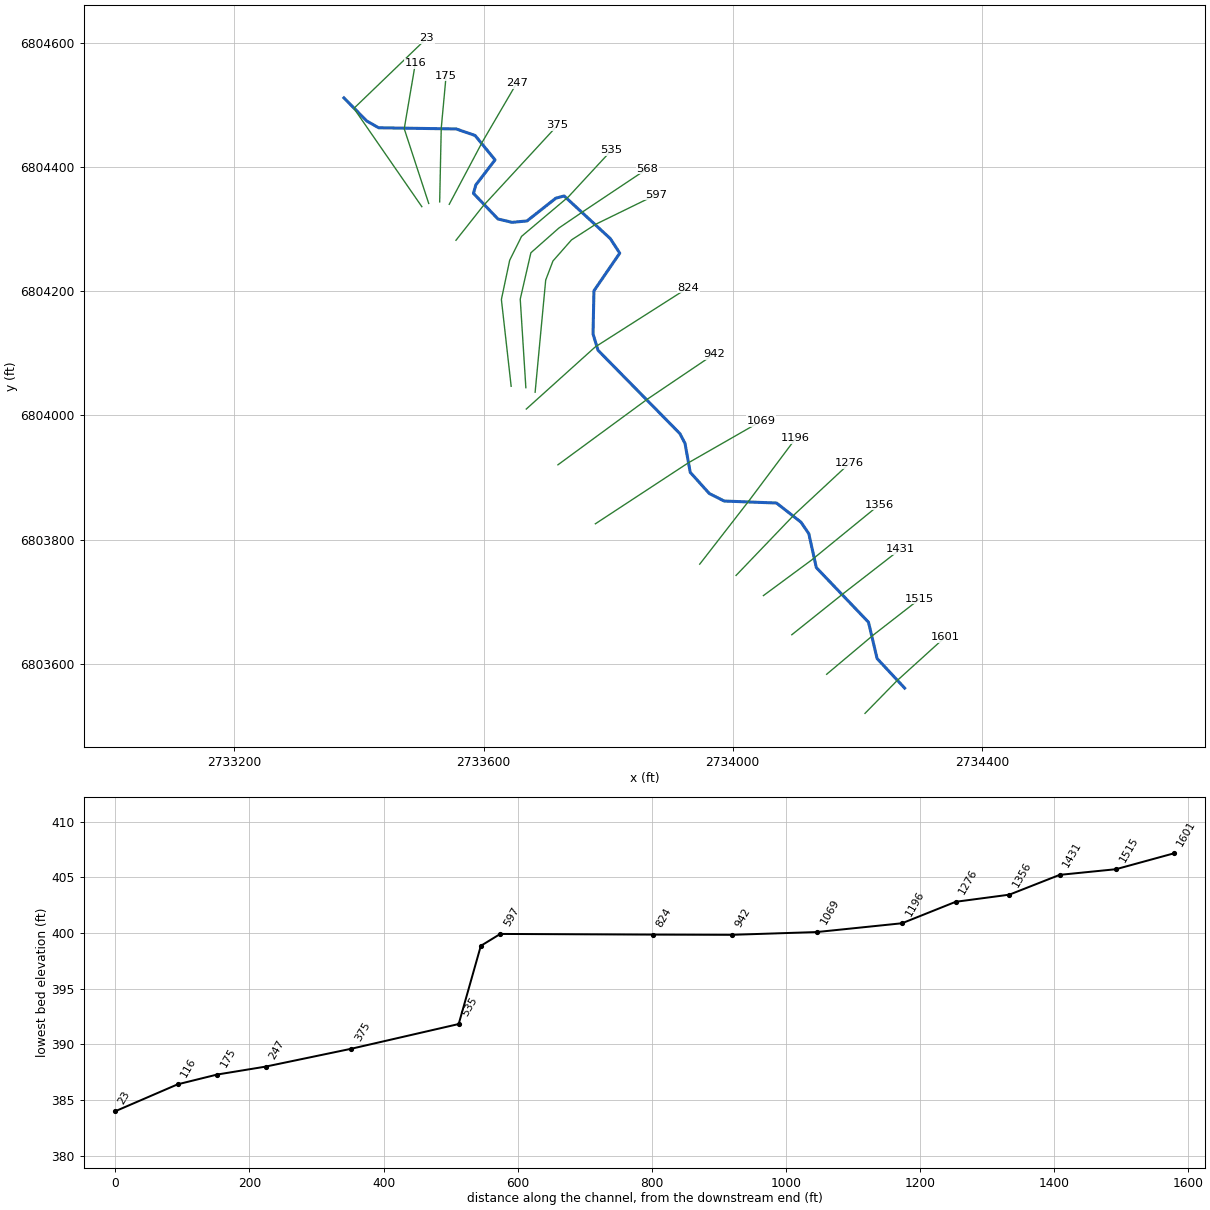
--- Twin Creek201.prj (project) ---

Proj Title=Twin Creek201 Base Level Engineering
Current Plan=p01
Default Exp/Contr=0.3,0.1
English Units
Geom File=g01
Flow File=f01
Plan File=p01
BEGIN DESCRIPTION:
Twin Creek201
END DESCRIPTION:

--- Twin Creek201.p01 (plan) ---

Plan Title=Multiple Run
Short Identifier=Multiple
Geom File=g01
Flow File=f01
Subcritical Flow
K Sum by GR= 0
Std Step Tol= 0.01
Critical Tol= 0.01
Num of Std Step Trials= 20
Max Error Tol= 0.3
Flow Tol Ratio= 0.001
Split Flow NTrial= 30
Split Flow Tol= 0.02
Split Flow Ratio= 0.02
Log Output Level= 0
Friction Slope Method= 1
Unsteady Friction Slope Method= 2
Unsteady Bridges Friction Slope Method= 1
Parabolic Critical Depth
Global Vel Dist=  1 , 1 , 1
Global Log Level= 0
CheckData=True
Encroach Param= -1, 0, 0, 0
BEGIN DESCRIPTION:
Multiple Run
END DESCRIPTION:

--- Twin Creek201.f01 (steady flow) ---

Flow Title=Multiple
Number of Profiles=7
Profile Names=10-year,25-year,50-year,1pct_min,100-year,1pct_plu,500-year
River Rch & RM= Twin Creek201,Reach-1,1601
      94     110     122      67     135     268     162
River Rch & RM= Twin Creek201,Reach-1,23
     215     270     313     181     360     719     476
Boundary for River Rch & Prof#=Twin Creek201,Reach-1,1
Up Type=0
Dn Type=3
Dn Slope=0.005
Boundary for River Rch & Prof#=Twin Creek201,Reach-1,2
Up Type=0
Dn Type=3
Dn Slope=0.005
Boundary for River Rch & Prof#=Twin Creek201,Reach-1,3
Up Type=0
Dn Type=3
Dn Slope=0.005
Boundary for River Rch & Prof#=Twin Creek201,Reach-1,4
Up Type=0
Dn Type=3
Dn Slope=0.005
Boundary for River Rch & Prof#=Twin Creek201,Reach-1,5
Up Type=0
Dn Type=3
Dn Slope=0.005
Boundary for River Rch & Prof#=Twin Creek201,Reach-1,6
Up Type=0
Dn Type=3
Dn Slope=0.005
Boundary for River Rch & Prof#=Twin Creek201,Reach-1,7
Up Type=0
Dn Type=3
Dn Slope=0.005

--- Twin Creek201.g01 (geometry) ---

Geom Title=Existing Conditions

River Reach=Twin Creek201,Reach-1
Reach XY= 30
      2734276.00      6803561.00      2734231.70      6803608.65
      2734217.93      6803667.08      2734134.18      6803754.98
      2734122.13      6803809.60      2734109.54      6803828.13
      2734070.29      6803858.92      2733986.34      6803862.11
      2733962.35      6803874.26      2733931.74      6803908.43
      2733923.45      6803954.91      2733915.21      6803970.66
      2733783.76      6804104.83      2733775.80      6804131.06
      2733777.27      6804200.52      2733818.68      6804261.12
      2733803.55      6804284.47      2733729.44      6804353.18
      2733716.14      6804349.61      2733669.87      6804312.99
      2733645.94      6804310.68      2733623.17      6804316.12
      2733583.90      6804357.35      2733587.66      6804370.86
      2733618.54      6804411.23      2733586.51      6804450.52
      2733556.24      6804461.03      2733431.79      6804462.91
      2733412.50      6804473.92      2733376.00      6804511.00

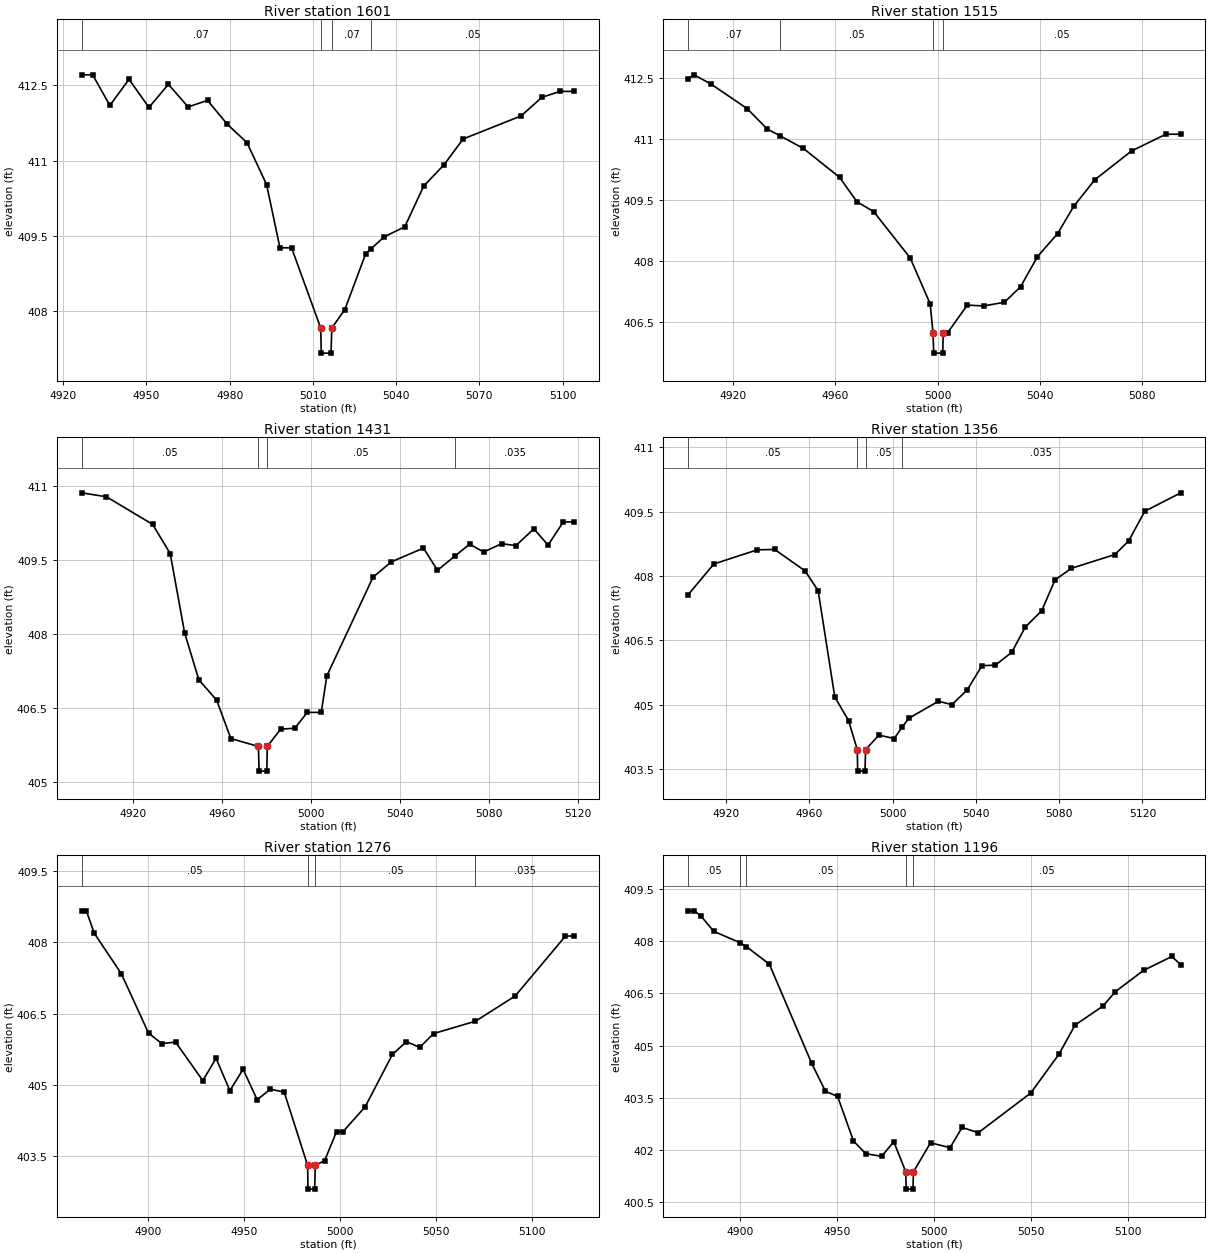
Type RM Length L Ch R = 1,1601,86,86,86
BEGIN DESCRIPTION:
Twin Creek2011601.345
END DESCRIPTION:
XS GIS Cut Line= 3
      2734212.33      6803520.34      2734263.61      6803572.85
      2734340.75      6803642.91
#Sta/Elev= 29
  4926.6  412.71  4930.6  412.71  4936.8  412.10  4943.7  412.62  4950.9  412.06
  4957.9  412.52  4965.0  412.07  4972.0  412.20  4979.2  411.72  4986.2  411.36
  4993.3  410.52  4998.1  409.26  5002.3  409.26  5012.8  407.66  5013.0  407.16
  5016.5  407.16  5016.8  407.66  5021.5  408.03  5029.0  409.14  5030.9  409.24
  5035.7  409.48  5043.1  409.68  5049.9  410.49  5057.3  410.92  5064.1  411.43
  5085.0  411.89  5092.5  412.26  5099.0  412.38  5104.2  412.38
#Mann=4,-1,0
  4926.6    0.07       0  5012.8    0.07       0  5016.8    0.07       0
  5030.9    0.05       0
Bank Sta=5012.8,5016.8
Exp/Cntr=0.3,0.1

Type RM Length L Ch R = 1,1515,84,84,84
BEGIN DESCRIPTION:
Twin Creek2011514.93
END DESCRIPTION:
XS GIS Cut Line= 3
      2734150.77      6803583.28      2734225.79      6803646.55
      2734300.18      6803704.60
#Sta/Elev= 28
  4902.5  412.48  4904.8  412.58  4911.3  412.36  4925.6  411.75  4933.4  411.25
  4938.5  411.08  4947.6  410.77  4961.7  410.06  4968.5  409.46  4975.0  409.22
  4989.3  408.08  4997.1  406.95  4998.2  406.24  4998.5  405.74  5002.0  405.74
  5002.2  406.24  5003.9  406.24  5011.6  406.92  5018.0  406.90  5026.1  406.99
  5032.4  407.37  5039.0  408.11  5046.9  408.68  5053.2  409.35  5061.4  410.00
  5075.8  410.71  5089.2  411.12  5095.0  411.12
#Mann=4,-1,0
  4902.5    0.07       0  4938.5    0.05       0  4998.2    0.05       0
  5002.2    0.05       0
Bank Sta=4998.2,5002.2
Exp/Cntr=0.3,0.1

Type RM Length L Ch R = 1,1431,75,75,75
BEGIN DESCRIPTION:
Twin Creek2011430.89
END DESCRIPTION:
XS GIS Cut Line= 3
      2734094.86      6803646.91      2734177.16      6803712.94
      2734268.90      6803784.40
#Sta/Elev= 30
  4896.7  410.87  4907.9  410.79  4928.7  410.23  4936.6  409.64  4943.1  408.03
  4949.5  407.08  4957.5  406.67  4963.9  405.89  4976.3  405.73  4976.6  405.23
  4980.1  405.23  4980.3  405.73  4986.3  406.08  4992.7  406.10  4998.3  406.42
  5004.6  406.42  5007.1  407.16  5027.9  409.16  5036.1  409.47  5050.6  409.75
  5056.9  409.30  5064.8  409.59  5071.4  409.83  5077.7  409.67  5085.8  409.84
  5092.2  409.80  5100.3  410.14  5106.7  409.81  5113.5  410.28  5118.5  410.28
#Mann=4,-1,0
  4896.7    0.05       0  4976.3    0.05       0  4980.3    0.05       0
  5064.8   0.035       0
Bank Sta=4976.3,4980.3
Exp/Cntr=0.3,0.1

Type RM Length L Ch R = 1,1356,80,80,80
BEGIN DESCRIPTION:
Twin Creek2011356.05
END DESCRIPTION:
XS GIS Cut Line= 3
      2734049.31      6803709.95      2734126.61      6803767.16
      2734235.36      6803856.17
#Sta/Elev= 30
  4901.7  407.56  4914.1  408.28  4934.9  408.61  4943.3  408.62  4957.9  408.12
  4964.2  407.66  4972.2  405.18  4978.8  404.63  4983.0  403.95  4983.2  403.45
  4986.7  403.45  4987.0  403.95  4993.4  404.29  5000.7  404.21  5004.5  404.47
  5007.7  404.68  5022.0  405.08  5028.5  405.00  5035.9  405.35  5042.9  405.91
  5049.3  405.92  5057.2  406.22  5063.7  406.81  5071.6  407.19  5078.0  407.91
  5085.9  408.18  5106.7  408.50  5113.4  408.82  5121.1  409.51  5138.4  409.94
#Mann=4,-1,0
  4901.7    0.05       0  4983.0    0.05       0  4987.0    0.05       0
  5004.5   0.035       0
Bank Sta=4983,4987
Exp/Cntr=0.3,0.1

Type RM Length L Ch R = 1,1276,80,80,80
BEGIN DESCRIPTION:
Twin Creek2011275.83
END DESCRIPTION:
XS GIS Cut Line= 3
      2734005.39      6803742.39      2734099.58      6803840.94
      2734187.71      6803923.10
#Sta/Elev= 30
  4865.4  408.66  4867.9  408.66  4872.0  408.19  4886.1  407.34  4900.3  406.09
  4907.2  405.87  4914.4  405.90  4928.6  405.09  4935.5  405.56  4942.7  404.88
  4949.6  405.33  4956.9  404.69  4963.8  404.91  4971.0  404.85  4983.2  403.31
  4983.4  402.81  4986.9  402.81  4987.2  403.31  4992.1  403.41  4998.3  404.02
  5001.7  404.02  5013.2  404.54  5027.4  405.64  5034.7  405.91  5041.6  405.79
  5048.9  406.08  5070.7  406.34  5091.4  406.87  5117.6  408.13  5122.2  408.13
#Mann=4,-1,0
  4865.4    0.05       0  4983.2    0.05       0  4987.2    0.05       0
  5070.7   0.035       0
Bank Sta=4983.2,4987.2
Exp/Cntr=0.3,0.1

Type RM Length L Ch R = 1,1196,127,127,127
BEGIN DESCRIPTION:
Twin Creek2011195.79
END DESCRIPTION:
XS GIS Cut Line= 3
      2733947.03      6803760.47      2734026.44      6803863.02
      2734101.16      6803963.11
#Sta/Elev= 30
  4872.9  408.87  4876.2  408.87  4879.6  408.72  4886.2  408.28  4899.6  407.96
  4903.1  407.84  4914.9  407.34  4936.8  404.49  4943.9  403.69  4950.2  403.54
  4958.4  402.26  4964.7  401.90  4972.9  401.82  4979.2  402.24  4985.4  401.38
  4985.6  400.88  4989.1  400.88  4989.4  401.38  4998.2  402.21  5008.3  402.07
  5014.5  402.65  5022.9  402.50  5050.0  403.64  5064.5  404.75  5072.9  405.59
  5087.4  406.14  5093.7  406.55  5108.3  407.16  5122.9  407.56  5127.5  407.32
#Mann=5,-1,0
  4872.9    0.05       0  4899.6   0.035       0  4903.1    0.05       0
  4985.4    0.05       0  4989.4    0.05       0
Bank Sta=4985.4,4989.4
Exp/Cntr=0.3,0.1

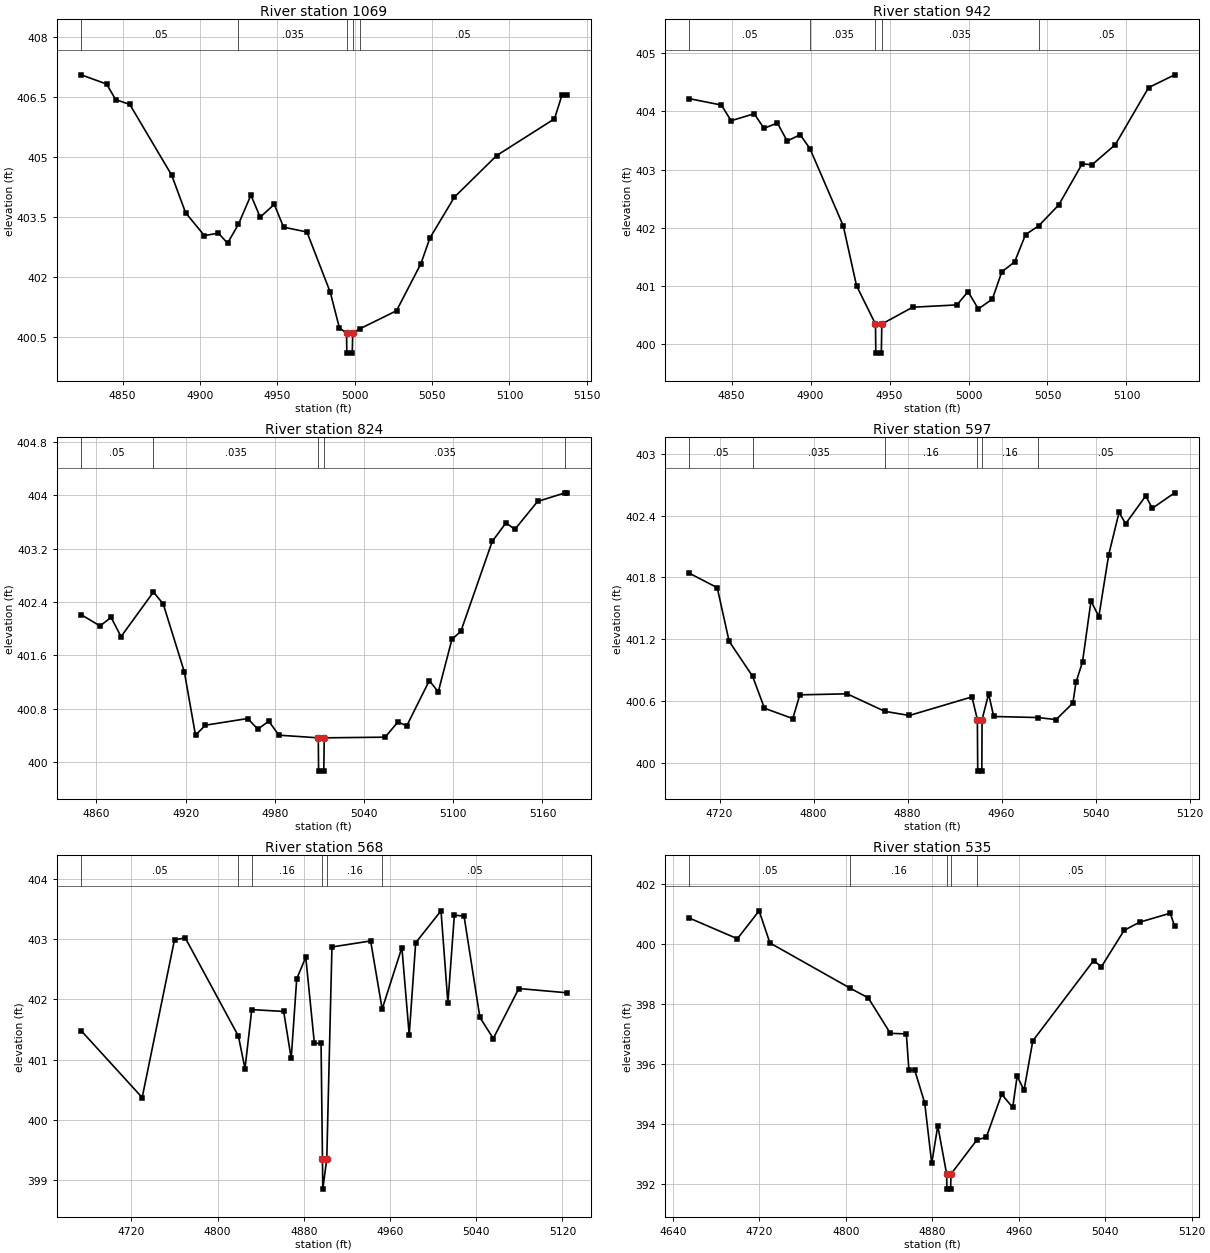
Type RM Length L Ch R = 1,1069,127,127,127
BEGIN DESCRIPTION:
Twin Creek2011068.86
END DESCRIPTION:
XS GIS Cut Line= 3
      2733779.61      6803825.51      2733928.07      6803923.19
      2734045.99      6803990.92
#Sta/Elev= 30
  4823.2  407.05  4839.6  406.82  4845.5  406.43  4854.6  406.31  4881.7  404.54
  4890.7  403.60  4902.8  403.03  4911.9  403.09  4917.8  402.84  4924.8  403.31
  4932.9  404.04  4938.9  403.49  4948.0  403.81  4954.0  403.24  4969.1  403.12
  4984.2  401.61  4990.1  400.72  4994.7  400.59  4994.9  400.09  4998.4  400.09
  4998.7  400.59  5003.4  400.70  5027.0  401.15  5042.8  402.33  5048.6  402.97
  5064.4  403.99  5091.7  405.03  5129.1  405.95  5134.0  406.55  5136.9  406.55
#Mann=5,-1,0
  4823.2    0.05       0  4924.8   0.035       0  4994.7   0.035       0
  4998.7   0.035       0  5003.4    0.05       0
Bank Sta=4994.7,4998.7
Exp/Cntr=0.3,0.1

Type RM Length L Ch R = 1,942,118,118,118
BEGIN DESCRIPTION:
Twin Creek201942.09
END DESCRIPTION:
XS GIS Cut Line= 3
      2733719.49      6803920.44      2733862.24      6804025.55
      2733969.91      6804098.45
#Sta/Elev= 30
  4823.2  404.22  4843.5  404.11  4849.7  403.84  4864.3  403.96  4870.5  403.71
  4879.0  403.80  4885.2  403.49  4893.4  403.60  4899.6  403.36  4920.7  402.03
  4929.1  401.00  4941.1  400.34  4941.3  399.84  4944.8  399.84  4945.1  400.34
  4964.6  400.63  4992.7  400.67  4999.7  400.90  5006.2  400.60  5015.1  400.77
  5021.1  401.24  5029.2  401.41  5036.1  401.88  5044.4  402.03  5057.1  402.39
  5072.0  403.10  5078.1  403.08  5093.0  403.43  5114.0  404.41  5130.5  404.63
#Mann=5,-1,0
  4823.2    0.05       0  4899.6   0.035       0  4941.1   0.035       0
  4945.1   0.035       0  5044.4    0.05       0
Bank Sta=4941.1,4945.1
Exp/Cntr=0.3,0.1

Type RM Length L Ch R = 1,824,227,227,227
BEGIN DESCRIPTION:
Twin Creek201823.63
END DESCRIPTION:
XS GIS Cut Line= 3
      2733668.67      6804010.18      2733779.35      6804110.18
      2733928.76      6804205.70
#Sta/Elev= 30
  4849.7  402.21  4862.4  402.04  4869.8  402.17  4876.5  401.88  4898.3  402.55
  4904.9  402.37  4919.1  401.35  4926.6  400.40  4933.3  400.55  4961.7  400.65
  4968.5  400.49  4975.9  400.61  4982.7  400.40  5009.2  400.36  5009.4  399.86
  5012.9  399.86  5013.2  400.36  5054.2  400.37  5062.8  400.60  5068.7  400.54
  5083.9  401.22  5089.9  401.05  5099.1  401.84  5105.1  401.96  5126.2  403.31
  5135.5  403.59  5141.4  403.49  5156.7  403.91  5175.2  404.04  5176.2  404.04
#Mann=5,-1,0
  4849.7    0.05       0  4898.3   0.035       0  5009.2   0.035       0
  5013.2   0.035       0  5175.2    0.05       0
Bank Sta=5009.2,5013.2
Exp/Cntr=0.3,0.1

Type RM Length L Ch R = 1,597,29,29,29
BEGIN DESCRIPTION:
Twin Creek201597.23
END DESCRIPTION:
XS GIS Cut Line= 6
      2733682.86      6804037.28      2733699.82      6804217.71
      2733711.45      6804248.47      2733741.24      6804282.42
      2733780.06      6804307.58      2733876.64      6804354.90
#Sta/Elev= 30
  4694.2  401.84  4718.0  401.70  4728.1  401.18  4748.1  400.84  4758.2  400.53
  4782.3  400.43  4788.3  400.66  4828.5  400.67  4860.6  400.50  4881.5  400.46
  4934.8  400.64  4939.4  400.42  4939.7  399.92  4943.2  399.92  4943.4  400.42
  4949.0  400.67  4953.3  400.45  4990.7  400.44  5006.4  400.42  5020.7  400.58
  5023.3  400.78  5028.9  400.98  5036.1  401.57  5042.8  401.42  5051.2  402.02
  5060.0  402.43  5065.6  402.32  5082.7  402.59  5088.3  402.47  5107.3  402.62
#Mann=6,-1,0
  4694.2    0.05       0  4748.1   0.035       0  4860.6    0.16       0
  4939.4    0.05       0  4943.4    0.16       0  4990.7    0.05       0
Bank Sta=4939.4,4943.4
Exp/Cntr=0.3,0.1

Type RM Length L Ch R = 1,568,33,33,33
BEGIN DESCRIPTION:
Twin Creek201568.39
END DESCRIPTION:
XS GIS Cut Line= 6
      2733667.98      6804044.55      2733658.97      6804187.16
      2733676.04      6804261.69      2733720.98      6804301.54
      2733760.93      6804328.80      2733862.83      6804397.00
#Sta/Elev= 30
  4673.4  401.48  4730.0  400.37  4760.0  402.99  4770.0  403.02  4819.3  401.39
  4825.4  400.85  4831.7  401.83  4861.3  401.80  4868.3  401.02  4873.4  402.34
  4881.8  402.70  4889.8  401.27  4896.0  401.27  4897.3  399.35  4897.6  398.85
  4901.3  399.35  4906.1  402.87  4942.0  402.97  4952.7  401.84  4971.0  402.86
  4977.8  401.41  4983.8  402.94  5007.3  403.47  5013.7  401.94  5019.7  403.40
  5028.7  403.38  5043.4  401.70  5055.8  401.35  5079.5  402.18  5123.8  402.11
#Mann=6,-1,0
  4673.4    0.05       0  4819.3   0.035       0  4831.7    0.16       0
  4897.3    0.05       0  4901.3    0.16       0  4952.7    0.05       0
Bank Sta=4897.3,4901.3
Exp/Cntr=0.3,0.1

Type RM Length L Ch R = 1,535,160,160,160
BEGIN DESCRIPTION:
Twin Creek201534.63
END DESCRIPTION:
XS GIS Cut Line= 6
      2733644.39      6804046.82      2733628.71      6804186.54
      2733642.00      6804249.60      2733661.10      6804288.15
      2733736.08      6804351.57      2733805.69      6804427.02
#Sta/Elev= 30
  4655.2  400.85  4699.7  400.16  4719.8  401.09  4729.8  400.02  4804.2  398.51
  4820.8  398.19  4841.2  397.01  4856.0  396.99  4858.4  395.78  4863.8  395.78
  4873.0  394.69  4879.5  392.68  4885.1  393.93  4893.3  392.32  4893.5  391.82
  4897.0  391.82  4897.3  392.32  4921.3  393.46  4930.0  393.55  4944.2  394.98
  4954.4  394.54  4958.5  395.58  4964.9  395.12  4973.0  396.76  5029.2  399.43
  5036.5  399.23  5057.5  400.44  5071.7  400.71  5100.1  401.01  5104.2  400.58
#Mann=5,-1,0
  4655.2    0.05       0  4804.2    0.16       0  4893.3    0.05       0
  4897.3    0.16       0  4921.3    0.05       0
Bank Sta=4893.3,4897.3
Exp/Cntr=0.3,0.1

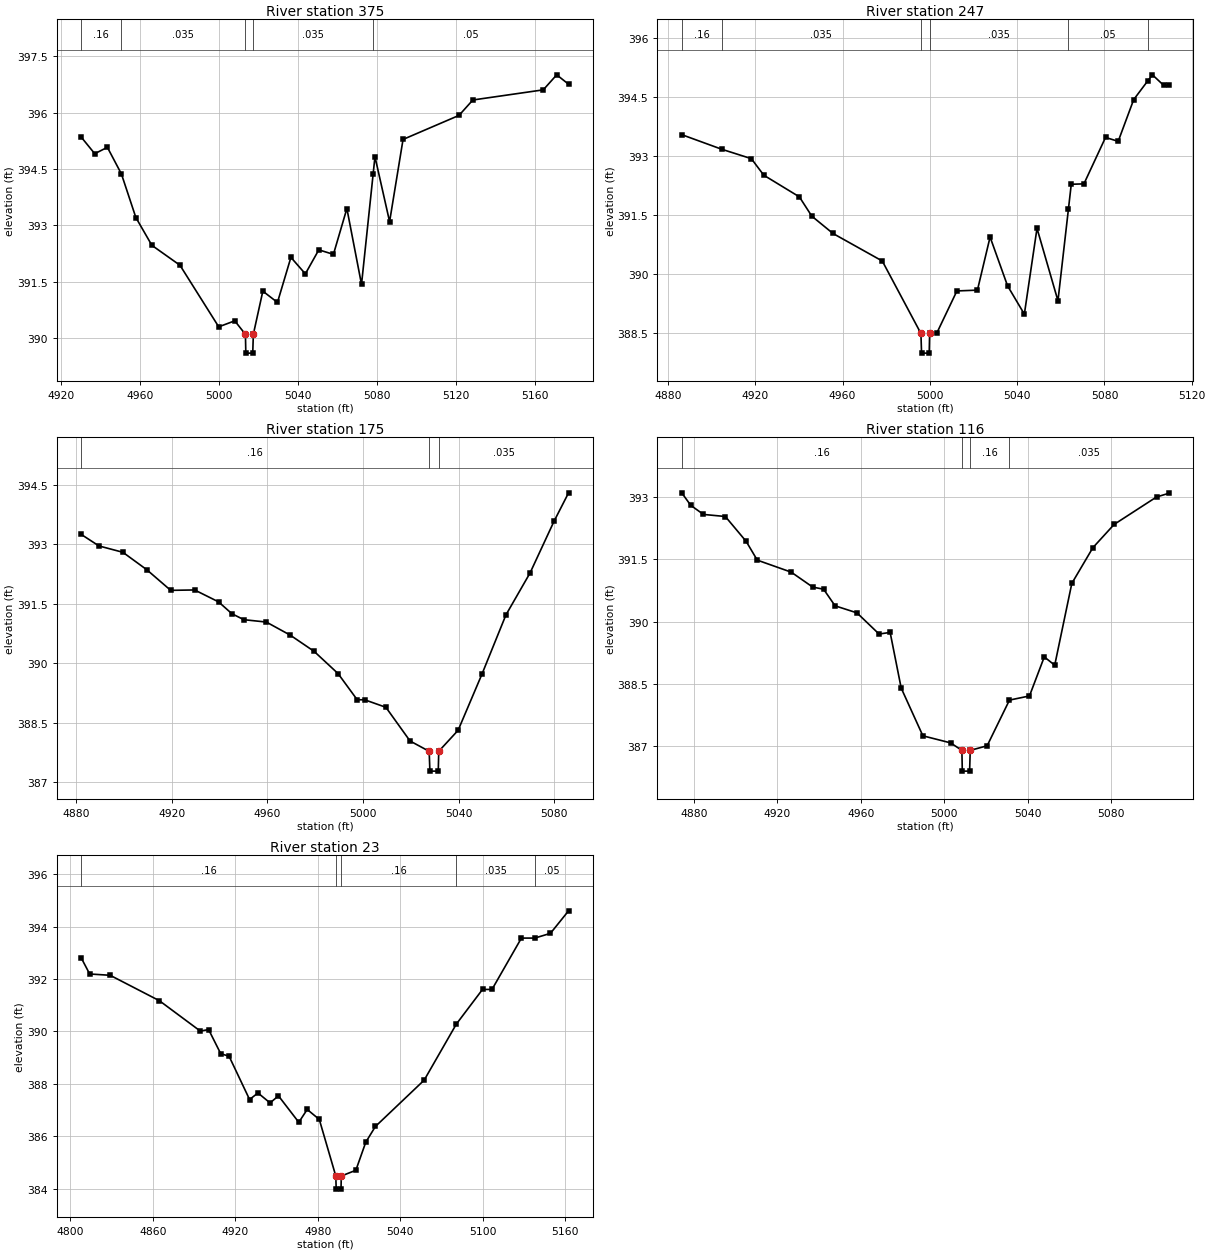
Type RM Length L Ch R = 1,375,128,128,128
BEGIN DESCRIPTION:
Twin Creek201375.33
END DESCRIPTION:
XS GIS Cut Line= 3
      2733555.81      6804281.85      2733599.23      6804336.92
      2733718.58      6804466.64
#Sta/Elev= 30
  4930.4  395.35  4937.2  394.91  4943.6  395.08  4950.7  394.37  4958.0  393.21
  4966.1  392.47  4980.3  391.94  4999.9  390.30  5008.0  390.46  5013.4  390.10
  5013.6  389.60  5017.1  389.60  5017.4  390.10  5022.2  391.25  5029.6  390.95
  5036.4  392.15  5043.7  391.71  5050.5  392.35  5057.9  392.23  5064.7  393.45
  5072.1  391.43  5078.0  394.38  5078.9  394.83  5086.3  393.10  5093.1  395.29
  5121.4  395.93  5128.4  396.34  5164.0  396.61  5170.8  397.01  5176.8  396.76
#Mann=5,-1,0
  4930.4    0.16       0  4950.7   0.035       0  5013.4   0.035       0
  5017.4   0.035       0  5078.0    0.05       0
Bank Sta=5013.4,5017.4
Exp/Cntr=0.3,0.1

Type RM Length L Ch R = 1,247,72,72,72
BEGIN DESCRIPTION:
Twin Creek201247.34
END DESCRIPTION:
XS GIS Cut Line= 3
      2733545.02      6804339.77      2733598.55      6804440.82
      2733653.40      6804534.95
#Sta/Elev= 30
  4886.3  393.54  4904.6  393.17  4918.2  392.93  4923.9  392.51  4940.2  391.96
  4945.9  391.47  4955.6  391.03  4978.2  390.33  4995.9  388.49  4996.2  387.99
  4999.7  387.99  4999.9  388.49  5003.1  388.49  5012.4  389.57  5021.8  389.59
  5027.6  390.94  5035.6  389.70  5043.3  388.98  5049.1  391.16  5058.7  389.32
  5063.5  391.65  5064.8  392.28  5070.6  392.29  5080.5  393.47  5086.3  393.37
  5093.4  394.43  5099.9  394.91  5102.0  395.06  5107.2  394.79  5109.6  394.79
#Mann=6,-1,0
  4886.3    0.16       0  4904.6   0.035       0  4995.9   0.035       0
  4999.9   0.035       0  5063.5    0.05       0  5099.9   0.035       0
Bank Sta=4995.9,4999.9
Exp/Cntr=0.3,0.1

Type RM Length L Ch R = 1,175,59,59,59
BEGIN DESCRIPTION:
Twin Creek201174.98
END DESCRIPTION:
XS GIS Cut Line= 3
      2733529.66      6804343.64      2733532.16      6804462.11
      2733540.02      6804547.05
#Sta/Elev= 27
  4882.2  393.25  4889.6  392.96  4899.6  392.80  4909.6  392.36  4919.6  391.84
  4929.6  391.85  4939.6  391.55  4945.2  391.25  4950.2  391.10  4959.6  391.04
  4969.6  390.71  4979.6  390.30  4989.6  389.74  4997.6  389.08  5000.7  389.08
  5009.6  388.89  5019.7  388.04  5027.7  387.78  5028.0  387.28  5031.5  387.28
  5031.7  387.78  5039.8  388.31  5049.8  389.73  5059.8  391.22  5069.9  392.28
  5079.9  393.58  5086.0  394.30
#Mann=3,-1,0
  4882.2    0.16       0  5027.7    0.07       0  5031.7   0.035       0
Bank Sta=5027.7,5031.7
Exp/Cntr=0.3,0.1

Type RM Length L Ch R = 1,116,93,93,93
BEGIN DESCRIPTION:
Twin Creek201115.82
END DESCRIPTION:
XS GIS Cut Line= 3
      2733512.06      6804341.12      2733472.76      6804461.40
      2733490.69      6804566.95
#Sta/Elev= 30
  4874.2  393.10  4878.5  392.80  4884.6  392.58  4895.1  392.53  4905.1  391.93
  4910.4  391.48  4926.7  391.19  4937.0  390.83  4942.2  390.78  4947.7  390.38
  4958.2  390.21  4968.8  389.70  4974.1  389.74  4979.4  388.40  4989.8  387.25
  5003.1  387.08  5008.5  386.90  5008.7  386.40  5012.2  386.40  5012.5  386.90
  5020.6  387.01  5031.3  388.11  5040.9  388.21  5048.0  389.15  5053.0  388.95
  5061.2  390.92  5071.3  391.78  5081.5  392.34  5101.8  393.00  5107.8  393.09
#Mann=4,-1,0
  4874.2    0.16       0  5008.5    0.07       0  5012.5    0.16       0
  5031.3   0.035       0
Bank Sta=5008.5,5012.5
Exp/Cntr=0.3,0.1

Type RM Length L Ch R = 1,23,0,0,0
BEGIN DESCRIPTION:
Twin Creek20123.219
END DESCRIPTION:
XS GIS Cut Line= 3
      2733501.00      6804335.99      2733391.97      6804494.15
      2733508.73      6804606.88
#Sta/Elev= 30
  4807.9  392.80  4814.0  392.19  4828.9  392.14  4864.7  391.17  4894.5  390.01
  4900.5  390.07  4909.3  389.15  4915.4  389.05  4930.3  387.40  4936.4  387.65
  4945.2  387.27  4951.3  387.54  4966.1  386.53  4972.2  387.02  4981.0  386.64
  4993.0  384.48  4993.3  383.98  4996.8  383.98  4997.0  384.48  5007.6  384.70
  5014.8  385.77  5021.8  386.37  5057.3  388.14  5080.7  390.28  5099.7  391.60
  5106.6  391.60  5128.0  393.56  5137.7  393.56  5149.1  393.74  5162.3  394.60
#Mann=5,-1,0
  4807.9    0.16       0  4993.0    0.07       0  4997.0    0.16       0
  5080.7   0.035       0  5137.7    0.05       0
Bank Sta=4993,4997
Exp/Cntr=0.3,0.1

Chan Stop Cuts=-1