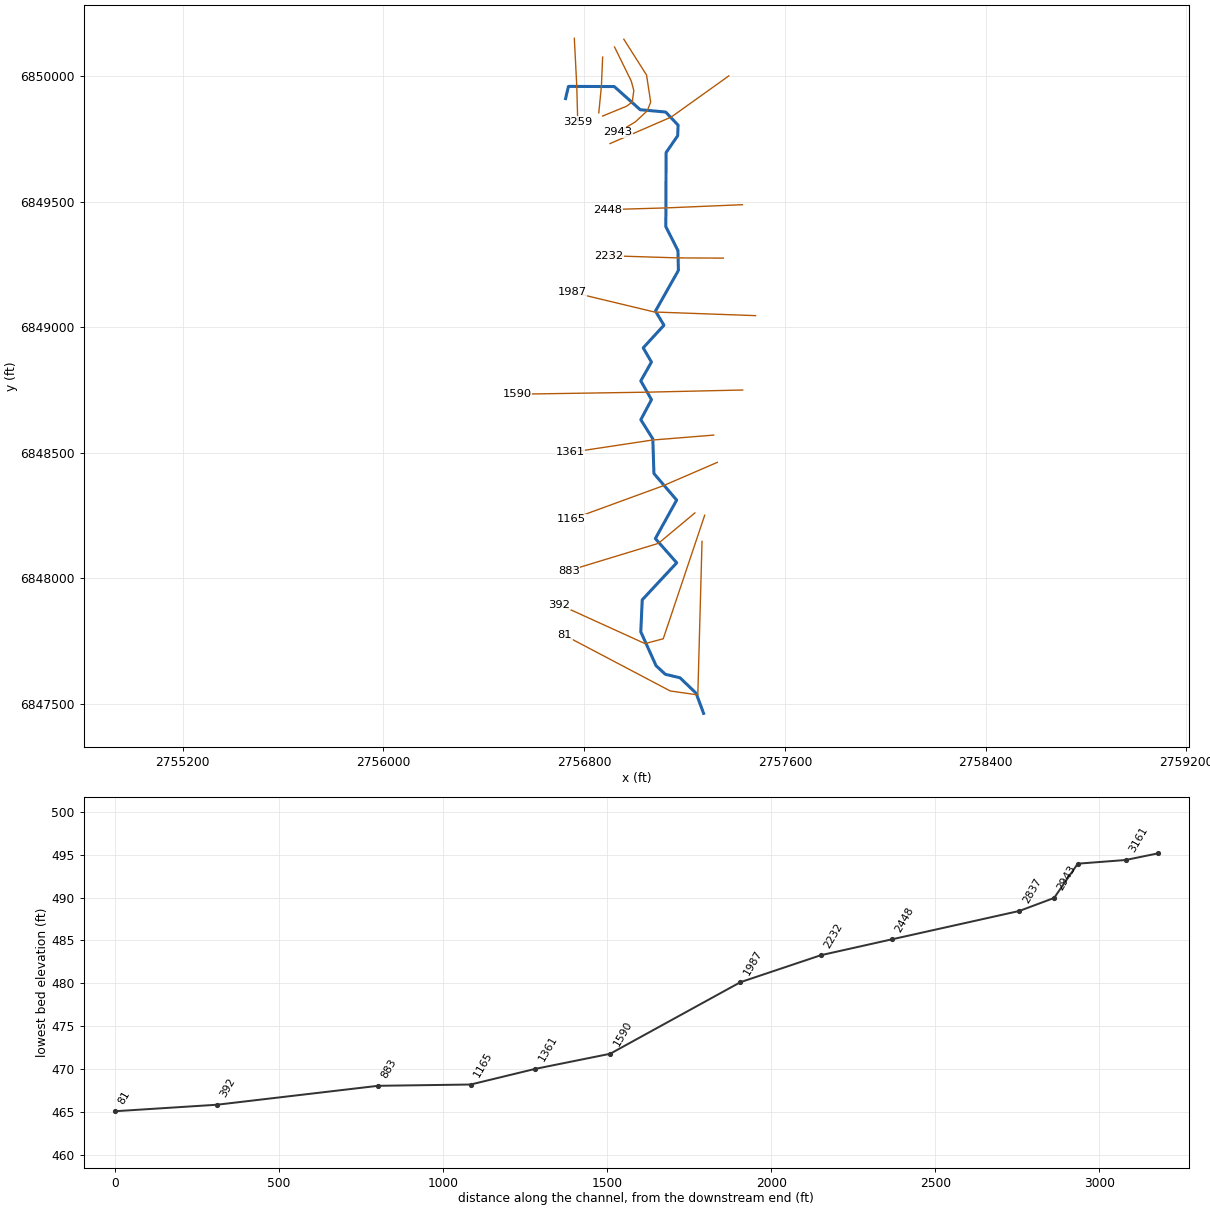
--- Twin Creek203.prj (project) ---

Proj Title=Twin Creek203 Base Level Engineering
Current Plan=p01
Default Exp/Contr=0.3,0.1
English Units
Geom File=g01
Flow File=f01
Plan File=p01
BEGIN DESCRIPTION:
Twin Creek203
END DESCRIPTION:

--- Twin Creek203.p01 (plan) ---

Plan Title=Multiple Run
Short Identifier=Multiple
Geom File=g01
Flow File=f01
Subcritical Flow
K Sum by GR= 0
Std Step Tol= 0.01
Critical Tol= 0.01
Num of Std Step Trials= 20
Max Error Tol= 0.3
Flow Tol Ratio= 0.001
Split Flow NTrial= 30
Split Flow Tol= 0.02
Split Flow Ratio= 0.02
Log Output Level= 0
Friction Slope Method= 1
Unsteady Friction Slope Method= 2
Unsteady Bridges Friction Slope Method= 1
Parabolic Critical Depth
Global Vel Dist=  1 , 1 , 1
Global Log Level= 0
CheckData=True
Encroach Param= -1, 0, 0, 0
BEGIN DESCRIPTION:
Multiple Run
END DESCRIPTION:

--- Twin Creek203.f01 (steady flow) ---

Flow Title=Multiple
Number of Profiles=7
Profile Names=10-year,25-year,50-year,1pct_min,100-year,1pct_plu,500-year
River Rch & RM= Twin Creek203,Reach-1,3259
     285     367     432     253     506    1009     693
Boundary for River Rch & Prof#=Twin Creek203,Reach-1,1
Up Type=0
Dn Type=3
Dn Slope=0.005
Boundary for River Rch & Prof#=Twin Creek203,Reach-1,2
Up Type=0
Dn Type=3
Dn Slope=0.005
Boundary for River Rch & Prof#=Twin Creek203,Reach-1,3
Up Type=0
Dn Type=3
Dn Slope=0.005
Boundary for River Rch & Prof#=Twin Creek203,Reach-1,4
Up Type=0
Dn Type=3
Dn Slope=0.005
Boundary for River Rch & Prof#=Twin Creek203,Reach-1,5
Up Type=0
Dn Type=3
Dn Slope=0.005
Boundary for River Rch & Prof#=Twin Creek203,Reach-1,6
Up Type=0
Dn Type=3
Dn Slope=0.005
Boundary for River Rch & Prof#=Twin Creek203,Reach-1,7
Up Type=0
Dn Type=3
Dn Slope=0.005

--- Twin Creek203.g01 (geometry) ---

Geom Title=Existing Conditions

River Reach=Twin Creek203,Reach-1
Reach XY= 30
      2756726.00      6849911.00      2756737.43      6849959.57
      2756920.14      6849958.94      2757023.58      6849866.54
      2757124.78      6849857.47      2757174.47      6849805.17
      2757172.67      6849762.78      2757126.54      6849695.79
      2757125.55      6849400.81      2757173.83      6849305.02
      2757175.63      6849226.27      2757084.25      6849064.23
      2757117.98      6849007.66      2757035.33      6848917.67
      2757068.16      6848861.09      2757025.77      6848786.00
      2757068.38      6848711.00      2757025.79      6848631.21
      2757073.70      6848555.07      2757078.08      6848416.86
      2757168.70      6848311.08      2757083.80      6848157.59
      2757168.90      6848061.00      2757031.45      6847913.45
      2757025.76      6847785.92      2757086.63      6847651.00
      2757123.46      6847616.75      2757182.05      6847602.85
      2757246.35      6847541.22      2757276.00      6847461.00

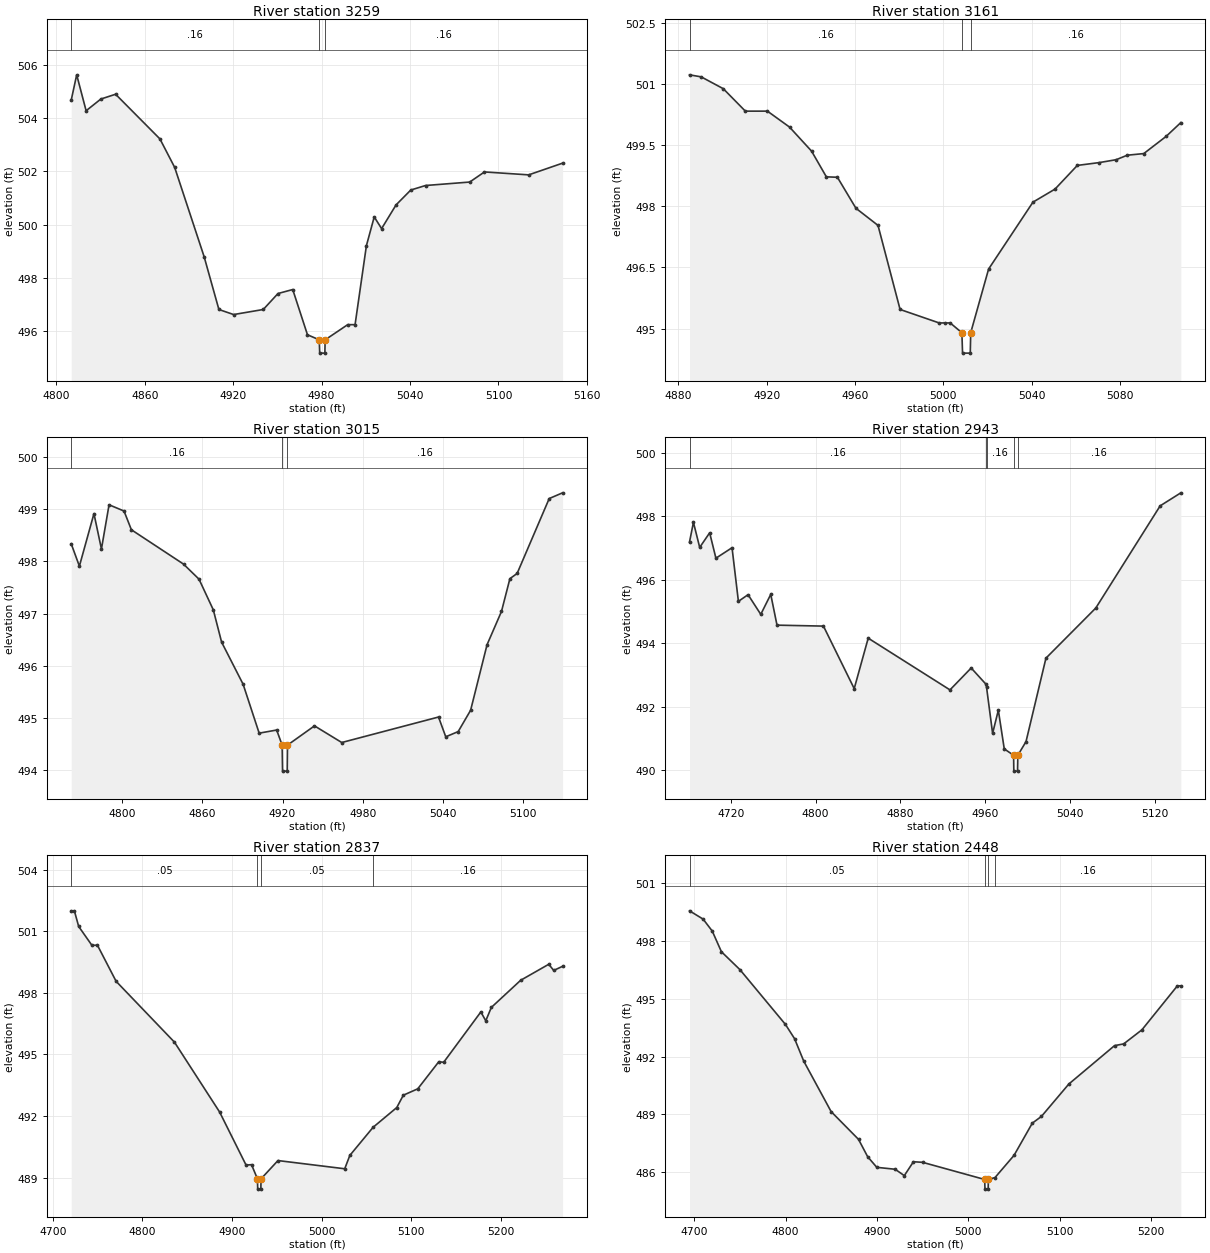
Type RM Length L Ch R = 1,3259,98,98,98
BEGIN DESCRIPTION:
Twin Creek2033204.06
END DESCRIPTION:
XS GIS Cut Line= 3
      2756760.89      6850151.10      2756770.56      6849961.45
      2756774.50      6849818.00
#Sta/Elev= 30
  4810.1  504.68  4813.8  505.63  4820.2  504.28  4830.2  504.72  4840.2  504.90
  4870.3  503.22  4880.3  502.15  4900.3  498.79  4910.3  496.81  4920.3  496.62
  4940.4  496.81  4950.4  497.41  4960.4  497.56  4970.4  495.86  4978.4  495.67
  4978.7  495.17  4982.2  495.17  4982.4  495.67  4997.7  496.24  5002.7  496.24
  5010.4  499.21  5015.7  500.29  5020.7  499.85  5030.5  500.74  5040.5  501.30
  5050.5  501.47  5080.5  501.60  5090.5  501.98  5120.5  501.87  5143.5  502.31
#Mann=3,-1,0
  4810.1    0.16       0  4978.4    0.07       0  4982.4    0.16       0
Bank Sta=4978.4,4982.4
Exp/Cntr=0.3,0.1

Type RM Length L Ch R = 1,3161,146,146,146
BEGIN DESCRIPTION:
Mapping XS aaacd183
END DESCRIPTION:
XS GIS Cut Line= 3
      2756873.69      6850076.29      2756868.80      6849960.58
      2756858.38      6849854.30
#Sta/Elev= 29
  4885.0  501.22  4890.3  501.17  4900.3  500.88  4910.3  500.33  4920.3  500.33
  4930.3  499.94  4940.3  499.35  4947.0  498.72  4952.0  498.71  4960.4  497.95
  4970.4  497.53  4980.4  495.47  4998.1  495.14  5000.8  495.14  5003.1  495.14
  5008.4  494.90  5008.7  494.40  5012.2  494.40  5012.4  494.90  5020.5  496.46
  5040.6  498.10  5050.6  498.42  5060.7  499.00  5070.7  499.07  5078.3  499.14
  5083.3  499.25  5090.8  499.29  5100.9  499.71  5107.6  500.05
#Mann=3,-1,0
  4885.0    0.16       0  5008.4    0.07       0  5012.4    0.16       0
Bank Sta=5008.4,5012.4
Exp/Cntr=0.3,0.1

Type RM Length L Ch R = 1,3015,72,72,72
BEGIN DESCRIPTION:
Mapping XS 32ed9170
END DESCRIPTION:
XS GIS Cut Line= 6
      2756921.17      6850116.45      2756987.83      6849980.58
      2756997.92      6849942.94      2756991.69      6849897.33
      2756969.15      6849880.54      2756873.71      6849841.42
#Sta/Elev= 30
  4761.9  498.34  4768.0  497.91  4778.9  498.92  4784.5  498.24  4790.2  499.09
  4801.4  498.97  4806.9  498.61  4845.9  497.95  4857.5  497.66  4868.2  497.07
  4874.4  496.45  4890.5  495.64  4902.5  494.70  4915.6  494.76  4919.7  494.47
  4920.0  493.97  4923.5  493.97  4923.7  494.47  4943.9  494.84  4964.3  494.52
  5036.7  495.01  5042.1  494.63  5051.4  494.73  5060.7  495.14  5073.0  496.40
  5083.8  497.04  5090.1  497.67  5095.5  497.77  5119.5  499.21  5129.5  499.32
#Mann=3,-1,0
  4761.9    0.16       0  4919.7    0.07       0  4923.7    0.16       0
Bank Sta=4919.7,4923.7
Exp/Cntr=0.3,0.1

Type RM Length L Ch R = 1,2943,106,106,106
BEGIN DESCRIPTION:
Mapping XS 96845d28
END DESCRIPTION:
XS GIS Cut Line= 6
      2756958.05      6850147.63      2757048.74      6850004.79
      2757065.13      6849896.95      2757051.30      6849861.98
      2757004.62      6849818.63      2756934.28      6849775.91
#Sta/Elev= 30
  4681.2  497.19  4684.9  497.81  4690.8  497.02  4700.2  497.48  4706.1  496.68
  4721.3  497.01  4727.3  495.32  4736.4  495.53  4748.4  494.91  4757.8  495.54
  4763.7  494.57  4807.5  494.54  4836.5  492.57  4849.7  494.16  4926.8  492.53
  4946.8  493.22  4960.7  492.71  4961.3  492.61  4967.0  491.16  4972.4  491.89
  4978.0  490.67  4986.8  490.47  4987.0  489.97  4990.5  489.97  4990.8  490.47
  4998.5  490.90  5017.3  493.53  5064.3  495.11  5125.0  498.33  5144.5  498.74
#Mann=5,-1,0
  4681.2    0.16       0  4960.7    0.05       0  4961.3    0.16       0
  4986.8    0.07       0  4990.8    0.16       0
Bank Sta=4986.8,4990.8
Exp/Cntr=0.3,0.1

Type RM Length L Ch R = 1,2837,389,389,389
BEGIN DESCRIPTION:
Mapping XS bd7733d4
END DESCRIPTION:
XS GIS Cut Line= 3
      2757376.73      6850001.57      2757147.22      6849837.54
      2756903.03      6849731.57
#Sta/Elev= 30
  4720.5  501.99  4724.0  501.99  4728.8  501.23  4743.6  500.31  4749.7  500.32
  4770.6  498.56  4835.7  495.60  4886.1  492.20  4915.6  489.62  4921.7  489.64
  4928.3  488.95  4928.6  488.45  4932.1  488.45  4932.3  488.95  4951.2  489.84
  5025.7  489.44  5031.4  490.09  5057.4  491.46  5083.8  492.42  5091.1  493.02
  5107.2  493.33  5130.7  494.65  5136.1  494.62  5177.6  497.07  5183.1  496.64
  5189.3  497.29  5222.0  498.61  5253.4  499.39  5258.9  499.09  5268.8  499.29
#Mann=4,-1,0
  4720.5    0.05       0  4928.3    0.05       0  4932.3    0.05       0
  5057.4    0.16       0
Bank Sta=4928.3,4932.3
Exp/Cntr=0.3,0.1

Type RM Length L Ch R = 1,2448,216,216,216
BEGIN DESCRIPTION:
Mapping XS 137a8a6e
END DESCRIPTION:
XS GIS Cut Line= 3
      2757430.87      6849488.12      2757125.47      6849475.28
      2756893.44      6849468.55
#Sta/Elev= 30
  4694.8  499.56  4709.7  499.13  4719.7  498.51  4729.7  497.44  4750.0  496.51
  4799.8  493.67  4809.8  492.93  4819.8  491.77  4849.8  489.15  4879.8  487.71
  4889.8  486.81  4899.8  486.26  4919.9  486.16  4929.9  485.83  4939.9  486.55
  4949.9  486.52  5017.9  485.63  5018.2  485.13  5021.7  485.13  5021.9  485.63
  5029.2  485.73  5050.0  486.88  5070.0  488.55  5080.0  488.90  5110.0  490.58
  5160.0  492.57  5170.0  492.66  5190.0  493.39  5228.8  495.67  5232.6  495.67
#Mann=4,-1,0
  4694.8    0.05       0  5017.9    0.05       0  5021.9    0.05       0
  5029.2    0.16       0
Bank Sta=5017.9,5021.9
Exp/Cntr=0.3,0.1

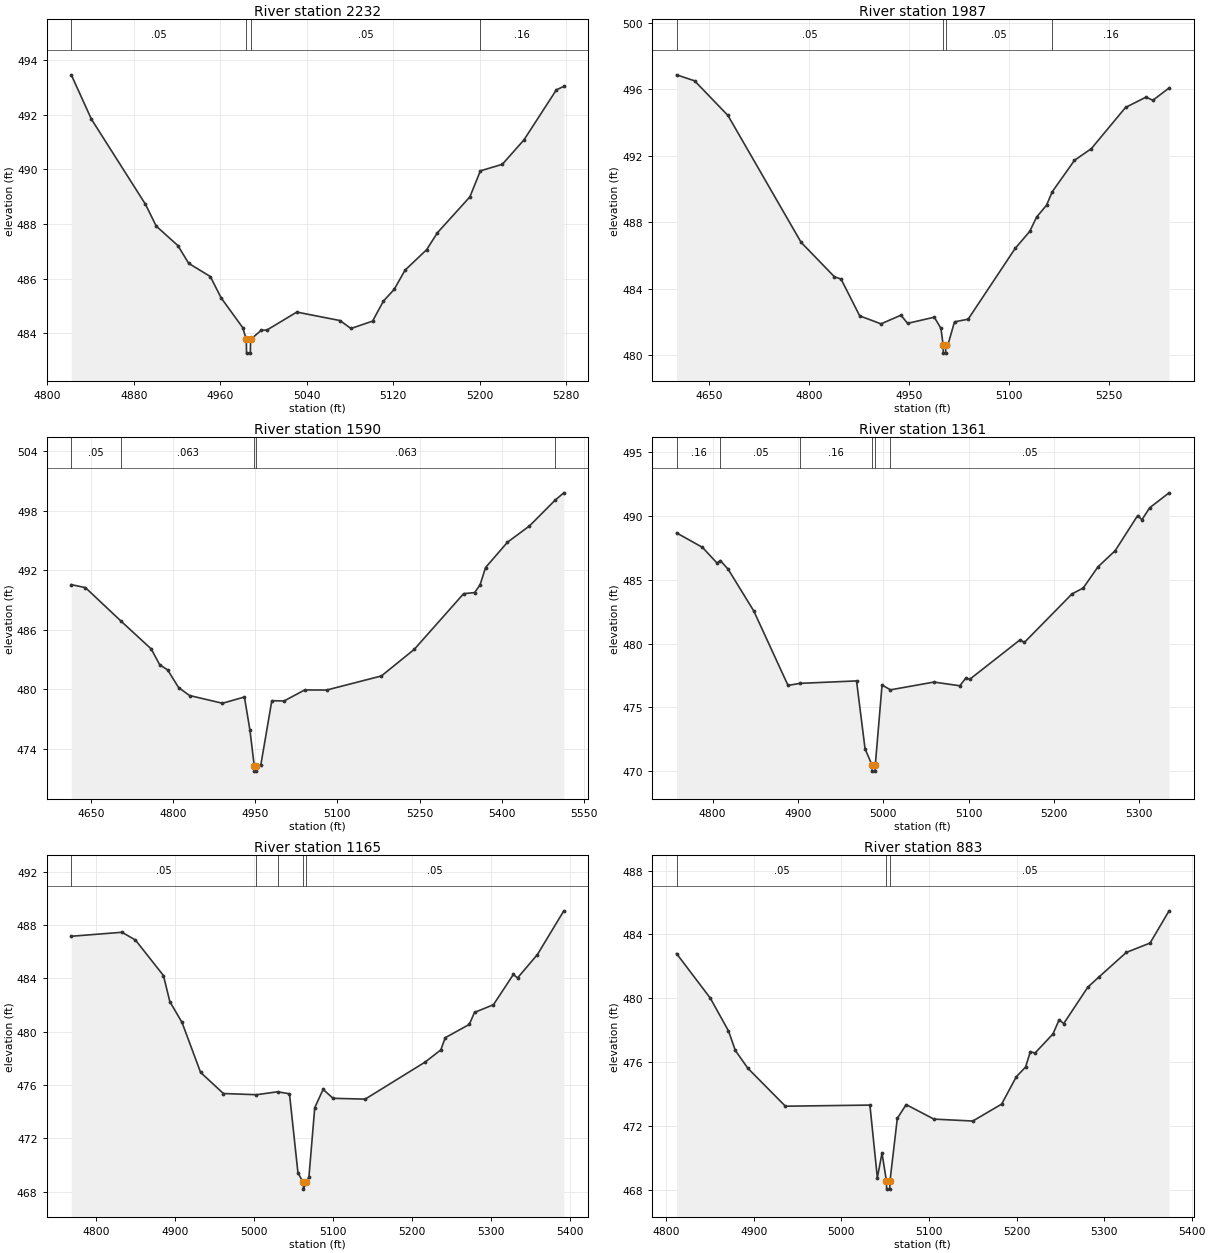
Type RM Length L Ch R = 1,2232,245,245,245
BEGIN DESCRIPTION:
Twin Creek2032269.907
END DESCRIPTION:
XS GIS Cut Line= 3
      2757354.61      6849275.27      2757176.71      6849276.06
      2756899.15      6849284.73
#Sta/Elev= 30
  4822.1  493.45  4840.7  491.83  4890.7  488.72  4900.7  487.92  4920.7  487.21
  4930.7  486.56  4950.7  486.08  4960.7  485.30  4980.7  484.21  4984.0  483.78
  4984.2  483.28  4987.7  483.28  4988.0  483.78  4997.9  484.12  5002.9  484.12
  5030.7  484.78  5070.7  484.47  5080.8  484.18  5100.8  484.45  5110.8  485.18
  5120.8  485.61  5130.8  486.31  5150.8  487.06  5160.8  487.68  5190.8  488.99
  5200.5  489.94  5220.8  490.18  5240.8  491.07  5270.8  492.90  5277.7  493.03
#Mann=4,-1,0
  4822.1    0.05       0  4984.0    0.05       0  4988.0    0.05       0
  5200.5    0.16       0
Bank Sta=4984,4988
Exp/Cntr=0.3,0.1

Type RM Length L Ch R = 1,1987,397,397,397
BEGIN DESCRIPTION:
Mapping XS dc97344d
END DESCRIPTION:
XS GIS Cut Line= 3
      2757483.12      6849046.03      2757080.29      6849060.47
      2756752.36      6849139.07
#Sta/Elev= 30
  4600.5  496.86  4627.6  496.50  4677.7  494.42  4787.7  486.79  4837.8  484.72
  4847.8  484.58  4875.8  482.37  4907.8  481.89  4937.8  482.41  4947.8  481.92
  4987.9  482.29  4997.9  481.62  5001.2  480.63  5001.5  480.13  5005.0  480.13
  5005.2  480.63  5008.4  480.63  5018.3  482.01  5038.8  482.17  5109.4  486.42
  5131.4  487.45  5141.7  488.31  5156.6  489.02  5165.2  489.83  5198.6  491.72
  5223.9  492.42  5275.4  494.90  5306.2  495.52  5316.5  495.33  5340.8  496.07
#Mann=4,-1,0
  4600.5    0.05       0  5001.2    0.05       0  5005.2    0.05       0
  5165.2    0.16       0
Bank Sta=5001.2,5005.2
Exp/Cntr=0.3,0.1

Type RM Length L Ch R = 1,1590,229,229,229
BEGIN DESCRIPTION:
Twin Creek2031435.164
END DESCRIPTION:
XS GIS Cut Line= 3
      2757431.77      6848749.67      2757046.37      6848740.93
      2756533.23      6848733.00
#Sta/Elev= 30
  4614.5  490.54  4640.3  490.24  4705.4  486.86  4760.3  484.07  4775.9  482.47
  4790.3  481.96  4810.3  480.18  4830.3  479.38  4890.3  478.60  4930.4  479.23
  4940.4  475.92  4948.4  472.27  4948.6  471.77  4952.1  471.77  4952.4  472.27
  4960.4  472.41  4980.4  478.86  5002.7  478.83  5040.4  479.94  5080.4  479.93
  5180.4  481.35  5240.4  484.03  5330.4  489.63  5350.4  489.74  5360.4  490.52
  5370.4  492.26  5410.4  494.81  5450.4  496.44  5497.1  499.03  5513.2  499.78
#Mann=5,-1,0
  4614.5    0.05       0  4705.4   0.063       0  4948.4   0.063       0
  4952.4   0.063       0  5497.1   0.035       0
Bank Sta=4948.4,4952.4
Exp/Cntr=0.3,0.1

Type RM Length L Ch R = 1,1361,196,196,196
BEGIN DESCRIPTION:
Mapping XS a5e6257f
END DESCRIPTION:
XS GIS Cut Line= 3
      2757316.17      6848569.99      2757071.36      6848550.18
      2756743.59      6848500.65
#Sta/Elev= 30
  4757.8  488.67  4788.1  487.54  4805.2  486.31  4809.1  486.50  4818.2  485.83
  4848.3  482.55  4888.4  476.72  4902.8  476.88  4968.7  477.07  4978.7  471.74
  4986.7  470.50  4987.0  470.00  4990.5  470.00  4990.7  470.50  4998.6  476.75
  5008.4  476.37  5059.4  476.98  5089.7  476.69  5096.5  477.27  5101.6  477.21
  5160.3  480.29  5165.4  480.09  5221.2  483.89  5234.3  484.35  5251.6  486.01
  5271.8  487.28  5298.1  490.03  5303.1  489.70  5312.2  490.64  5334.9  491.81
#Mann=6,-1,0
  4757.8    0.16       0  4809.1    0.05       0  4902.8    0.16       0
  4986.7    0.07       0  4990.7    0.16       0  5008.4    0.05       0
Bank Sta=4986.7,4990.7
Exp/Cntr=0.3,0.1

Type RM Length L Ch R = 1,1165,282,282,282
BEGIN DESCRIPTION:
Mapping XS 6f652f7c
END DESCRIPTION:
XS GIS Cut Line= 3
      2757330.53      6848461.22      2757113.99      6848367.65
      2756749.76      6848234.50
#Sta/Elev= 30
  4768.1  487.17  4832.3  487.47  4849.3  486.89  4884.8  484.22  4892.9  482.26
  4908.3  480.70  4931.8  476.95  4960.7  475.36  5002.6  475.27  5029.3  475.49
  5044.4  475.34  5055.1  469.42  5061.7  468.68  5062.0  468.18  5065.7  468.68
  5069.0  469.07  5076.4  474.30  5087.0  475.67  5099.6  475.00  5140.3  474.94
  5216.4  477.73  5236.1  478.64  5241.6  479.55  5272.1  480.55  5278.7  481.45
  5302.7  482.03  5327.9  484.30  5333.2  484.04  5358.4  485.80  5391.8  489.08
#Mann=5,-1,0
  4768.1    0.05       0  5002.6    0.16       0  5029.3    0.05       0
  5061.7    0.05       0  5065.7    0.05       0
Bank Sta=5061.7,5065.7
Exp/Cntr=0.3,0.1

Type RM Length L Ch R = 1,883,491,491,491
BEGIN DESCRIPTION:
Mapping XS 47a1096f
END DESCRIPTION:
XS GIS Cut Line= 3
      2757241.46      6848259.91      2757096.06      6848138.61
      2756739.18      6848029.98
#Sta/Elev= 30
  4811.8  482.80  4850.3  480.01  4871.1  477.95  4878.9  476.73  4893.2  475.61
  4936.1  473.23  5032.6  473.30  5041.1  468.74  5046.4  470.29  5051.5  468.53
  5051.7  468.03  5055.2  468.03  5055.5  468.53  5063.9  472.47  5074.0  473.33
  5105.7  472.42  5150.1  472.30  5183.0  473.36  5199.8  475.08  5210.3  475.68
  5215.8  476.65  5221.1  476.56  5241.6  477.76  5248.7  478.65  5253.9  478.41
  5281.5  480.70  5293.9  481.32  5325.3  482.87  5352.5  483.46  5374.2  485.48
#Mann=3,-1,0
  4811.8    0.05       0  5051.5    0.05       0  5055.5    0.05       0
Bank Sta=5051.5,5055.5
Exp/Cntr=0.3,0.1

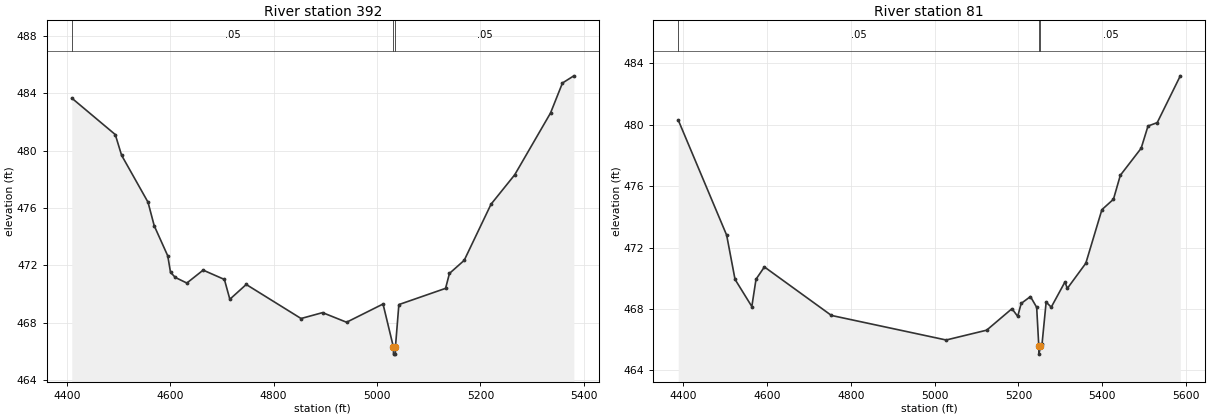
Type RM Length L Ch R = 1,392,311,311,311
BEGIN DESCRIPTION:
Mapping XS 79df1d5c
END DESCRIPTION:
XS GIS Cut Line= 4
      2757280.46      6848250.76      2757115.27      6847758.37
      2757042.63      6847738.99      2756700.28      6847894.83
#Sta/Elev= 30
  4409.8  483.65  4493.9  481.11  4506.1  479.67  4557.2  476.40  4569.2  474.76
  4595.4  472.66  4600.7  471.52  4610.0  471.16  4632.3  470.77  4663.8  471.67
  4704.9  471.02  4715.4  469.64  4747.1  470.67  4853.1  468.30  4894.7  468.71
  4941.1  468.04  5011.6  469.31  5031.6  466.32  5031.9  465.82  5035.4  465.82
  5035.6  466.32  5042.2  469.27  5132.5  470.40  5140.0  471.44  5168.5  472.35
  5220.4  476.26  5266.2  478.31  5335.4  482.61  5358.5  484.70  5380.5  485.20
#Mann=3,-1,0
  4409.8    0.05       0  5031.6    0.05       0  5035.6    0.05       0
Bank Sta=5031.6,5035.6
Exp/Cntr=0.3,0.1

Type RM Length L Ch R = 1,81,0,0,0
BEGIN DESCRIPTION:
Twin Creek203974.359
END DESCRIPTION:
XS GIS Cut Line= 4
      2757269.79      6848146.58      2757252.98      6847534.52
      2757142.93      6847550.38      2756722.57      6847771.80
#Sta/Elev= 30
  4387.7  480.31  4503.3  472.81  4523.3  469.93  4563.4  468.16  4573.4  469.94
  4593.4  470.74  4753.4  467.58  5027.3  465.98  5124.0  466.62  5184.4  468.02
  5198.1  467.52  5206.4  468.36  5228.5  468.81  5243.4  468.11  5248.5  465.56
  5248.7  465.06  5252.5  465.56  5256.1  465.69  5266.0  468.45  5278.2  468.12
  5310.9  469.76  5316.6  469.34  5360.7  470.98  5399.1  474.47  5426.7  475.15
  5443.1  476.71  5492.8  478.47  5509.2  479.92  5531.2  480.14  5586.3  483.19
#Mann=3,-1,0
  4387.7    0.05       0  5248.5    0.05       0  5252.5    0.05       0
Bank Sta=5248.5,5252.5
Exp/Cntr=0.3,0.1

Chan Stop Cuts=-1