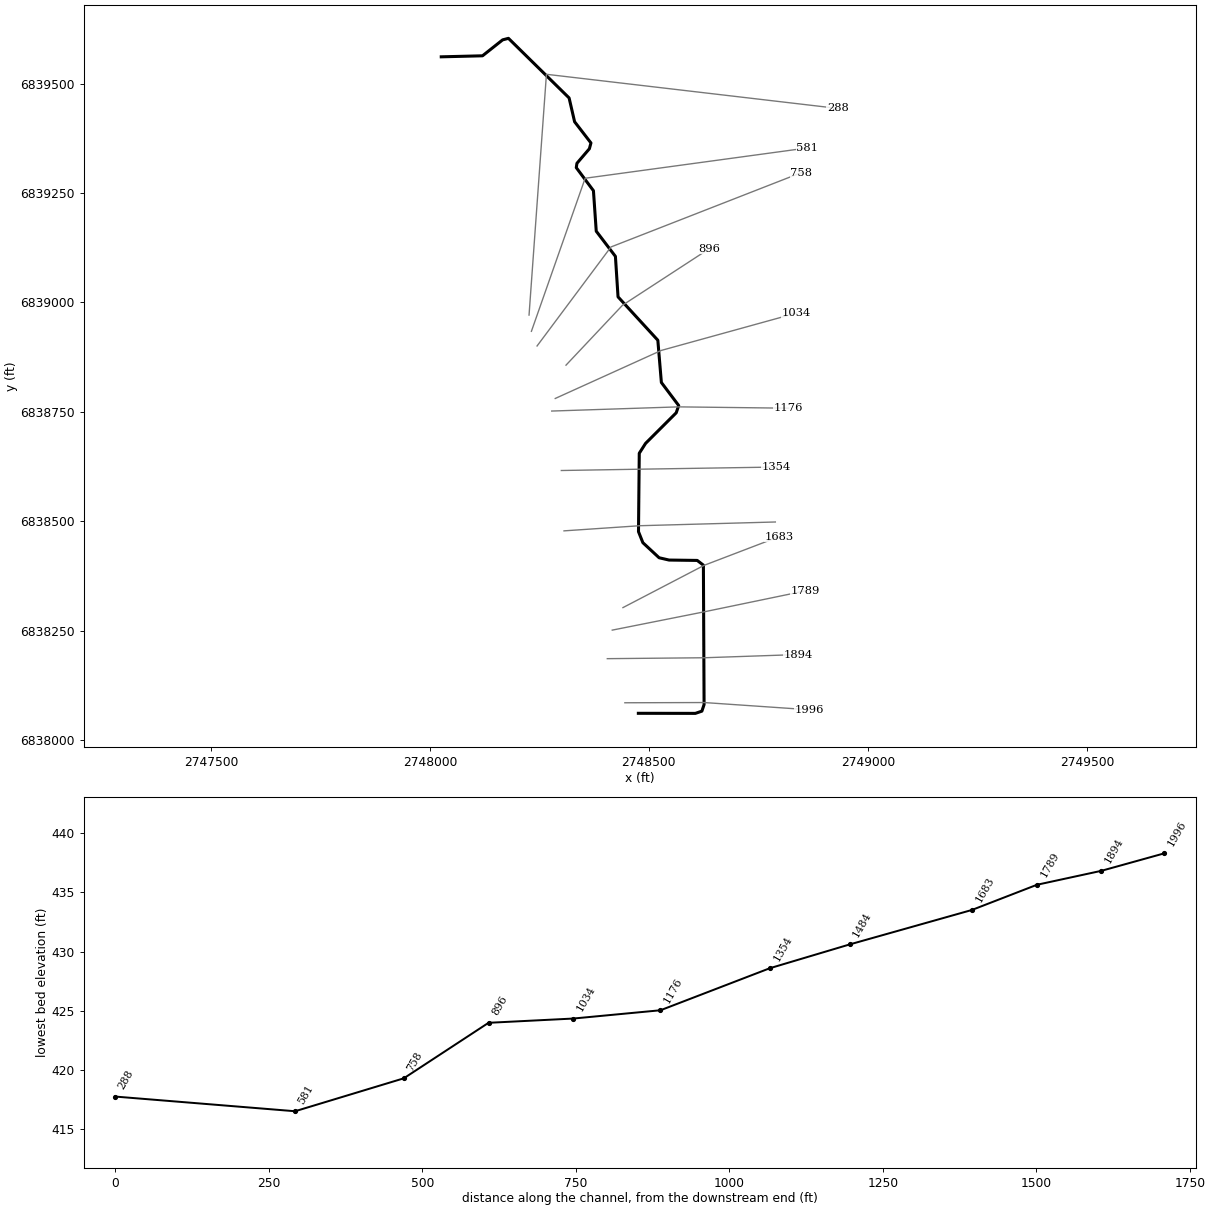
--- Twin Creek205.prj (project) ---

Proj Title=Twin Creek205 Base Level Engineering
Current Plan=p01
Default Exp/Contr=0.3,0.1
English Units
Geom File=g01
Flow File=f01
Plan File=p01
BEGIN DESCRIPTION:
Twin Creek205
END DESCRIPTION:

--- Twin Creek205.p01 (plan) ---

Plan Title=Multiple Run
Short Identifier=Multiple
Geom File=g01
Flow File=f01
Subcritical Flow
K Sum by GR= 0
Std Step Tol= 0.01
Critical Tol= 0.01
Num of Std Step Trials= 20
Max Error Tol= 0.3
Flow Tol Ratio= 0.001
Split Flow NTrial= 30
Split Flow Tol= 0.02
Split Flow Ratio= 0.02
Log Output Level= 0
Friction Slope Method= 1
Unsteady Friction Slope Method= 2
Unsteady Bridges Friction Slope Method= 1
Parabolic Critical Depth
Global Vel Dist=  1 , 1 , 1
Global Log Level= 0
CheckData=True
Encroach Param= -1, 0, 0, 0
BEGIN DESCRIPTION:
Multiple Run
END DESCRIPTION:

--- Twin Creek205.f01 (steady flow) ---

Flow Title=Multiple
Number of Profiles=7
Profile Names=10-year,25-year,50-year,1pct_min,100-year,1pct_plu,500-year
River Rch & RM= Twin Creek205,Reach-1,1996
     226     289     338     198     394     787     536
Boundary for River Rch & Prof#=Twin Creek205,Reach-1,1
Up Type=0
Dn Type=3
Dn Slope=0.005
Boundary for River Rch & Prof#=Twin Creek205,Reach-1,2
Up Type=0
Dn Type=3
Dn Slope=0.005
Boundary for River Rch & Prof#=Twin Creek205,Reach-1,3
Up Type=0
Dn Type=3
Dn Slope=0.005
Boundary for River Rch & Prof#=Twin Creek205,Reach-1,4
Up Type=0
Dn Type=3
Dn Slope=0.005
Boundary for River Rch & Prof#=Twin Creek205,Reach-1,5
Up Type=0
Dn Type=3
Dn Slope=0.005
Boundary for River Rch & Prof#=Twin Creek205,Reach-1,6
Up Type=0
Dn Type=3
Dn Slope=0.005
Boundary for River Rch & Prof#=Twin Creek205,Reach-1,7
Up Type=0
Dn Type=3
Dn Slope=0.005

--- Twin Creek205.g01 (geometry) ---

Geom Title=Existing Conditions

River Reach=Twin Creek205,Reach-1
Reach XY= 30
      2748476.00      6838061.00      2748606.17      6838060.83
      2748621.06      6838065.94      2748626.07      6838080.93
      2748624.50      6838399.47      2748610.40      6838410.31
      2748546.12      6838411.16      2748523.35      6838416.43
      2748486.33      6838450.83      2748476.32      6838476.02
      2748478.07      6838655.15      2748492.50      6838677.76
      2748562.44      6838747.63      2748568.12      6838764.22
      2748528.56      6838816.89      2748520.47      6838913.42
      2748429.62      6839012.50      2748423.64      6839105.02
      2748379.85      6839162.60      2748373.46      6839255.11
      2748334.28      6839307.78      2748335.77      6839317.73
      2748364.19      6839350.96      2748367.76      6839364.23
      2748330.44      6839412.65      2748317.88      6839467.05
      2748179.42      6839603.25      2748166.15      6839599.76
      2748120.23      6839563.35      2748026.00      6839561.00

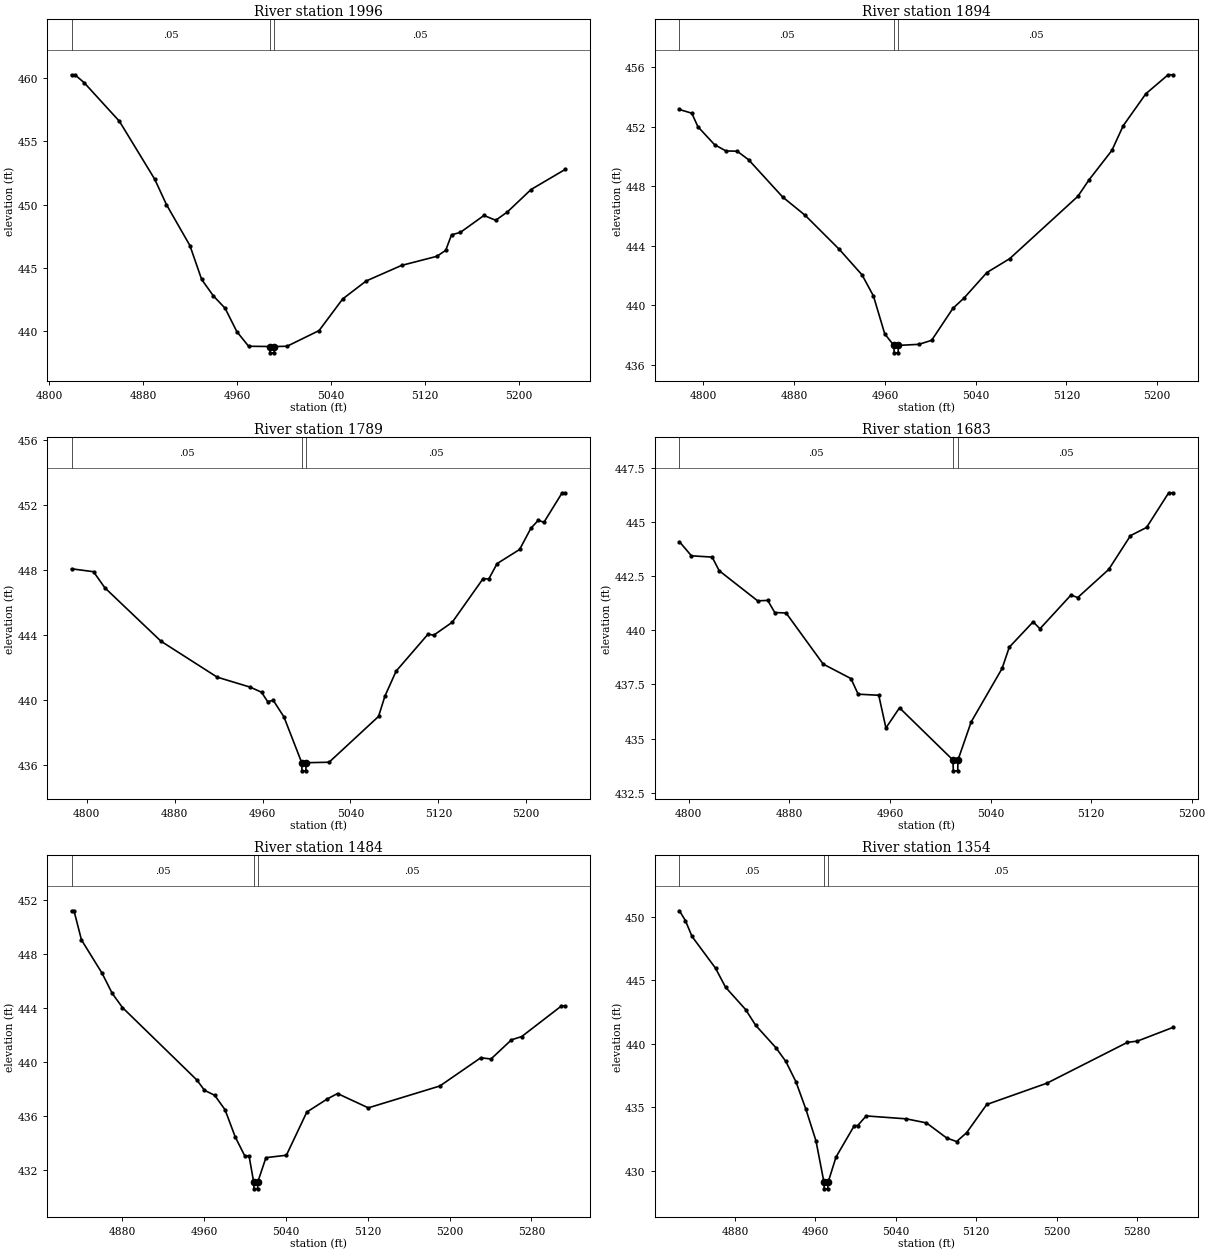
Type RM Length L Ch R = 1,1996,102,102,102
BEGIN DESCRIPTION:
Twin Creek2051996.159
END DESCRIPTION:
XS GIS Cut Line= 3
      2748445.22      6838085.07      2748626.42      6838085.58
      2748865.26      6838069.20
#Sta/Elev= 30
  4818.8  460.27  4821.7  460.27  4829.6  459.64  4859.6  456.59  4889.6  452.02
  4899.6  450.01  4919.6  446.77  4929.6  444.09  4939.6  442.79  4949.6  441.81
  4959.6  439.96  4969.6  438.81  4987.6  438.79  4987.8  438.29  4991.3  438.29
  4991.6  438.79  5002.3  438.81  5029.6  440.05  5049.7  442.55  5069.7  443.97
  5099.8  445.20  5129.9  445.92  5137.4  446.39  5142.4  447.62  5149.9  447.81
  5170.0  449.15  5180.0  448.77  5190.0  449.43  5210.1  451.20  5239.4  452.80
#Mann=3,-1,0
  4818.8    0.05       0  4987.6    0.05       0  4991.6    0.05       0
Bank Sta=4987.6,4991.6
Exp/Cntr=0.3,0.1

Type RM Length L Ch R = 1,1894,105,105,105
BEGIN DESCRIPTION:
Twin Creek2051893.8
END DESCRIPTION:
XS GIS Cut Line= 3
      2748405.09      6838185.84      2748627.29      6838187.94
      2748840.16      6838195.23
#Sta/Elev= 30
  4779.0  453.15  4789.9  452.90  4795.2  452.00  4809.9  450.79  4819.9  450.37
  4829.9  450.35  4839.9  449.78  4869.9  447.28  4889.9  446.04  4919.9  443.76
  4939.9  442.05  4949.9  440.64  4959.9  438.09  4967.9  437.32  4968.2  436.82
  4971.7  436.82  4971.9  437.32  4989.9  437.39  5001.2  437.66  5019.9  439.80
  5029.9  440.51  5049.9  442.21  5070.0  443.14  5130.0  447.32  5140.0  448.44
  5160.0  450.40  5170.0  452.06  5190.0  454.21  5209.6  455.48  5214.2  455.48
#Mann=3,-1,0
  4779.0    0.05       0  4967.9    0.05       0  4971.9    0.05       0
Bank Sta=4967.9,4971.9
Exp/Cntr=0.3,0.1

Type RM Length L Ch R = 1,1789,106,106,106
BEGIN DESCRIPTION:
Twin Creek2051788.91
END DESCRIPTION:
XS GIS Cut Line= 3
      2748416.40      6838251.06      2748626.60      6838292.92
      2748856.88      6838340.68
#Sta/Elev= 30
  4786.2  448.08  4806.2  447.90  4816.5  446.91  4867.6  443.62  4918.7  441.41
  4948.9  440.79  4959.1  440.48  4964.7  439.90  4969.8  439.98  4979.5  438.96
  4995.7  436.14  4995.9  435.64  4999.4  435.64  4999.7  436.14  5020.6  436.17
  5065.6  438.99  5071.4  440.24  5081.6  441.78  5110.7  444.06  5115.8  443.99
  5132.7  444.79  5160.8  447.48  5165.9  447.45  5173.5  448.40  5194.0  449.27
  5204.2  450.57  5211.0  451.07  5216.1  450.94  5232.7  452.76  5235.7  452.76
#Mann=3,-1,0
  4786.2    0.05       0  4995.7    0.05       0  4999.7    0.05       0
Bank Sta=4995.7,4999.7
Exp/Cntr=0.3,0.1

Type RM Length L Ch R = 1,1683,199,199,199
BEGIN DESCRIPTION:
Twin Creek2051683.2
END DESCRIPTION:
XS GIS Cut Line= 3
      2748440.84      6838302.50      2748625.88      6838398.97
      2748797.83      6838464.80
#Sta/Elev= 30
  4792.6  444.09  4802.1  443.44  4818.6  443.38  4824.2  442.75  4854.8  441.36
  4862.8  441.38  4868.4  440.82  4877.4  440.80  4906.9  438.44  4929.0  437.77
  4934.7  437.05  4951.1  437.00  4956.8  435.49  4967.6  436.42  5010.1  434.01
  5010.4  433.51  5013.9  433.51  5014.1  434.01  5024.6  435.77  5049.2  438.24
  5054.9  439.22  5073.9  440.39  5079.3  440.07  5104.0  441.63  5109.3  441.51
  5134.0  442.81  5151.3  444.37  5164.1  444.75  5181.7  446.35  5185.4  446.35
#Mann=3,-1,0
  4792.6    0.05       0  5010.1    0.05       0  5014.1    0.05       0
Bank Sta=5010.1,5014.1
Exp/Cntr=0.3,0.1

Type RM Length L Ch R = 1,1484,130,130,130
BEGIN DESCRIPTION:
Twin Creek2051483.51
END DESCRIPTION:
XS GIS Cut Line= 3
      2748306.29      6838477.87      2748479.53      6838489.62
      2748788.77      6838498.14
#Sta/Elev= 30
  4830.3  451.20  4832.7  451.20  4840.0  449.04  4860.1  446.58  4870.1  445.08
  4880.1  444.03  4952.9  438.66  4960.3  437.90  4970.3  437.53  4980.4  436.46
  4990.4  434.44  4999.7  433.04  5003.9  433.04  5008.4  431.10  5008.7  430.60
  5012.2  430.60  5012.4  431.10  5020.4  432.91  5040.4  433.09  5060.4  436.29
  5080.4  437.26  5090.4  437.66  5120.5  436.60  5190.5  438.22  5230.5  440.31
  5240.5  440.22  5260.5  441.64  5270.5  441.88  5309.4  444.15  5313.3  444.15
#Mann=3,-1,0
  4830.3    0.05       0  5008.4    0.05       0  5012.4    0.05       0
Bank Sta=5008.4,5012.4
Exp/Cntr=0.3,0.1

Type RM Length L Ch R = 1,1354,178,178,178
BEGIN DESCRIPTION:
Twin Creek2051354.16
END DESCRIPTION:
XS GIS Cut Line= 3
      2748300.14      6838615.77      2748477.50      6838618.73
      2748791.78      6838623.71
#Sta/Elev= 30
  4824.6  450.48  4830.5  449.71  4837.1  448.46  4860.5  445.96  4870.5  444.46
  4890.5  442.70  4900.5  441.46  4920.5  439.71  4930.5  438.62  4940.5  437.03
  4950.5  434.85  4960.5  432.37  4968.5  429.09  4968.7  428.59  4972.2  428.59
  4972.5  429.09  4980.5  431.10  4998.7  433.57  5002.0  433.57  5010.5  434.33
  5050.5  434.10  5070.5  433.78  5090.5  432.60  5100.5  432.31  5110.5  433.01
  5130.5  435.23  5190.5  436.91  5270.5  440.12  5280.5  440.22  5316.3  441.31
#Mann=3,-1,0
  4824.6    0.05       0  4968.5    0.05       0  4972.5    0.05       0
Bank Sta=4968.5,4972.5
Exp/Cntr=0.3,0.1

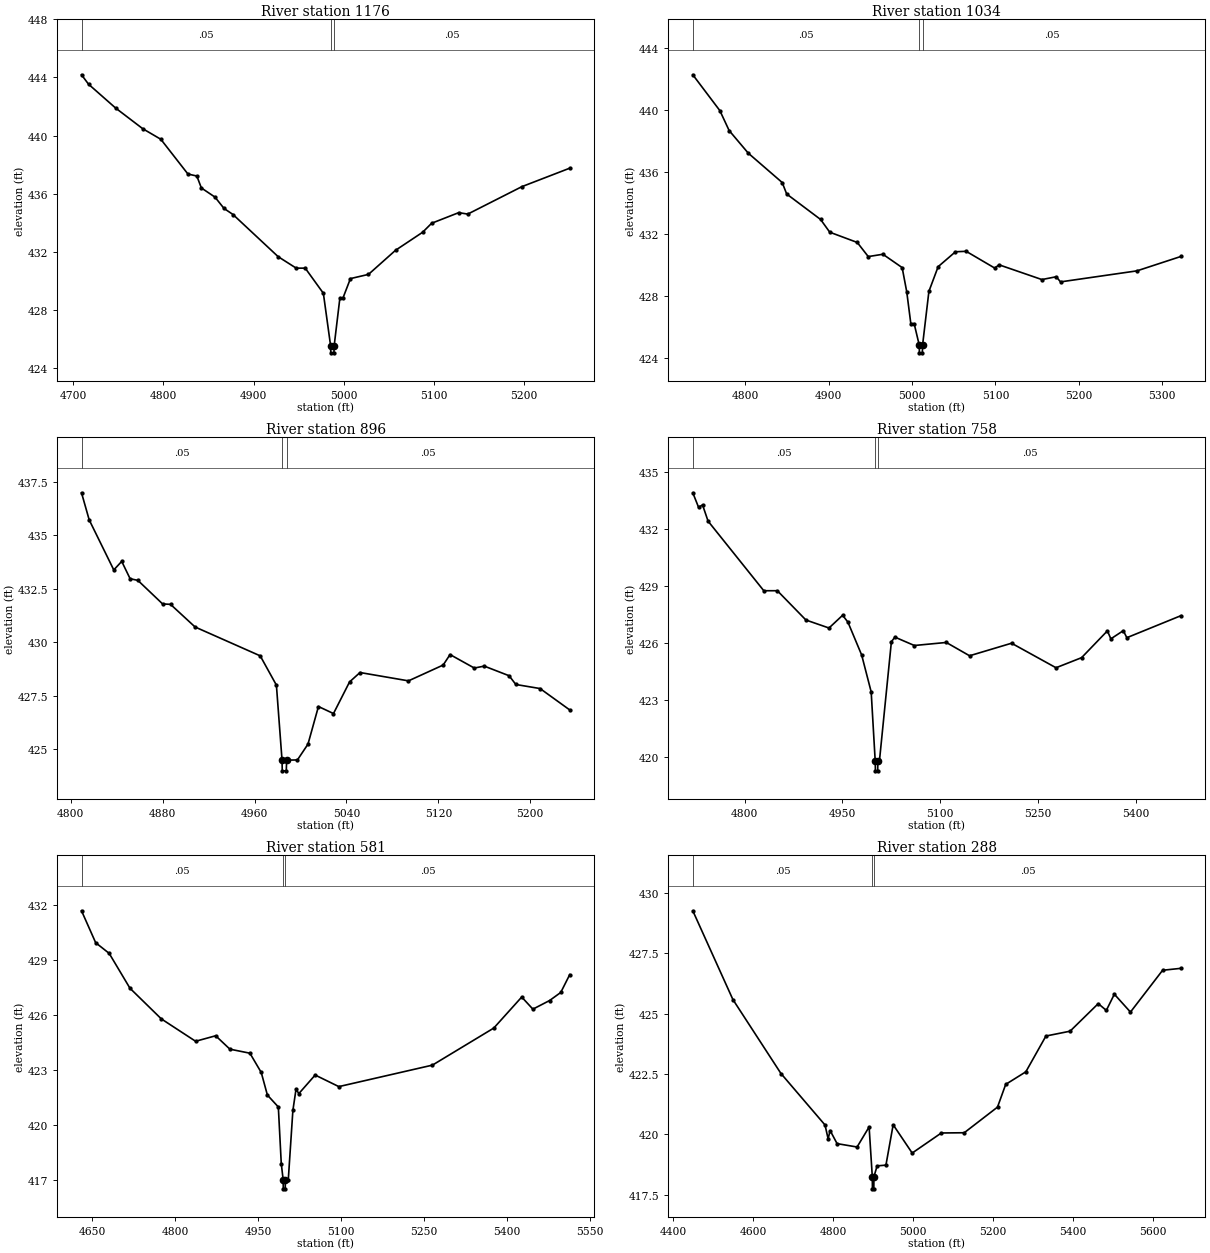
Type RM Length L Ch R = 1,1176,142,142,142
BEGIN DESCRIPTION:
Twin Creek2051176.36
END DESCRIPTION:
XS GIS Cut Line= 3
      2748278.19      6838751.62      2748567.74      6838761.18
      2748819.01      6838758.14
#Sta/Elev= 30
  4709.4  444.18  4717.2  443.53  4747.2  441.89  4777.2  440.47  4797.3  439.74
  4827.3  437.35  4837.2  437.21  4842.2  436.39  4857.3  435.76  4867.3  434.98
  4877.3  434.56  4927.3  431.66  4947.3  430.87  4957.3  430.87  4977.4  429.14
  4985.4  425.54  4985.6  425.04  4989.1  425.04  4989.4  425.54  4995.7  428.81
  4999.1  428.81  5007.4  430.15  5027.4  430.44  5057.4  432.10  5087.4  433.34
  5097.4  433.96  5127.4  434.69  5137.4  434.59  5197.4  436.48  5250.4  437.75
#Mann=3,-1,0
  4709.4    0.05       0  4985.4    0.05       0  4989.4    0.05       0
Bank Sta=4985.4,4989.4
Exp/Cntr=0.3,0.1

Type RM Length L Ch R = 1,1034,138,138,138
BEGIN DESCRIPTION:
Twin Creek2051034.4
END DESCRIPTION:
XS GIS Cut Line= 3
      2748286.26      6838780.37      2748528.27      6838890.12
      2748836.95      6838975.48
#Sta/Elev= 30
  4736.8  442.25  4769.3  439.94  4780.4  438.66  4803.4  437.20  4844.1  435.31
  4849.5  434.57  4890.2  432.93  4901.2  432.11  4934.2  431.45  4947.4  430.54
  4965.0  430.69  4988.1  429.83  4993.6  428.27  4998.5  426.22  5002.5  426.22
  5008.6  424.84  5008.8  424.34  5012.3  424.34  5012.6  424.84  5020.2  428.30
  5031.3  429.89  5052.1  430.85  5064.9  430.88  5099.2  429.80  5104.4  430.01
  5155.8  429.06  5173.0  429.24  5178.2  428.91  5269.9  429.62  5322.8  430.55
#Mann=3,-1,0
  4736.8    0.05       0  5008.6    0.05       0  5012.6    0.05       0
Bank Sta=5008.6,5012.6
Exp/Cntr=0.3,0.1

Type RM Length L Ch R = 1,896,138,138,138
BEGIN DESCRIPTION:
Twin Creek205895.96
END DESCRIPTION:
XS GIS Cut Line= 3
      2748310.84      6838856.49      2748439.77      6838993.37
      2748638.34      6839122.86
#Sta/Elev= 30
  4809.3  436.99  4816.0  435.72  4837.4  433.38  4844.3  433.78  4851.6  432.97
  4858.4  432.89  4879.9  431.79  4886.8  431.77  4908.2  430.71  4964.9  429.36
  4979.0  427.99  4983.9  424.48  4984.1  423.98  4987.6  423.98  4987.9  424.48
  4997.3  424.49  5006.5  425.23  5015.6  426.99  5028.7  426.66  5042.7  428.14
  5051.8  428.58  5094.0  428.19  5124.2  428.93  5130.2  429.42  5151.3  428.79
  5160.0  428.88  5181.6  428.43  5187.5  428.02  5208.6  427.83  5234.4  426.83
#Mann=3,-1,0
  4809.3    0.05       0  4983.9    0.05       0  4987.9    0.05       0
Bank Sta=4983.9,4987.9
Exp/Cntr=0.3,0.1

Type RM Length L Ch R = 1,758,177,177,177
BEGIN DESCRIPTION:
Twin Creek205758.24
END DESCRIPTION:
XS GIS Cut Line= 3
      2748244.74      6838900.32      2748413.42      6839126.51
      2748848.03      6839296.39
#Sta/Elev= 30
  4720.4  433.91  4729.2  433.15  4735.4  433.27  4743.8  432.42  4829.3  428.76
  4850.1  428.76  4893.9  427.22  4929.3  426.80  4950.2  427.47  4958.3  427.11
  4979.4  425.38  4994.0  423.44  5000.2  419.79  5000.5  419.29  5004.0  419.29
  5004.2  419.79  5006.6  419.79  5025.0  426.08  5030.4  426.32  5060.2  425.88
  5109.2  426.04  5144.9  425.34  5209.3  426.00  5277.5  424.71  5316.7  425.24
  5356.3  426.65  5361.6  426.23  5380.7  426.66  5386.1  426.29  5469.2  427.45
#Mann=3,-1,0
  4720.4    0.05       0  5000.2    0.05       0  5004.2    0.05       0
Bank Sta=5000.2,5004.2
Exp/Cntr=0.3,0.1

Type RM Length L Ch R = 1,581,293,293,293
BEGIN DESCRIPTION:
Twin Creek205581.21
END DESCRIPTION:
XS GIS Cut Line= 3
      2748231.85      6838933.84      2748354.55      6839283.56
      2748862.03      6839352.81
#Sta/Elev= 30
  4630.5  431.66  4656.1  429.92  4680.5  429.34  4718.1  427.44  4774.8  425.77
  4836.8  424.55  4873.1  424.85  4898.8  424.12  4935.0  423.90  4955.5  422.85
  4966.6  421.62  4986.4  420.97  4991.7  417.89  4995.1  417.01  4995.4  416.51
  4998.9  416.51  4999.1  417.01  5004.4  417.01  5012.7  420.78  5018.4  421.94
  5023.5  421.70  5053.0  422.71  5095.8  422.08  5265.0  423.25  5376.0  425.27
  5426.5  426.96  5446.7  426.30  5476.9  426.77  5497.1  427.21  5513.3  428.18
#Mann=3,-1,0
  4630.5    0.05       0  4995.1    0.05       0  4999.1    0.05       0
Bank Sta=4995.1,4999.1
Exp/Cntr=0.3,0.1

Type RM Length L Ch R = 1,288,0,0,0
BEGIN DESCRIPTION:
Twin Creek205287.6
END DESCRIPTION:
XS GIS Cut Line= 3
      2748226.43      6838970.93      2748266.13      6839521.10
      2748931.67      6839443.07
#Sta/Elev= 30
  4448.4  429.25  4548.7  425.58  4669.0  422.52  4779.3  420.39  4787.0  419.82
  4792.1  420.16  4809.4  419.62  4859.5  419.48  4889.6  420.31  4897.6  418.25
  4897.9  417.75  4901.4  417.75  4901.6  418.25  4909.7  418.70  4931.7  418.73
  4949.8  420.40  4997.4  419.23  5070.3  420.06  5127.7  420.07  5210.9  421.13
  5231.4  422.07  5281.8  422.59  5332.1  424.07  5392.5  424.27  5463.0  425.41
  5483.2  425.13  5503.3  425.80  5543.6  425.06  5624.1  426.79  5670.1  426.87
#Mann=3,-1,0
  4448.4    0.05       0  4897.6    0.05       0  4901.6    0.05       0
Bank Sta=4897.6,4901.6
Exp/Cntr=0.3,0.1

Chan Stop Cuts=-1