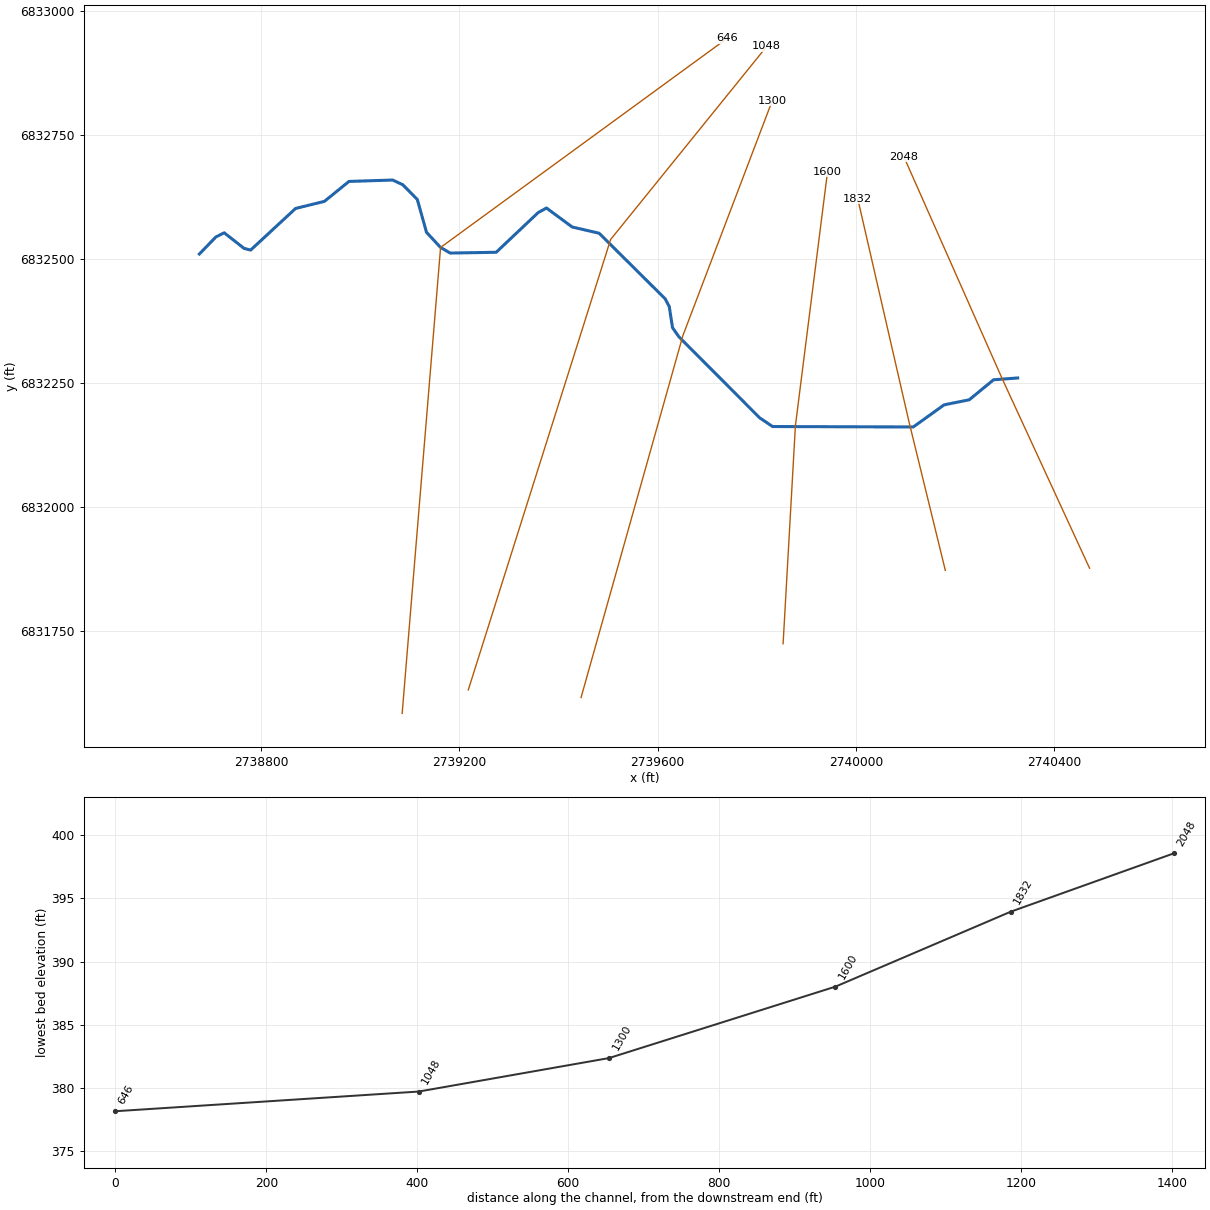
--- Twin Creek208.prj (project) ---

Proj Title=Twin Creek208 Base Level Engineering
Current Plan=p01
Default Exp/Contr=0.3,0.1
English Units
Geom File=g01
Flow File=f01
Plan File=p01
BEGIN DESCRIPTION:
Twin Creek208
END DESCRIPTION:

--- Twin Creek208.p01 (plan) ---

Plan Title=Multiple Run
Short Identifier=Multiple
Geom File=g01
Flow File=f01
Subcritical Flow
K Sum by GR= 0
Std Step Tol= 0.01
Critical Tol= 0.01
Num of Std Step Trials= 20
Max Error Tol= 0.3
Flow Tol Ratio= 0.001
Split Flow NTrial= 30
Split Flow Tol= 0.02
Split Flow Ratio= 0.02
Log Output Level= 0
Friction Slope Method= 1
Unsteady Friction Slope Method= 2
Unsteady Bridges Friction Slope Method= 1
Parabolic Critical Depth
Global Vel Dist=  1 , 1 , 1
Global Log Level= 0
CheckData=True
Encroach Param= -1, 0, 0, 0
BEGIN DESCRIPTION:
Multiple Run
END DESCRIPTION:

--- Twin Creek208.f01 (steady flow) ---

Flow Title=Multiple
Number of Profiles=7
Profile Names=10-year,25-year,50-year,1pct_min,100-year,1pct_plu,500-year
River Rch & RM= Twin Creek208,Reach-1,2048
     221     278     321     186     370     739     489
Boundary for River Rch & Prof#=Twin Creek208,Reach-1,1
Up Type=0
Dn Type=3
Dn Slope=0.005
Boundary for River Rch & Prof#=Twin Creek208,Reach-1,2
Up Type=0
Dn Type=3
Dn Slope=0.005
Boundary for River Rch & Prof#=Twin Creek208,Reach-1,3
Up Type=0
Dn Type=3
Dn Slope=0.005
Boundary for River Rch & Prof#=Twin Creek208,Reach-1,4
Up Type=0
Dn Type=3
Dn Slope=0.005
Boundary for River Rch & Prof#=Twin Creek208,Reach-1,5
Up Type=0
Dn Type=3
Dn Slope=0.005
Boundary for River Rch & Prof#=Twin Creek208,Reach-1,6
Up Type=0
Dn Type=3
Dn Slope=0.005
Boundary for River Rch & Prof#=Twin Creek208,Reach-1,7
Up Type=0
Dn Type=3
Dn Slope=0.005

--- Twin Creek208.g01 (geometry) ---

Geom Title=Existing Conditions

River Reach=Twin Creek208,Reach-1
Reach XY= 30
      2740326.00      6832261.00      2740277.49      6832257.40
      2740228.25      6832216.95      2740177.73      6832206.83
      2740115.50      6832162.20      2739831.85      6832163.06
      2739805.84      6832180.60      2739642.65      6832344.33
      2739629.98      6832362.65      2739623.47      6832404.95
      2739615.22      6832420.68      2739482.05      6832552.88
      2739427.65      6832565.47      2739375.92      6832603.70
      2739359.31      6832594.68      2739274.50      6832514.48
      2739181.71      6832512.89      2739162.35      6832524.19
      2739134.03      6832554.64      2739115.37      6832621.04
      2739086.10      6832650.70      2739065.67      6832660.13
      2738977.59      6832657.33      2738928.17      6832617.14
      2738869.94      6832602.82      2738779.33      6832518.87
      2738766.00      6832522.42      2738726.00      6832553.76
      2738709.22      6832545.31      2738676.00      6832511.00

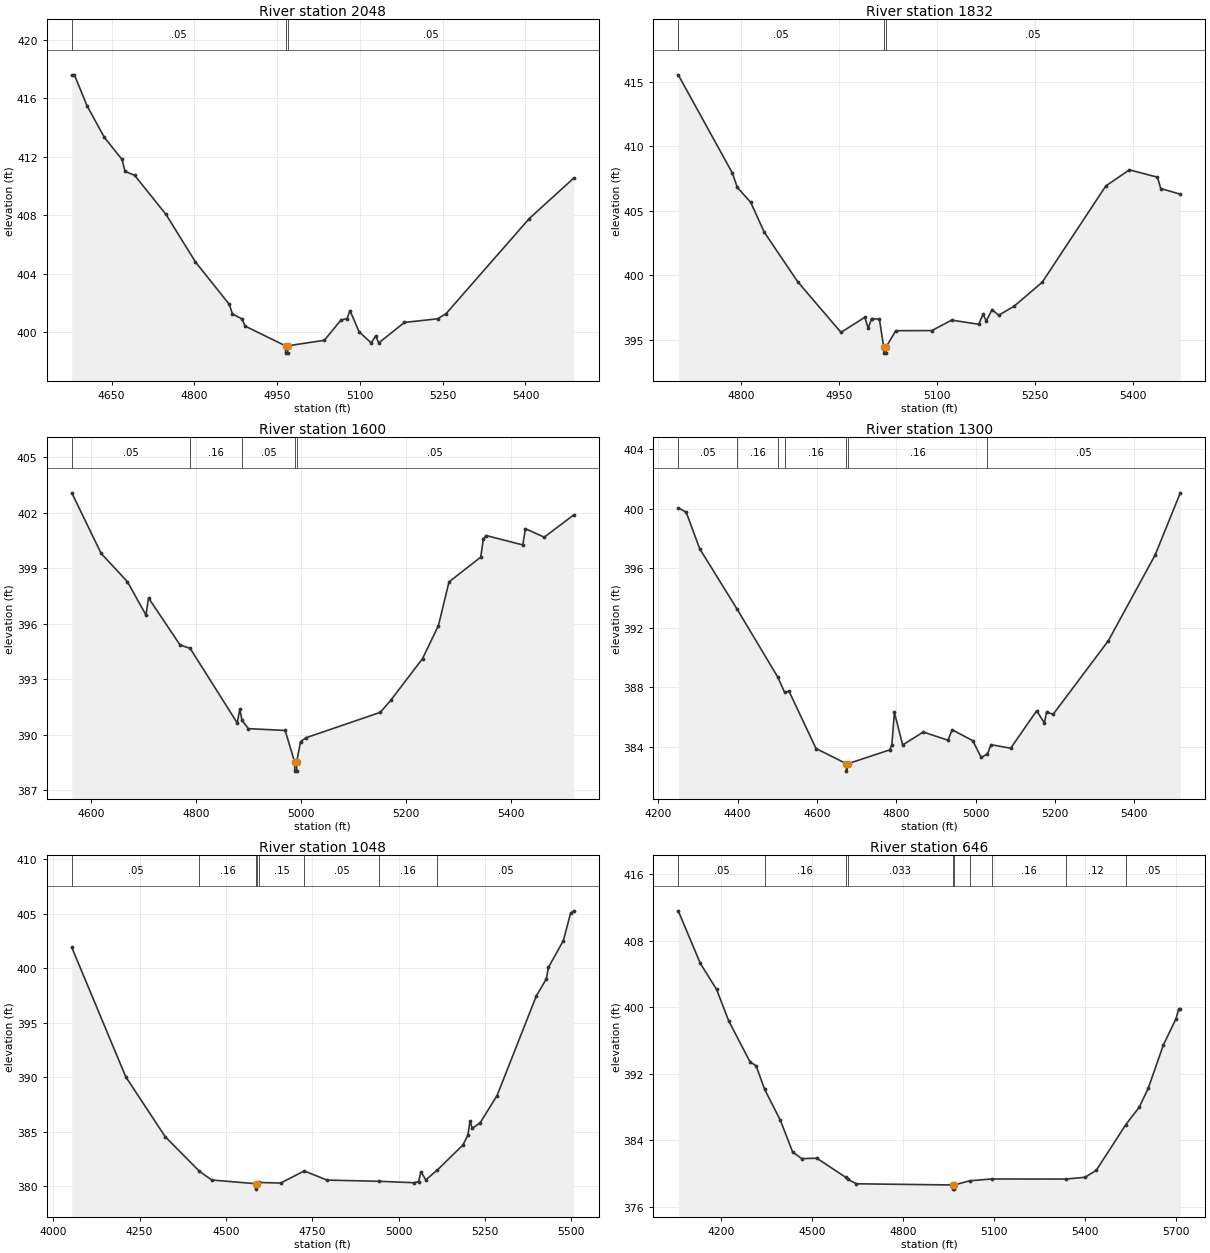
Type RM Length L Ch R = 1,2048,216,216,216
BEGIN DESCRIPTION:
Twin Creek2082048.362
END DESCRIPTION:
XS GIS Cut Line= 3
      2740471.01      6831877.40      2740294.19      6832260.90
      2740096.68      6832706.82
#Sta/Elev= 30
  4577.7  417.62  4582.4  417.62  4605.4  415.50  4636.7  413.34  4668.8  411.83
  4674.3  411.01  4691.7  410.74  4748.6  408.06  4801.9  404.81  4863.4  401.90
  4868.9  401.25  4886.3  400.91  4891.9  400.42  4965.1  399.07  4965.3  398.57
  4968.8  398.57  4969.1  399.07  5035.5  399.45  5065.7  400.84  5076.6  400.93
  5082.0  401.48  5098.5  400.03  5120.4  399.27  5128.6  399.74  5134.1  399.27
  5180.6  400.67  5240.7  400.92  5256.0  401.27  5406.6  407.77  5487.7  410.56
#Mann=3,-1,0
  4577.7    0.05       0  4965.1    0.05       0  4969.1    0.05       0
Bank Sta=4965.1,4969.1
Exp/Cntr=0.3,0.1

Type RM Length L Ch R = 1,1832,232,232,232
BEGIN DESCRIPTION:
Twin Creek2081831.96
END DESCRIPTION:
XS GIS Cut Line= 3
      2740180.14      6831873.09      2740106.88      6832172.68
      2740003.60      6832622.26
#Sta/Elev= 30
  4703.2  415.54  4786.2  407.92  4793.7  406.81  4814.3  405.65  4834.9  403.35
  4886.3  399.49  4952.7  395.56  4989.2  396.73  4994.4  395.88  4999.6  396.63
  5011.6  396.58  5018.1  394.45  5018.4  393.95  5021.9  393.95  5022.1  394.45
  5036.7  395.69  5092.0  395.70  5122.4  396.51  5163.8  396.19  5170.4  396.96
  5175.5  396.46  5184.3  397.32  5194.6  396.89  5218.4  397.60  5261.2  399.45
  5358.7  406.92  5394.9  408.17  5437.8  407.60  5442.9  406.72  5472.9  406.28
#Mann=3,-1,0
  4703.2    0.05       0  5018.1    0.05       0  5022.1    0.05       0
Bank Sta=5018.1,5022.1
Exp/Cntr=0.3,0.1

Type RM Length L Ch R = 1,1600,300,300,300
BEGIN DESCRIPTION:
Twin Creek2081599.89
END DESCRIPTION:
XS GIS Cut Line= 3
      2739853.03      6831725.07      2739877.84      6832164.63
      2739942.65      6832676.98
#Sta/Elev= 30
  4563.8  403.08  4619.8  399.80  4669.9  398.27  4705.1  396.47  4710.1  397.39
  4770.1  394.85  4789.5  394.66  4879.0  390.63  4884.0  391.37  4888.3  390.76
  4900.3  390.32  4970.4  390.22  4988.4  388.52  4988.7  388.02  4992.2  388.02
  4992.4  388.52  4999.7  389.62  5010.5  389.83  5151.6  391.20  5171.8  391.86
  5232.2  394.11  5262.5  395.90  5282.6  398.26  5343.0  399.60  5348.1  400.58
  5353.2  400.77  5423.2  400.26  5428.2  401.14  5464.1  400.68  5520.5  401.89
#Mann=5,-1,0
  4563.8    0.05       0  4789.5    0.16       0  4888.3    0.05       0
  4988.4    0.05       0  4992.4    0.05       0
Bank Sta=4988.4,4992.4
Exp/Cntr=0.3,0.1

Type RM Length L Ch R = 1,1300,252,252,252
BEGIN DESCRIPTION:
Twin Creek2081299.73
END DESCRIPTION:
XS GIS Cut Line= 3
      2739445.62      6831616.61      2739650.89      6832346.26
      2739831.19      6832820.26
#Sta/Elev= 30
  4250.6  400.07  4270.6  399.78  4304.7  397.32  4399.3  393.24  4501.7  388.67
  4518.6  387.66  4529.7  387.74  4597.8  383.88  4674.3  382.86  4674.5  382.36
  4678.3  382.86  4783.6  383.79  4788.8  384.13  4795.3  386.31  4816.1  384.12
  4868.1  384.99  4930.2  384.44  4940.8  385.14  4992.7  384.41  5013.9  383.28
  5029.7  383.51  5038.7  384.14  5088.2  383.90  5153.8  386.42  5173.2  385.60
  5178.6  386.32  5195.5  386.19  5334.6  391.14  5452.3  396.90  5515.7  401.08
#Mann=7,-1,0
  4250.6    0.05       0  4399.3    0.16       0  4501.7    0.05       0
  4518.6    0.16       0  4674.3    0.07       0  4678.3    0.16       0
  5029.7    0.05       0
Bank Sta=4674.3,4678.3
Exp/Cntr=0.3,0.1

Type RM Length L Ch R = 1,1048,402,402,402
BEGIN DESCRIPTION:
Twin Creek2081048.44
END DESCRIPTION:
XS GIS Cut Line= 3
      2739218.21      6831631.99      2739505.21      6832540.22
      2739819.99      6832929.60
#Sta/Elev= 30
  4053.8  401.92  4210.1  390.03  4324.4  384.52  4423.2  381.35  4458.9  380.55
  4585.6  380.21  4585.9  379.71  4589.6  380.21  4596.0  380.32  4658.1  380.27
  4726.7  381.38  4792.7  380.54  4943.6  380.43  5043.4  380.30  5057.8  380.40
  5064.2  381.31  5078.6  380.56  5111.6  381.46  5185.7  383.76  5200.1  384.65
  5206.5  385.95  5213.0  385.30  5235.3  385.78  5284.8  388.31  5398.4  397.46
  5427.1  399.01  5433.6  400.09  5476.7  402.55  5497.5  405.06  5507.0  405.28
#Mann=8,-1,0
  4053.8    0.05       0  4423.2    0.16       0  4585.6    0.07       0
  4589.6    0.16       0  4596.0    0.15       0  4726.7    0.05       0
  4943.6    0.16       0  5111.6    0.05       0
Bank Sta=4585.6,4589.6
Exp/Cntr=0.3,0.1

Type RM Length L Ch R = 1,646,0,0,0
BEGIN DESCRIPTION:
Twin Creek208646.193
END DESCRIPTION:
XS GIS Cut Line= 3
      2739084.88      6831584.68      2739162.35      6832524.19
      2739740.26      6832945.88
#Sta/Elev= 30
  4057.3  411.59  4130.3  405.27  4184.0  402.14  4224.2  398.35  4294.4  393.45
  4314.5  392.97  4342.5  390.15  4394.8  386.41  4434.9  382.63  4465.0  381.82
  4515.2  381.86  4609.9  379.58  4617.5  379.33  4645.6  378.79  4964.7  378.65
  4964.9  378.15  4968.4  378.15  4968.7  378.65  5019.7  379.15  5092.3  379.37
  5337.0  379.36  5400.7  379.57  5437.8  380.41  5535.4  385.90  5580.0  388.01
  5609.4  390.26  5659.6  395.49  5701.3  398.63  5709.7  399.75  5715.4  399.75
#Mann=10,-1,0
  4057.3    0.05       0  4342.5    0.16       0  4609.9    0.15       0
  4617.5   0.033       0  4964.7   0.033       0  4968.7   0.033       0
  5019.7    0.12       0  5092.3    0.16       0  5337.0    0.12       0
  5535.4    0.05       0
Bank Sta=4964.7,4968.7
Exp/Cntr=0.3,0.1

Chan Stop Cuts=-1