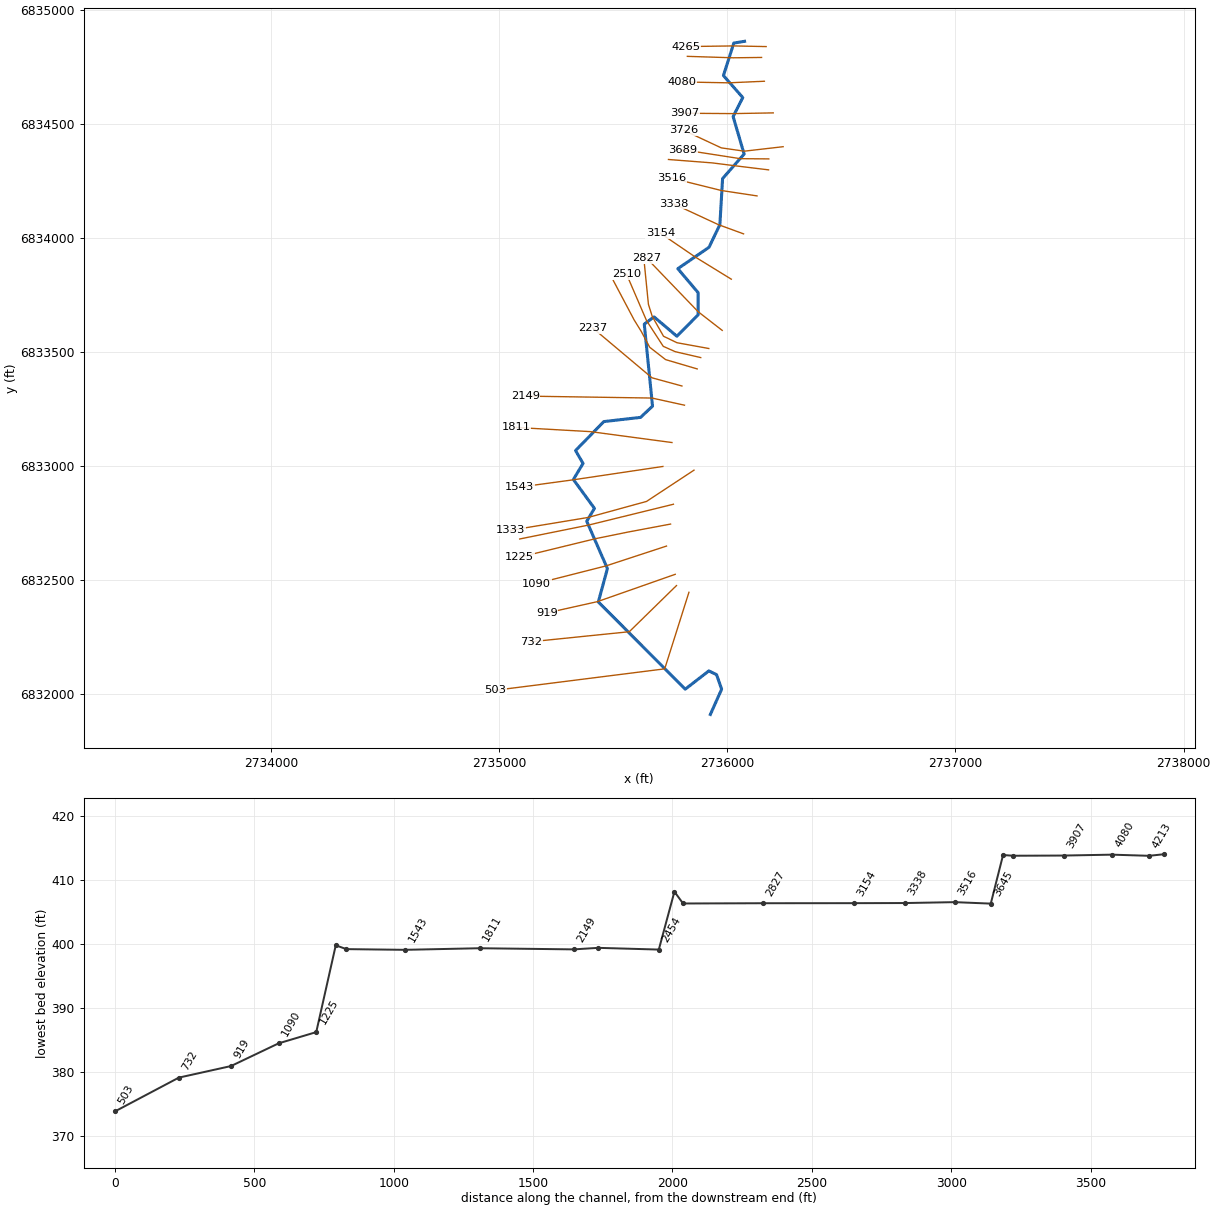
--- Twin Creek210.prj (project) ---

Proj Title=Twin Creek210 Base Level Engineering
Current Plan=p01
Default Exp/Contr=0.3,0.1
English Units
Geom File=g01
Flow File=f01
Plan File=p01
BEGIN DESCRIPTION:
Twin Creek210
END DESCRIPTION:

--- Twin Creek210.p01 (plan) ---

Plan Title=Multiple Run
Short Identifier=Multiple
Geom File=g01
Flow File=f01
Subcritical Flow
K Sum by GR= 0
Std Step Tol= 0.01
Critical Tol= 0.01
Num of Std Step Trials= 20
Max Error Tol= 0.3
Flow Tol Ratio= 0.001
Split Flow NTrial= 30
Split Flow Tol= 0.02
Split Flow Ratio= 0.02
Log Output Level= 0
Friction Slope Method= 1
Unsteady Friction Slope Method= 2
Unsteady Bridges Friction Slope Method= 1
Parabolic Critical Depth
Global Vel Dist=  1 , 1 , 1
Global Log Level= 0
CheckData=True
Encroach Param= -1, 0, 0, 0
BEGIN DESCRIPTION:
Multiple Run
END DESCRIPTION:

--- Twin Creek210.f01 (steady flow) ---

Flow Title=Multiple
Number of Profiles=7
Profile Names=10-year,25-year,50-year,1pct_min,100-year,1pct_plu,500-year
River Rch & RM= Twin Creek210,Reach-1,4265
     279     355     414     240     480     957     642
Boundary for River Rch & Prof#=Twin Creek210,Reach-1,1
Up Type=0
Dn Type=3
Dn Slope=0.005
Boundary for River Rch & Prof#=Twin Creek210,Reach-1,2
Up Type=0
Dn Type=3
Dn Slope=0.005
Boundary for River Rch & Prof#=Twin Creek210,Reach-1,3
Up Type=0
Dn Type=3
Dn Slope=0.005
Boundary for River Rch & Prof#=Twin Creek210,Reach-1,4
Up Type=0
Dn Type=3
Dn Slope=0.005
Boundary for River Rch & Prof#=Twin Creek210,Reach-1,5
Up Type=0
Dn Type=3
Dn Slope=0.005
Boundary for River Rch & Prof#=Twin Creek210,Reach-1,6
Up Type=0
Dn Type=3
Dn Slope=0.005
Boundary for River Rch & Prof#=Twin Creek210,Reach-1,7
Up Type=0
Dn Type=3
Dn Slope=0.005

--- Twin Creek210.g01 (geometry) ---

Geom Title=Existing Conditions

River Reach=Twin Creek210,Reach-1
Reach XY= 30
      2736076.00      6834861.00      2736028.83      6834853.24
      2735983.33      6834710.90      2736068.15      6834614.41
      2736025.79      6834531.21      2736074.03      6834366.89
      2735979.62      6834259.50      2735967.76      6834057.76
      2735920.29      6833958.46      2735783.49      6833864.58
      2735872.52      6833759.50      2735872.54      6833662.47
      2735779.35      6833568.60      2735679.13      6833653.47
      2735636.47      6833621.56      2735672.57      6833262.22
      2735620.35      6833212.98      2735459.23      6833194.57
      2735335.30      6833067.67      2735368.16      6833011.09
      2735325.75      6832940.84      2735417.99      6832814.33
      2735384.29      6832757.78      2735474.89      6832550.45
      2735435.13      6832404.26      2735816.00      6832021.96
      2735919.53      6832102.07      2735953.29      6832085.47
      2735975.43      6832021.79      2735926.00      6831911.00

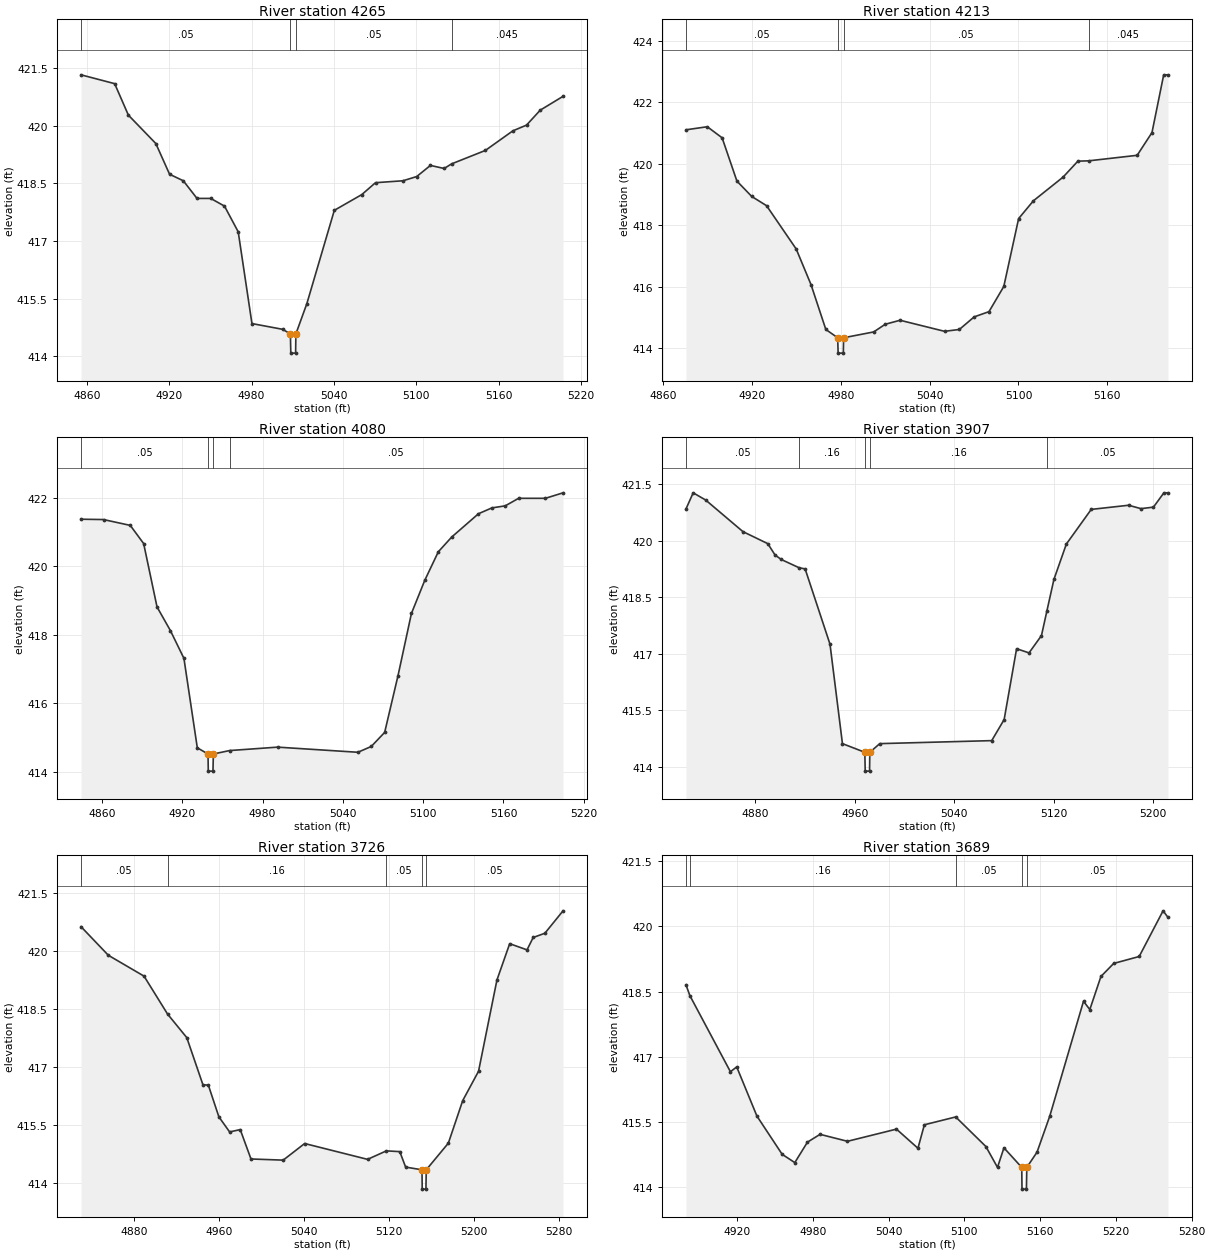
Type RM Length L Ch R = 1,4265,52,52,52
BEGIN DESCRIPTION:
Twin Creek2104264.988
END DESCRIPTION:
XS GIS Cut Line= 3
      2736170.49      6834837.86      2736026.32      6834840.80
      2735819.44      6834837.85
#Sta/Elev= 30
  4855.8  421.33  4880.3  421.10  4890.3  420.28  4910.3  419.54  4920.3  418.74
  4930.3  418.57  4940.3  418.11  4950.3  418.11  4960.3  417.91  4970.3  417.24
  4980.3  414.85  5002.7  414.70  5008.3  414.58  5008.6  414.08  5012.1  414.08
  5012.3  414.58  5020.3  415.37  5040.3  417.80  5060.3  418.21  5070.3  418.52
  5090.3  418.57  5100.3  418.68  5110.3  418.97  5120.3  418.89  5125.7  419.01
  5150.3  419.36  5170.3  419.87  5180.3  420.02  5190.3  420.41  5206.9  420.77
#Mann=4,-1,0
  4855.8    0.05       0  5008.3    0.05       0  5012.3    0.05       0
  5125.7   0.045       0
Bank Sta=5008.3,5012.3
Exp/Cntr=0.3,0.1

Type RM Length L Ch R = 1,4213,133,133,133
BEGIN DESCRIPTION:
Twin Creek2104212.92
END DESCRIPTION:
XS GIS Cut Line= 3
      2736150.44      6834790.28      2736026.44      6834788.73
      2735825.25      6834795.05
#Sta/Elev= 30
  4875.6  421.11  4890.0  421.21  4900.0  420.85  4910.0  419.44  4920.0  418.94
  4930.0  418.64  4950.0  417.23  4960.0  416.07  4970.0  414.61  4978.0  414.34
  4978.3  413.84  4981.8  413.84  4982.0  414.34  5002.3  414.53  5010.1  414.78
  5020.1  414.91  5050.1  414.55  5060.1  414.61  5070.1  415.02  5080.1  415.19
  5090.1  416.01  5100.1  418.22  5110.1  418.80  5130.1  419.57  5140.1  420.09
  5147.4  420.10  5180.1  420.28  5190.1  421.02  5198.0  422.90  5200.9  422.90
#Mann=4,-1,0
  4875.6    0.05       0  4978.0    0.05       0  4982.0    0.05       0
  5147.4   0.045       0
Bank Sta=4978,4982
Exp/Cntr=0.3,0.1

Type RM Length L Ch R = 1,4080,173,173,173
BEGIN DESCRIPTION:
Twin Creek2104080.45
END DESCRIPTION:
XS GIS Cut Line= 3
      2736162.78      6834685.97      2736006.78      6834679.03
      2735802.77      6834682.86
#Sta/Elev= 28
  4844.3  421.37  4861.1  421.36  4881.1  421.19  4891.1  420.66  4901.1  418.81
  4911.1  418.12  4921.2  417.31  4931.2  414.70  4939.2  414.52  4939.4  414.02
  4942.9  414.02  4943.2  414.52  4955.3  414.62  4991.2  414.72  5051.2  414.57
  5061.2  414.74  5071.2  415.15  5081.2  416.81  5091.2  418.62  5101.2  419.59
  5111.3  420.42  5121.3  420.85  5141.3  421.53  5151.3  421.70  5161.3  421.76
  5171.3  421.98  5191.3  421.98  5204.5  422.14
#Mann=4,-1,0
  4844.3    0.05       0  4939.2    0.05       0  4943.2    0.05       0
  4955.3    0.05       0
Bank Sta=4939.2,4943.2
Exp/Cntr=0.3,0.1

Type RM Length L Ch R = 1,3907,181,181,181
BEGIN DESCRIPTION:
Twin Creek2103906.62
END DESCRIPTION:
XS GIS Cut Line= 3
      2736201.78      6834547.27      2736025.58      6834544.18
      2735814.32      6834545.67
#Sta/Elev= 30
  4824.3  420.84  4830.1  421.27  4840.1  421.08  4870.1  420.24  4890.1  419.92
  4895.9  419.62  4900.9  419.50  4915.3  419.28  4920.1  419.25  4940.1  417.25
  4950.1  414.61  4968.1  414.38  4968.4  413.88  4971.9  413.88  4972.1  414.38
  4980.1  414.61  5070.1  414.69  5080.1  415.25  5090.1  417.13  5100.1  417.02
  5110.1  417.48  5114.5  418.14  5120.1  418.97  5130.1  419.91  5150.1  420.83
  5180.1  420.94  5190.1  420.85  5200.1  420.89  5208.5  421.27  5211.8  421.27
#Mann=5,-1,0
  4824.3    0.05       0  4915.3    0.16       0  4968.1    0.07       0
  4972.1    0.16       0  5114.5    0.05       0
Bank Sta=4968.1,4972.1
Exp/Cntr=0.3,0.1

Type RM Length L Ch R = 1,3726,37,37,37
BEGIN DESCRIPTION:
Twin Creek2103725.74
END DESCRIPTION:
XS GIS Cut Line= 4
      2736244.86      6834399.14      2736074.48      6834379.52
      2735973.85      6834394.02      2735810.52      6834470.45
#Sta/Elev= 30
  4830.1  420.64  4855.8  419.90  4889.4  419.36  4911.5  418.38  4929.6  417.77
  4944.8  416.55  4949.9  416.54  4959.8  415.72  4969.9  415.33  4979.9  415.39
  4990.0  414.63  5020.3  414.60  5040.5  415.03  5099.7  414.62  5117.4  414.84
  5130.0  414.82  5135.5  414.42  5150.9  414.35  5151.1  413.85  5154.6  413.85
  5154.9  414.35  5175.7  415.04  5189.2  416.14  5204.1  416.90  5221.4  419.26
  5233.4  420.20  5249.7  420.04  5255.5  420.36  5266.5  420.47  5283.6  421.05
#Mann=5,-1,0
  4830.1    0.05       0  4911.5    0.16       0  5117.4    0.05       0
  5150.9    0.07       0  5154.9    0.05       0
Bank Sta=5150.9,5154.9
Exp/Cntr=0.3,0.1

Type RM Length L Ch R = 1,3689,44,44,44
BEGIN DESCRIPTION:
Twin Creek2103688.78
END DESCRIPTION:
XS GIS Cut Line= 3
      2736182.16      6834345.70      2736057.63      6834346.65
      2735803.50      6834386.04
#Sta/Elev= 30
  4879.5  418.66  4882.6  418.41  4914.7  416.66  4919.7  416.77  4935.7  415.64
  4955.7  414.76  4965.7  414.57  4975.7  415.04  4985.7  415.22  5007.4  415.06
  5046.2  415.34  5063.2  414.90  5068.3  415.44  5093.1  415.62  5117.0  414.94
  5126.2  414.46  5131.3  414.91  5145.4  414.46  5145.6  413.96  5149.1  413.96
  5149.4  414.46  5157.5  414.81  5167.6  415.64  5194.3  418.28  5199.3  418.09
  5208.1  418.85  5218.2  419.15  5238.4  419.31  5257.3  420.36  5261.2  420.21
#Mann=5,-1,0
  4879.5    0.05       0  4882.6    0.16       0  5093.1    0.05       0
  5145.4    0.07       0  5149.4    0.05       0
Bank Sta=5145.4,5149.4
Exp/Cntr=0.3,0.1

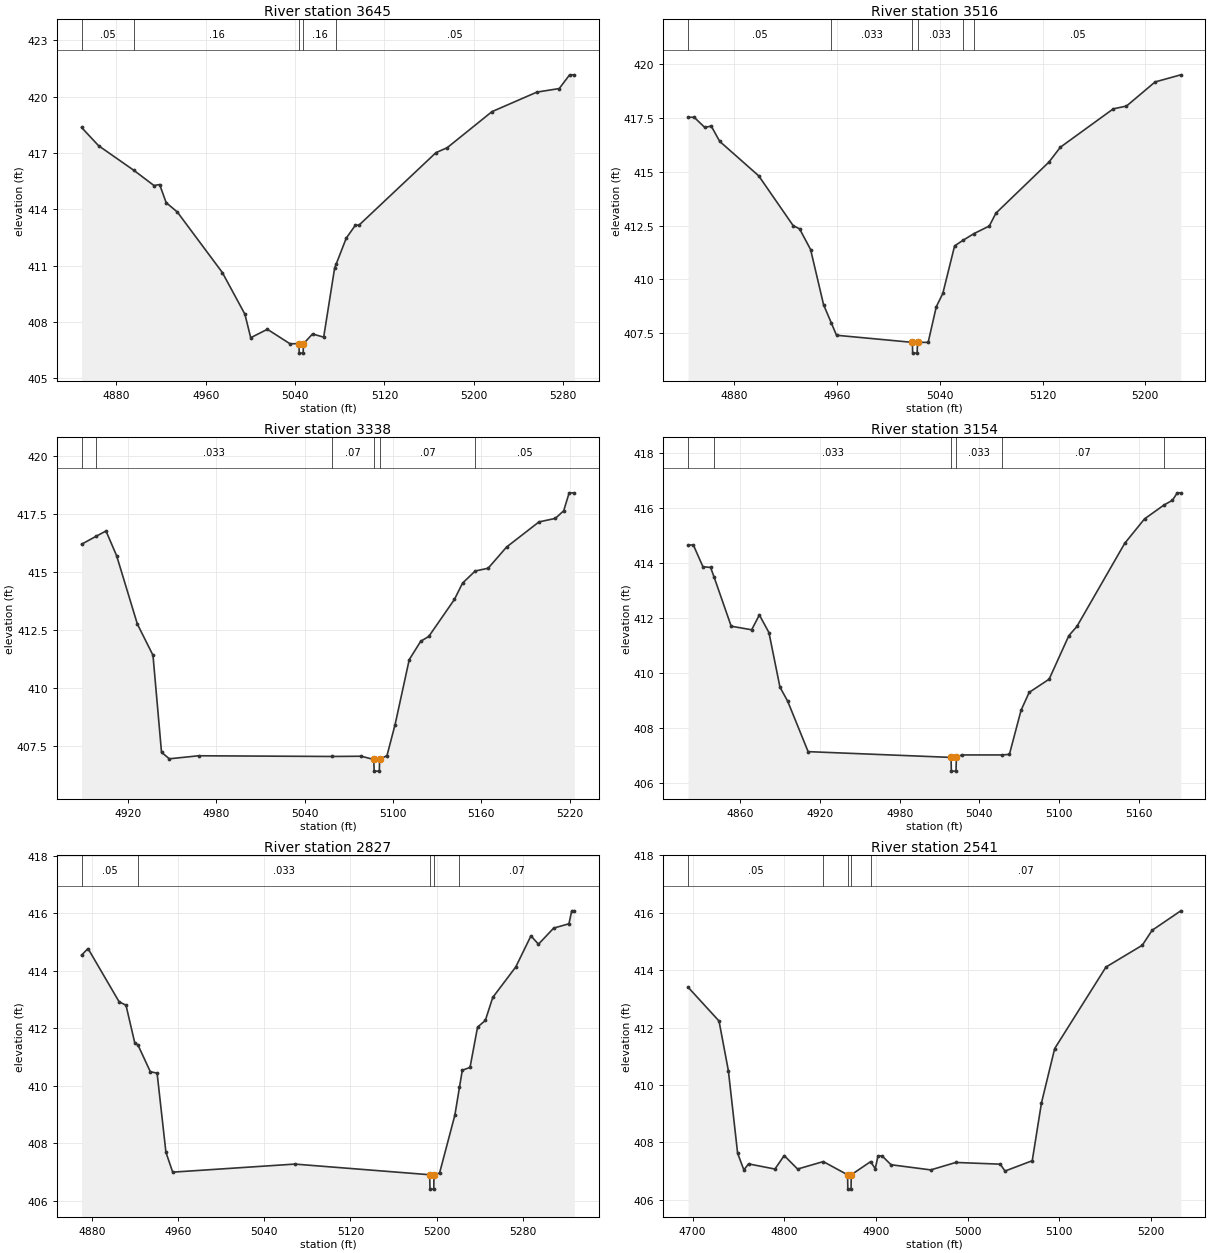
Type RM Length L Ch R = 1,3645,129,129,129
BEGIN DESCRIPTION:
Twin Creek2103645.48
END DESCRIPTION:
XS GIS Cut Line= 4
      2736181.10      6834297.62      2736029.70      6834316.11
      2735934.64      6834328.15      2735742.56      6834343.08
#Sta/Elev= 30
  4848.9  418.36  4864.1  417.39  4895.9  416.07  4913.7  415.27  4918.8  415.32
  4924.6  414.36  4934.6  413.86  4974.9  410.64  4995.1  408.42  5000.3  407.17
  5015.2  407.62  5035.4  406.85  5043.5  406.85  5043.7  406.35  5047.2  406.35
  5047.5  406.85  5055.6  407.37  5065.6  407.20  5075.4  410.88  5076.8  411.09
  5085.8  412.47  5094.0  413.16  5097.2  413.16  5166.1  417.02  5176.1  417.28
  5216.2  419.20  5256.4  420.24  5276.4  420.43  5285.7  421.16  5289.9  421.16
#Mann=5,-1,0
  4848.9    0.05       0  4895.9    0.16       0  5043.5    0.07       0
  5047.5    0.16       0  5076.8    0.05       0
Bank Sta=5043.5,5047.5
Exp/Cntr=0.3,0.1

Type RM Length L Ch R = 1,3516,178,178,178
BEGIN DESCRIPTION:
Twin Creek2103515.7
END DESCRIPTION:
XS GIS Cut Line= 3
      2736130.44      6834183.53      2735974.51      6834207.11
      2735754.99      6834261.67
#Sta/Elev= 30
  4843.8  417.53  4848.6  417.53  4856.8  417.06  4861.9  417.12  4868.5  416.41
  4898.9  414.81  4925.7  412.50  4930.7  412.35  4939.3  411.39  4949.4  408.83
  4955.3  408.00  4959.5  407.41  5018.6  407.08  5018.8  406.58  5022.3  406.58
  5022.6  407.08  5030.9  407.08  5037.2  408.73  5042.3  409.35  5051.5  411.56
  5058.1  411.82  5066.6  412.13  5078.5  412.48  5083.7  413.08  5125.0  415.45
  5133.9  416.14  5175.1  417.92  5185.4  418.05  5207.7  419.17  5227.7  419.50
#Mann=6,-1,0
  4843.8    0.05       0  4955.3   0.033       0  5018.6   0.033       0
  5022.6   0.033       0  5058.1    0.16       0  5066.6    0.05       0
Bank Sta=5018.6,5022.6
Exp/Cntr=0.3,0.1

Type RM Length L Ch R = 1,3338,184,184,184
BEGIN DESCRIPTION:
Twin Creek2103338.42
END DESCRIPTION:
XS GIS Cut Line= 3
      2736071.56      6834017.19      2735961.53      6834057.44
      2735764.26      6834148.90
#Sta/Elev= 30
  4888.5  416.19  4898.6  416.54  4905.1  416.76  4912.3  415.70  4926.4  412.76
  4937.0  411.42  4942.8  407.25  4948.1  406.97  4968.0  407.10  5058.4  407.07
  5078.5  407.08  5086.9  406.94  5087.2  406.44  5090.7  406.44  5090.9  406.94
  5095.9  407.11  5101.4  408.44  5111.0  411.23  5118.8  412.02  5124.3  412.23
  5141.7  413.82  5147.2  414.52  5155.8  415.04  5164.6  415.16  5177.1  416.07
  5199.1  417.15  5210.2  417.30  5215.9  417.63  5219.6  418.40  5223.1  418.40
#Mann=6,-1,0
  4888.5    0.05       0  4898.6   0.033       0  5058.4    0.07       0
  5086.9   0.033       0  5090.9    0.07       0  5155.8    0.05       0
Bank Sta=5086.9,5090.9
Exp/Cntr=0.3,0.1

Type RM Length L Ch R = 1,3154,327,327,327
BEGIN DESCRIPTION:
Twin Creek2103153.52
END DESCRIPTION:
XS GIS Cut Line= 3
      2736017.85      6833818.51      2735861.31      6833914.79
      2735706.73      6834020.24
#Sta/Elev= 30
  4820.7  414.66  4824.7  414.66  4831.9  413.87  4837.7  413.84  4840.4  413.48
  4853.2  411.70  4868.6  411.57  4874.4  412.11  4881.6  411.47  4889.9  409.48
  4895.7  408.97  4911.1  407.13  5018.7  406.92  5018.9  406.42  5022.4  406.42
  5022.7  406.92  5026.7  407.01  5057.0  407.01  5062.6  407.03  5071.4  408.64
  5077.5  409.29  5092.5  409.77  5107.4  411.36  5113.4  411.69  5149.4  414.72
  5164.3  415.61  5178.8  416.11  5185.3  416.29  5189.0  416.56  5191.6  416.56
#Mann=6,-1,0
  4820.7    0.05       0  4840.4   0.033       0  5018.7   0.033       0
  5022.7   0.033       0  5057.0    0.07       0  5178.8    0.05       0
Bank Sta=5018.7,5022.7
Exp/Cntr=0.3,0.1

Type RM Length L Ch R = 1,2827,286,286,286
BEGIN DESCRIPTION:
Twin Creek2102826.78
END DESCRIPTION:
XS GIS Cut Line= 3
      2735978.02      6833594.13      2735872.47      6833676.07
      2735647.63      6833909.74
#Sta/Elev= 30
  4870.1  414.54  4876.1  414.77  4905.0  412.92  4911.4  412.80  4919.5  411.50
  4922.5  411.42  4934.0  410.49  4940.3  410.44  4948.5  407.69  4954.8  407.00
  5068.3  407.28  5193.6  406.91  5193.9  406.41  5197.4  406.41  5197.6  406.91
  5202.8  406.97  5217.0  408.98  5221.3  409.95  5223.9  410.54  5231.1  410.64
  5238.1  412.04  5245.3  412.27  5252.2  413.07  5273.6  414.13  5287.7  415.21
  5294.7  414.92  5308.8  415.48  5323.0  415.63  5325.6  416.08  5328.0  416.08
#Mann=5,-1,0
  4870.1    0.05       0  4922.5   0.033       0  5193.6   0.033       0
  5197.6   0.033       0  5221.3    0.07       0
Bank Sta=5193.6,5197.6
Exp/Cntr=0.3,0.1

Type RM Length L Ch R = 1,2541,31,31,31
BEGIN DESCRIPTION:
Twin Creek2102541.37
END DESCRIPTION:
XS GIS Cut Line= 6
      2735919.27      6833514.82      2735779.81      6833540.10
      2735720.73      6833568.57      2735671.28      6833655.72
      2735654.60      6833708.58      2735637.27      6833882.17
#Sta/Elev= 30
  4695.0  413.41  4728.8  412.23  4739.0  410.50  4749.1  407.62  4755.9  407.04
  4761.0  407.25  4789.8  407.07  4799.9  407.54  4814.5  407.07  4842.5  407.33
  4869.0  406.87  4869.3  406.37  4872.8  406.37  4873.0  406.87  4894.2  407.33
  4899.2  407.08  4902.2  407.53  4906.6  407.53  4916.4  407.22  4959.7  407.04
  4987.1  407.30  5035.5  407.24  5040.7  407.00  5070.4  407.36  5080.5  409.38
  5094.9  411.27  5150.8  414.11  5190.4  414.87  5201.1  415.39  5232.4  416.07
#Mann=5,-1,0
  4695.0    0.05       0  4842.5   0.033       0  4869.0    0.07       0
  4873.0   0.033       0  4894.2    0.07       0
Bank Sta=4869,4873
Exp/Cntr=0.3,0.1

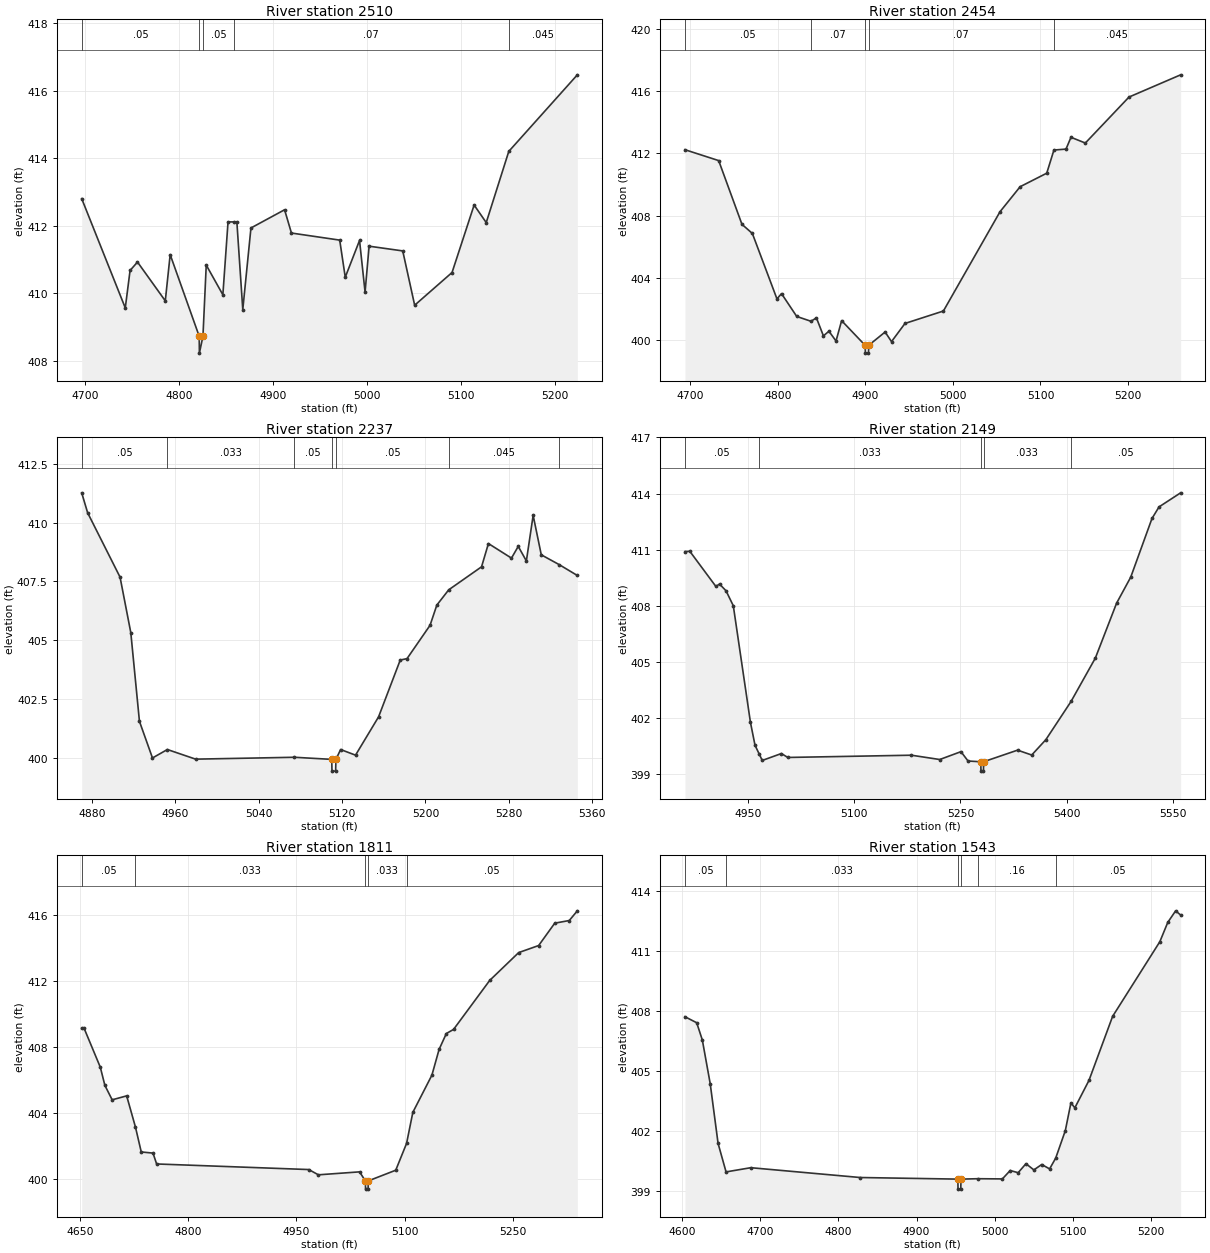
Type RM Length L Ch R = 1,2510,56,56,56
BEGIN DESCRIPTION:
Twin Creek2102510.03
END DESCRIPTION:
XS GIS Cut Line= 5
      2735883.87      6833475.01      2735771.92      6833500.94
      2735719.57      6833524.38      2735646.38      6833636.95
      2735558.92      6833840.08
#Sta/Elev= 30
  4696.3  412.80  4742.7  409.56  4747.8  410.67  4755.7  410.92  4785.3  409.77
  4790.5  411.14  4821.4  408.72  4821.6  408.22  4825.4  408.72  4828.9  410.83
  4846.6  409.95  4852.1  412.11  4858.2  412.11  4861.5  412.11  4867.8  409.51
  4876.5  411.93  4912.3  412.47  4919.6  411.78  4971.0  411.57  4976.9  410.47
  4992.1  411.56  4998.0  410.03  5002.3  411.39  5038.1  411.25  5050.8  409.64
  5090.6  410.61  5114.1  412.61  5127.0  412.09  5151.0  414.20  5224.0  416.47
#Mann=5,-1,0
  4696.3    0.05       0  4821.4    0.07       0  4825.4    0.05       0
  4858.2    0.07       0  5151.0   0.045       0
Bank Sta=4821.4,4825.4
Exp/Cntr=0.3,0.1

Type RM Length L Ch R = 1,2454,217,217,217
BEGIN DESCRIPTION:
Twin Creek2102453.88
END DESCRIPTION:
XS GIS Cut Line= 6
      2735868.47      6833425.30      2735729.77      6833466.18
      2735660.16      6833520.38      2735623.25      6833589.64
      2735592.31      6833639.57      2735500.49      6833813.13
#Sta/Elev= 30
  4693.8  412.24  4732.3  411.54  4758.9  407.44  4770.8  406.85  4798.9  402.64
  4804.1  402.98  4821.5  401.51  4837.8  401.20  4844.0  401.42  4852.0  400.26
  4858.3  400.56  4866.4  399.93  4872.8  401.24  4899.7  399.65  4900.0  399.15
  4903.5  399.15  4903.7  399.65  4922.5  400.51  4929.8  399.89  4945.2  401.06
  4989.1  401.86  5053.8  408.25  5076.8  409.86  5107.2  410.73  5115.4  412.22
  5129.2  412.28  5134.9  413.04  5151.3  412.67  5201.2  415.63  5260.2  417.06
#Mann=5,-1,0
  4693.8    0.05       0  4837.8    0.07       0  4899.7    0.07       0
  4903.7    0.07       0  5115.4   0.045       0
Bank Sta=4899.7,4903.7
Exp/Cntr=0.3,0.1

Type RM Length L Ch R = 1,2237,88,88,88
BEGIN DESCRIPTION:
Twin Creek2102237.38
END DESCRIPTION:
XS GIS Cut Line= 3
      2735801.47      6833350.57      2735670.24      6833386.43
      2735410.39      6833604.85
#Sta/Elev= 30
  4870.2  411.27  4875.9  410.42  4907.0  407.68  4917.3  405.32  4925.6  401.54
  4938.1  399.98  4952.4  400.34  4979.5  399.93  5074.3  400.01  5110.1  399.92
  5110.3  399.42  5113.8  399.42  5114.1  399.92  5118.6  400.34  5132.9  400.10
  5155.0  401.73  5175.8  404.15  5182.3  404.21  5204.4  405.63  5210.9  406.49
  5222.3  407.14  5253.8  408.12  5260.4  409.11  5282.5  408.49  5289.0  408.99
  5296.8  408.37  5303.3  410.31  5311.1  408.63  5328.4  408.21  5345.7  407.75
#Mann=7,-1,0
  4870.2    0.05       0  4952.4   0.033       0  5074.3    0.05       0
  5110.1   0.033       0  5114.1    0.05       0  5222.3   0.045       0
  5328.4    0.05       0
Bank Sta=5110.1,5114.1
Exp/Cntr=0.3,0.1

Type RM Length L Ch R = 1,2149,338,338,338
BEGIN DESCRIPTION:
Twin Creek2102148.95
END DESCRIPTION:
XS GIS Cut Line= 3
      2735812.68      6833266.40      2735670.50      6833297.68
      2735115.55      6833306.20
#Sta/Elev= 30
  4860.6  410.90  4867.4  410.92  4904.3  409.04  4909.4  409.17  4918.6  408.81
  4928.9  408.01  4953.1  401.79  4959.6  400.56  4965.8  400.07  4969.8  399.75
  4996.9  400.12  5005.9  399.91  5180.7  400.03  5220.7  399.80  5250.7  400.22
  5260.7  399.72  5278.7  399.68  5279.0  399.18  5282.5  399.18  5282.7  399.68
  5330.7  400.30  5350.7  400.04  5370.7  400.86  5406.3  402.90  5440.7  405.22
  5470.7  408.15  5490.7  409.54  5520.7  412.67  5530.7  413.29  5561.2  414.04
#Mann=5,-1,0
  4860.6    0.05       0  4965.8   0.033       0  5278.7   0.033       0
  5282.7   0.033       0  5406.3    0.05       0
Bank Sta=5278.7,5282.7
Exp/Cntr=0.3,0.1

Type RM Length L Ch R = 1,1811,268,268,268
BEGIN DESCRIPTION:
Twin Creek2101810.65
END DESCRIPTION:
XS GIS Cut Line= 3
      2735757.79      6833102.75      2735400.30      6833150.58
      2735074.79      6833168.85
#Sta/Elev= 30
  4652.7  409.13  4656.1  409.13  4678.5  406.77  4684.8  405.67  4694.9  404.79
  4715.0  405.03  4727.2  403.13  4735.2  401.62  4751.5  401.55  4756.5  400.89
  4967.3  400.55  4980.6  400.23  5037.7  400.41  5045.7  399.86  5046.0  399.36
  5049.5  399.36  5049.7  399.86  5087.8  400.51  5102.8  402.14  5111.5  404.03
  5137.9  406.29  5147.9  407.86  5157.9  408.82  5167.9  409.07  5218.0  412.05
  5258.1  413.74  5285.8  414.17  5308.1  415.53  5328.2  415.69  5339.4  416.28
#Mann=5,-1,0
  4652.7    0.05       0  4727.2   0.033       0  5045.7   0.033       0
  5049.7   0.033       0  5102.8    0.05       0
Bank Sta=5045.7,5049.7
Exp/Cntr=0.3,0.1

Type RM Length L Ch R = 1,1543,210,210,210
BEGIN DESCRIPTION:
Twin Creek2101543.21
END DESCRIPTION:
XS GIS Cut Line= 3
      2735717.98      6832997.90      2735320.82      6832938.72
      2735089.67      6832907.43
#Sta/Elev= 30
  4603.4  407.72  4618.4  407.42  4625.6  406.56  4635.7  404.38  4645.8  401.39
  4656.0  399.97  4687.7  400.18  4827.8  399.69  4952.9  399.61  4953.1  399.11
  4956.6  399.11  4956.9  399.61  4978.6  399.63  5009.9  399.62  5019.9  400.04
  5030.1  399.93  5040.1  400.38  5050.2  400.07  5060.3  400.34  5070.4  400.12
  5078.2  400.66  5090.5  402.03  5097.7  403.42  5102.7  403.17  5120.8  404.54
  5151.1  407.74  5211.6  411.47  5221.7  412.43  5231.8  413.01  5238.2  412.80
#Mann=6,-1,0
  4603.4    0.05       0  4656.0   0.033       0  4952.9    0.07       0
  4956.9   0.033       0  4978.6    0.16       0  5078.2    0.05       0
Bank Sta=4952.9,4956.9
Exp/Cntr=0.3,0.1

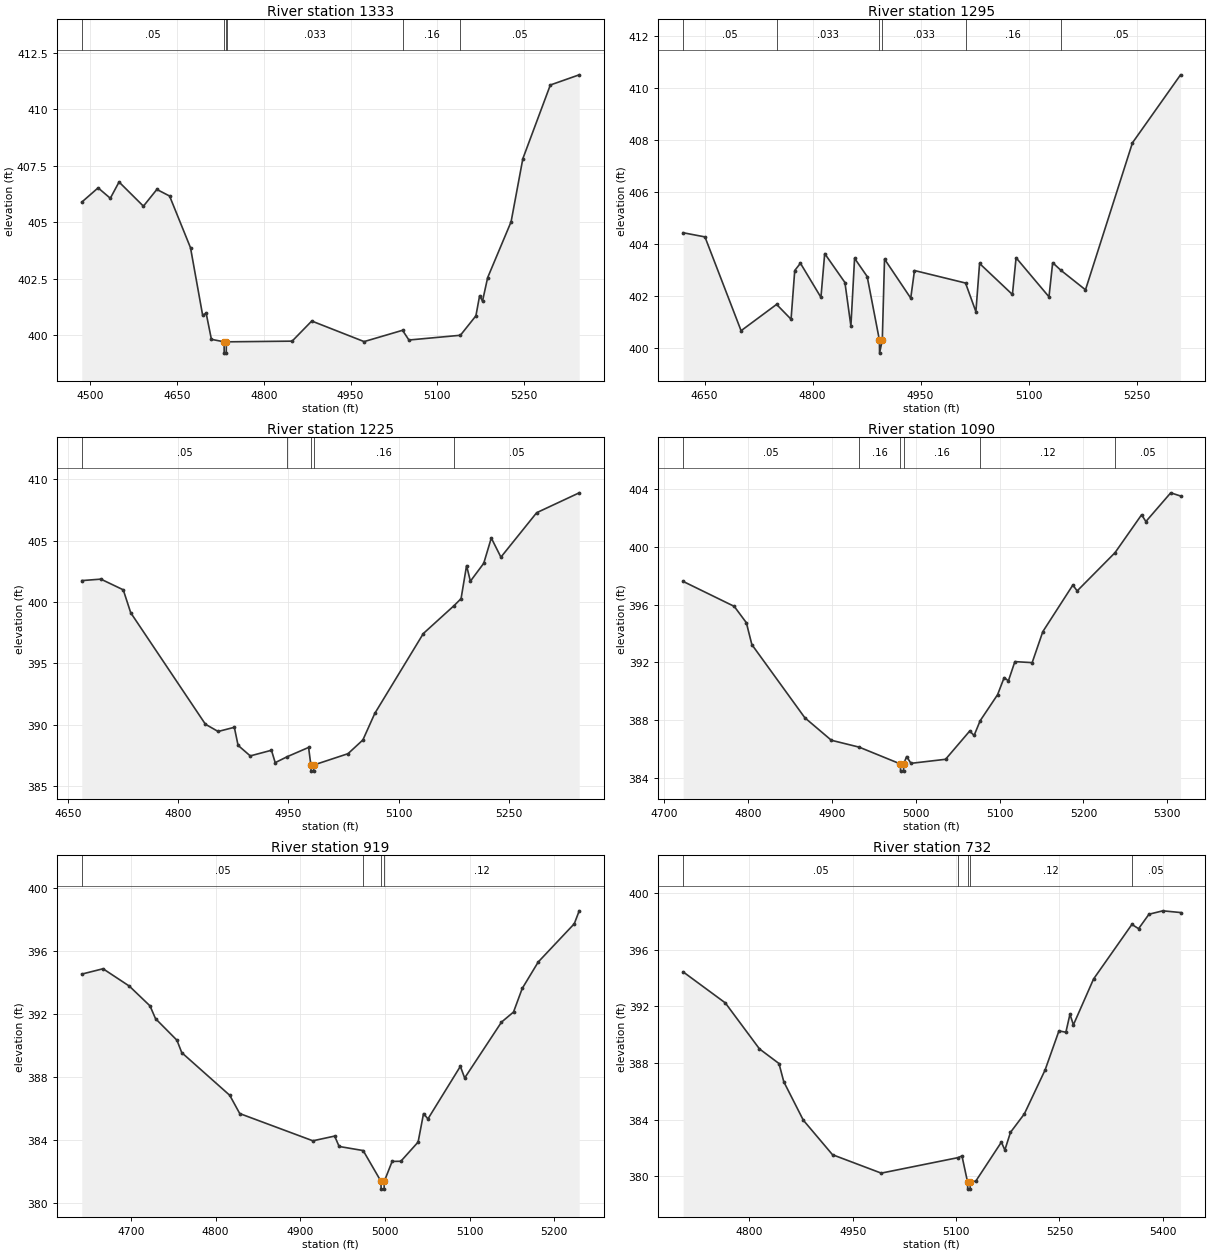
Type RM Length L Ch R = 1,1333,38,38,38
BEGIN DESCRIPTION:
Twin Creek2101332.621
END DESCRIPTION:
XS GIS Cut Line= 4
      2735854.34      6832981.67      2735646.32      6832844.68
      2735390.37      6832774.38      2735049.88      6832718.17
#Sta/Elev= 30
  4485.5  405.90  4513.7  406.53  4534.8  406.07  4549.9  406.79  4592.0  405.72
  4615.2  406.46  4637.2  406.17  4673.4  403.88  4694.4  400.89  4700.4  400.99
  4709.5  399.83  4731.4  399.72  4731.6  399.22  4735.1  399.22  4735.4  399.72
  4736.5  399.72  4849.0  399.75  4882.9  400.64  4973.4  399.73  5039.8  400.23
  5050.8  399.80  5139.8  400.01  5166.6  400.87  5173.0  401.76  5178.0  401.52
  5186.9  402.56  5227.4  405.03  5247.7  407.82  5295.2  411.08  5345.1  411.53
#Mann=6,-1,0
  4485.5    0.05       0  4731.4   0.033       0  4735.4    0.05       0
  4736.5   0.033       0  5039.8    0.16       0  5139.8    0.05       0
Bank Sta=4731.4,4735.4
Exp/Cntr=0.3,0.1

Type RM Length L Ch R = 1,1295,70,70,70
BEGIN DESCRIPTION:
Twin Creek2101294.58
END DESCRIPTION:
XS GIS Cut Line= 3
      2735764.20      6832832.32      2735393.45      6832741.28
      2735090.53      6832680.09
#Sta/Elev= 30
  4620.2  404.44  4650.5  404.28  4700.7  400.68  4750.0  401.69  4770.1  401.12
  4775.2  402.99  4783.1  403.27  4811.6  401.96  4816.8  403.64  4844.9  402.53
  4853.2  400.86  4858.3  403.46  4875.8  402.76  4892.8  400.32  4893.0  399.82
  4896.8  400.32  4899.9  403.43  4936.3  401.93  4941.5  402.99  5012.4  402.51
  5026.8  401.41  5031.9  403.26  5077.5  402.07  5082.6  403.48  5128.3  401.98
  5133.4  403.29  5144.8  403.00  5179.0  402.25  5244.2  407.89  5311.0  410.50
#Mann=6,-1,0
  4620.2    0.05       0  4750.0   0.033       0  4892.8   0.033       0
  4896.8   0.033       0  5012.4    0.16       0  5144.8    0.05       0
Bank Sta=4892.8,4896.8
Exp/Cntr=0.3,0.1

Type RM Length L Ch R = 1,1225,135,135,135
BEGIN DESCRIPTION:
Twin Creek2101224.72
END DESCRIPTION:
XS GIS Cut Line= 4
      2735751.57      6832745.43      2735566.83      6832710.75
      2735422.42      6832681.35      2735089.61      6832600.19
#Sta/Elev= 30
  4668.3  401.74  4694.3  401.86  4724.8  400.99  4735.0  399.12  4836.8  390.04
  4854.1  389.45  4876.2  389.79  4881.3  388.32  4897.9  387.46  4926.8  387.92
  4931.9  386.91  4948.4  387.40  4977.4  388.15  4980.5  386.72  4980.8  386.22
  4984.3  386.22  4984.5  386.72  5031.1  387.64  5051.4  388.76  5067.6  390.92
  5133.8  397.43  5175.8  399.71  5185.2  400.27  5192.7  402.96  5197.9  401.69
  5216.1  403.15  5226.4  405.21  5239.5  403.65  5288.2  407.27  5346.2  408.89
#Mann=5,-1,0
  4668.3    0.05       0  4948.4    0.16       0  4980.5    0.07       0
  4984.5    0.16       0  5175.8    0.05       0
Bank Sta=4980.5,4984.5
Exp/Cntr=0.3,0.1

Type RM Length L Ch R = 1,1090,171,171,171
BEGIN DESCRIPTION:
Twin Creek2101090.1
END DESCRIPTION:
XS GIS Cut Line= 3
      2735733.83      6832649.03      2735469.20      6832562.25
      2735164.66      6832484.91
#Sta/Elev= 30
  4723.0  397.61  4783.9  395.88  4798.3  394.75  4804.9  393.23  4868.0  388.16
  4899.6  386.60  4932.9  386.12  4981.8  384.96  4982.1  384.46  4985.6  384.46
  4985.8  384.96  4989.3  385.47  4994.5  385.00  5035.7  385.28  5064.5  387.24
  5069.7  386.93  5076.9  387.95  5097.7  389.76  5105.5  390.94  5110.6  390.72
  5118.3  392.05  5138.9  391.98  5151.6  394.13  5187.4  397.36  5192.5  396.95
  5237.6  399.60  5269.3  402.23  5274.4  401.76  5304.0  403.75  5315.7  403.53
#Mann=6,-1,0
  4723.0    0.05       0  4932.9    0.16       0  4981.8    0.07       0
  4985.8    0.16       0  5076.9    0.12       0  5237.6    0.05       0
Bank Sta=4981.8,4985.8
Exp/Cntr=0.3,0.1

Type RM Length L Ch R = 1,919,187,187,187
BEGIN DESCRIPTION:
Twin Creek210918.8
END DESCRIPTION:
XS GIS Cut Line= 3
      2735772.06      6832525.26      2735431.03      6832405.48
      2735210.31      6832356.25
#Sta/Elev= 30
  4641.9  394.56  4667.0  394.90  4698.0  393.80  4722.5  392.54  4729.0  391.73
  4754.3  390.36  4760.0  389.57  4816.7  386.86  4828.5  385.70  4914.9  383.97
  4940.6  384.27  4945.9  383.61  4974.3  383.35  4995.3  381.40  4995.5  380.90
  4999.0  380.90  4999.3  381.40  5008.5  382.66  5018.8  382.67  5039.2  383.89
  5045.6  385.70  5050.8  385.36  5089.1  388.70  5094.2  387.96  5137.7  391.51
  5151.9  392.15  5162.2  393.65  5181.1  395.33  5223.7  397.76  5229.5  398.58
#Mann=4,-1,0
  4641.9    0.05       0  4974.3    0.12       0  4995.3    0.07       0
  4999.3    0.12       0
Bank Sta=4995.3,4999.3
Exp/Cntr=0.3,0.1

Type RM Length L Ch R = 1,732,229,229,229
BEGIN DESCRIPTION:
Twin Creek210732.2
END DESCRIPTION:
XS GIS Cut Line= 3
      2735777.61      6832476.01      2735570.81      6832273.71
      2735140.44      6832229.81
#Sta/Elev= 30
  4703.8  394.43  4765.0  392.24  4814.6  388.99  4842.9  387.96  4849.9  386.67
  4878.2  383.96  4920.6  381.52  4991.3  380.22  5102.4  381.31  5108.5  381.43
  5116.6  379.59  5116.8  379.09  5120.3  379.09  5120.6  379.59  5128.6  379.66
  5165.7  382.41  5170.7  381.85  5178.9  383.10  5199.0  384.40  5229.1  387.50
  5249.2  390.26  5259.3  390.17  5265.2  391.44  5270.2  390.69  5299.5  393.93
  5355.1  397.78  5364.8  397.48  5379.9  398.50  5400.0  398.74  5425.7  398.62
#Mann=5,-1,0
  4703.8    0.05       0  5102.4    0.12       0  5116.6    0.05       0
  5120.6    0.12       0  5355.1    0.05       0
Bank Sta=5116.6,5120.6
Exp/Cntr=0.3,0.1

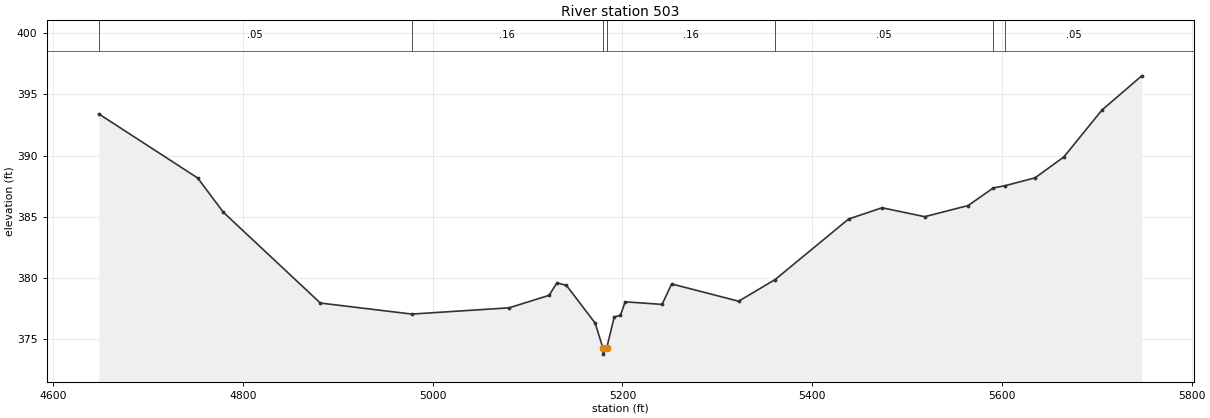
Type RM Length L Ch R = 1,503,0,0,0
BEGIN DESCRIPTION:
Twin Creek210503.123
END DESCRIPTION:
XS GIS Cut Line= 3
      2735832.09      6832446.45      2735726.00      6832111.00
      2734984.43      6832017.25
#Sta/Elev= 30
  4648.1  393.41  4752.3  388.18  4779.4  385.38  4881.6  377.97  4978.0  377.07
  5080.6  377.58  5122.7  378.60  5131.0  379.62  5141.0  379.41  5171.3  376.33
  5179.4  374.30  5179.6  373.80  5183.4  374.30  5191.4  376.84  5197.9  376.96
  5202.9  378.07  5241.8  377.86  5251.9  379.53  5322.5  378.12  5361.0  379.89
  5438.4  384.83  5473.7  385.75  5518.6  385.02  5564.4  385.93  5591.0  387.37
  5603.2  387.55  5634.9  388.19  5665.2  389.89  5705.5  393.73  5747.4  396.52
#Mann=7,-1,0
  4648.1    0.05       0  4978.0    0.16       0  5179.4    0.07       0
  5183.4    0.16       0  5361.0    0.05       0  5591.0    0.12       0
  5603.2    0.05       0
Bank Sta=5179.4,5183.4
Exp/Cntr=0.3,0.1

Chan Stop Cuts=-1