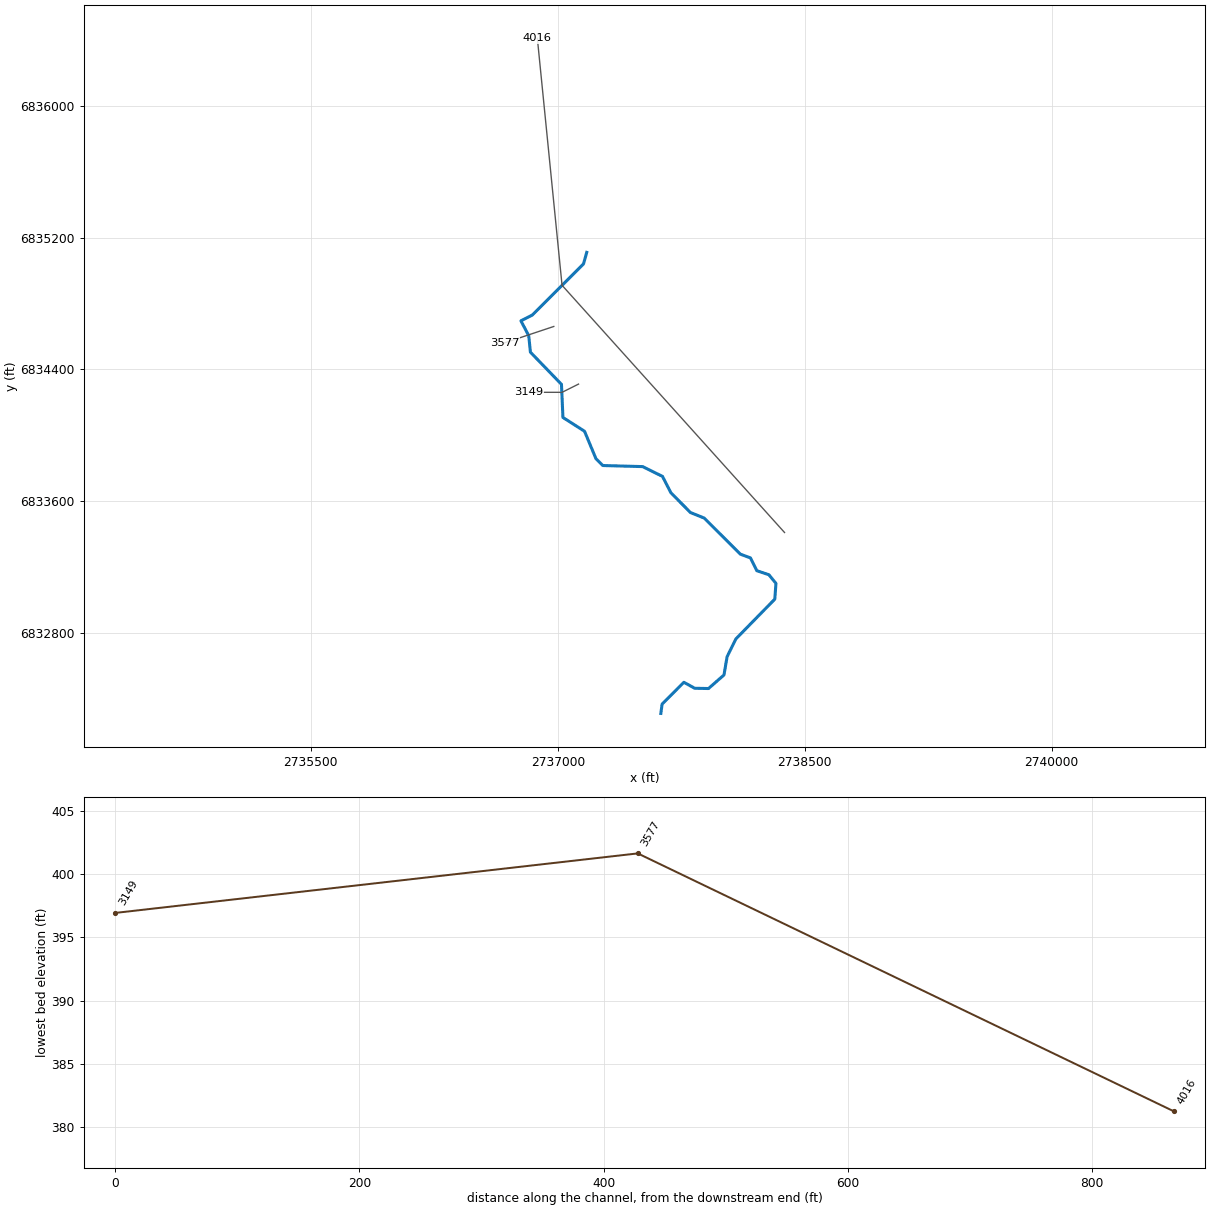
--- Twin Creek212.prj (project) ---

Proj Title=Twin Creek212 Base Level Engineering
Current Plan=p01
Default Exp/Contr=0.3,0.1
English Units
Geom File=g01
Flow File=f01
Plan File=p01
BEGIN DESCRIPTION:
Twin Creek212
END DESCRIPTION:

--- Twin Creek212.p01 (plan) ---

Plan Title=Multiple Run
Short Identifier=Multiple
Geom File=g01
Flow File=f01
Subcritical Flow
K Sum by GR= 0
Std Step Tol= 0.01
Critical Tol= 0.01
Num of Std Step Trials= 20
Max Error Tol= 0.3
Flow Tol Ratio= 0.001
Split Flow NTrial= 30
Split Flow Tol= 0.02
Split Flow Ratio= 0.02
Log Output Level= 0
Friction Slope Method= 1
Unsteady Friction Slope Method= 2
Unsteady Bridges Friction Slope Method= 1
Parabolic Critical Depth
Global Vel Dist=  1 , 1 , 1
Global Log Level= 0
CheckData=True
Encroach Param= -1, 0, 0, 0
BEGIN DESCRIPTION:
Multiple Run
END DESCRIPTION:

--- Twin Creek212.f01 (steady flow) ---

Flow Title=Multiple
Number of Profiles=7
Profile Names=10-year,25-year,50-year,1pct_min,100-year,1pct_plu,500-year
River Rch & RM= Twin Creek212,Reach-1,4016
     301     385     450     262     523    1044     703
Boundary for River Rch & Prof#=Twin Creek212,Reach-1,1
Up Type=0
Dn Type=3
Dn Slope=0.005
Boundary for River Rch & Prof#=Twin Creek212,Reach-1,2
Up Type=0
Dn Type=3
Dn Slope=0.005
Boundary for River Rch & Prof#=Twin Creek212,Reach-1,3
Up Type=0
Dn Type=3
Dn Slope=0.005
Boundary for River Rch & Prof#=Twin Creek212,Reach-1,4
Up Type=0
Dn Type=3
Dn Slope=0.005
Boundary for River Rch & Prof#=Twin Creek212,Reach-1,5
Up Type=0
Dn Type=3
Dn Slope=0.005
Boundary for River Rch & Prof#=Twin Creek212,Reach-1,6
Up Type=0
Dn Type=3
Dn Slope=0.005
Boundary for River Rch & Prof#=Twin Creek212,Reach-1,7
Up Type=0
Dn Type=3
Dn Slope=0.005

--- Twin Creek212.g01 (geometry) ---

Geom Title=Existing Conditions

River Reach=Twin Creek212,Reach-1
Reach XY= 30
      2737176.00      6835111.00      2737156.22      6835040.91
      2736845.88      6834730.86      2736776.23      6834694.99
      2736823.61      6834605.06      2736833.86      6834504.83
      2737022.46      6834309.54      2737031.36      6834108.30
      2737162.52      6834024.56      2737231.71      6833858.42
      2737273.30      6833816.36      2737515.50      6833809.80
      2737636.00      6833750.37      2737686.79      6833651.34
      2737805.91      6833530.79      2737889.21      6833497.37
      2738109.52      6833277.73      2738170.37      6833255.35
      2738209.00      6833177.58      2738282.37      6833152.97
      2738325.13      6833100.67      2738318.24      6833004.83
      2738081.83      6832763.30      2738028.33      6832655.03
      2738009.56      6832544.21      2737915.52      6832461.94
      2737831.89      6832463.37      2737765.94      6832499.90
      2737633.76      6832367.21      2737626.00      6832311.00

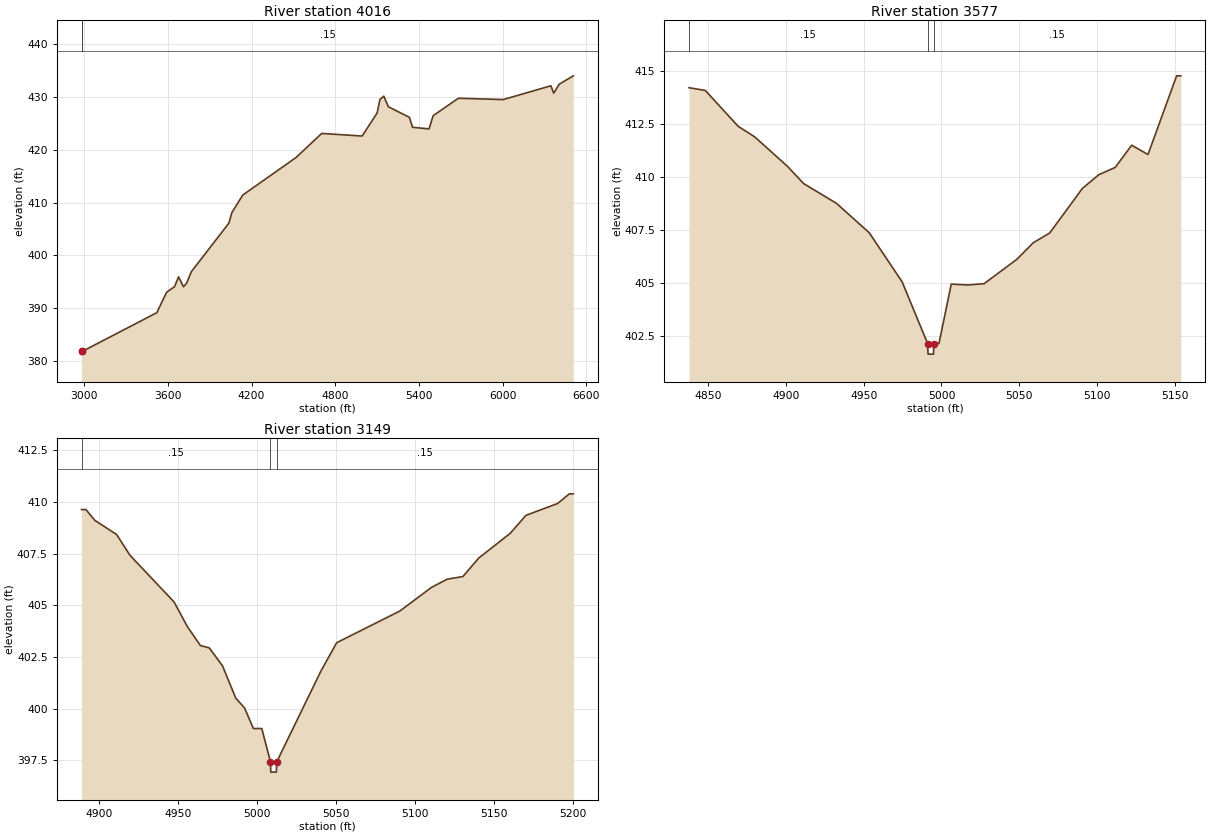
Type RM Length L Ch R = 1,4016,439,439,439
BEGIN DESCRIPTION:
Twin Creek212 3.0
END DESCRIPTION:
XS GIS Cut Line= 3
      2738377.32      6833409.54      2737026.00      6834911.00
      2736876.00      6836411.01
#Sta/Elev= 30
  2980.0  381.77  2980.2  381.27  2984.0  381.77  3520.1  389.12  3590.7  393.01
  3647.5  394.06  3676.0  395.92  3711.1  394.05  3732.8  394.65  3767.9  396.89
  4037.0  406.09  4058.3  408.08  4136.4  411.41  4518.3  418.52  4702.9  423.09
  4992.9  422.60  5100.5  426.98  5120.6  429.53  5148.2  430.15  5180.9  428.15
  5331.7  426.15  5354.3  424.26  5472.4  423.95  5502.5  426.46  5683.4  429.76
  6005.0  429.51  6346.7  432.12  6366.8  430.73  6407.0  432.43  6507.5  434.01
#Mann=2,-1,0
  2980.0    0.05       0  2984.0    0.15       0
Bank Sta=2980,2984
Exp/Cntr=0.3,0.1

Type RM Length L Ch R = 1,3577,428,428,428
BEGIN DESCRIPTION:
Twin Creek212 2.0
END DESCRIPTION:
XS GIS Cut Line= 3
      2736975.96      6834660.99      2736826.00      6834611.00
      2736675.98      6834560.99
#Sta/Elev= 27
  4837.7  414.19  4848.2  414.06  4869.3  412.37  4879.8  411.88  4900.9  410.49
  4911.4  409.67  4932.5  408.74  4953.6  407.35  4974.7  405.04  4991.1  402.13
  4991.4  401.63  4994.9  401.63  4995.1  402.13  4998.4  402.13  5006.3  404.93
  5016.9  404.89  5027.4  404.95  5048.5  406.10  5059.0  406.88  5069.6  407.34
  5090.6  409.44  5101.2  410.09  5111.7  410.43  5122.3  411.48  5132.8  411.04
  5151.2  414.75  5153.9  414.75
#Mann=3,-1,0
  4837.7    0.15       0  4991.1    0.05       0  4995.1    0.15       0
Bank Sta=4991.1,4995.1
Exp/Cntr=0.3,0.1

Type RM Length L Ch R = 1,3149,0,0,0
BEGIN DESCRIPTION:
Twin Creek212 1.0
END DESCRIPTION:
XS GIS Cut Line= 3
      2737125.98      6834310.99      2737026.00      6834261.00
      2736825.98      6834261.00
#Sta/Elev= 30
  4888.7  409.63  4891.5  409.63  4897.1  409.11  4911.0  408.42  4919.4  407.42
  4947.4  405.16  4955.8  403.97  4964.1  403.05  4969.7  402.94  4978.1  402.07
  4986.5  400.51  4992.1  400.03  4997.7  399.04  5003.0  399.04  5008.5  397.43
  5008.7  396.93  5012.2  396.93  5012.5  397.43  5040.5  401.82  5050.5  403.19
  5090.5  404.72  5110.5  405.86  5120.5  406.26  5130.5  406.39  5140.5  407.28
  5160.5  408.48  5170.5  409.35  5190.5  409.92  5198.0  410.39  5200.5  410.39
#Mann=3,-1,0
  4888.7    0.15       0  5008.5    0.05       0  5012.5    0.15       0
Bank Sta=5008.5,5012.5
Exp/Cntr=0.3,0.1

Chan Stop Cuts=-1