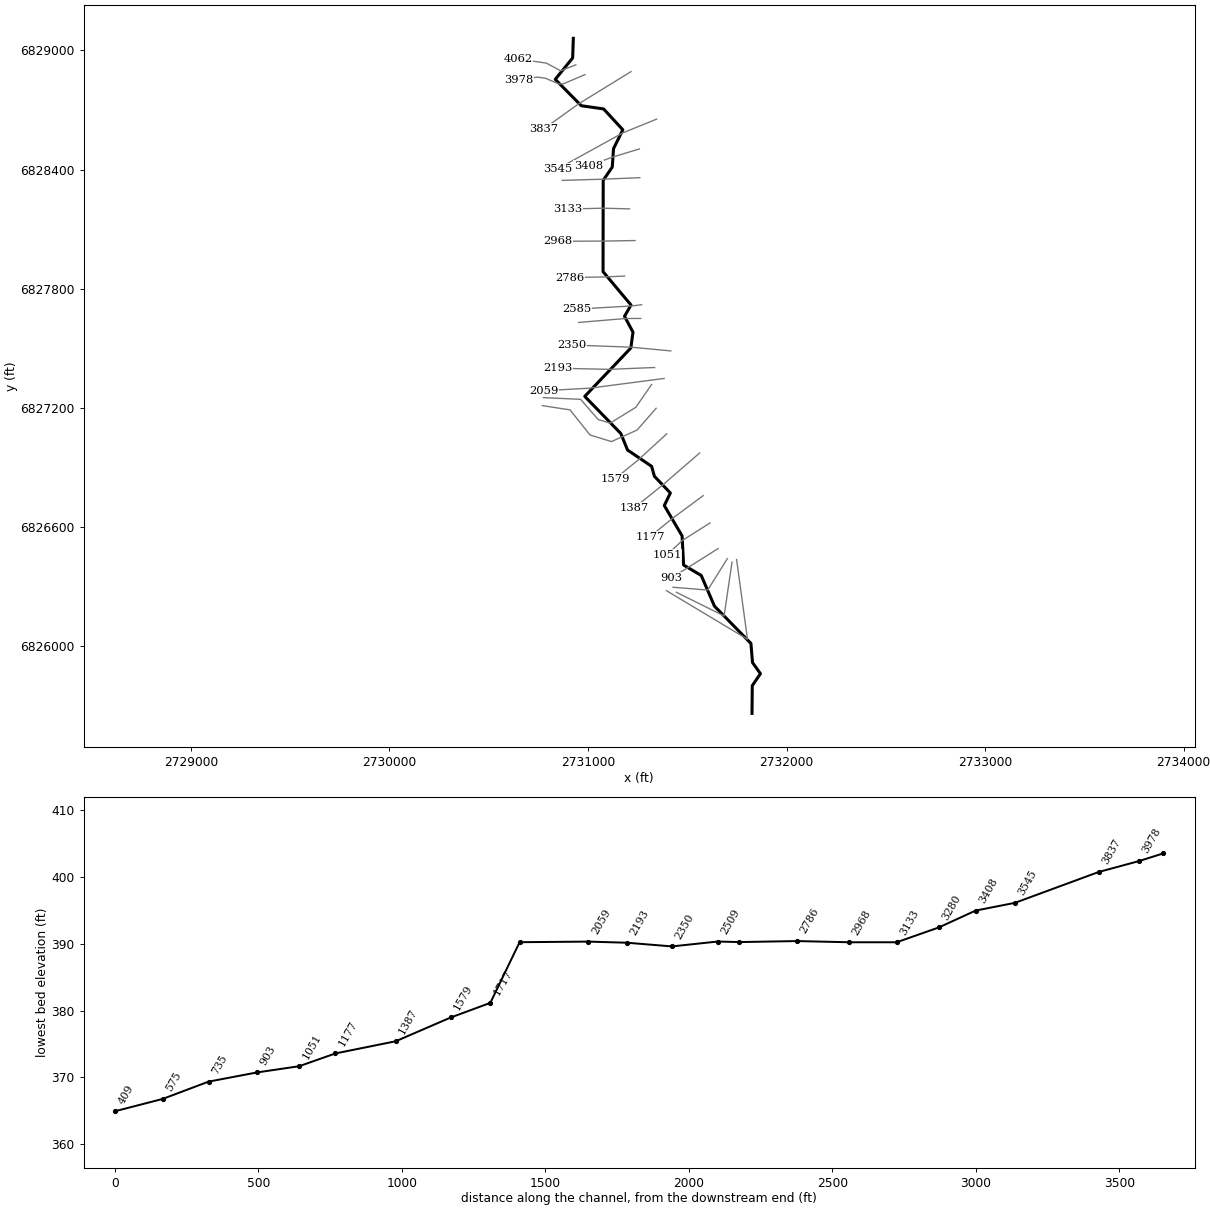
--- Twin Creek214.prj (project) ---

Proj Title=Twin Creek214 Base Level Engineering
Current Plan=p01
Default Exp/Contr=0.3,0.1
English Units
Geom File=g01
Flow File=f01
Plan File=p01
BEGIN DESCRIPTION:
Twin Creek214
END DESCRIPTION:

--- Twin Creek214.p01 (plan) ---

Plan Title=Multiple Run
Short Identifier=Multiple
Geom File=g01
Flow File=f01
Subcritical Flow
K Sum by GR= 0
Std Step Tol= 0.01
Critical Tol= 0.01
Num of Std Step Trials= 20
Max Error Tol= 0.3
Flow Tol Ratio= 0.001
Split Flow NTrial= 30
Split Flow Tol= 0.02
Split Flow Ratio= 0.02
Log Output Level= 0
Friction Slope Method= 1
Unsteady Friction Slope Method= 2
Unsteady Bridges Friction Slope Method= 1
Parabolic Critical Depth
Global Vel Dist=  1 , 1 , 1
Global Log Level= 0
CheckData=True
Encroach Param= -1, 0, 0, 0
BEGIN DESCRIPTION:
Multiple Run
END DESCRIPTION:

--- Twin Creek214.f01 (steady flow) ---

Flow Title=Multiple
Number of Profiles=7
Profile Names=10-year,25-year,50-year,1pct_min,100-year,1pct_plu,500-year
River Rch & RM= Twin Creek214,Reach-1,4062
     153     187     212     120     239     476     302
Boundary for River Rch & Prof#=Twin Creek214,Reach-1,1
Up Type=0
Dn Type=3
Dn Slope=0.005
Boundary for River Rch & Prof#=Twin Creek214,Reach-1,2
Up Type=0
Dn Type=3
Dn Slope=0.005
Boundary for River Rch & Prof#=Twin Creek214,Reach-1,3
Up Type=0
Dn Type=3
Dn Slope=0.005
Boundary for River Rch & Prof#=Twin Creek214,Reach-1,4
Up Type=0
Dn Type=3
Dn Slope=0.005
Boundary for River Rch & Prof#=Twin Creek214,Reach-1,5
Up Type=0
Dn Type=3
Dn Slope=0.005
Boundary for River Rch & Prof#=Twin Creek214,Reach-1,6
Up Type=0
Dn Type=3
Dn Slope=0.005
Boundary for River Rch & Prof#=Twin Creek214,Reach-1,7
Up Type=0
Dn Type=3
Dn Slope=0.005

--- Twin Creek214.g01 (geometry) ---

Geom Title=Existing Conditions

River Reach=Twin Creek214,Reach-1
Reach XY= 30
      2730926.00      6829061.00      2730922.59      6828962.40
      2730834.96      6828854.33      2730966.21      6828721.52
      2731078.44      6828705.48      2731175.41      6828600.39
      2731128.38      6828505.03      2731122.14      6828412.60
      2731076.52      6828345.78      2731075.70      6827885.88
      2731216.70      6827717.67      2731183.81      6827661.10
      2731226.54      6827581.08      2731215.56      6827501.21
      2730983.59      6827257.67      2731165.22      6827070.68
      2731199.00      6826987.49      2731320.38      6826905.38
      2731334.32      6826855.25      2731414.74      6826771.00
      2731384.25      6826707.77      2731473.75      6826555.07
      2731481.40      6826408.32      2731570.37      6826355.38
      2731636.77      6826201.32      2731820.48      6826013.43
      2731828.56      6825916.90      2731868.45      6825861.00
      2731827.34      6825800.59      2731826.00      6825661.00

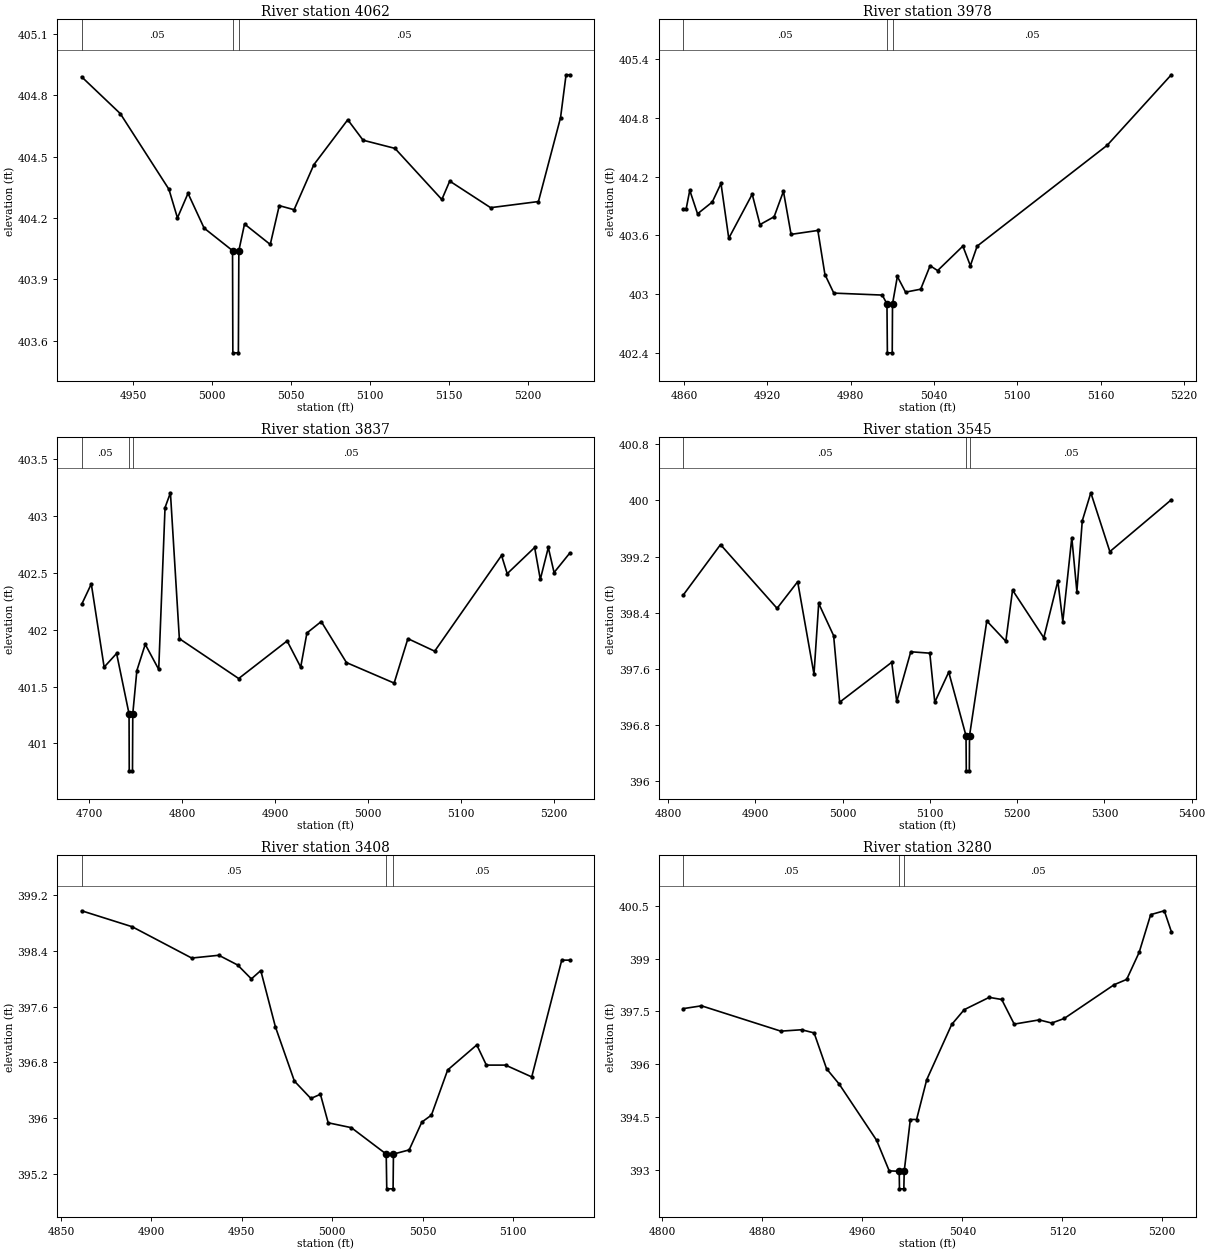
Type RM Length L Ch R = 1,4062,84,84,84
BEGIN DESCRIPTION:
Twin Creek2144062.117
END DESCRIPTION:
XS GIS Cut Line= 4
      2730938.83      6828927.50      2730861.93      6828897.62
      2730790.20      6828936.13      2730646.42      6828956.99
#Sta/Elev= 25
  4917.5  404.89  4942.0  404.71  4972.8  404.34  4978.2  404.20  4984.9  404.32
  4995.1  404.15  5013.1  404.04  5013.3  403.54  5016.8  403.54  5017.1  404.04
  5020.7  404.17  5037.0  404.07  5042.7  404.26  5052.1  404.24  5064.6  404.46
  5086.1  404.68  5095.8  404.58  5116.0  404.54  5145.7  404.29  5150.7  404.38
  5176.6  404.25  5206.9  404.28  5220.9  404.69  5224.4  404.90  5226.7  404.90
#Mann=3,-1,0
  4917.5    0.05       0  5013.1    0.05       0  5017.1    0.05       0
Bank Sta=5013.1,5017.1
Exp/Cntr=0.3,0.1

Type RM Length L Ch R = 1,3978,141,141,141
BEGIN DESCRIPTION:
Twin Creek2143978.11
END DESCRIPTION:
XS GIS Cut Line= 6
      2730984.77      6828878.34      2730874.96      6828831.61
      2730851.44      6828831.93      2730786.12      6828859.83
      2730744.83      6828865.79      2730650.36      6828851.54
#Sta/Elev= 30
  4859.3  403.87  4861.4  403.87  4864.0  404.06  4869.6  403.82  4880.2  403.94
  4886.5  404.13  4892.1  403.57  4909.0  404.02  4914.6  403.71  4924.8  403.79
  4931.5  404.05  4937.0  403.61  4956.3  403.65  4961.4  403.20  4967.8  403.01
  5002.7  402.99  5006.1  402.90  5006.4  402.40  5009.9  402.40  5010.1  402.90
  5013.6  403.18  5019.5  403.02  5030.4  403.05  5037.2  403.29  5042.6  403.24
  5060.8  403.49  5066.2  403.29  5071.1  403.49  5164.8  404.52  5211.0  405.24
#Mann=3,-1,0
  4859.3    0.05       0  5006.1    0.05       0  5010.1    0.05       0
Bank Sta=5006.1,5010.1
Exp/Cntr=0.3,0.1

Type RM Length L Ch R = 1,3837,292,292,292
BEGIN DESCRIPTION:
Twin Creek2143836.54
END DESCRIPTION:
XS GIS Cut Line= 3
      2731216.61      6828893.46      2730952.50      6828730.83
      2730777.97      6828605.74
#Sta/Elev= 30
  4692.1  402.22  4702.5  402.40  4716.3  401.67  4729.7  401.79  4743.1  401.26
  4743.3  400.76  4746.8  400.76  4747.1  401.26  4751.5  401.64  4760.5  401.87
  4775.0  401.65  4781.8  403.07  4787.6  403.20  4797.2  401.92  4861.0  401.57
  4913.1  401.90  4927.7  401.67  4934.4  401.97  4949.8  402.07  4976.9  401.71
  5028.2  401.53  5043.0  401.92  5071.8  401.81  5143.7  402.65  5149.8  402.49
  5179.3  402.72  5185.4  402.44  5194.0  402.72  5200.2  402.50  5217.0  402.67
#Mann=3,-1,0
  4692.1    0.05       0  4743.1    0.05       0  4747.1    0.05       0
Bank Sta=4743.1,4747.1
Exp/Cntr=0.3,0.1

Type RM Length L Ch R = 1,3545,137,137,137
BEGIN DESCRIPTION:
Twin Creek2143545.48
END DESCRIPTION:
XS GIS Cut Line= 3
      2731345.59      6828654.18      2731176.36      6828585.26
      2730846.69      6828403.47
#Sta/Elev= 30
  4817.4  398.65  4860.1  399.37  4924.9  398.46  4948.5  398.84  4967.2  397.52
  4972.6  398.53  4989.7  398.07  4996.6  397.12  5056.3  397.69  5062.0  397.13
  5078.1  397.84  5099.9  397.82  5105.6  397.12  5121.6  397.55  5141.4  396.64
  5141.7  396.14  5145.2  396.14  5145.4  396.64  5165.2  398.28  5187.0  397.99
  5194.7  398.72  5230.5  398.04  5246.6  398.85  5252.3  398.27  5262.6  399.47
  5268.4  398.70  5274.6  399.71  5284.4  400.11  5306.2  399.27  5376.6  400.01
#Mann=3,-1,0
  4817.4    0.05       0  5141.4    0.05       0  5145.4    0.05       0
Bank Sta=5141.4,5145.4
Exp/Cntr=0.3,0.1

Type RM Length L Ch R = 1,3408,128,128,128
BEGIN DESCRIPTION:
Mapping XS ba38fc31
END DESCRIPTION:
XS GIS Cut Line= 3
      2731258.64      6828503.85      2731125.10      6828463.47
      2731002.73      6828418.17
#Sta/Elev= 27
  4861.4  398.98  4889.4  398.75  4922.3  398.30  4937.3  398.34  4947.7  398.20
  4955.3  398.00  4960.5  398.12  4968.6  397.31  4979.1  396.53  4988.2  396.28
  4993.5  396.34  4997.8  395.93  5010.6  395.86  5029.9  395.48  5030.2  394.98
  5033.7  394.98  5033.9  395.48  5042.6  395.54  5049.6  395.94  5054.9  396.04
  5063.9  396.69  5080.0  397.05  5085.3  396.76  5095.9  396.76  5110.4  396.59
  5127.0  398.27  5131.4  398.27
#Mann=3,-1,0
  4861.4    0.05       0  5029.9    0.05       0  5033.9    0.05       0
Bank Sta=5029.9,5033.9
Exp/Cntr=0.3,0.1

Type RM Length L Ch R = 1,3280,147,147,147
BEGIN DESCRIPTION:
Twin Creek2143279.53
END DESCRIPTION:
XS GIS Cut Line= 3
      2731260.61      6828359.15      2731077.13      6828351.59
      2730870.35      6828345.64
#Sta/Elev= 30
  4816.7  397.58  4831.3  397.66  4894.8  396.94  4911.4  396.98  4921.4  396.89
  4931.4  395.87  4941.4  395.44  4971.4  393.84  4981.5  392.97  4989.5  392.96
  4989.7  392.46  4993.2  392.46  4993.5  392.96  4998.4  394.43  5003.4  394.43
  5011.5  395.56  5031.5  397.13  5041.5  397.55  5061.5  397.90  5071.5  397.84
  5081.5  397.14  5101.5  397.26  5111.5  397.17  5121.5  397.30  5161.5  398.26
  5171.5  398.41  5181.5  399.18  5190.7  400.25  5201.6  400.36  5207.2  399.77
#Mann=3,-1,0
  4816.7    0.05       0  4989.5    0.05       0  4993.5    0.05       0
Bank Sta=4989.5,4993.5
Exp/Cntr=0.3,0.1

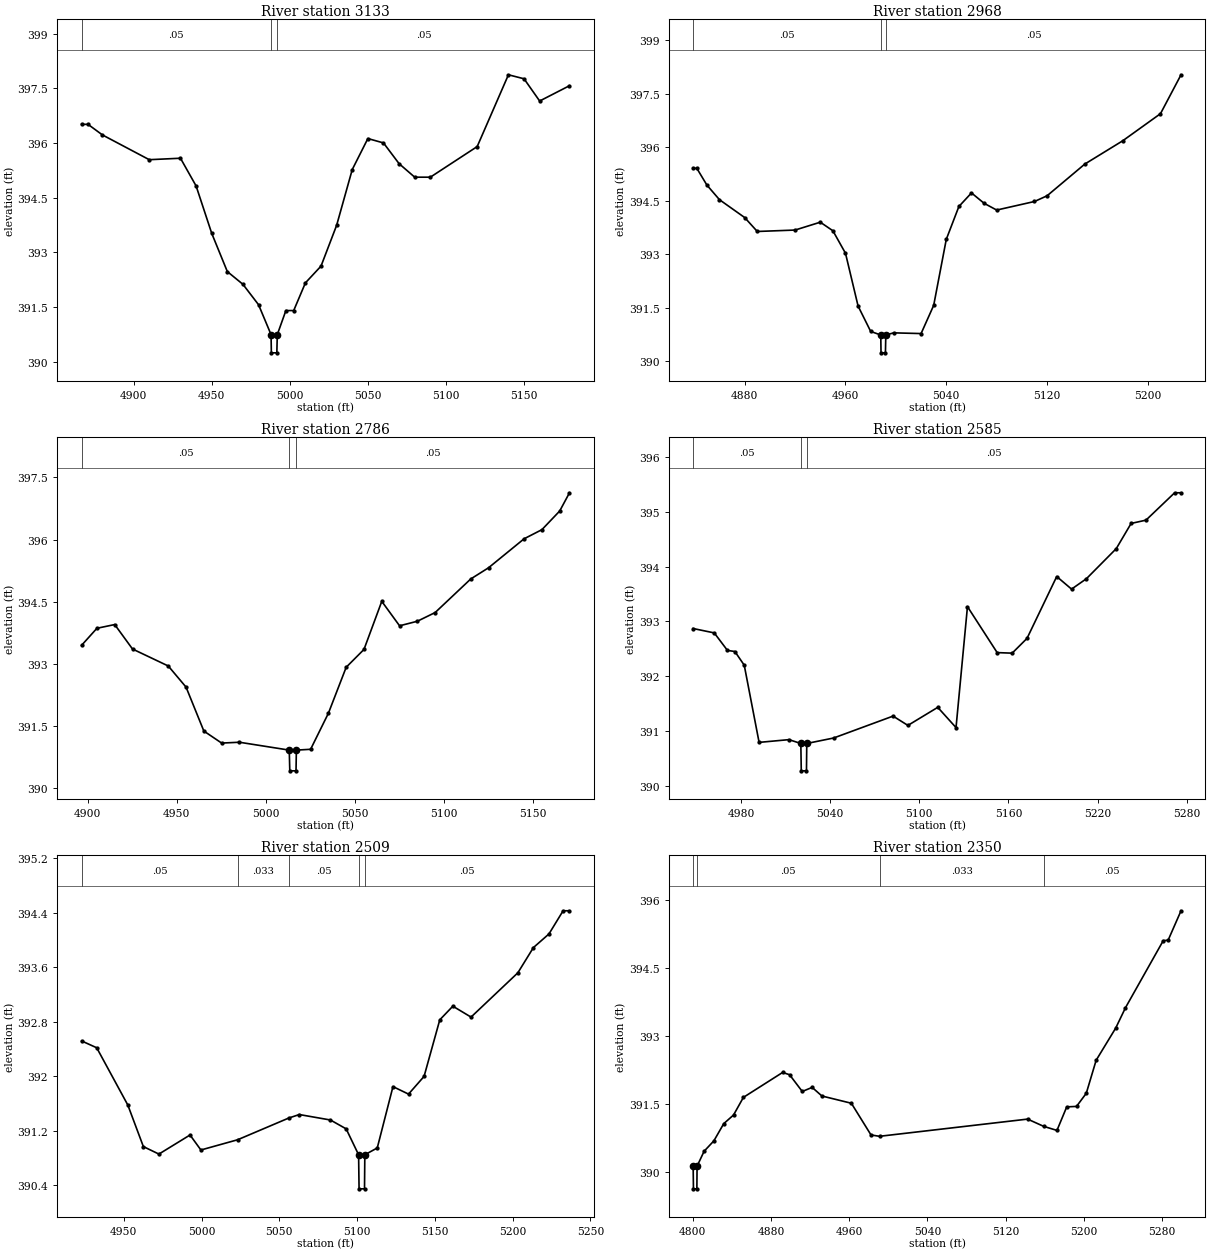
Type RM Length L Ch R = 1,3133,165,165,165
BEGIN DESCRIPTION:
Twin Creek2143133.26
END DESCRIPTION:
XS GIS Cut Line= 3
      2731209.25      6828202.08      2731075.98      6828205.44
      2730896.94      6828201.23
#Sta/Elev= 30
  4866.7  396.51  4870.8  396.51  4880.0  396.22  4910.0  395.54  4930.0  395.58
  4940.0  394.82  4950.0  393.52  4960.0  392.47  4970.0  392.12  4980.0  391.56
  4988.0  390.74  4988.2  390.24  4991.7  390.24  4992.0  390.74  4997.5  391.40
  5002.5  391.40  5010.0  392.16  5020.0  392.62  5030.0  393.74  5040.0  395.27
  5050.0  396.12  5060.0  396.00  5070.0  395.43  5080.0  395.06  5090.0  395.06
  5120.0  395.90  5140.0  397.87  5150.0  397.76  5160.0  397.15  5179.1  397.57
#Mann=3,-1,0
  4866.7    0.05       0  4988.0    0.05       0  4992.0    0.05       0
Bank Sta=4988,4992
Exp/Cntr=0.3,0.1

Type RM Length L Ch R = 1,2968,182,182,182
BEGIN DESCRIPTION:
Twin Creek2142967.65
END DESCRIPTION:
XS GIS Cut Line= 3
      2731236.85      6828042.54      2731074.36      6828039.80
      2730849.68      6828038.82
#Sta/Elev= 30
  4839.1  395.41  4842.0  395.41  4850.0  394.94  4860.0  394.53  4880.0  394.03
  4890.0  393.64  4920.0  393.68  4940.0  393.90  4950.0  393.66  4960.0  393.03
  4970.0  391.55  4980.0  390.84  4988.0  390.74  4988.2  390.24  4991.7  390.24
  4992.0  390.74  4998.3  390.80  5020.0  390.78  5030.0  391.57  5040.0  393.42
  5050.0  394.34  5060.0  394.72  5070.0  394.43  5080.0  394.24  5110.0  394.48
  5120.0  394.64  5150.0  395.53  5180.0  396.18  5210.0  396.94  5226.3  398.03
#Mann=3,-1,0
  4839.1    0.05       0  4988.0    0.05       0  4992.0    0.05       0
Bank Sta=4988,4992
Exp/Cntr=0.3,0.1

Type RM Length L Ch R = 1,2786,201,201,201
BEGIN DESCRIPTION:
Twin Creek2142786.02
END DESCRIPTION:
XS GIS Cut Line= 3
      2731184.62      6827863.76      2731079.75      6827858.95
      2730910.55      6827856.27
#Sta/Elev= 27
  4896.5  393.45  4905.1  393.86  4915.1  393.95  4925.1  393.36  4945.2  392.95
  4955.2  392.44  4965.2  391.38  4975.2  391.09  4985.2  391.11  5013.2  390.92
  5013.5  390.42  5017.0  390.42  5017.2  390.92  5025.2  390.94  5035.2  391.81
  5045.2  392.92  5055.2  393.35  5065.2  394.51  5075.2  393.92  5085.2  394.03
  5095.2  394.24  5115.2  395.05  5125.2  395.32  5145.2  396.02  5155.2  396.24
  5165.2  396.69  5170.7  397.13
#Mann=3,-1,0
  4896.5    0.05       0  5013.2    0.05       0  5017.2    0.05       0
Bank Sta=5013.2,5017.2
Exp/Cntr=0.3,0.1

Type RM Length L Ch R = 1,2585,76,76,76
BEGIN DESCRIPTION:
Twin Creek2142584.91
END DESCRIPTION:
XS GIS Cut Line= 3
      2731270.12      6827719.17      2731216.56      6827712.81
      2730942.44      6827697.27
#Sta/Elev= 28
  4947.7  392.87  4961.9  392.79  4970.8  392.47  4975.8  392.45  4982.1  392.20
  4992.1  390.79  5012.2  390.84  5020.2  390.77  5020.5  390.27  5024.0  390.27
  5024.2  390.77  5042.3  390.87  5082.3  391.27  5092.3  391.10  5112.4  391.43
  5124.7  391.06  5132.4  393.27  5152.4  392.43  5162.5  392.42  5172.5  392.69
  5192.5  393.82  5202.5  393.59  5212.5  393.78  5232.6  394.33  5242.6  394.79
  5252.6  394.85  5271.9  395.35  5276.2  395.35
#Mann=3,-1,0
  4947.7    0.05       0  5020.2    0.05       0  5024.2    0.05       0
Bank Sta=5020.2,5024.2
Exp/Cntr=0.3,0.1

Type RM Length L Ch R = 1,2509,159,159,159
BEGIN DESCRIPTION:
Twin Creek2142508.56
END DESCRIPTION:
XS GIS Cut Line= 3
      2731265.74      6827650.21      2731187.18      6827649.77
      2730952.88      6827629.97
#Sta/Elev= 28
  4922.9  392.52  4932.6  392.42  4952.6  391.58  4962.6  390.97  4972.6  390.86
  4992.6  391.14  4999.6  390.92  5023.2  391.07  5056.2  391.39  5062.9  391.44
  5082.9  391.36  5093.0  391.23  5101.0  390.85  5101.3  390.35  5104.8  390.35
  5105.0  390.85  5113.0  390.95  5123.1  391.85  5133.1  391.74  5143.1  392.00
  5153.2  392.83  5161.6  393.03  5173.3  392.87  5203.4  393.52  5213.4  393.89
  5223.4  394.09  5232.5  394.43  5236.6  394.43
#Mann=5,-1,0
  4922.9    0.05       0  5023.2   0.033       0  5056.2    0.05       0
  5101.0    0.05       0  5105.0    0.05       0
Bank Sta=5101,5105
Exp/Cntr=0.3,0.1

Type RM Length L Ch R = 1,2350,157,157,157
BEGIN DESCRIPTION:
Twin Creek2142349.77
END DESCRIPTION:
XS GIS Cut Line= 3
      2731417.13      6827486.59      2731218.13      6827505.29
      2730919.22      6827516.55
#Sta/Elev= 29
  4800.5  390.12  4800.8  389.62  4804.3  389.62  4804.5  390.12  4811.7  390.45
  4821.7  390.68  4831.8  391.06  4841.8  391.25  4851.9  391.64  4892.0  392.19
  4899.1  392.14  4912.1  391.77  4922.2  391.86  4932.2  391.67  4962.3  391.51
  4982.4  390.81  4991.1  390.78  5142.6  391.16  5159.0  391.00  5172.6  390.91
  5182.6  391.43  5192.6  391.44  5202.6  391.73  5212.7  392.46  5232.7  393.17
  5242.7  393.62  5281.3  395.10  5286.3  395.11  5299.5  395.76
#Mann=4,-1,0
  4800.5   0.033       0  4804.5    0.05       0  4991.1   0.033       0
  5159.0    0.05       0
Bank Sta=4800.5,4804.5
Exp/Cntr=0.3,0.1

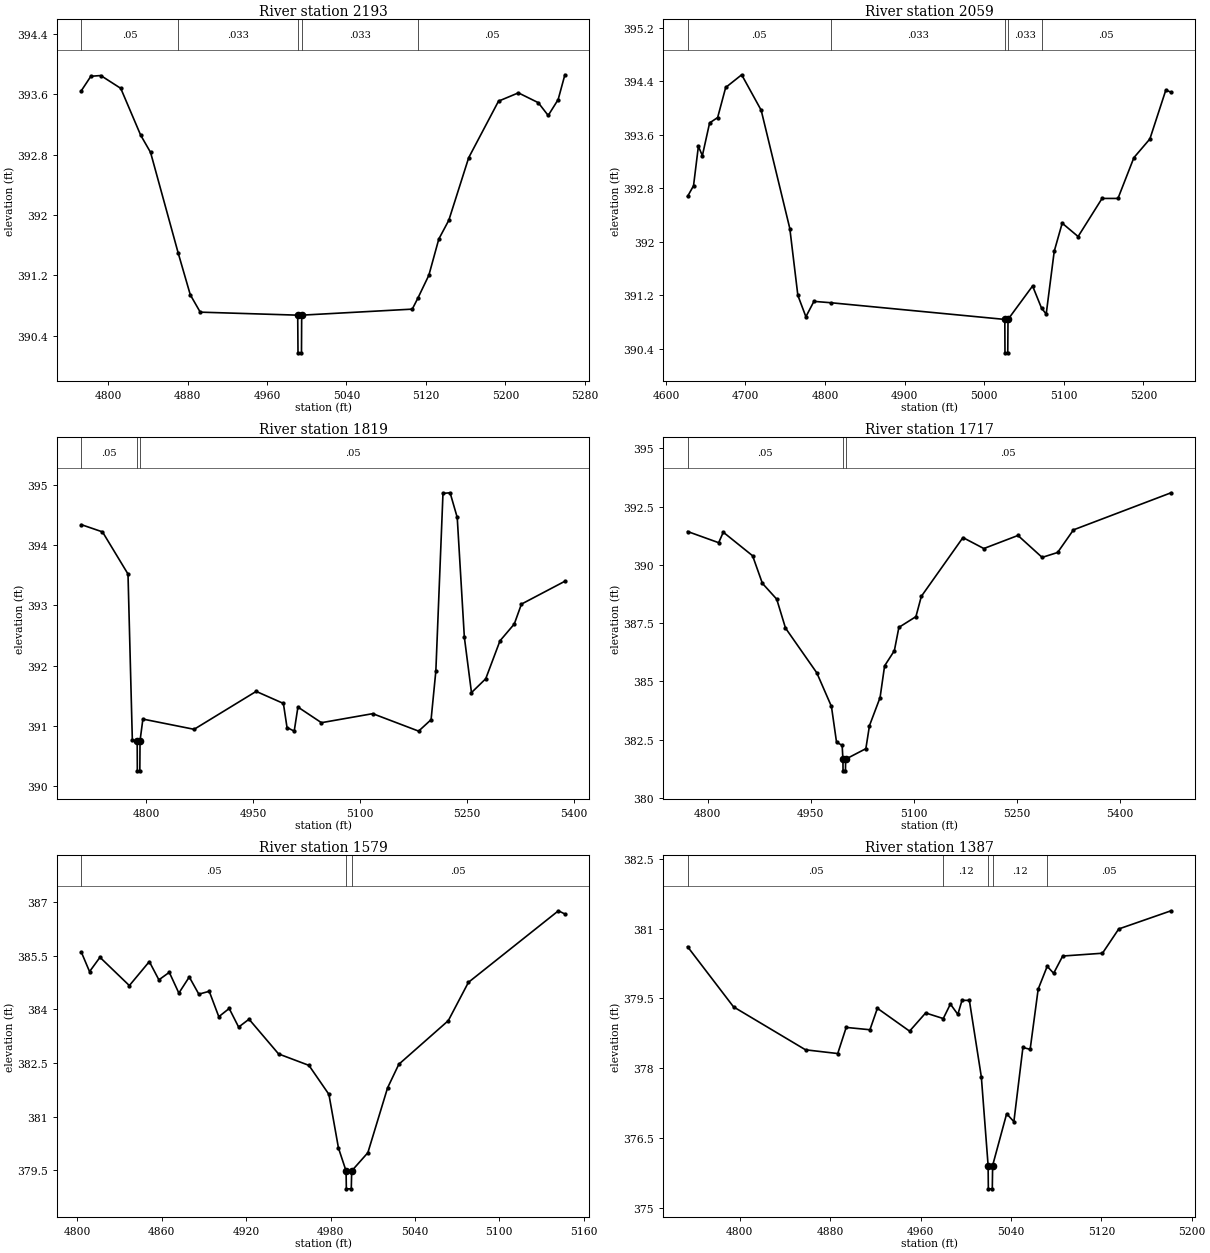
Type RM Length L Ch R = 1,2193,134,134,134
BEGIN DESCRIPTION:
Mapping XS fd13ca9d
END DESCRIPTION:
XS GIS Cut Line= 3
      2731335.53      6827403.08      2731106.47      6827393.80
      2730849.18      6827399.35
#Sta/Elev= 25
  4773.2  393.65  4782.7  393.84  4792.7  393.85  4812.8  393.68  4832.8  393.06
  4842.8  392.83  4870.5  391.50  4882.8  390.94  4892.8  390.71  4990.9  390.67
  4991.2  390.17  4994.7  390.17  4994.9  390.67  5106.2  390.75  5112.0  390.90
  5122.9  391.20  5132.9  391.68  5143.0  391.93  5163.0  392.76  5193.0  393.51
  5213.0  393.62  5233.0  393.49  5243.0  393.32  5253.0  393.53  5259.8  393.86
#Mann=5,-1,0
  4773.2    0.05       0  4870.5   0.033       0  4990.9   0.033       0
  4994.9   0.033       0  5112.0    0.05       0
Bank Sta=4990.9,4994.9
Exp/Cntr=0.3,0.1

Type RM Length L Ch R = 1,2059,240,240,240
BEGIN DESCRIPTION:
Twin Creek2142059.48
END DESCRIPTION:
XS GIS Cut Line= 3
      2731383.46      6827347.90      2731009.88      6827299.07
      2730779.40      6827286.12
#Sta/Elev= 30
  4627.2  392.68  4634.7  392.84  4640.8  393.43  4645.8  393.29  4654.9  393.78
  4665.0  393.86  4675.1  394.31  4695.2  394.50  4719.7  393.97  4755.7  392.20
  4765.8  391.20  4775.9  390.88  4786.0  391.11  4806.9  391.09  5025.9  390.84
  5026.1  390.34  5029.6  390.34  5029.9  390.84  5060.8  391.34  5072.0  391.01
  5077.9  390.92  5088.0  391.86  5098.0  392.28  5118.0  392.08  5148.1  392.65
  5168.1  392.65  5188.1  393.26  5208.2  393.54  5228.2  394.27  5234.8  394.24
#Mann=5,-1,0
  4627.2    0.05       0  4806.9   0.033       0  5025.9   0.033       0
  5029.9   0.033       0  5072.0    0.05       0
Bank Sta=5025.9,5029.9
Exp/Cntr=0.3,0.1

Type RM Length L Ch R = 1,1819,102,102,102
BEGIN DESCRIPTION:
Twin Creek2141818.87
END DESCRIPTION:
XS GIS Cut Line= 6
      2731320.00      6827317.17      2731240.95      6827202.76
      2731111.48      6827122.87      2731051.35      6827140.94
      2730962.61      6827242.76      2730775.04      6827251.33
#Sta/Elev= 30
  4709.2  394.34  4738.8  394.22  4774.6  393.52  4780.7  390.76  4787.5  390.75
  4787.7  390.25  4791.2  390.25  4791.5  390.75  4795.5  391.11  4867.4  390.94
  4954.5  391.57  4992.7  391.37  4997.8  390.97  5007.9  390.91  5013.1  391.31
  5046.1  391.05  5118.1  391.20  5182.5  390.91  5200.0  391.10  5206.7  391.91
  5216.7  394.86  5226.7  394.87  5236.7  394.46  5246.7  392.47  5256.7  391.55
  5276.7  391.78  5296.7  392.41  5316.8  392.69  5326.8  393.02  5387.8  393.40
#Mann=3,-1,0
  4709.2    0.05       0  4787.5    0.05       0  4791.5    0.05       0
Bank Sta=4787.5,4791.5
Exp/Cntr=0.3,0.1

Type RM Length L Ch R = 1,1717,138,138,138
BEGIN DESCRIPTION:
Twin Creek2141717.03
END DESCRIPTION:
XS GIS Cut Line= 6
      2731343.05      6827197.61      2731247.32      6827088.18
      2731118.26      6827029.94      2731010.00      6827063.12
      2730909.66      6827189.56      2730770.27      6827211.04
#Sta/Elev= 30
  4770.6  391.43  4815.9  390.95  4822.6  391.40  4865.3  390.39  4879.5  389.21
  4900.4  388.53  4913.2  387.29  4958.8  385.37  4980.1  383.93  4987.5  382.40
  4995.7  382.26  4996.8  381.67  4997.0  381.17  5000.5  381.17  5000.8  381.67
  5030.2  382.12  5035.5  383.11  5050.9  384.31  5057.5  385.67  5071.7  386.32
  5078.3  387.32  5103.1  387.78  5111.0  388.65  5171.6  391.17  5202.0  390.70
  5251.7  391.26  5286.9  390.32  5309.4  390.53  5332.5  391.50  5474.6  393.09
#Mann=3,-1,0
  4770.6    0.05       0  4996.8    0.05       0  5000.8    0.05       0
Bank Sta=4996.8,5000.8
Exp/Cntr=0.3,0.1

Type RM Length L Ch R = 1,1579,192,192,192
BEGIN DESCRIPTION:
Twin Creek2141579.03
END DESCRIPTION:
XS GIS Cut Line= 3
      2731396.36      6827068.89      2731250.73      6826935.61
      2731137.12      6826843.29
#Sta/Elev= 30
  4802.8  385.59  4808.6  385.05  4816.0  385.45  4836.9  384.66  4851.1  385.33
  4857.9  384.82  4865.3  385.03  4872.1  384.45  4879.5  384.90  4886.3  384.42
  4893.7  384.50  4900.5  383.79  4907.9  384.02  4914.6  383.50  4922.0  383.72
  4943.0  382.75  4964.6  382.43  4978.8  381.62  4985.6  380.12  4991.0  379.48
  4991.2  378.98  4994.7  378.98  4995.0  379.48  5006.5  379.99  5020.5  381.80
  5028.5  382.46  5063.7  383.68  5078.0  384.75  5142.0  386.75  5146.6  386.66
#Mann=3,-1,0
  4802.8    0.05       0  4991.0    0.05       0  4995.0    0.05       0
Bank Sta=4991,4995
Exp/Cntr=0.3,0.1

Type RM Length L Ch R = 1,1387,210,210,210
BEGIN DESCRIPTION:
Twin Creek2141387.35
END DESCRIPTION:
XS GIS Cut Line= 3
      2731562.12      6826972.38      2731376.00      6826811.27
      2731234.27      6826697.53
#Sta/Elev= 30
  4753.8  380.61  4794.5  379.32  4858.2  378.40  4886.7  378.32  4894.2  378.88
  4915.2  378.83  4921.8  379.29  4950.3  378.80  4964.5  379.19  4980.1  379.07
  4986.4  379.38  4993.0  379.16  4996.7  379.46  5003.2  379.46  5013.8  377.82
  5019.8  375.92  5020.0  375.42  5023.5  375.42  5023.8  375.92  5036.2  377.03
  5042.6  376.86  5050.6  378.45  5057.0  378.41  5064.1  379.70  5072.1  380.19
  5077.8  380.04  5085.8  380.41  5121.0  380.47  5135.4  380.99  5181.7  381.38
#Mann=5,-1,0
  4753.8    0.05       0  4980.1    0.12       0  5019.8    0.07       0
  5023.8    0.12       0  5072.1    0.05       0
Bank Sta=5019.8,5023.8
Exp/Cntr=0.3,0.1

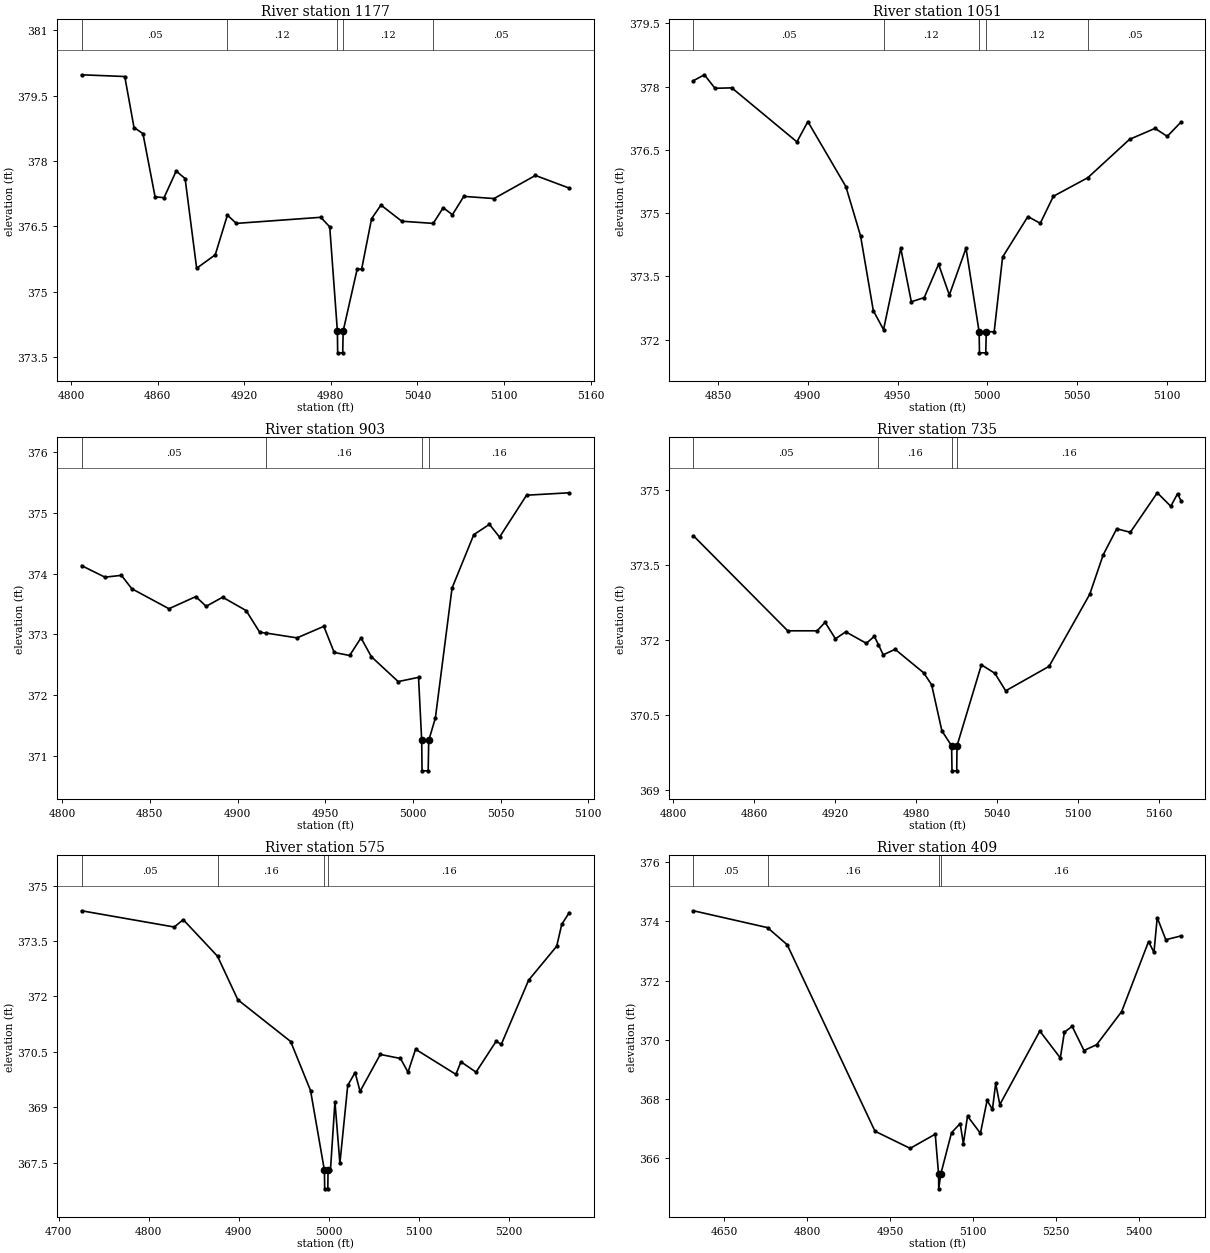
Type RM Length L Ch R = 1,1177,126,126,126
BEGIN DESCRIPTION:
Twin Creek2141177.15
END DESCRIPTION:
XS GIS Cut Line= 3
      2731580.07      6826757.61      2731424.07      6826642.25
      2731312.69      6826551.33
#Sta/Elev= 30
  4807.4  379.98  4837.3  379.94  4843.7  378.77  4849.9  378.63  4858.3  377.18
  4864.5  377.16  4872.9  377.77  4879.1  377.60  4887.1  375.54  4900.0  375.85
  4908.4  376.76  4914.6  376.57  4973.1  376.71  4979.3  376.49  4984.6  374.10
  4984.8  373.60  4988.3  373.60  4988.6  374.10  4998.3  375.52  5001.4  375.52
  5008.3  376.68  5014.8  376.99  5029.2  376.62  5051.0  376.57  5057.9  376.93
  5064.3  376.77  5072.2  377.19  5093.1  377.14  5121.8  377.67  5145.2  377.38
#Mann=5,-1,0
  4807.4    0.05       0  4908.4    0.12       0  4984.6    0.07       0
  4988.6    0.12       0  5051.0    0.05       0
Bank Sta=4984.6,4988.6
Exp/Cntr=0.3,0.1

Type RM Length L Ch R = 1,1051,148,148,148
BEGIN DESCRIPTION:
Twin Creek2141050.86
END DESCRIPTION:
XS GIS Cut Line= 3
      2731614.82      6826620.12      2731475.80      6826532.42
      2731397.09      6826459.16
#Sta/Elev= 30
  4836.2  378.14  4842.3  378.28  4848.2  377.96  4857.6  377.97  4893.9  376.69
  4900.0  377.17  4921.2  375.63  4929.4  374.46  4936.5  372.69  4942.2  372.24
  4951.8  374.17  4957.7  372.90  4964.9  373.00  4972.9  373.79  4978.9  373.06
  4988.2  374.17  4995.5  372.19  4995.7  371.69  4999.2  371.69  4999.5  372.19
  5003.9  372.19  5008.6  373.96  5022.7  374.92  5029.6  374.76  5036.9  375.40
  5056.1  375.84  5079.4  376.75  5093.6  377.01  5100.4  376.82  5108.1  377.16
#Mann=5,-1,0
  4836.2    0.05       0  4942.2    0.12       0  4995.5    0.07       0
  4999.5    0.12       0  5056.1    0.05       0
Bank Sta=4995.5,4999.5
Exp/Cntr=0.3,0.1

Type RM Length L Ch R = 1,903,168,168,168
BEGIN DESCRIPTION:
Twin Creek214902.87
END DESCRIPTION:
XS GIS Cut Line= 3
      2731655.34      6826491.19      2731494.58      6826389.99
      2731419.80      6826343.53
#Sta/Elev= 30
  4811.1  374.13  4824.4  373.94  4833.8  373.97  4839.7  373.75  4860.9  373.42
  4876.2  373.62  4882.1  373.46  4891.5  373.61  4904.9  373.39  4912.7  373.03
  4916.2  373.02  4933.9  372.94  4949.2  373.13  4955.1  372.70  4963.9  372.65
  4970.4  372.94  4976.3  372.63  4991.6  372.22  5003.2  372.29  5005.0  371.25
  5005.2  370.75  5008.7  370.75  5009.0  371.25  5012.8  371.62  5022.3  373.76
  5034.7  374.64  5043.6  374.81  5049.4  374.60  5064.8  375.29  5089.1  375.33
#Mann=4,-1,0
  4811.1    0.05       0  4916.2    0.16       0  5005.0    0.07       0
  5009.0    0.16       0
Bank Sta=5005,5009
Exp/Cntr=0.3,0.1

Type RM Length L Ch R = 1,735,160,160,160
BEGIN DESCRIPTION:
Twin Creek214735.35
END DESCRIPTION:
XS GIS Cut Line= 3
      2731701.71      6826440.30      2731602.94      6826282.14
      2731428.48      6826296.22
#Sta/Elev= 30
  4814.9  374.08  4884.8  372.18  4906.6  372.18  4912.5  372.35  4920.2  372.02
  4927.8  372.16  4943.1  371.93  4949.0  372.07  4952.1  371.90  4955.6  371.70
  4964.4  371.81  4985.6  371.34  4991.5  371.10  4999.1  370.18  5006.3  369.88
  5006.6  369.38  5010.1  369.38  5010.3  369.88  5028.4  371.50  5038.4  371.33
  5046.4  370.98  5078.6  371.47  5108.7  372.91  5118.7  373.70  5128.7  374.22
  5138.8  374.15  5158.8  374.94  5168.8  374.67  5173.8  374.92  5176.4  374.78
#Mann=4,-1,0
  4814.9    0.05       0  4952.1    0.16       0  5006.3    0.07       0
  5010.3    0.16       0
Bank Sta=5006.3,5010.3
Exp/Cntr=0.3,0.1

Type RM Length L Ch R = 1,575,166,166,166
BEGIN DESCRIPTION:
Twin Creek214575.15
END DESCRIPTION:
XS GIS Cut Line= 3
      2731725.30      6826422.74      2731685.38      6826151.60
      2731445.56      6826270.65
#Sta/Elev= 30
  4725.5  374.32  4828.5  373.88  4838.4  374.08  4876.5  373.09  4899.1  371.91
  4957.8  370.78  4979.9  369.45  4995.3  367.29  4995.6  366.79  4999.1  366.79
  4999.3  367.29  5002.0  367.29  5007.0  369.15  5012.5  367.48  5021.2  369.59
  5029.4  369.94  5034.9  369.43  5057.4  370.43  5079.8  370.32  5088.2  369.95
  5096.6  370.57  5141.4  369.89  5147.0  370.23  5163.8  369.95  5186.2  370.79
  5191.8  370.70  5222.2  372.44  5253.4  373.36  5259.0  373.95  5267.3  374.27
#Mann=4,-1,0
  4725.5    0.05       0  4876.5    0.16       0  4995.3    0.07       0
  4999.3    0.16       0
Bank Sta=4995.3,4999.3
Exp/Cntr=0.3,0.1

Type RM Length L Ch R = 1,409,0,0,0
BEGIN DESCRIPTION:
Twin Creek214408.685
END DESCRIPTION:
XS GIS Cut Line= 3
      2731748.42      6826435.81      2731803.12      6826034.52
      2731395.31      6826278.85
#Sta/Elev= 30
  4595.0  374.36  4728.8  373.79  4764.3  373.21  4922.8  366.90  4986.3  366.32
  5031.6  366.80  5037.6  365.45  5037.9  364.95  5041.6  365.45  5061.0  366.85
  5076.6  367.16  5082.4  366.48  5089.9  367.41  5113.2  366.83  5125.2  367.94
  5134.9  367.64  5140.7  368.52  5148.2  367.80  5220.4  370.29  5257.4  369.38
  5264.8  370.25  5278.8  370.45  5300.2  369.63  5323.1  369.83  5368.2  370.95
  5416.8  373.32  5426.5  372.95  5432.4  374.13  5447.9  373.38  5475.4  373.51
#Mann=4,-1,0
  4595.0    0.05       0  4728.8    0.16       0  5037.6    0.07       0
  5041.6    0.16       0
Bank Sta=5037.6,5041.6
Exp/Cntr=0.3,0.1

Chan Stop Cuts=-1