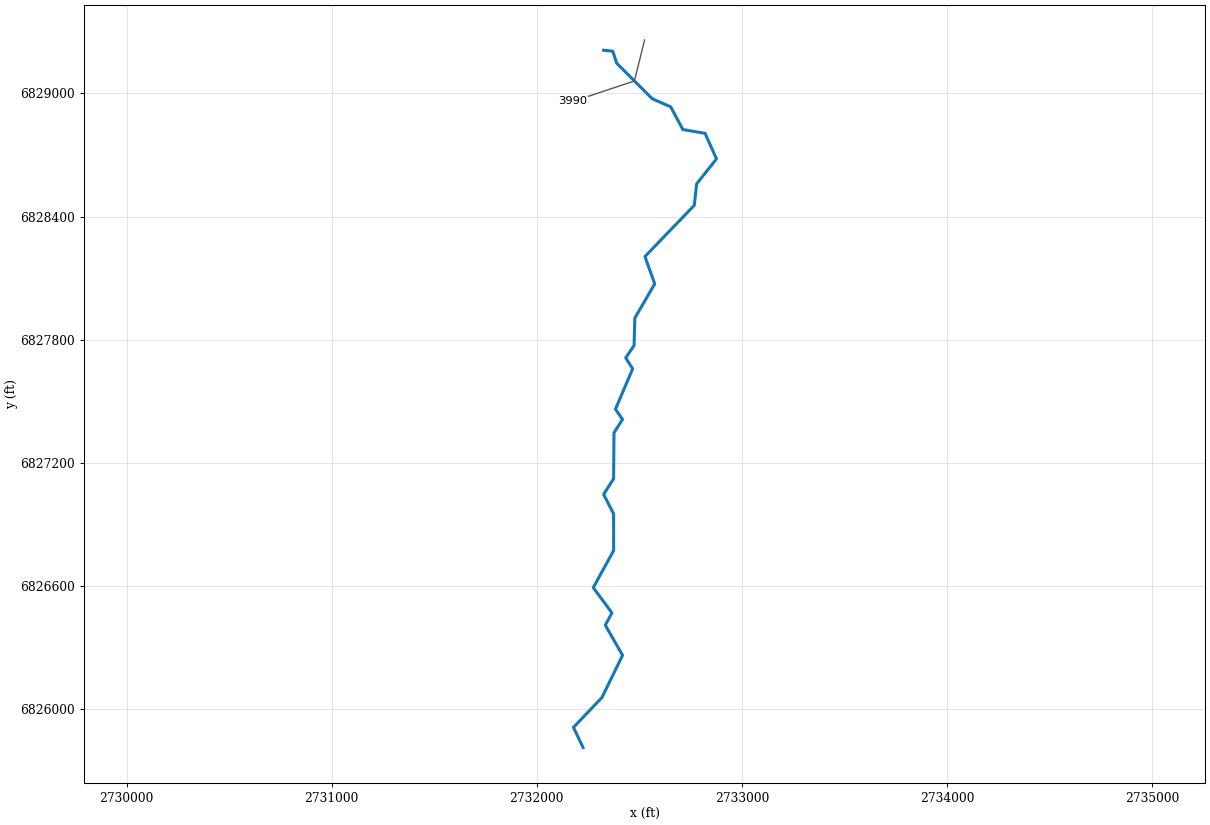
--- Twin Creek216.prj (project) ---

Proj Title=Twin Creek216 Base Level Engineering
Current Plan=p01
Default Exp/Contr=0.3,0.1
English Units
Geom File=g01
Flow File=f01
Plan File=p01
BEGIN DESCRIPTION:
Twin Creek216
END DESCRIPTION:

--- Twin Creek216.p01 (plan) ---

Plan Title=Multiple Run
Short Identifier=Multiple
Geom File=g01
Flow File=f01
Subcritical Flow
K Sum by GR= 0
Std Step Tol= 0.01
Critical Tol= 0.01
Num of Std Step Trials= 20
Max Error Tol= 0.3
Flow Tol Ratio= 0.001
Split Flow NTrial= 30
Split Flow Tol= 0.02
Split Flow Ratio= 0.02
Log Output Level= 0
Friction Slope Method= 1
Unsteady Friction Slope Method= 2
Unsteady Bridges Friction Slope Method= 1
Parabolic Critical Depth
Global Vel Dist=  1 , 1 , 1
Global Log Level= 0
CheckData=True
Encroach Param= -1, 0, 0, 0
BEGIN DESCRIPTION:
Multiple Run
END DESCRIPTION:

--- Twin Creek216.f01 (steady flow) ---

Flow Title=Multiple
Number of Profiles=7
Profile Names=10-year,25-year,50-year,1pct_min,100-year,1pct_plu,500-year
River Rch & RM= Twin Creek216,Reach-1,3990
     272     345     400     231     462     922     613
Boundary for River Rch & Prof#=Twin Creek216,Reach-1,1
Up Type=0
Dn Type=3
Dn Slope=0.005
Boundary for River Rch & Prof#=Twin Creek216,Reach-1,2
Up Type=0
Dn Type=3
Dn Slope=0.005
Boundary for River Rch & Prof#=Twin Creek216,Reach-1,3
Up Type=0
Dn Type=3
Dn Slope=0.005
Boundary for River Rch & Prof#=Twin Creek216,Reach-1,4
Up Type=0
Dn Type=3
Dn Slope=0.005
Boundary for River Rch & Prof#=Twin Creek216,Reach-1,5
Up Type=0
Dn Type=3
Dn Slope=0.005
Boundary for River Rch & Prof#=Twin Creek216,Reach-1,6
Up Type=0
Dn Type=3
Dn Slope=0.005
Boundary for River Rch & Prof#=Twin Creek216,Reach-1,7
Up Type=0
Dn Type=3
Dn Slope=0.005

--- Twin Creek216.g01 (geometry) ---

Geom Title=Existing Conditions

River Reach=Twin Creek216,Reach-1
Reach XY= 30
      2732326.00      6829211.00      2732370.67      6829206.08
      2732389.60      6829147.92      2732562.80      6828974.64
      2732653.14      6828934.83      2732712.38      6828824.28
      2732820.56      6828805.75      2732876.40      6828681.14
      2732779.63      6828559.50      2732768.14      6828454.83
      2732527.62      6828204.97      2732575.25      6828071.69
      2732478.25      6827905.07      2732474.61      6827771.44
      2732433.79      6827710.90      2732467.72      6827657.78
      2732383.79      6827460.90      2732418.21      6827411.10
      2732376.65      6827345.84      2732374.76      6827121.50
      2732326.09      6827045.61      2732374.76      6826950.50
      2732374.80      6826771.50      2732275.63      6826590.80
      2732366.68      6826467.66      2732334.25      6826407.77
      2732418.50      6826261.00      2732317.86      6826054.94
      2732179.08      6825909.42      2732226.00      6825811.00

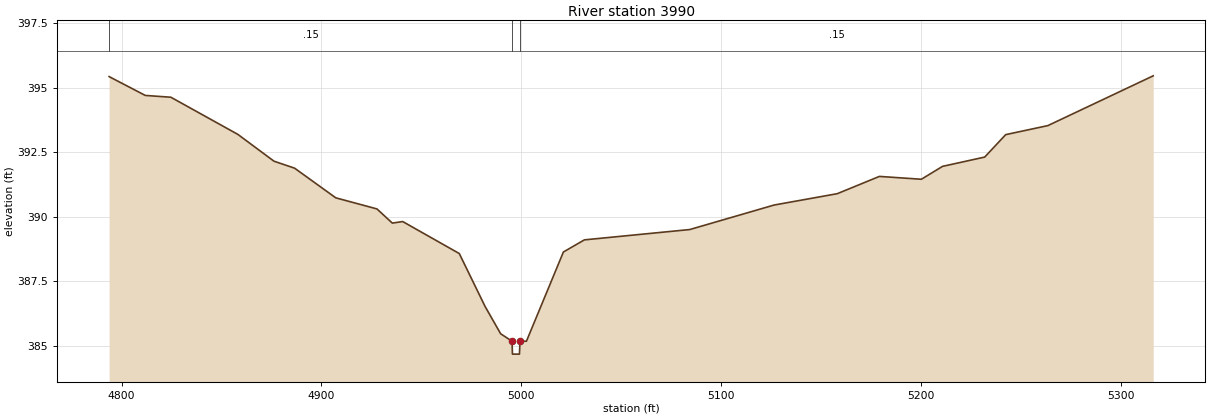
Type RM Length L Ch R = 1,3990,0,0,0
BEGIN DESCRIPTION:
Twin Creek216 1.0
END DESCRIPTION:
XS GIS Cut Line= 3
      2732526.00      6829261.01      2732476.00      6829061.00
      2732176.00      6828961.00
#Sta/Elev= 30
  4793.8  395.43  4811.9  394.70  4824.7  394.63  4858.2  393.19  4876.3  392.15
  4886.6  391.88  4907.2  390.73  4927.8  390.30  4935.5  389.75  4940.7  389.81
  4969.0  388.57  4981.9  386.52  4989.7  385.46  4995.4  385.17  4995.6  384.67
  4999.1  384.67  4999.4  385.17  5002.6  385.17  5021.1  388.63  5031.6  389.10
  5084.3  389.50  5126.5  390.45  5158.1  390.89  5179.2  391.56  5200.2  391.45
  5210.8  391.95  5231.9  392.31  5242.4  393.18  5263.5  393.53  5316.2  395.46
#Mann=3,-1,0
  4793.8    0.15       0  4995.4    0.05       0  4999.4    0.15       0
Bank Sta=4995.4,4999.4
Exp/Cntr=0.3,0.1

Chan Stop Cuts=-1