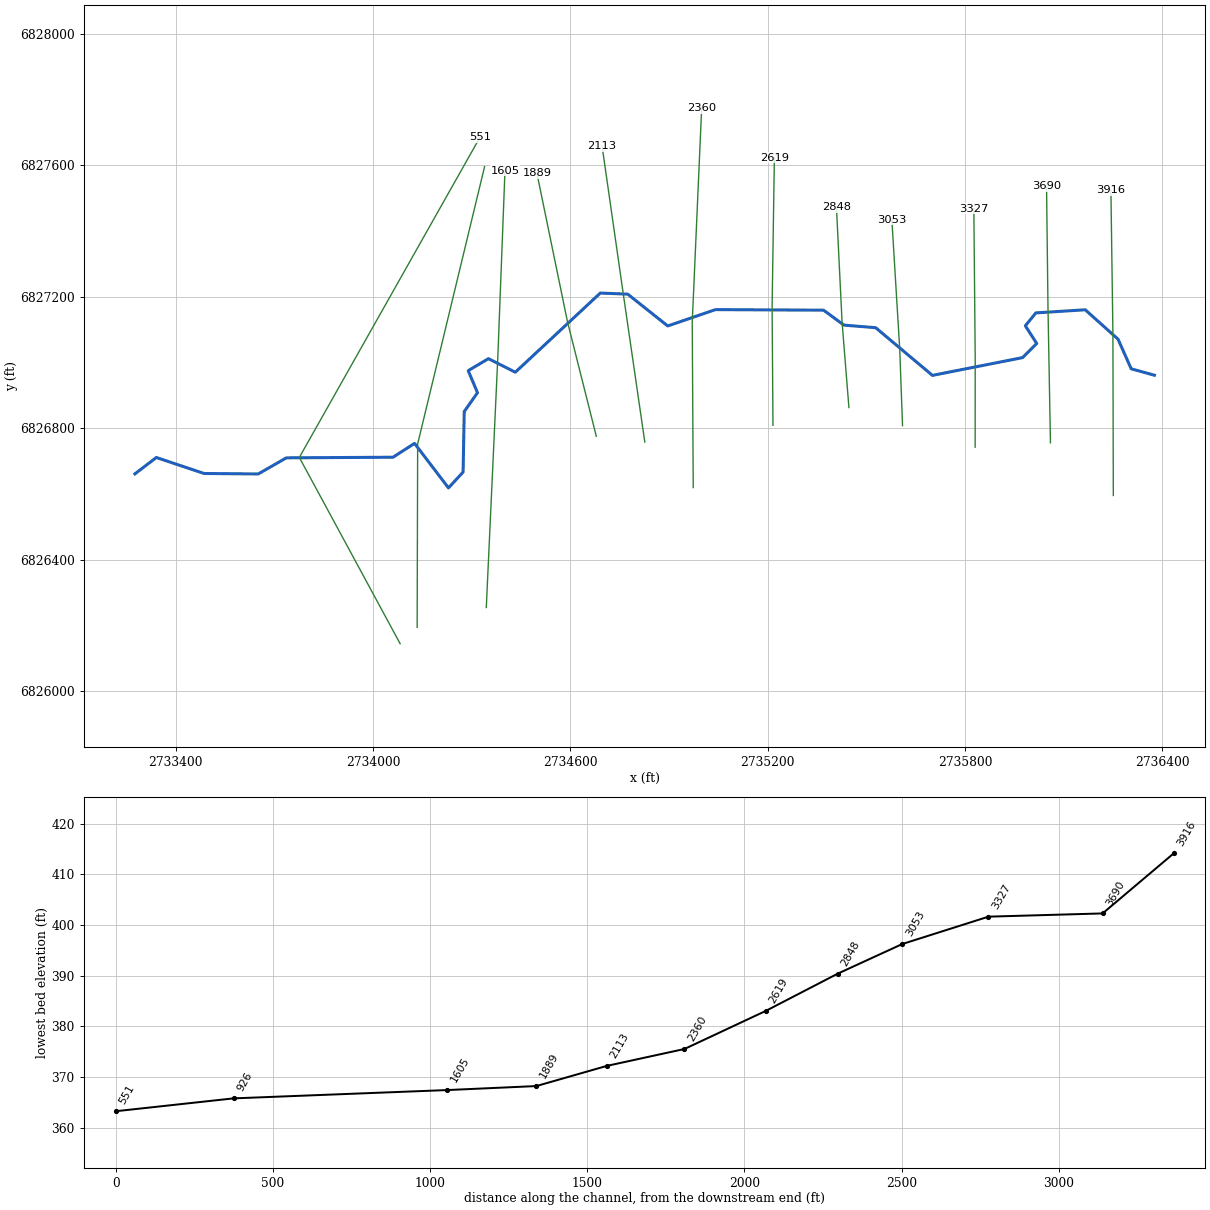
--- Twin Creek218.prj (project) ---

Proj Title=Twin Creek218 Base Level Engineering
Current Plan=p01
Default Exp/Contr=0.3,0.1
English Units
Geom File=g01
Flow File=f01
Plan File=p01
BEGIN DESCRIPTION:
Twin Creek218
END DESCRIPTION:

--- Twin Creek218.p01 (plan) ---

Plan Title=Multiple Run
Short Identifier=Multiple
Geom File=g01
Flow File=f01
Subcritical Flow
K Sum by GR= 0
Std Step Tol= 0.01
Critical Tol= 0.01
Num of Std Step Trials= 20
Max Error Tol= 0.3
Flow Tol Ratio= 0.001
Split Flow NTrial= 30
Split Flow Tol= 0.02
Split Flow Ratio= 0.02
Log Output Level= 0
Friction Slope Method= 1
Unsteady Friction Slope Method= 2
Unsteady Bridges Friction Slope Method= 1
Parabolic Critical Depth
Global Vel Dist=  1 , 1 , 1
Global Log Level= 0
CheckData=True
Encroach Param= -1, 0, 0, 0
BEGIN DESCRIPTION:
Multiple Run
END DESCRIPTION:

--- Twin Creek218.f01 (steady flow) ---

Flow Title=Multiple
Number of Profiles=7
Profile Names=10-year,25-year,50-year,1pct_min,100-year,1pct_plu,500-year
River Rch & RM= Twin Creek218,Reach-1,3916
     462     614     737     439     877    1749    1240
Boundary for River Rch & Prof#=Twin Creek218,Reach-1,1
Up Type=0
Dn Type=3
Dn Slope=0.005
Boundary for River Rch & Prof#=Twin Creek218,Reach-1,2
Up Type=0
Dn Type=3
Dn Slope=0.005
Boundary for River Rch & Prof#=Twin Creek218,Reach-1,3
Up Type=0
Dn Type=3
Dn Slope=0.005
Boundary for River Rch & Prof#=Twin Creek218,Reach-1,4
Up Type=0
Dn Type=3
Dn Slope=0.005
Boundary for River Rch & Prof#=Twin Creek218,Reach-1,5
Up Type=0
Dn Type=3
Dn Slope=0.005
Boundary for River Rch & Prof#=Twin Creek218,Reach-1,6
Up Type=0
Dn Type=3
Dn Slope=0.005
Boundary for River Rch & Prof#=Twin Creek218,Reach-1,7
Up Type=0
Dn Type=3
Dn Slope=0.005

--- Twin Creek218.g01 (geometry) ---

Geom Title=Existing Conditions

River Reach=Twin Creek218,Reach-1
Reach XY= 30
      2736376.00      6826961.00      2736305.36      6826980.55
      2736265.24      6827070.69      2736165.57      6827159.97
      2736015.49      6827150.53      2735983.47      6827111.23
      2736018.11      6827057.39      2735975.00      6827014.54
      2735700.96      6826960.50      2735528.43      6827105.48
      2735431.98      6827113.36      2735370.06      6827158.74
      2735041.22      6827160.48      2734896.05      6827110.79
      2734774.50      6827207.53      2734691.10      6827210.80
      2734432.73      6826970.15      2734350.82      6827011.40
      2734289.50      6826974.83      2734317.71      6826907.80
      2734277.38      6826850.57      2734273.93      6826666.44
      2734229.44      6826618.39      2734126.32      6826753.77
      2734060.85      6826711.67      2733736.50      6826709.78
      2733651.08      6826660.80      2733486.50      6826662.22
      2733341.22      6826710.81      2733276.00      6826661.00

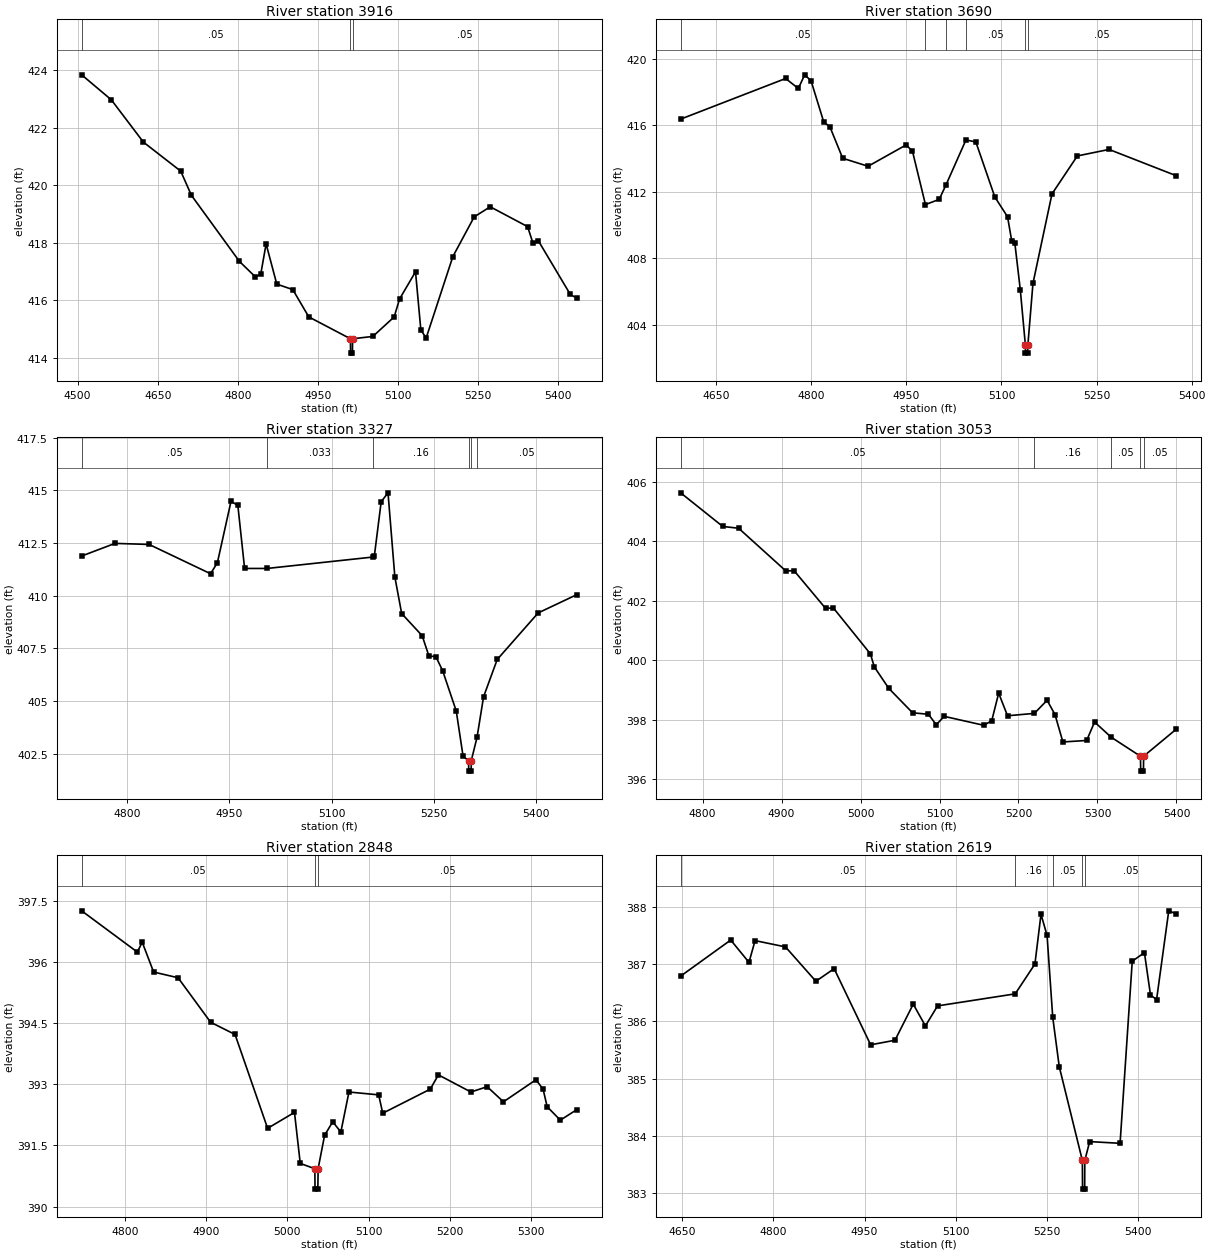
Type RM Length L Ch R = 1,3916,226,226,226
BEGIN DESCRIPTION:
Twin Creek2183764.132
END DESCRIPTION:
XS GIS Cut Line= 3
      2736250.95      6826595.39      2736249.73      6827087.88
      2736243.67      6827523.44
#Sta/Elev= 30
  4507.5  423.84  4563.1  422.97  4623.1  421.50  4693.1  420.49  4713.1  419.65
  4803.1  417.35  4833.1  416.81  4843.1  416.91  4853.1  417.96  4873.1  416.56
  4903.1  416.37  4933.1  415.42  5011.1  414.66  5011.4  414.16  5014.9  414.16
  5015.1  414.66  5053.1  414.74  5093.1  415.42  5103.1  416.04  5133.1  416.99
  5143.1  414.96  5153.1  414.69  5203.1  417.52  5243.1  418.90  5273.1  419.25
  5343.1  418.56  5353.1  417.99  5363.2  418.07  5423.2  416.20  5435.6  416.07
#Mann=3,-1,0
  4507.5    0.05       0  5011.1    0.05       0  5015.1    0.05       0
Bank Sta=5011.1,5015.1
Exp/Cntr=0.3,0.1

Type RM Length L Ch R = 1,3690,363,363,363
BEGIN DESCRIPTION:
Twin Creek2183690.16
END DESCRIPTION:
XS GIS Cut Line= 3
      2736059.82      6826755.43      2736052.37      6827163.12
      2736047.94      6827536.53
#Sta/Elev= 30
  4594.0  416.36  4759.6  418.80  4779.6  418.20  4789.6  419.02  4799.6  418.67
  4819.6  416.20  4829.6  415.88  4849.6  414.01  4889.6  413.53  4949.6  414.81
  4959.6  414.44  4980.1  411.23  5001.8  411.54  5012.4  412.40  5044.0  415.11
  5059.6  414.99  5089.6  411.68  5109.6  410.50  5116.1  409.07  5121.1  408.92
  5129.7  406.12  5137.7  402.81  5137.9  402.31  5141.4  402.31  5141.7  402.81
  5149.7  406.50  5179.7  411.87  5219.7  414.15  5269.7  414.54  5375.2  412.97
#Mann=6,-1,0
  4594.0    0.05       0  4980.1   0.033       0  5012.4    0.16       0
  5044.0    0.05       0  5137.7   0.033       0  5141.7    0.05       0
Bank Sta=5137.7,5141.7
Exp/Cntr=0.3,0.1

Type RM Length L Ch R = 1,3327,274,274,274
BEGIN DESCRIPTION:
Twin Creek2183326.72
END DESCRIPTION:
XS GIS Cut Line= 3
      2735830.86      6826742.20      2735831.02      6827015.00
      2735826.89      6827467.78
#Sta/Elev= 30
  4733.8  411.88  4782.6  412.48  4832.6  412.43  4922.6  411.04  4932.6  411.56
  4952.6  414.48  4962.6  414.28  4972.5  411.29  5005.4  411.29  5160.0  411.83
  5162.6  411.89  5172.6  414.46  5182.6  414.88  5192.6  410.89  5202.6  409.15
  5232.6  408.10  5242.6  407.13  5252.6  407.11  5262.6  406.44  5282.6  404.52
  5292.6  402.37  5300.6  402.17  5300.9  401.67  5304.4  401.67  5304.6  402.17
  5313.0  403.27  5322.6  405.20  5342.6  406.97  5402.6  409.18  5459.4  410.05
#Mann=6,-1,0
  4733.8    0.05       0  5005.4   0.033       0  5160.0    0.16       0
  5300.6    0.05       0  5304.6    0.16       0  5313.0    0.05       0
Bank Sta=5300.6,5304.6
Exp/Cntr=0.3,0.1

Type RM Length L Ch R = 1,3053,205,205,205
BEGIN DESCRIPTION:
Twin Creek2183052.79
END DESCRIPTION:
XS GIS Cut Line= 3
      2735610.03      6826807.69      2735601.60      6827039.54
      2735577.58      6827433.81
#Sta/Elev= 30
  4772.3  405.62  4825.6  404.49  4845.7  404.43  4905.7  402.99  4915.7  403.01
  4955.7  401.74  4965.7  401.75  5012.5  400.21  5017.5  399.77  5035.8  399.05
  5065.9  398.23  5085.9  398.18  5095.9  397.83  5106.0  398.11  5156.0  397.81
  5166.1  397.96  5174.9  398.89  5186.1  398.13  5220.1  398.21  5236.2  398.65
  5246.2  398.17  5256.2  397.25  5286.3  397.30  5296.3  397.92  5317.3  397.41
  5354.4  396.77  5354.7  396.27  5358.2  396.27  5358.4  396.77  5399.3  397.67
#Mann=5,-1,0
  4772.3    0.05       0  5220.1    0.16       0  5317.3    0.05       0
  5354.4    0.05       0  5358.4    0.05       0
Bank Sta=5354.4,5358.4
Exp/Cntr=0.3,0.1

Type RM Length L Ch R = 1,2848,229,229,229
BEGIN DESCRIPTION:
Twin Creek2182848.03
END DESCRIPTION:
XS GIS Cut Line= 3
      2735447.06      6826862.69      2735426.23      6827121.98
      2735409.15      6827471.44
#Sta/Elev= 30
  4746.6  397.25  4815.1  396.24  4821.2  396.48  4835.2  395.75  4865.3  395.61
  4905.4  394.52  4935.5  394.22  4975.6  391.92  5008.7  392.31  5015.8  391.06
  5033.8  390.93  5034.0  390.43  5037.5  390.43  5037.8  390.93  5045.8  391.75
  5055.8  392.08  5065.8  391.83  5075.8  392.81  5112.4  392.74  5117.4  392.29
  5175.9  392.88  5186.0  393.23  5226.0  392.81  5246.0  392.94  5266.1  392.57
  5306.1  393.11  5314.9  392.88  5319.9  392.45  5336.1  392.12  5356.6  392.38
#Mann=3,-1,0
  4746.6    0.05       0  5033.8    0.05       0  5037.8    0.05       0
Bank Sta=5033.8,5037.8
Exp/Cntr=0.3,0.1

Type RM Length L Ch R = 1,2619,259,259,259
BEGIN DESCRIPTION:
Twin Creek2182619.28
END DESCRIPTION:
XS GIS Cut Line= 3
      2735216.12      6826808.73      2735213.49      6827168.90
      2735220.39      6827622.77
#Sta/Elev= 30
  4647.7  386.79  4730.0  387.42  4760.0  387.03  4770.0  387.41  4820.0  387.30
  4870.0  386.70  4900.0  386.92  4960.0  385.59  5000.0  385.67  5030.0  386.30
  5050.0  385.92  5070.0  386.27  5197.6  386.48  5230.0  387.00  5240.0  387.87
  5250.0  387.50  5259.3  386.07  5270.0  385.21  5308.0  383.57  5308.3  383.07
  5311.8  383.07  5312.0  383.57  5320.0  383.90  5370.0  383.87  5390.0  387.05
  5410.0  387.20  5420.0  386.46  5430.0  386.38  5450.0  387.93  5461.8  387.88
#Mann=5,-1,0
  4647.7    0.05       0  5197.6    0.16       0  5259.3    0.05       0
  5308.0    0.05       0  5312.0    0.05       0
Bank Sta=5308,5312
Exp/Cntr=0.3,0.1

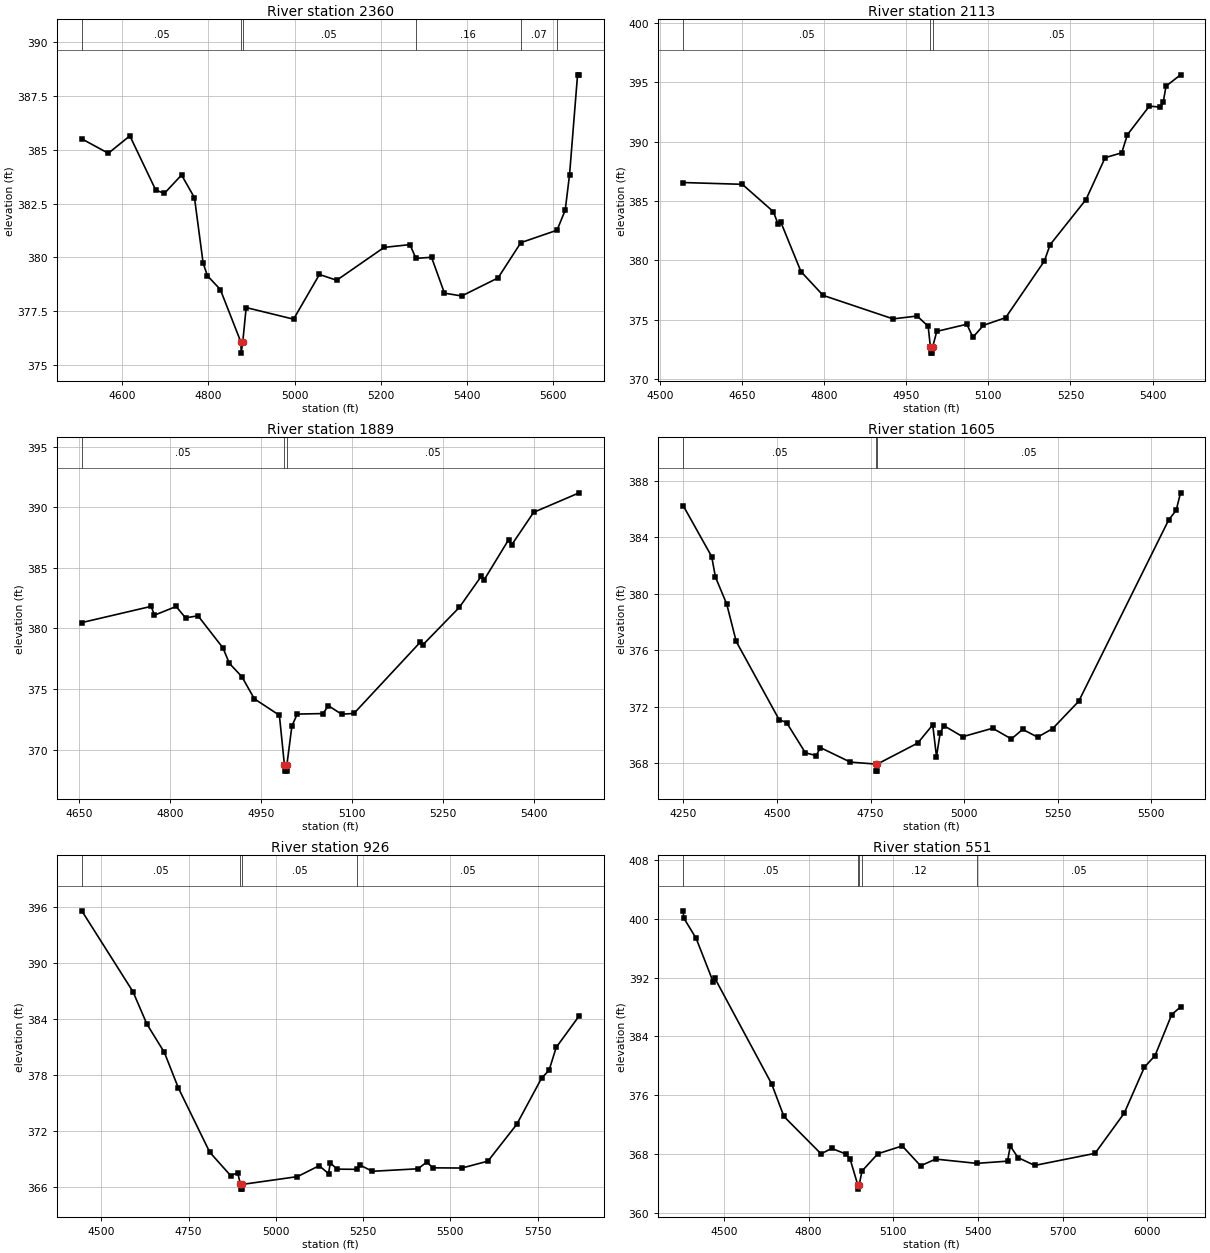
Type RM Length L Ch R = 1,2360,247,247,247
BEGIN DESCRIPTION:
Twin Creek2182360.48
END DESCRIPTION:
XS GIS Cut Line= 3
      2734973.69      6826619.41      2734970.64      6827121.59
      2734999.32      6827773.47
#Sta/Elev= 30
  4506.0  385.51  4567.6  384.84  4617.6  385.65  4677.6  383.13  4697.6  382.97
  4737.6  383.83  4767.6  382.77  4787.6  379.74  4797.6  379.14  4827.6  378.50
  4875.6  376.04  4875.9  375.54  4879.6  376.04  4887.6  377.66  4997.6  377.12
  5057.7  379.20  5097.7  378.93  5207.8  380.46  5267.9  380.59  5281.6  379.95
  5317.9  380.00  5347.9  378.33  5388.0  378.20  5472.3  379.04  5525.2  380.68
  5609.2  381.26  5628.2  382.19  5638.2  383.83  5656.9  388.49  5660.7  388.49
#Mann=6,-1,0
  4506.0    0.05       0  4875.6    0.05       0  4879.6    0.05       0
  5281.6    0.16       0  5525.2    0.07       0  5609.2    0.05       0
Bank Sta=4875.6,4879.6
Exp/Cntr=0.3,0.1

Type RM Length L Ch R = 1,2113,224,224,224
BEGIN DESCRIPTION:
Twin Creek2182112.79
END DESCRIPTION:
XS GIS Cut Line= 3
      2734826.39      6826757.93      2734759.68      6827217.05
      2734696.55      6827657.41
#Sta/Elev= 30
  4542.4  386.55  4650.5  386.40  4707.2  384.10  4715.6  383.09  4720.7  383.24
  4757.7  379.06  4798.1  377.06  4926.0  375.08  4969.9  375.32  4990.1  374.46
  4994.2  372.70  4994.4  372.20  4997.9  372.20  4998.2  372.70  5005.8  374.03
  5060.8  374.63  5071.8  373.53  5091.1  374.54  5131.6  375.18  5202.3  379.94
  5212.9  381.32  5278.5  385.12  5313.4  388.64  5343.7  389.05  5354.1  390.57
  5394.2  392.98  5414.4  392.89  5419.6  393.33  5424.7  394.66  5451.2  395.61
#Mann=3,-1,0
  4542.4    0.05       0  4994.2    0.05       0  4998.2    0.05       0
Bank Sta=4994.2,4998.2
Exp/Cntr=0.3,0.1

Type RM Length L Ch R = 1,1889,284,284,284
BEGIN DESCRIPTION:
Twin Creek2181889.35
END DESCRIPTION:
XS GIS Cut Line= 3
      2734679.00      6826775.27      2734591.42      6827123.02
      2734498.46      6827574.54
#Sta/Elev= 30
  4654.5  380.48  4768.9  381.82  4774.1  381.09  4810.0  381.81  4825.4  380.87
  4846.0  381.04  4887.1  378.39  4897.6  377.12  4918.2  376.02  4938.8  374.19
  4980.1  372.83  4988.4  368.72  4988.7  368.22  4992.2  368.22  4992.4  368.72
  5000.7  371.94  5009.5  372.93  5051.9  372.97  5060.9  373.62  5082.5  372.92
  5102.9  372.98  5211.8  378.84  5217.0  378.67  5276.5  381.73  5312.5  384.29
  5317.6  384.02  5357.7  387.31  5362.8  386.89  5399.0  389.58  5474.1  391.19
#Mann=3,-1,0
  4654.5    0.05       0  4988.4    0.05       0  4992.4    0.05       0
Bank Sta=4988.4,4992.4
Exp/Cntr=0.3,0.1

Type RM Length L Ch R = 1,1605,679,679,679
BEGIN DESCRIPTION:
Twin Creek2181605
END DESCRIPTION:
XS GIS Cut Line= 3
      2734344.44      6826254.76      2734379.42      6827014.11
      2734401.26      6827582.64
#Sta/Elev= 30
  4249.1  386.26  4325.4  382.64  4335.4  381.19  4365.5  379.28  4391.0  376.62
  4505.6  371.08  4525.6  370.87  4575.7  368.73  4604.8  368.53  4615.7  369.10
  4695.8  368.07  4763.9  367.93  4764.1  367.43  4767.6  367.43  4767.9  367.93
  4876.0  369.42  4916.0  370.71  4926.1  368.46  4936.1  370.16  4946.1  370.65
  4996.1  369.87  5076.2  370.47  5126.2  369.71  5156.3  370.39  5196.3  369.84
  5236.3  370.44  5306.1  372.38  5546.5  385.24  5566.5  385.92  5578.2  387.16
#Mann=3,-1,0
  4249.1    0.05       0  4763.9    0.05       0  4767.9    0.05       0
Bank Sta=4763.9,4767.9
Exp/Cntr=0.3,0.1

Type RM Length L Ch R = 1,926,375,375,375
BEGIN DESCRIPTION:
Twin Creek218925.87
END DESCRIPTION:
XS GIS Cut Line= 3
      2734134.23      6826194.40      2734135.76      6826752.05
      2734339.25      6827595.08
#Sta/Elev= 30
  4444.0  395.60  4590.6  386.94  4630.6  383.46  4680.6  380.43  4720.6  376.63
  4810.6  369.74  4870.6  367.23  4890.6  367.54  4898.6  366.29  4898.9  365.79
  4902.4  365.79  4902.6  366.29  5061.9  367.13  5124.0  368.30  5150.8  367.45
  5155.9  368.59  5175.5  367.93  5233.0  367.91  5239.7  368.39  5276.4  367.70
  5407.2  367.97  5432.6  368.70  5449.1  368.07  5532.9  368.05  5607.5  368.79
  5689.8  372.72  5761.8  377.72  5782.4  378.50  5803.0  380.97  5868.9  384.35
#Mann=4,-1,0
  4444.0    0.05       0  4898.6    0.07       0  4902.6    0.05       0
  5233.0    0.05       0
Bank Sta=4898.6,4902.6
Exp/Cntr=0.3,0.1

Type RM Length L Ch R = 1,551,0,0,0
BEGIN DESCRIPTION:
Twin Creek218551.64
END DESCRIPTION:
XS GIS Cut Line= 3
      2734082.49      6826144.68      2733776.00      6826711.00
      2734325.38      6827684.78
#Sta/Elev= 30
  4355.6  401.06  4357.9  400.08  4401.7  397.32  4461.6  391.45  4467.3  391.95
  4669.0  377.56  4712.7  373.12  4844.0  368.05  4882.1  368.78  4931.5  368.03
  4947.0  367.35  4974.8  363.75  4975.0  363.25  4978.8  363.75  4989.3  365.71
  5045.1  368.05  5131.7  369.12  5196.7  366.42  5250.2  367.33  5395.5  366.75
  5504.7  367.05  5514.5  369.10  5541.9  367.53  5601.1  366.47  5814.7  368.11
  5918.1  373.57  5989.6  379.82  6027.2  381.39  6086.4  386.97  6117.6  388.00
#Mann=5,-1,0
  4355.6    0.05       0  4974.8    0.07       0  4978.8    0.05       0
  4989.3    0.12       0  5395.5    0.05       0
Bank Sta=4974.8,4978.8
Exp/Cntr=0.3,0.1

Chan Stop Cuts=-1