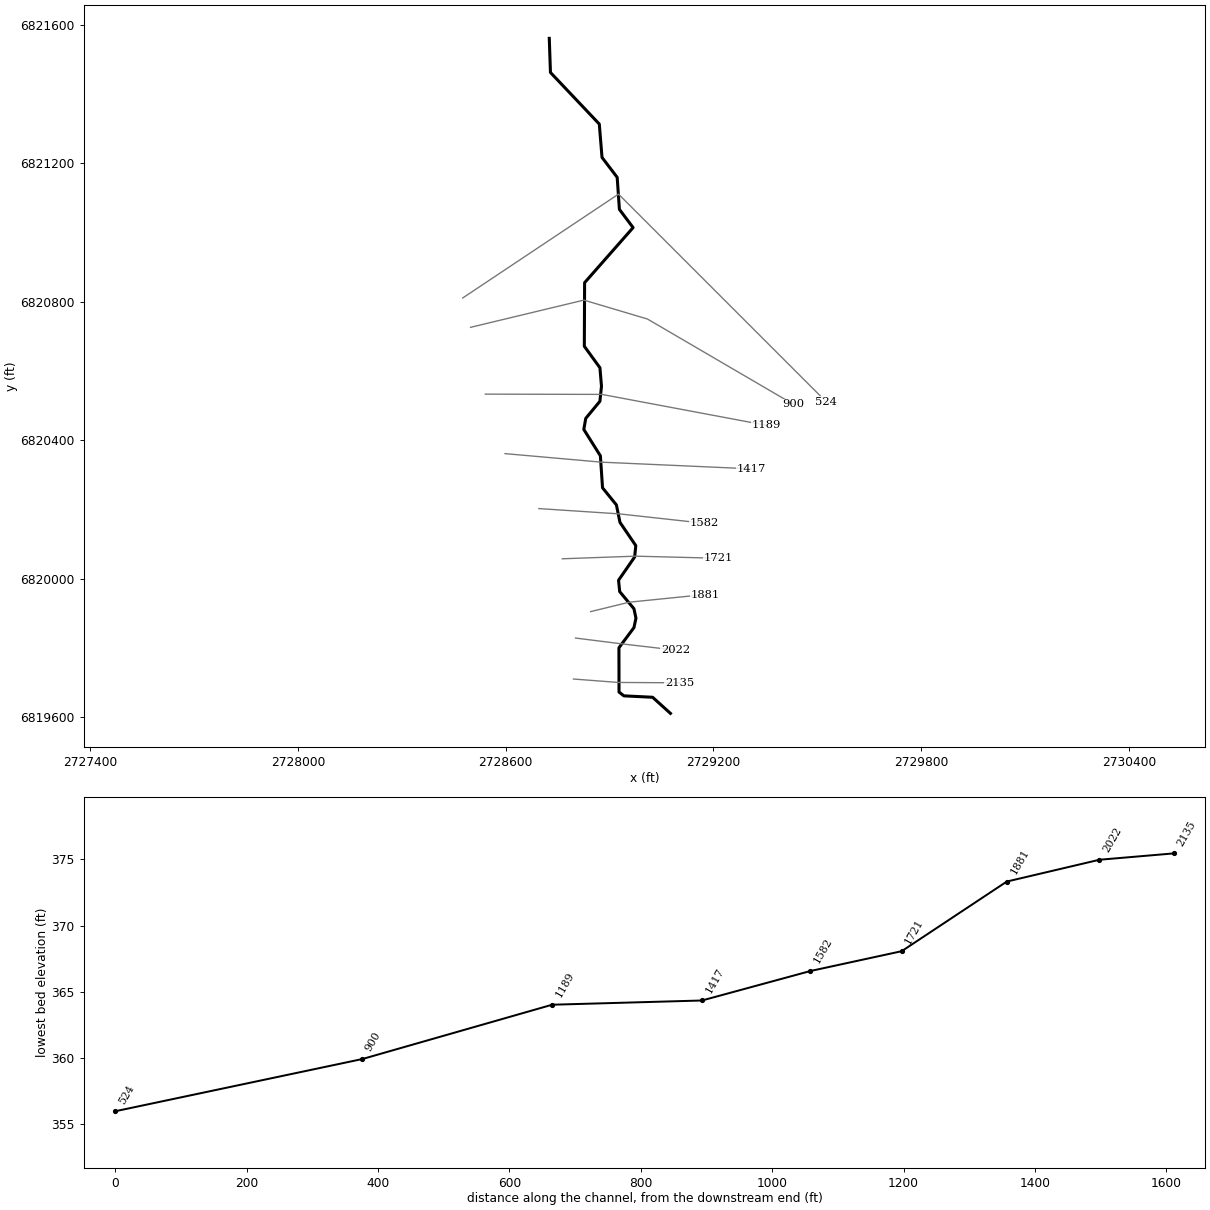
--- Twin Creek222.prj (project) ---

Proj Title=Twin Creek222 Base Level Engineering
Current Plan=p01
Default Exp/Contr=0.3,0.1
English Units
Geom File=g01
Flow File=f01
Plan File=p01
BEGIN DESCRIPTION:
Twin Creek222
END DESCRIPTION:

--- Twin Creek222.p01 (plan) ---

Plan Title=Multiple Run
Short Identifier=Multiple
Geom File=g01
Flow File=f01
Subcritical Flow
K Sum by GR= 0
Std Step Tol= 0.01
Critical Tol= 0.01
Num of Std Step Trials= 20
Max Error Tol= 0.3
Flow Tol Ratio= 0.001
Split Flow NTrial= 30
Split Flow Tol= 0.02
Split Flow Ratio= 0.02
Log Output Level= 0
Friction Slope Method= 1
Unsteady Friction Slope Method= 2
Unsteady Bridges Friction Slope Method= 1
Parabolic Critical Depth
Global Vel Dist=  1 , 1 , 1
Global Log Level= 0
CheckData=True
Encroach Param= -1, 0, 0, 0
BEGIN DESCRIPTION:
Multiple Run
END DESCRIPTION:

--- Twin Creek222.f01 (steady flow) ---

Flow Title=Multiple
Number of Profiles=7
Profile Names=10-year,25-year,50-year,1pct_min,100-year,1pct_plu,500-year
River Rch & RM= Twin Creek222,Reach-1,2135
     174     216     246     141     281     560     362
Boundary for River Rch & Prof#=Twin Creek222,Reach-1,1
Up Type=0
Dn Type=3
Dn Slope=0.005
Boundary for River Rch & Prof#=Twin Creek222,Reach-1,2
Up Type=0
Dn Type=3
Dn Slope=0.005
Boundary for River Rch & Prof#=Twin Creek222,Reach-1,3
Up Type=0
Dn Type=3
Dn Slope=0.005
Boundary for River Rch & Prof#=Twin Creek222,Reach-1,4
Up Type=0
Dn Type=3
Dn Slope=0.005
Boundary for River Rch & Prof#=Twin Creek222,Reach-1,5
Up Type=0
Dn Type=3
Dn Slope=0.005
Boundary for River Rch & Prof#=Twin Creek222,Reach-1,6
Up Type=0
Dn Type=3
Dn Slope=0.005
Boundary for River Rch & Prof#=Twin Creek222,Reach-1,7
Up Type=0
Dn Type=3
Dn Slope=0.005

--- Twin Creek222.g01 (geometry) ---

Geom Title=Existing Conditions

River Reach=Twin Creek222,Reach-1
Reach XY= 30
      2729076.00      6819611.00      2729024.49      6819657.56
      2728941.54      6819661.61      2728927.47      6819672.52
      2728927.22      6819800.48      2728970.62      6819858.82
      2728976.39      6819886.00      2728970.59      6819913.20
      2728929.41      6819962.72      2728926.11      6819995.61
      2728972.60      6820062.72      2728975.92      6820095.61
      2728930.22      6820162.72      2728919.89      6820213.18
      2728879.83      6820262.58      2728873.62      6820355.03
      2728825.72      6820431.18      2728831.38      6820463.18
      2728872.26      6820512.58      2728876.80      6820555.97
      2728872.29      6820609.40      2728827.22      6820671.50
      2728828.06      6820855.15      2728968.13      6821014.22
      2728928.56      6821066.89      2728922.15      6821159.40
      2728878.36      6821216.98      2728870.48      6821313.43
      2728729.38      6821462.40      2728726.00      6821561.00

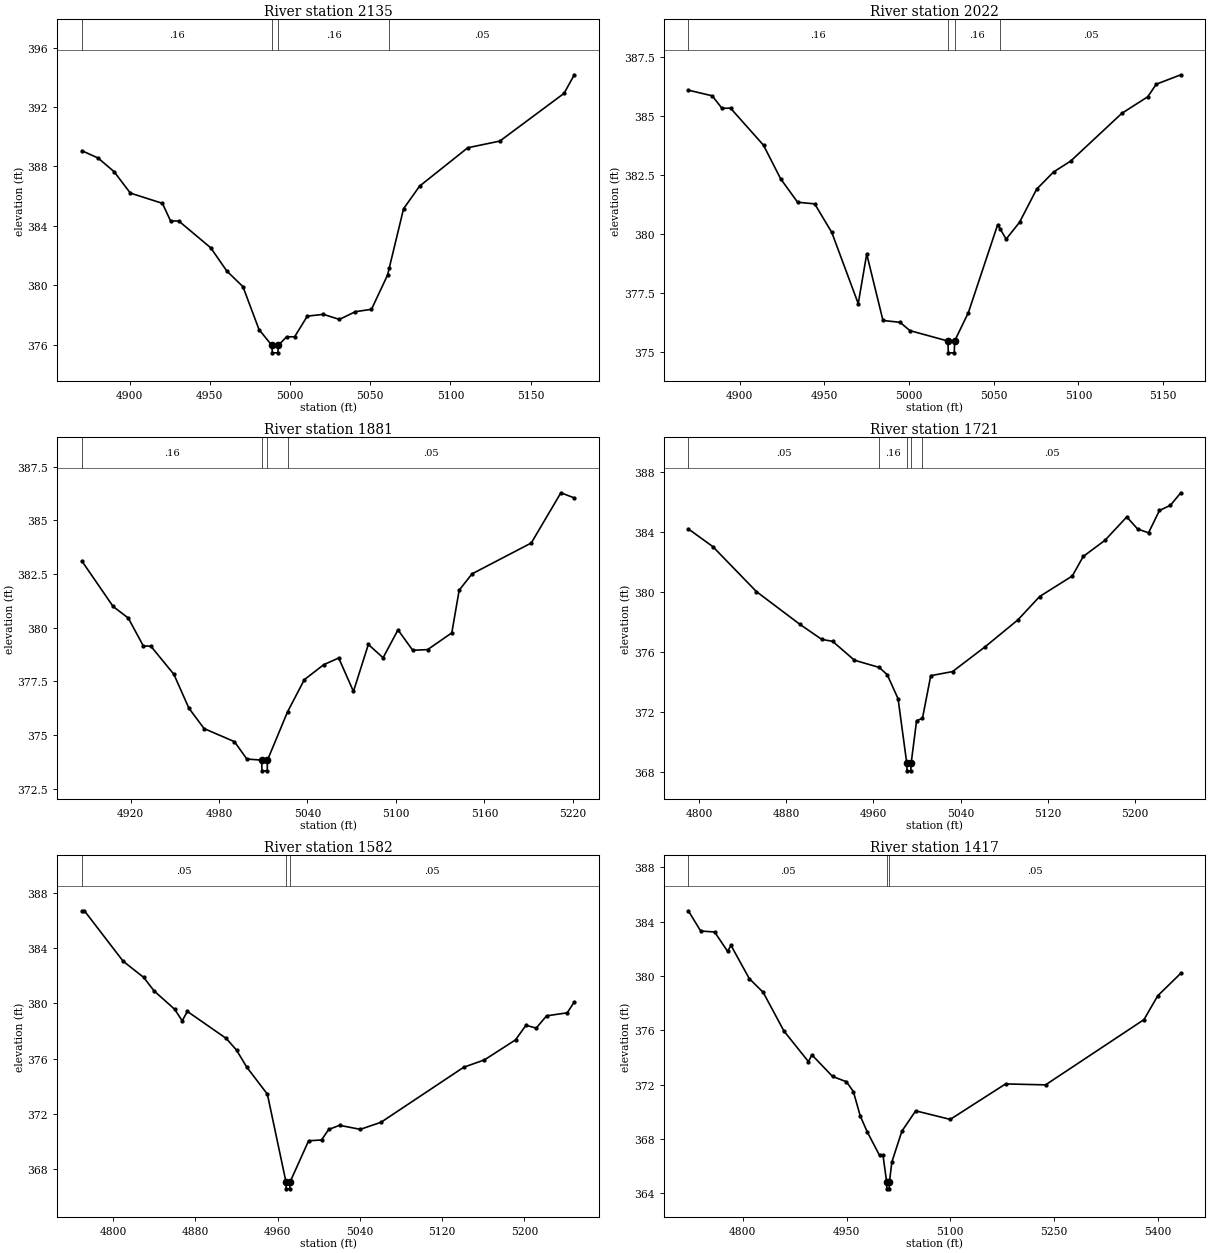
Type RM Length L Ch R = 1,2135,113,113,113
BEGIN DESCRIPTION:
Twin Creek2222134.974
END DESCRIPTION:
XS GIS Cut Line= 3
      2728795.93      6819710.24      2728925.25      6819700.33
      2729102.45      6819699.28
#Sta/Elev= 30
  4870.3  389.06  4880.4  388.57  4890.4  387.65  4900.5  386.21  4920.5  385.52
  4925.6  384.33  4930.7  384.33  4950.6  382.53  4960.6  380.97  4970.7  379.91
  4980.7  377.03  4988.7  375.96  4989.0  375.46  4992.5  375.46  4992.7  375.96
  4997.9  376.54  5002.9  376.54  5010.8  377.93  5020.8  378.05  5030.8  377.71
  5040.8  378.23  5050.8  378.39  5060.8  380.69  5061.8  381.14  5070.8  385.16
  5080.8  386.68  5110.8  389.26  5130.8  389.71  5170.8  392.92  5177.2  394.17
#Mann=4,-1,0
  4870.3    0.16       0  4988.7    0.07       0  4992.7    0.16       0
  5061.8    0.05       0
Bank Sta=4988.7,4992.7
Exp/Cntr=0.3,0.1

Type RM Length L Ch R = 1,2022,141,141,141
BEGIN DESCRIPTION:
Twin Creek2222022.18
END DESCRIPTION:
XS GIS Cut Line= 3
      2728801.97      6819828.58      2728932.49      6819812.15
      2729090.58      6819793.78
#Sta/Elev= 30
  4869.7  386.09  4883.8  385.85  4889.6  385.32  4894.6  385.33  4914.1  383.76
  4924.2  382.34  4934.2  381.35  4944.3  381.28  4954.4  380.07  4970.0  377.06
  4975.0  379.16  4984.6  376.35  4994.7  376.27  5000.5  375.92  5022.9  375.48
  5023.2  374.98  5026.7  374.98  5026.9  375.48  5035.0  376.68  5052.3  380.40
  5053.7  380.23  5057.3  379.79  5065.2  380.50  5075.3  381.90  5085.3  382.63
  5095.4  383.09  5125.6  385.11  5140.9  385.81  5145.9  386.34  5160.4  386.74
#Mann=4,-1,0
  4869.7    0.16       0  5022.9    0.07       0  5026.9    0.16       0
  5053.7    0.05       0
Bank Sta=5022.9,5026.9
Exp/Cntr=0.3,0.1

Type RM Length L Ch R = 1,1881,160,160,160
BEGIN DESCRIPTION:
Twin Creek2221880.68
END DESCRIPTION:
XS GIS Cut Line= 3
      2728845.43      6819904.92      2728957.24      6819932.22
      2729175.03      6819954.22
#Sta/Elev= 30
  4887.0  383.11  4908.2  380.99  4918.5  380.45  4928.7  379.15  4933.8  379.14
  4949.4  377.83  4959.6  376.25  4969.9  375.30  4990.5  374.69  4998.9  373.88
  5008.9  373.83  5009.2  373.33  5012.7  373.33  5012.9  373.83  5026.5  376.08
  5037.9  377.58  5051.1  378.28  5061.2  378.59  5071.2  377.03  5081.3  379.22
  5091.3  378.60  5101.4  379.90  5111.4  378.95  5121.5  378.98  5137.9  379.76
  5142.9  381.75  5151.6  382.51  5191.8  383.95  5211.9  386.29  5221.0  386.05
#Mann=4,-1,0
  4887.0    0.16       0  5008.9    0.07       0  5012.9    0.16       0
  5026.5    0.05       0
Bank Sta=5008.9,5012.9
Exp/Cntr=0.3,0.1

Type RM Length L Ch R = 1,1721,139,139,139
BEGIN DESCRIPTION:
Twin Creek2221721.14
END DESCRIPTION:
XS GIS Cut Line= 3
      2728763.56      6820057.57      2728975.07      6820065.12
      2729215.55      6820059.07
#Sta/Elev= 30
  4790.0  384.20  4812.5  383.02  4852.5  380.02  4892.5  377.83  4912.5  376.83
  4922.5  376.70  4942.5  375.44  4965.2  374.96  4972.6  374.48  4982.6  372.87
  4990.6  368.56  4990.8  368.06  4994.3  368.06  4994.6  368.56  4999.6  371.41
  5005.0  371.56  5012.6  374.41  5032.6  374.68  5062.6  376.34  5092.6  378.13
  5112.6  379.69  5142.6  381.06  5152.6  382.36  5172.6  383.44  5192.6  385.00
  5202.6  384.19  5212.6  383.94  5222.6  385.43  5232.6  385.77  5242.2  386.61
#Mann=5,-1,0
  4790.0    0.05       0  4965.2    0.16       0  4990.6    0.07       0
  4994.6    0.16       0  5005.0    0.05       0
Bank Sta=4990.6,4994.6
Exp/Cntr=0.3,0.1

Type RM Length L Ch R = 1,1582,165,165,165
BEGIN DESCRIPTION:
Twin Creek2221582.4
END DESCRIPTION:
XS GIS Cut Line= 3
      2728695.97      6820202.58      2728928.58      6820187.25
      2729172.88      6820160.32
#Sta/Elev= 30
  4769.6  386.70  4772.1  386.70  4809.7  383.05  4829.8  381.87  4839.8  380.90
  4859.8  379.57  4867.2  378.73  4872.2  379.41  4909.9  377.46  4920.0  376.61
  4930.0  375.37  4950.0  373.42  4968.1  367.06  4968.3  366.56  4971.8  366.56
  4972.1  367.06  4990.1  370.04  5002.7  370.10  5009.6  370.86  5020.2  371.16
  5040.4  370.87  5060.5  371.38  5141.0  375.37  5161.1  375.90  5191.3  377.35
  5201.5  378.41  5211.4  378.20  5221.5  379.09  5241.6  379.31  5248.5  380.10
#Mann=3,-1,0
  4769.6    0.05       0  4968.1    0.05       0  4972.1    0.05       0
Bank Sta=4968.1,4972.1
Exp/Cntr=0.3,0.1

Type RM Length L Ch R = 1,1417,228,228,228
BEGIN DESCRIPTION:
Twin Creek2221417.28
END DESCRIPTION:
XS GIS Cut Line= 3
      2728598.14      6820361.34      2728876.57      6820336.69
      2729309.22      6820317.40
#Sta/Elev= 30
  4721.1  384.79  4739.0  383.30  4759.1  383.23  4777.9  381.81  4782.9  382.24
  4809.3  379.80  4829.4  378.79  4859.5  375.94  4894.9  373.69  4899.9  374.19
  4929.8  372.60  4949.9  372.21  4959.9  371.49  4969.9  369.69  4980.0  368.52
  4997.8  366.79  5002.8  366.79  5008.1  364.83  5008.3  364.33  5011.8  364.33
  5012.1  364.83  5015.6  366.30  5030.1  368.57  5050.1  370.07  5100.1  369.44
  5180.2  372.05  5238.0  371.98  5380.4  376.78  5400.4  378.54  5433.7  380.19
#Mann=3,-1,0
  4721.1    0.05       0  5008.1    0.05       0  5012.1    0.05       0
Bank Sta=5008.1,5012.1
Exp/Cntr=0.3,0.1

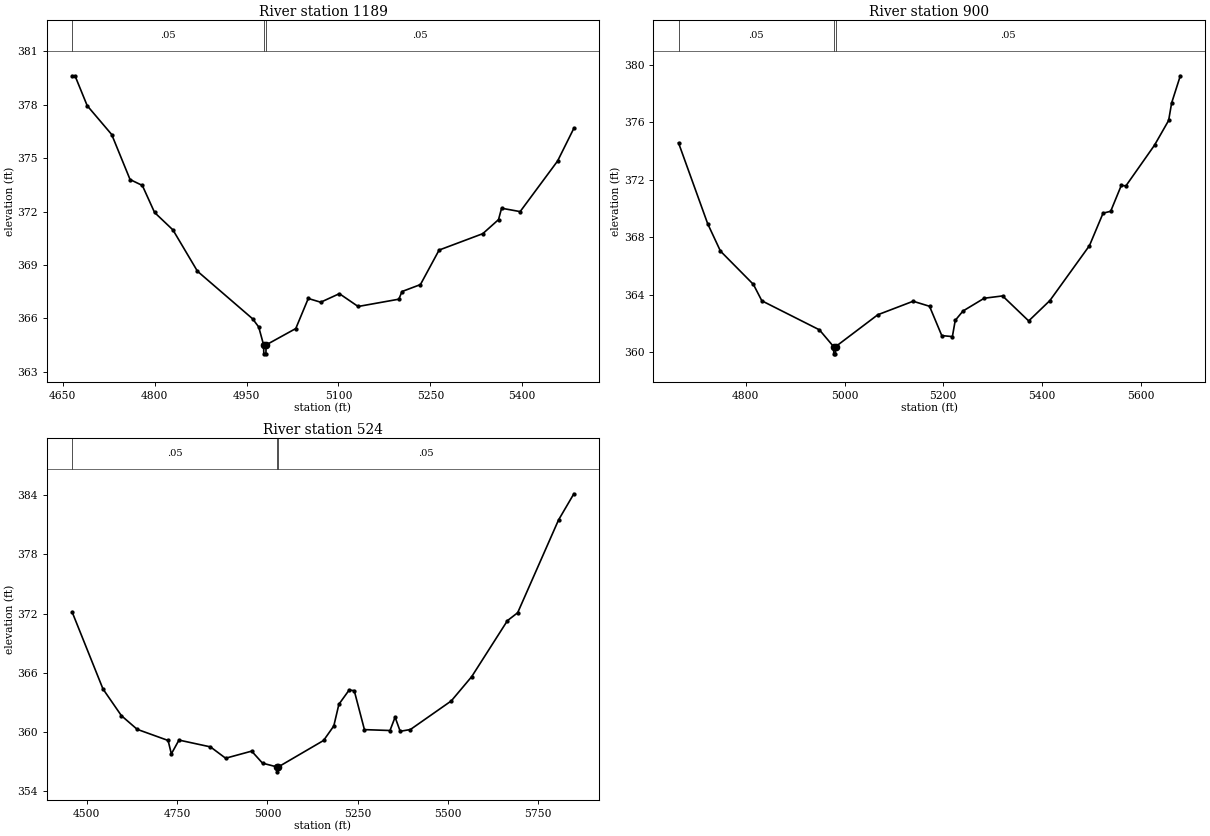
Type RM Length L Ch R = 1,1189,289,289,289
BEGIN DESCRIPTION:
Twin Creek2221188.96
END DESCRIPTION:
XS GIS Cut Line= 3
      2728541.27      6820533.18      2728877.86      6820532.42
      2729352.17      6820443.33
#Sta/Elev= 30
  4665.1  379.63  4669.9  379.63  4689.8  377.95  4729.8  376.33  4759.8  373.80
  4779.8  373.47  4799.8  371.95  4829.8  370.97  4869.8  368.65  4959.8  365.98
  4969.8  365.52  4977.8  364.51  4978.1  364.01  4981.6  364.01  4981.8  364.51
  5030.3  365.43  5050.7  367.12  5071.0  366.91  5101.5  367.39  5132.1  366.67
  5198.6  367.08  5203.7  367.51  5233.8  367.90  5264.3  369.84  5335.6  370.76
  5361.3  371.55  5366.3  372.19  5396.6  372.00  5457.7  374.84  5484.3  376.68
#Mann=3,-1,0
  4665.1    0.05       0  4977.8    0.05       0  4981.8    0.05       0
Bank Sta=4977.8,4981.8
Exp/Cntr=0.3,0.1

Type RM Length L Ch R = 1,900,376,376,376
BEGIN DESCRIPTION:
Twin Creek222900.43
END DESCRIPTION:
XS GIS Cut Line= 4
      2728498.52      6820726.15      2728825.90      6820804.82
      2729009.46      6820750.24      2729431.16      6820503.88
#Sta/Elev= 30
  4663.6  374.58  4722.7  368.95  4748.5  367.05  4815.3  364.73  4832.4  363.59
  4949.0  361.57  4977.8  360.40  4978.1  359.90  4981.6  359.90  4981.8  360.40
  5067.3  362.62  5138.9  363.56  5172.1  363.21  5196.9  361.17  5218.4  361.10
  5224.2  362.23  5239.9  362.88  5282.9  363.77  5320.1  363.93  5373.0  362.19
  5416.0  363.61  5496.1  367.43  5523.7  369.69  5539.1  369.82  5560.6  371.62
  5570.0  371.59  5627.9  374.42  5656.5  376.14  5662.6  377.36  5680.2  379.25
#Mann=3,-1,0
  4663.6    0.05       0  4977.8    0.05       0  4981.8    0.05       0
Bank Sta=4977.8,4981.8
Exp/Cntr=0.3,0.1

Type RM Length L Ch R = 1,524,0,0,0
BEGIN DESCRIPTION:
Twin Creek222524.08
END DESCRIPTION:
XS GIS Cut Line= 3
      2728475.99      6820810.99      2728926.00      6821111.00
      2729526.02      6820510.98
#Sta/Elev= 30
  4459.1  372.17  4544.7  364.35  4595.8  361.64  4639.4  360.26  4725.0  359.13
  4734.0  357.77  4755.1  359.17  4842.2  358.48  4884.3  357.33  4956.4  358.05
  4986.4  356.83  5026.2  356.45  5026.5  355.95  5030.2  356.45  5155.5  359.13
  5183.8  360.60  5197.9  362.80  5226.2  364.24  5240.4  364.18  5268.6  360.23
  5339.4  360.14  5353.5  361.49  5367.6  360.06  5395.9  360.24  5509.1  363.14
  5565.6  365.60  5664.6  371.28  5692.9  372.08  5806.0  381.48  5848.5  384.14
#Mann=3,-1,0
  4459.1    0.05       0  5026.2    0.05       0  5030.2    0.05       0
Bank Sta=5026.2,5030.2
Exp/Cntr=0.3,0.1

Chan Stop Cuts=-1