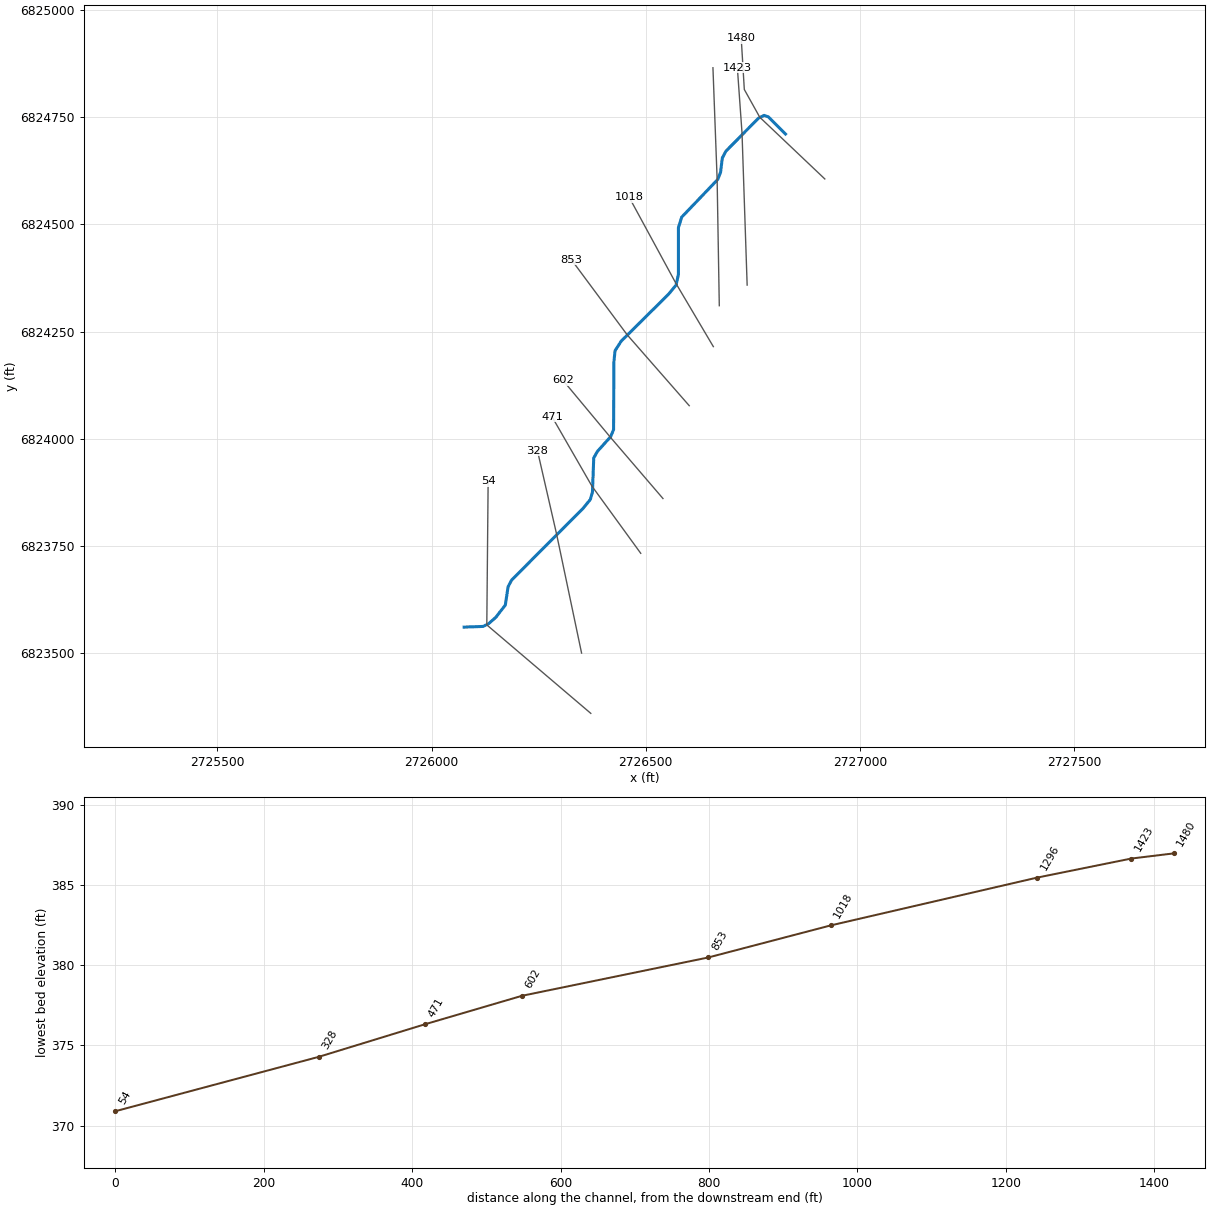
--- Twin Creek223.prj (project) ---

Proj Title=Twin Creek223 Base Level Engineering
Current Plan=p01
Default Exp/Contr=0.3,0.1
English Units
Geom File=g01
Flow File=f01
Plan File=p01
BEGIN DESCRIPTION:
Twin Creek223
END DESCRIPTION:

--- Twin Creek223.p01 (plan) ---

Plan Title=Multiple Run
Short Identifier=Multiple
Geom File=g01
Flow File=f01
Subcritical Flow
K Sum by GR= 0
Std Step Tol= 0.01
Critical Tol= 0.01
Num of Std Step Trials= 20
Max Error Tol= 0.3
Flow Tol Ratio= 0.001
Split Flow NTrial= 30
Split Flow Tol= 0.02
Split Flow Ratio= 0.02
Log Output Level= 0
Friction Slope Method= 1
Unsteady Friction Slope Method= 2
Unsteady Bridges Friction Slope Method= 1
Parabolic Critical Depth
Global Vel Dist=  1 , 1 , 1
Global Log Level= 0
CheckData=True
Encroach Param= -1, 0, 0, 0
BEGIN DESCRIPTION:
Multiple Run
END DESCRIPTION:

--- Twin Creek223.f01 (steady flow) ---

Flow Title=Multiple
Number of Profiles=7
Profile Names=10-year,25-year,50-year,1pct_min,100-year,1pct_plu,500-year
River Rch & RM= Twin Creek223,Reach-1,1480
     146     177     199     112     224     447     281
Boundary for River Rch & Prof#=Twin Creek223,Reach-1,1
Up Type=0
Dn Type=3
Dn Slope=0.005
Boundary for River Rch & Prof#=Twin Creek223,Reach-1,2
Up Type=0
Dn Type=3
Dn Slope=0.005
Boundary for River Rch & Prof#=Twin Creek223,Reach-1,3
Up Type=0
Dn Type=3
Dn Slope=0.005
Boundary for River Rch & Prof#=Twin Creek223,Reach-1,4
Up Type=0
Dn Type=3
Dn Slope=0.005
Boundary for River Rch & Prof#=Twin Creek223,Reach-1,5
Up Type=0
Dn Type=3
Dn Slope=0.005
Boundary for River Rch & Prof#=Twin Creek223,Reach-1,6
Up Type=0
Dn Type=3
Dn Slope=0.005
Boundary for River Rch & Prof#=Twin Creek223,Reach-1,7
Up Type=0
Dn Type=3
Dn Slope=0.005

--- Twin Creek223.g01 (geometry) ---

Geom Title=Existing Conditions

River Reach=Twin Creek223,Reach-1
Reach XY= 30
      2726826.00      6824711.00      2726785.99      6824750.90
      2726775.99      6824754.43      2726762.63      6824747.58
      2726686.77      6824670.72      2726678.53      6824654.97
      2726674.45      6824621.65      2726667.82      6824604.96
      2726583.83      6824517.18      2726576.11      6824492.77
      2726576.17      6824383.66      2726570.53      6824358.55
      2726553.14      6824337.47      2726442.43      6824227.76
      2726428.17      6824205.56      2726425.54      6824179.37
      2726424.78      6824021.50      2726417.86      6824004.94
      2726386.90      6823970.63      2726378.47      6823955.43
      2726375.48      6823876.22      2726370.48      6823858.57
      2726353.12      6823837.48      2726186.77      6823670.67
      2726178.51      6823654.94      2726172.14      6823612.46
      2726149.98      6823583.82      2726132.63      6823568.59
      2726120.13      6823562.56      2726076.00      6823561.00

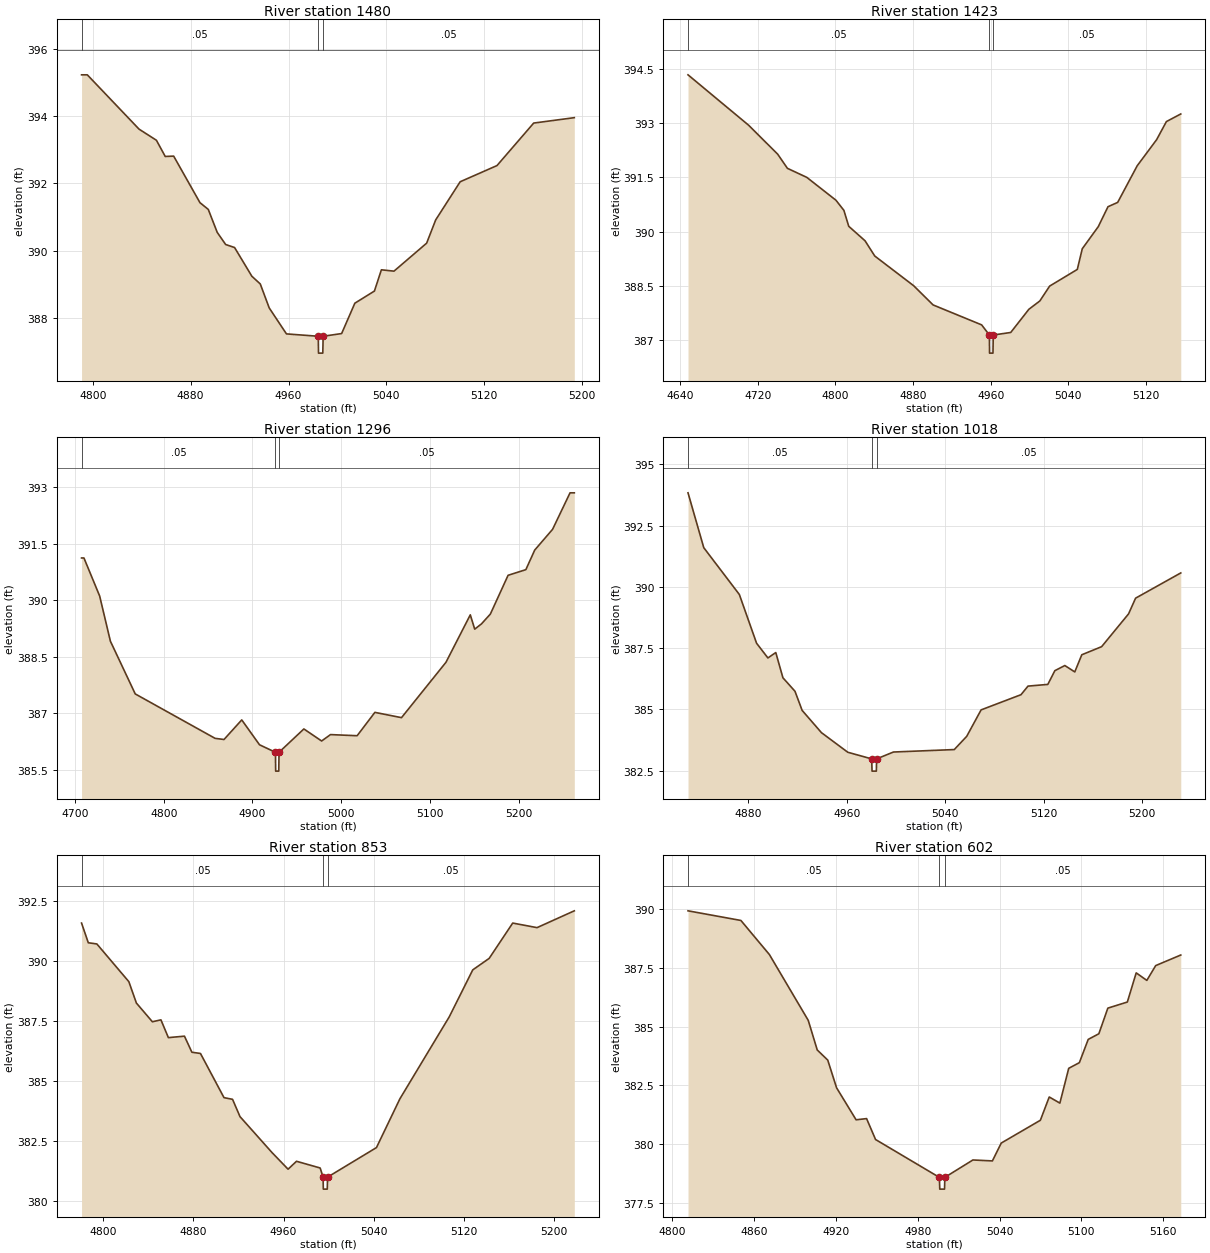
Type RM Length L Ch R = 1,1480,57,57,57
BEGIN DESCRIPTION:
Twin Creek2231480.304
END DESCRIPTION:
XS GIS Cut Line= 4
      2726917.79      6824606.19      2726765.97      6824750.12
      2726729.90      6824814.82      2726722.70      6824934.13
#Sta/Elev= 30
  4790.8  395.22  4795.5  395.22  4837.8  393.61  4852.0  393.28  4859.2  392.80
  4866.1  392.81  4887.6  391.43  4894.4  391.23  4901.7  390.55  4908.6  390.19
  4915.9  390.10  4930.0  389.25  4936.9  389.02  4944.2  388.31  4958.3  387.54
  4984.3  387.47  4984.5  386.97  4988.0  386.97  4988.3  387.47  5003.4  387.55
  5014.2  388.45  5030.2  388.81  5035.9  389.44  5046.2  389.40  5072.9  390.23
  5080.3  390.92  5100.3  392.05  5130.4  392.53  5160.4  393.79  5193.6  393.95
#Mann=3,-1,0
  4790.8    0.05       0  4984.3    0.05       0  4988.3    0.05       0
Bank Sta=4984.3,4988.3
Exp/Cntr=0.3,0.1

Type RM Length L Ch R = 1,1423,127,127,127
BEGIN DESCRIPTION:
Twin Creek2231422.93
END DESCRIPTION:
XS GIS Cut Line= 3
      2726736.52      6824358.68      2726724.55      6824713.39
      2726713.64      6824865.79
#Sta/Elev= 30
  4648.1  394.33  4710.5  392.94  4740.5  392.14  4750.5  391.75  4770.5  391.50
  4800.5  390.87  4808.7  390.59  4813.7  390.15  4830.5  389.75  4840.5  389.33
  4880.6  388.51  4900.6  387.98  4950.6  387.43  4958.6  387.15  4958.8  386.65
  4962.3  386.65  4962.6  387.15  4980.6  387.22  4999.3  387.86  5010.6  388.09
  5020.7  388.50  5049.2  388.96  5054.3  389.53  5070.8  390.14  5080.8  390.69
  5090.8  390.81  5110.9  391.82  5130.9  392.54  5141.0  393.04  5155.8  393.25
#Mann=3,-1,0
  4648.1    0.05       0  4958.6    0.05       0  4962.6    0.05       0
Bank Sta=4958.6,4962.6
Exp/Cntr=0.3,0.1

Type RM Length L Ch R = 1,1296,278,278,278
BEGIN DESCRIPTION:
Twin Creek2231296.18
END DESCRIPTION:
XS GIS Cut Line= 3
      2726671.51      6824310.56      2726666.44      6824605.96
      2726656.69      6824865.53
#Sta/Elev= 30
  4707.4  391.12  4710.1  391.12  4727.8  390.11  4739.9  388.91  4767.9  387.51
  4857.9  386.33  4867.9  386.30  4887.9  386.82  4907.9  386.16  4925.9  385.96
  4926.1  385.46  4929.6  385.46  4929.9  385.96  4957.9  386.58  4977.9  386.26
  4987.9  386.43  5017.9  386.40  5037.9  387.02  5067.9  386.88  5118.0  388.35
  5145.4  389.61  5150.4  389.23  5158.0  389.37  5168.0  389.63  5188.0  390.66
  5208.0  390.81  5218.0  391.33  5238.1  391.88  5257.8  392.85  5262.6  392.85
#Mann=3,-1,0
  4707.4    0.05       0  4925.9    0.05       0  4929.9    0.05       0
Bank Sta=4925.9,4929.9
Exp/Cntr=0.3,0.1

Type RM Length L Ch R = 1,1018,165,165,165
BEGIN DESCRIPTION:
Twin Creek2231018
END DESCRIPTION:
XS GIS Cut Line= 3
      2726657.62      6824215.14      2726570.41      6824362.44
      2726461.01      6824563.76
#Sta/Elev= 30
  4831.0  393.84  4843.8  391.60  4872.7  389.69  4886.7  387.70  4895.9  387.10
  4902.3  387.32  4908.1  386.29  4917.9  385.74  4923.7  384.96  4939.4  384.05
  4960.8  383.25  4980.2  382.98  4980.5  382.48  4984.0  382.48  4984.2  382.98
  4997.9  383.26  5047.3  383.36  5057.4  383.90  5069.1  384.98  5101.5  385.60
  5107.2  385.95  5123.3  386.02  5129.0  386.58  5137.1  386.79  5145.2  386.53
  5150.9  387.23  5167.0  387.56  5188.9  388.90  5194.6  389.54  5231.3  390.57
#Mann=3,-1,0
  4831.0    0.05       0  4980.2    0.05       0  4984.2    0.05       0
Bank Sta=4980.2,4984.2
Exp/Cntr=0.3,0.1

Type RM Length L Ch R = 1,853,251,251,251
BEGIN DESCRIPTION:
Twin Creek223852.99
END DESCRIPTION:
XS GIS Cut Line= 3
      2726601.34      6824077.41      2726456.36      6824242.88
      2726326.59      6824417.55
#Sta/Elev= 30
  4780.6  391.56  4786.6  390.74  4794.2  390.69  4822.6  389.12  4829.3  388.23
  4843.5  387.45  4851.1  387.53  4857.7  386.79  4872.0  386.85  4878.6  386.18
  4886.2  386.13  4907.1  384.29  4914.7  384.22  4921.3  383.50  4949.8  382.00
  4964.0  381.31  4971.5  381.64  4992.5  381.36  4995.1  380.98  4995.3  380.48
  4998.8  380.48  4999.1  380.98  5042.5  382.21  5063.3  384.24  5107.2  387.66
  5128.0  389.61  5142.6  390.09  5163.5  391.56  5185.1  391.37  5218.2  392.07
#Mann=3,-1,0
  4780.6    0.05       0  4995.1    0.05       0  4999.1    0.05       0
Bank Sta=4995.1,4999.1
Exp/Cntr=0.3,0.1

Type RM Length L Ch R = 1,602,131,131,131
BEGIN DESCRIPTION:
Twin Creek223602.24
END DESCRIPTION:
XS GIS Cut Line= 3
      2726540.02      6823860.91      2726416.13      6824005.21
      2726306.47      6824136.83
#Sta/Elev= 30
  4811.4  389.93  4850.2  389.52  4871.1  388.07  4899.6  385.27  4906.2  384.01
  4913.9  383.58  4920.4  382.40  4934.7  381.04  4942.4  381.09  4949.0  380.20
  4995.8  378.59  4996.1  378.09  4999.6  378.09  4999.8  378.59  5020.4  379.33
  5034.7  379.29  5041.2  380.05  5069.9  381.02  5076.4  382.01  5084.2  381.75
  5090.7  383.23  5098.5  383.47  5105.0  384.46  5112.8  384.70  5119.4  385.79
  5133.7  386.05  5140.2  387.29  5148.0  386.97  5154.5  387.60  5172.9  388.05
#Mann=3,-1,0
  4811.4    0.05       0  4995.8    0.05       0  4999.8    0.05       0
Bank Sta=4995.8,4999.8
Exp/Cntr=0.3,0.1

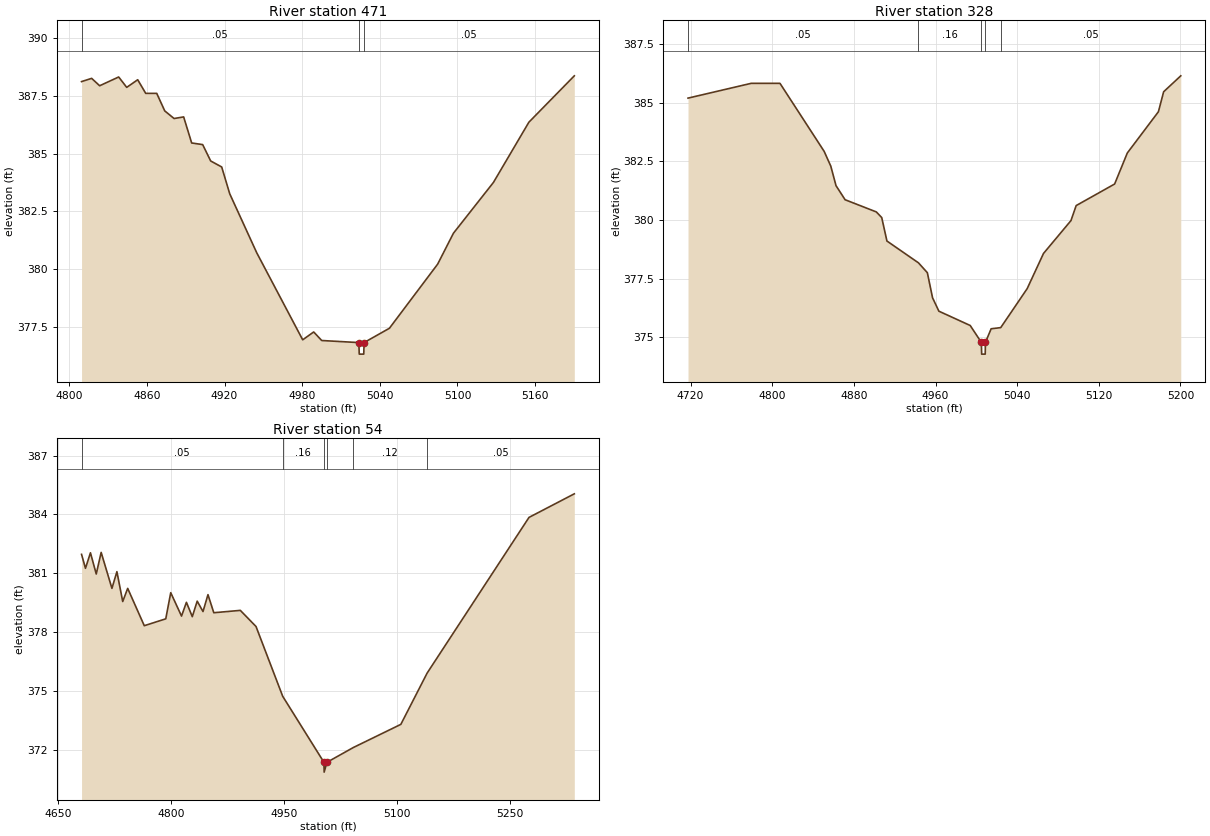
Type RM Length L Ch R = 1,471,143,143,143
BEGIN DESCRIPTION:
Twin Creek223471.25
END DESCRIPTION:
XS GIS Cut Line= 3
      2726488.14      6823733.14      2726374.22      6823889.84
      2726280.89      6824051.96
#Sta/Elev= 30
  4809.5  388.12  4817.3  388.26  4823.5  387.94  4838.2  388.32  4844.4  387.87
  4852.9  388.20  4859.1  387.61  4867.6  387.61  4873.8  386.85  4881.0  386.52
  4888.4  386.59  4894.6  385.46  4903.1  385.39  4909.3  384.68  4917.8  384.42
  4924.0  383.26  4944.9  380.70  4980.4  376.93  4988.9  377.27  4995.1  376.90
  5023.8  376.81  5024.1  376.31  5027.6  376.31  5027.8  376.81  5047.4  377.43
  5084.7  380.21  5096.9  381.55  5127.8  383.75  5155.2  386.36  5190.3  388.37
#Mann=3,-1,0
  4809.5    0.05       0  5023.8    0.05       0  5027.8    0.05       0
Bank Sta=5023.8,5027.8
Exp/Cntr=0.3,0.1

Type RM Length L Ch R = 1,328,274,274,274
BEGIN DESCRIPTION:
Twin Creek223328.24
END DESCRIPTION:
XS GIS Cut Line= 3
      2726350.09      6823500.42      2726291.18      6823780.47
      2726247.20      6823972.11
#Sta/Elev= 30
  4717.5  385.19  4779.4  385.82  4807.6  385.82  4850.9  382.92  4857.4  382.29
  4862.5  381.46  4871.4  380.86  4902.0  380.34  4907.3  380.10  4912.4  379.10
  4943.3  378.17  4952.0  377.75  4957.1  376.68  4963.3  376.11  4994.0  375.50
  5004.9  374.78  5005.2  374.28  5008.7  374.28  5008.9  374.78  5014.5  375.36
  5023.9  375.41  5049.8  377.07  5065.8  378.57  5092.7  379.97  5097.8  380.61
  5135.5  381.53  5147.9  382.85  5178.4  384.61  5183.5  385.46  5200.3  386.14
#Mann=5,-1,0
  4717.5    0.05       0  4943.3    0.16       0  5004.9    0.07       0
  5008.9    0.16       0  5023.9    0.05       0
Bank Sta=5004.9,5008.9
Exp/Cntr=0.3,0.1

Type RM Length L Ch R = 1,54,0,0,0
BEGIN DESCRIPTION:
Twin Creek22353.776
END DESCRIPTION:
XS GIS Cut Line= 3
      2726371.63      6823359.80      2726128.89      6823566.15
      2726132.01      6823901.14
#Sta/Elev= 30
  4681.4  381.97  4686.6  381.26  4693.2  382.05  4700.9  380.97  4707.4  382.07
  4721.7  380.24  4728.3  381.09  4736.0  379.57  4742.6  380.24  4764.6  378.34
  4793.1  378.69  4799.7  380.02  4814.0  378.83  4820.5  379.53  4828.3  378.80
  4834.8  379.59  4842.5  379.06  4849.1  379.92  4856.8  379.00  4892.0  379.12
  4912.8  378.30  4948.2  374.75  5002.9  371.39  5003.2  370.89  5006.9  371.39
  5041.8  372.14  5104.9  373.32  5139.8  375.93  5274.9  383.85  5335.0  385.05
#Mann=6,-1,0
  4681.4    0.05       0  4948.2    0.16       0  5002.9    0.07       0
  5006.9    0.16       0  5041.8    0.12       0  5139.8    0.05       0
Bank Sta=5002.9,5006.9
Exp/Cntr=0.3,0.1

Chan Stop Cuts=-1