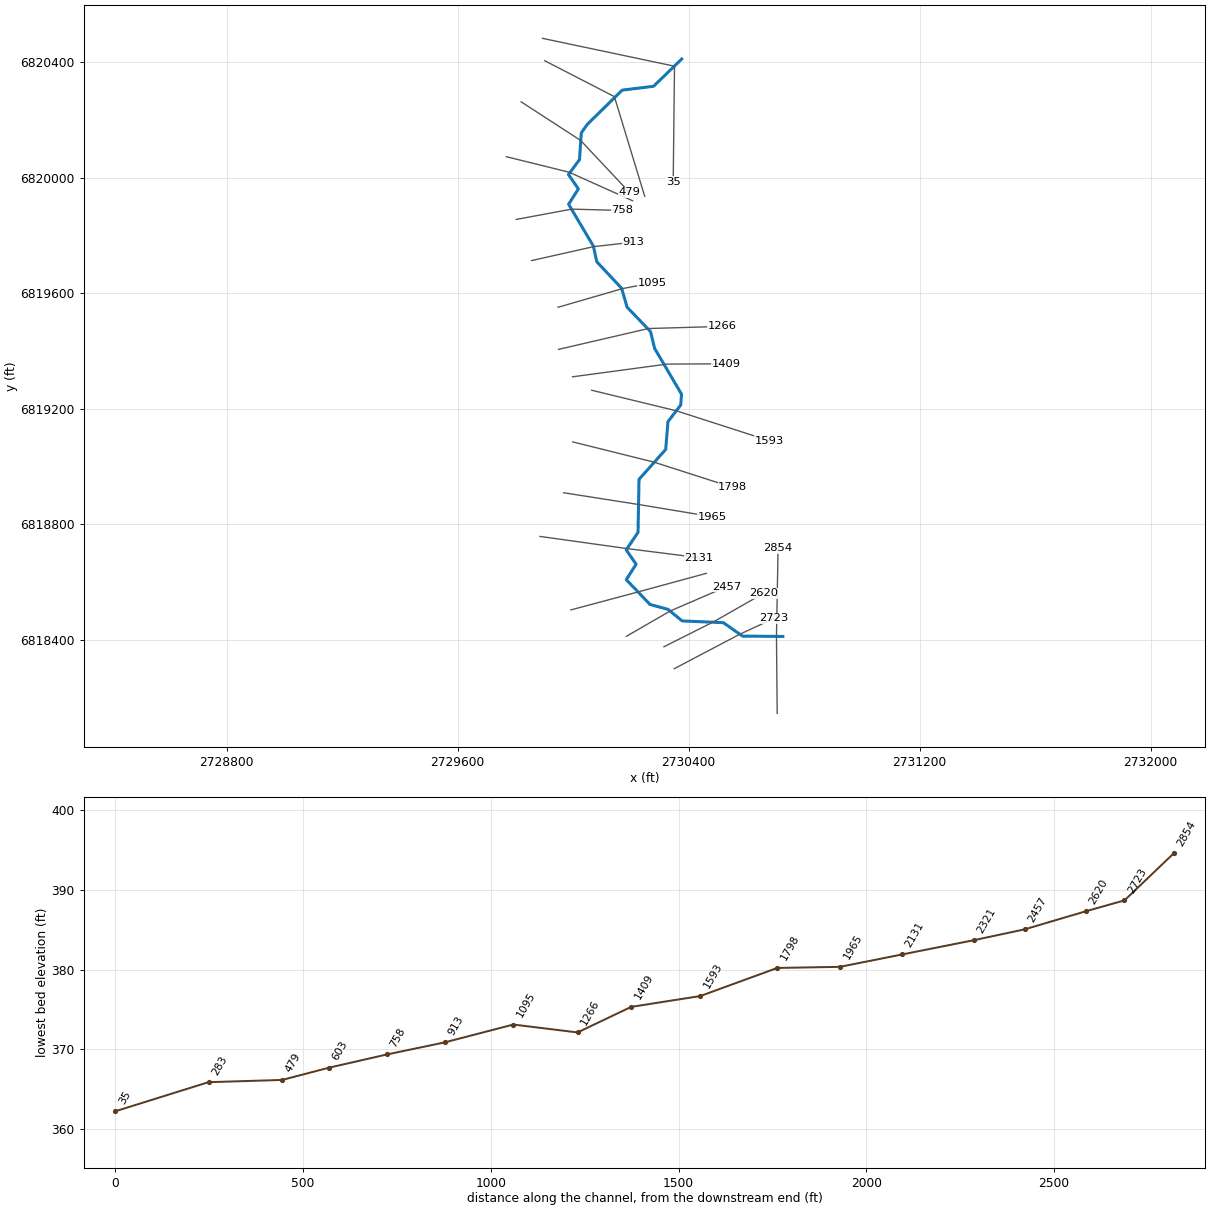
--- Twin Creek225.prj (project) ---

Proj Title=Twin Creek225 Base Level Engineering
Current Plan=p01
Default Exp/Contr=0.3,0.1
English Units
Geom File=g01
Flow File=f01
Plan File=p01
BEGIN DESCRIPTION:
Twin Creek225
END DESCRIPTION:

--- Twin Creek225.p01 (plan) ---

Plan Title=Multiple Run
Short Identifier=Multiple
Geom File=g01
Flow File=f01
Subcritical Flow
K Sum by GR= 0
Std Step Tol= 0.01
Critical Tol= 0.01
Num of Std Step Trials= 20
Max Error Tol= 0.3
Flow Tol Ratio= 0.001
Split Flow NTrial= 30
Split Flow Tol= 0.02
Split Flow Ratio= 0.02
Log Output Level= 0
Friction Slope Method= 1
Unsteady Friction Slope Method= 2
Unsteady Bridges Friction Slope Method= 1
Parabolic Critical Depth
Global Vel Dist=  1 , 1 , 1
Global Log Level= 0
CheckData=True
Encroach Param= -1, 0, 0, 0
BEGIN DESCRIPTION:
Multiple Run
END DESCRIPTION:

--- Twin Creek225.f01 (steady flow) ---

Flow Title=Multiple
Number of Profiles=7
Profile Names=10-year,25-year,50-year,1pct_min,100-year,1pct_plu,500-year
River Rch & RM= Twin Creek225,Reach-1,2854
     180     223     255     145     290     579     373
Boundary for River Rch & Prof#=Twin Creek225,Reach-1,1
Up Type=0
Dn Type=3
Dn Slope=0.005
Boundary for River Rch & Prof#=Twin Creek225,Reach-1,2
Up Type=0
Dn Type=3
Dn Slope=0.005
Boundary for River Rch & Prof#=Twin Creek225,Reach-1,3
Up Type=0
Dn Type=3
Dn Slope=0.005
Boundary for River Rch & Prof#=Twin Creek225,Reach-1,4
Up Type=0
Dn Type=3
Dn Slope=0.005
Boundary for River Rch & Prof#=Twin Creek225,Reach-1,5
Up Type=0
Dn Type=3
Dn Slope=0.005
Boundary for River Rch & Prof#=Twin Creek225,Reach-1,6
Up Type=0
Dn Type=3
Dn Slope=0.005
Boundary for River Rch & Prof#=Twin Creek225,Reach-1,7
Up Type=0
Dn Type=3
Dn Slope=0.005

--- Twin Creek225.g01 (geometry) ---

Geom Title=Existing Conditions

River Reach=Twin Creek225,Reach-1
Reach XY= 30
      2730726.00      6818411.00      2730586.48      6818412.17
      2730520.06      6818458.73      2730377.56      6818464.76
      2730328.17      6818504.86      2730266.27      6818521.76
      2730183.98      6818607.65      2730217.96      6818660.99
      2730183.78      6818710.90      2730224.62      6818771.43
      2730228.07      6818955.14      2730320.46      6819058.58
      2730328.38      6819155.03      2730372.63      6819212.74
      2730375.25      6819250.32      2730282.10      6819408.81
      2730267.84      6819467.05      2730186.80      6819551.33
      2730167.82      6819617.04      2730081.85      6819708.71
      2730069.89      6819763.19      2729984.23      6819907.77
      2730017.97      6819961.00      2729983.78      6820010.90
      2730021.92      6820062.50      2730028.15      6820155.11
      2730048.87      6820184.52      2730169.83      6820303.14
      2730278.45      6820316.46      2730376.00      6820411.00

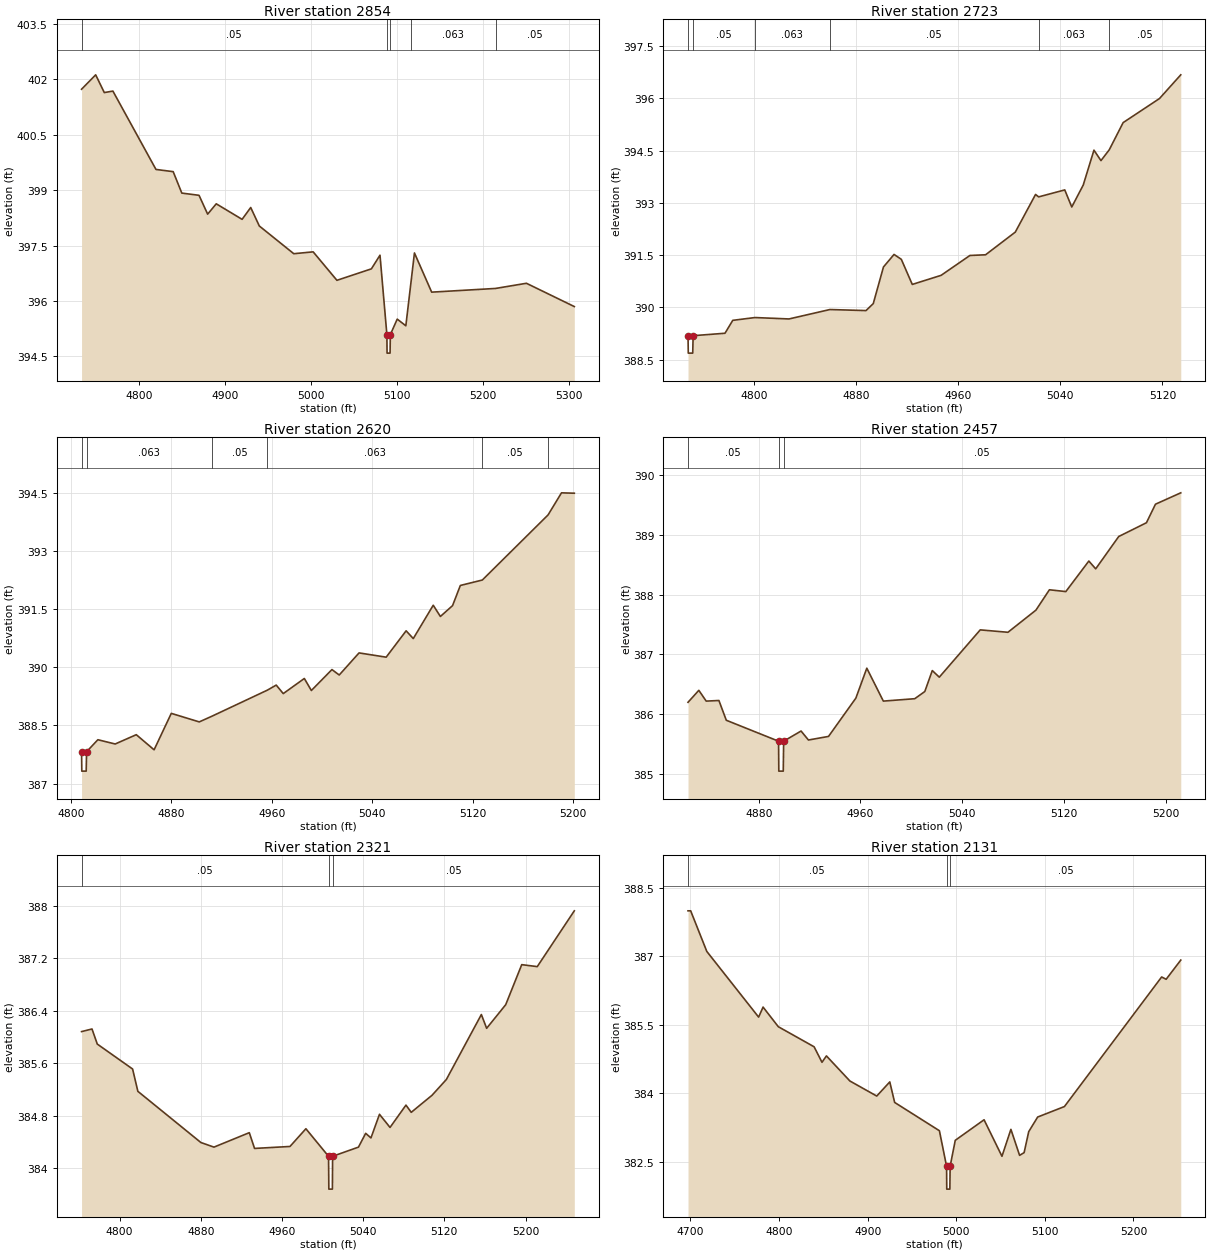
Type RM Length L Ch R = 1,2854,131,131,131
BEGIN DESCRIPTION:
Twin Creek2252854.477
END DESCRIPTION:
XS GIS Cut Line= 3
      2730706.64      6818144.56      2730704.13      6818410.95
      2730709.71      6818716.60
#Sta/Elev= 30
  4733.6  401.73  4750.0  402.12  4760.0  401.64  4770.0  401.68  4820.0  399.56
  4840.0  399.50  4850.0  398.92  4870.0  398.86  4880.0  398.35  4890.0  398.63
  4920.0  398.21  4930.0  398.53  4940.0  398.03  4980.0  397.28  5002.5  397.33
  5030.1  396.56  5070.1  396.87  5080.1  397.24  5088.1  395.09  5088.3  394.59
  5091.8  394.59  5092.1  395.09  5100.1  395.51  5110.1  395.33  5116.2  396.53
  5120.1  397.30  5140.1  396.24  5214.2  396.34  5250.1  396.48  5305.7  395.85
#Mann=5,-1,0
  4733.6    0.05       0  5088.1    0.05       0  5092.1    0.05       0
  5116.2   0.063       0  5214.2    0.05       0
Bank Sta=5088.1,5092.1
Exp/Cntr=0.3,0.1

Type RM Length L Ch R = 1,2723,103,103,103
BEGIN DESCRIPTION:
Twin Creek2252722.84
END DESCRIPTION:
XS GIS Cut Line= 3
      2730350.37      6818299.45      2730574.30      6818417.29
      2730695.39      6818473.40
#Sta/Elev= 30
  4747.9  389.19  4748.1  388.69  4751.6  388.69  4751.9  389.19  4776.9  389.26
  4783.0  389.63  4800.4  389.71  4827.1  389.67  4859.2  389.94  4887.5  389.91
  4893.2  390.11  4901.2  391.16  4909.5  391.52  4915.2  391.38  4923.8  390.66
  4946.4  390.92  4969.0  391.49  4981.3  391.51  5004.6  392.16  5020.5  393.24
  5022.9  393.17  5043.4  393.37  5048.9  392.88  5057.9  393.51  5066.3  394.51
  5071.8  394.21  5078.3  394.52  5089.2  395.30  5117.7  395.99  5134.4  396.67
#Mann=6,-1,0
  4747.9    0.05       0  4751.9    0.05       0  4800.4   0.063       0
  4859.2    0.05       0  5022.9   0.063       0  5078.3    0.05       0
Bank Sta=4747.9,4751.9
Exp/Cntr=0.3,0.1

Type RM Length L Ch R = 1,2620,163,163,163
BEGIN DESCRIPTION:
Twin Creek2252619.73
END DESCRIPTION:
XS GIS Cut Line= 3
      2730314.39      6818375.26      2730489.42      6818463.35
      2730660.20      6818560.86
#Sta/Elev= 30
  4808.4  387.82  4808.6  387.32  4812.1  387.32  4812.4  387.82  4821.4  388.13
  4835.2  388.02  4852.0  388.26  4866.2  387.87  4879.9  388.81  4902.2  388.59
  4912.5  388.74  4956.5  389.41  4963.5  389.54  4969.1  389.32  4985.9  389.71
  4991.5  389.40  5007.9  389.94  5013.7  389.80  5029.5  390.37  5051.1  390.26
  5067.0  390.94  5072.7  390.74  5088.6  391.60  5094.3  391.31  5104.0  391.59
  5110.2  392.11  5127.7  392.25  5180.1  393.93  5190.8  394.50  5201.0  394.49
#Mann=6,-1,0
  4808.4   0.063       0  4812.4   0.063       0  4912.5    0.05       0
  4956.5   0.063       0  5127.7    0.05       0  5180.1   0.063       0
Bank Sta=4808.4,4812.4
Exp/Cntr=0.3,0.1

Type RM Length L Ch R = 1,2457,136,136,136
BEGIN DESCRIPTION:
Twin Creek2252457.29
END DESCRIPTION:
XS GIS Cut Line= 3
      2730184.22      6818411.37      2730336.53      6818499.38
      2730530.82      6818583.18
#Sta/Elev= 30
  4824.4  386.20  4832.9  386.40  4838.7  386.22  4848.7  386.23  4854.5  385.90
  4895.6  385.55  4895.8  385.05  4899.3  385.05  4899.6  385.55  4913.3  385.72
  4919.1  385.57  4934.9  385.63  4956.4  386.27  4965.0  386.77  4978.0  386.22
  5002.7  386.26  5010.6  386.38  5016.5  386.73  5022.0  386.62  5054.2  387.41
  5076.0  387.37  5098.0  387.74  5108.6  388.08  5121.5  388.05  5139.6  388.56
  5145.0  388.43  5163.1  388.97  5184.9  389.20  5192.0  389.51  5211.9  389.70
#Mann=3,-1,0
  4824.4    0.05       0  4895.6    0.05       0  4899.6    0.05       0
Bank Sta=4895.6,4899.6
Exp/Cntr=0.3,0.1

Type RM Length L Ch R = 1,2321,190,190,190
BEGIN DESCRIPTION:
Twin Creek2252320.71
END DESCRIPTION:
XS GIS Cut Line= 3
      2729992.41      6818502.98      2730221.44      6818564.22
      2730461.22      6818629.56
#Sta/Elev= 30
  4762.5  386.08  4772.8  386.12  4778.0  385.89  4812.8  385.51  4818.0  385.17
  4880.1  384.39  4893.0  384.32  4927.8  384.54  4933.0  384.30  4967.9  384.33
  4983.6  384.60  5005.9  384.18  5006.2  383.68  5009.7  383.68  5009.9  384.18
  5035.4  384.32  5042.5  384.53  5047.7  384.46  5056.1  384.82  5066.5  384.62
  5082.2  384.96  5087.4  384.85  5107.9  385.11  5122.0  385.35  5156.5  386.34
  5161.7  386.13  5180.5  386.49  5196.3  387.10  5211.6  387.07  5248.1  387.92
#Mann=3,-1,0
  4762.5    0.05       0  5005.9    0.05       0  5009.9    0.05       0
Bank Sta=5005.9,5009.9
Exp/Cntr=0.3,0.1

Type RM Length L Ch R = 1,2131,166,166,166
BEGIN DESCRIPTION:
Twin Creek2252131.17
END DESCRIPTION:
XS GIS Cut Line= 3
      2729885.03      6818757.43      2730183.71      6818715.73
      2730436.22      6818683.78
#Sta/Elev= 30
  4697.3  388.00  4700.3  388.00  4718.5  387.11  4777.0  385.67  4782.0  385.89
  4799.2  385.46  4839.6  385.02  4848.5  384.68  4853.5  384.82  4880.0  384.27
  4910.3  383.94  4925.0  384.25  4930.5  383.80  4981.0  383.18  4989.1  382.40
  4989.3  381.90  4992.8  381.90  4993.1  382.40  4998.9  382.97  5031.4  383.42
  5051.6  382.62  5061.7  383.21  5071.5  382.64  5076.6  382.70  5081.8  383.16
  5091.9  383.48  5122.1  383.71  5231.8  386.55  5236.9  386.50  5253.4  386.92
#Mann=3,-1,0
  4697.3    0.05       0  4989.1    0.05       0  4993.1    0.05       0
Bank Sta=4989.1,4993.1
Exp/Cntr=0.3,0.1

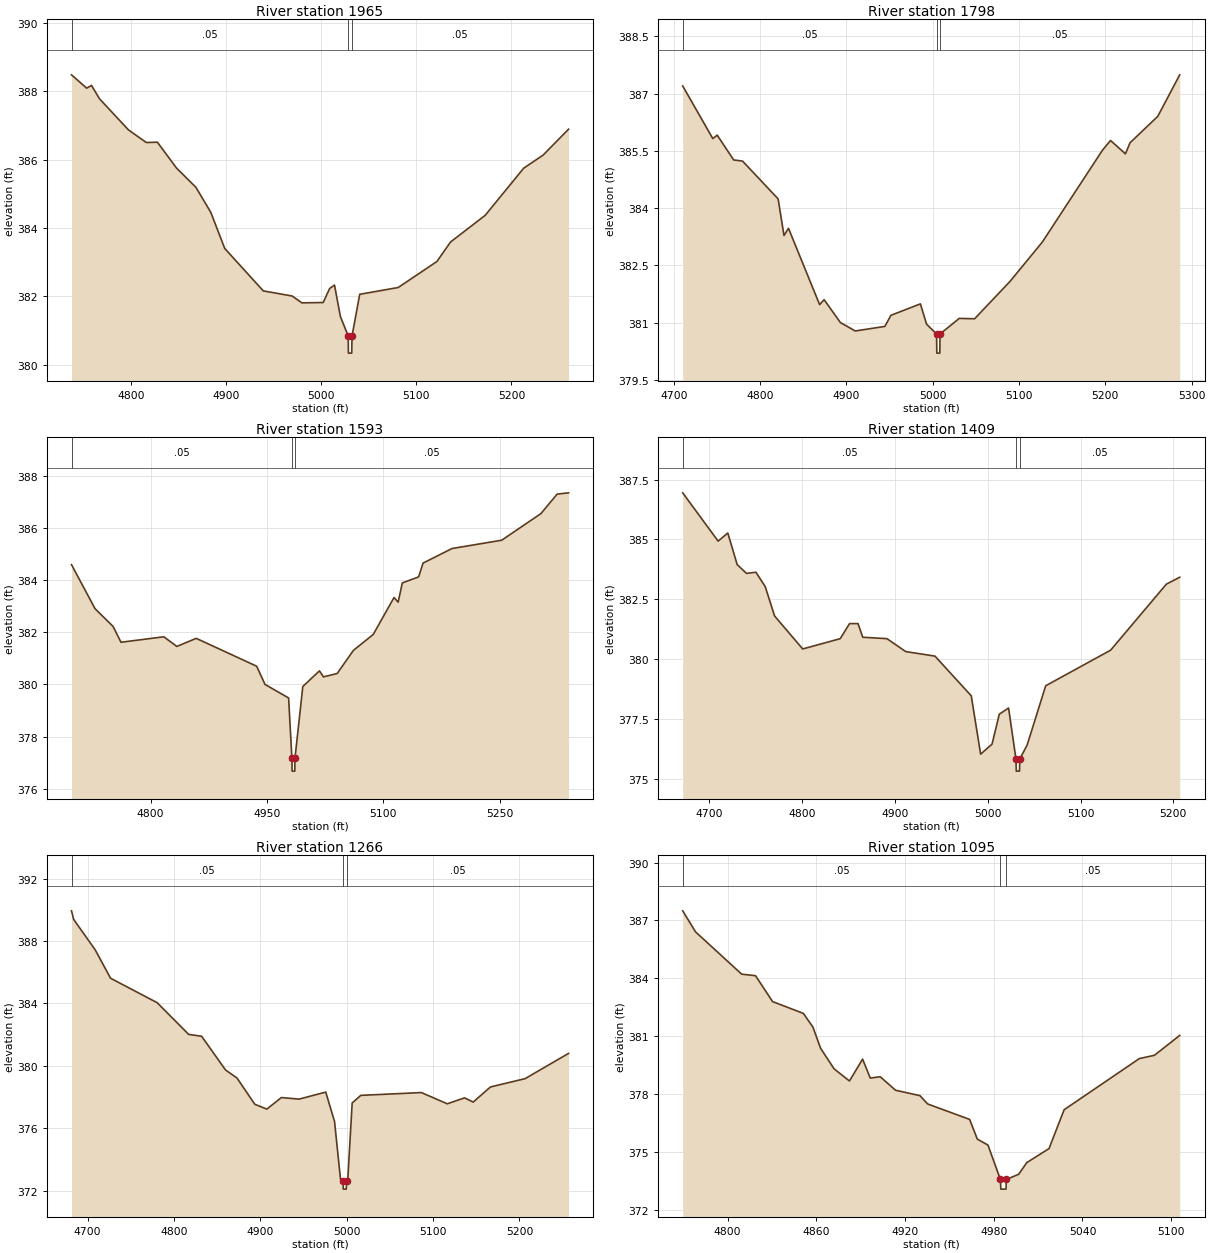
Type RM Length L Ch R = 1,1965,167,167,167
BEGIN DESCRIPTION:
Twin Creek2251964.89
END DESCRIPTION:
XS GIS Cut Line= 3
      2729966.91      6818908.72      2730225.14      6818868.24
      2730482.45      6818825.58
#Sta/Elev= 30
  4737.8  388.48  4753.7  388.09  4758.8  388.17  4767.2  387.78  4797.6  386.87
  4816.4  386.50  4828.0  386.51  4848.2  385.75  4868.5  385.19  4884.1  384.46
  4898.8  383.40  4939.3  382.16  4969.7  382.01  4979.8  381.81  5002.2  381.82
  5009.0  382.23  5014.1  382.33  5020.3  381.41  5028.5  380.84  5028.7  380.34
  5032.2  380.34  5032.5  380.84  5040.6  382.06  5081.1  382.26  5121.7  383.02
  5136.0  383.59  5172.4  384.37  5212.9  385.75  5233.2  386.13  5260.0  386.89
#Mann=3,-1,0
  4737.8    0.05       0  5028.5    0.05       0  5032.5    0.05       0
Bank Sta=5028.5,5032.5
Exp/Cntr=0.3,0.1

Type RM Length L Ch R = 1,1798,205,205,205
BEGIN DESCRIPTION:
Twin Creek2251798
END DESCRIPTION:
XS GIS Cut Line= 3
      2729998.65      6819084.80      2730280.51      6819014.57
      2730552.35      6818927.23
#Sta/Elev= 30
  4710.2  387.20  4745.1  385.82  4750.2  385.91  4769.3  385.26  4779.6  385.23
  4820.8  384.24  4827.6  383.28  4832.8  383.47  4868.9  381.47  4874.1  381.60
  4893.0  381.00  4910.2  380.78  4944.5  380.90  4951.5  381.19  4985.7  381.49
  4992.8  380.96  5004.4  380.70  5004.7  380.20  5008.2  380.20  5008.4  380.70
  5030.7  381.11  5048.5  381.10  5089.6  382.08  5127.0  383.11  5196.5  385.51
  5206.0  385.77  5223.3  385.42  5228.6  385.71  5260.7  386.40  5286.2  387.49
#Mann=3,-1,0
  4710.2    0.05       0  5004.4    0.05       0  5008.4    0.05       0
Bank Sta=5004.4,5008.4
Exp/Cntr=0.3,0.1

Type RM Length L Ch R = 1,1593,184,184,184
BEGIN DESCRIPTION:
Twin Creek2251592.73
END DESCRIPTION:
XS GIS Cut Line= 3
      2730064.03      6819263.75      2730356.73      6819192.70
      2730679.99      6819088.60
#Sta/Elev= 30
  4698.1  384.60  4728.4  382.91  4751.6  382.23  4761.9  381.62  4817.1  381.83
  4833.9  381.46  4858.9  381.77  4936.8  380.70  4947.6  380.00  4978.0  379.48
  4982.2  377.17  4982.5  376.67  4986.0  376.67  4986.2  377.17  4996.3  379.92
  5017.7  380.52  5023.0  380.29  5040.6  380.42  5061.6  381.31  5087.1  381.92
  5113.9  383.34  5119.2  383.16  5124.6  383.90  5145.6  384.13  5151.3  384.66
  5188.6  385.22  5252.7  385.54  5303.2  386.56  5324.2  387.31  5338.9  387.36
#Mann=3,-1,0
  4698.1    0.05       0  4982.2    0.05       0  4986.2    0.05       0
Bank Sta=4982.2,4986.2
Exp/Cntr=0.3,0.1

Type RM Length L Ch R = 1,1409,143,143,143
BEGIN DESCRIPTION:
Twin Creek2251409.22
END DESCRIPTION:
XS GIS Cut Line= 3
      2729997.85      6819310.26      2730325.37      6819354.32
      2730530.39      6819355.24
#Sta/Elev= 30
  4671.4  386.95  4709.6  384.93  4720.0  385.27  4730.1  383.95  4740.2  383.58
  4750.3  383.63  4760.3  383.03  4770.4  381.80  4800.7  380.42  4841.1  380.85
  4851.2  381.48  4860.3  381.48  4865.4  380.91  4891.5  380.85  4911.7  380.31
  4943.2  380.12  4982.3  378.46  4992.4  376.02  5004.7  376.44  5012.5  377.69
  5022.5  377.95  5030.5  375.81  5030.8  375.31  5034.3  375.31  5034.5  375.81
  5042.5  376.40  5062.5  378.88  5132.5  380.37  5192.5  383.13  5206.9  383.42
#Mann=3,-1,0
  4671.4    0.05       0  5030.5    0.05       0  5034.5    0.05       0
Bank Sta=5030.5,5034.5
Exp/Cntr=0.3,0.1

Type RM Length L Ch R = 1,1266,171,171,171
BEGIN DESCRIPTION:
Twin Creek2251266.28
END DESCRIPTION:
XS GIS Cut Line= 3
      2729949.33      6819405.24      2730260.73      6819477.49
      2730516.36      6819484.79
#Sta/Elev= 30
  4681.4  389.94  4683.9  389.39  4708.8  387.44  4726.6  385.62  4780.6  384.05
  4817.0  382.02  4832.0  381.90  4859.7  379.74  4873.0  379.22  4893.6  377.54
  4907.5  377.23  4924.4  377.97  4944.9  377.87  4975.7  378.32  4985.9  376.44
  4992.8  372.74  4995.8  372.60  4996.0  372.10  4999.5  372.10  4999.8  372.60
  5001.1  372.60  5006.3  377.62  5016.3  378.11  5086.4  378.29  5116.4  377.57
  5136.4  377.95  5146.4  377.68  5166.4  378.65  5206.4  379.18  5256.8  380.80
#Mann=3,-1,0
  4681.4    0.05       0  4995.8    0.05       0  4999.8    0.05       0
Bank Sta=4995.8,4999.8
Exp/Cntr=0.3,0.1

Type RM Length L Ch R = 1,1095,182,182,182
BEGIN DESCRIPTION:
Twin Creek2251094.88
END DESCRIPTION:
XS GIS Cut Line= 3
      2729947.65      6819551.10      2730171.24      6819615.88
      2730272.81      6819635.28
#Sta/Elev= 30
  4769.6  387.50  4778.3  386.41  4809.5  384.22  4818.9  384.14  4830.4  382.80
  4851.2  382.19  4857.7  381.48  4862.9  380.38  4872.0  379.32  4882.4  378.69
  4891.3  379.82  4896.5  378.84  4903.2  378.91  4913.6  378.21  4930.1  377.93
  4935.3  377.50  4963.7  376.70  4968.9  375.68  4976.1  375.37  4984.5  373.59
  4984.8  373.09  4988.3  373.09  4988.5  373.59  4996.9  373.86  5002.3  374.46
  5017.4  375.19  5027.6  377.20  5078.5  379.85  5088.7  380.02  5105.8  381.05
#Mann=3,-1,0
  4769.6    0.05       0  4984.5    0.05       0  4988.5    0.05       0
Bank Sta=4984.5,4988.5
Exp/Cntr=0.3,0.1

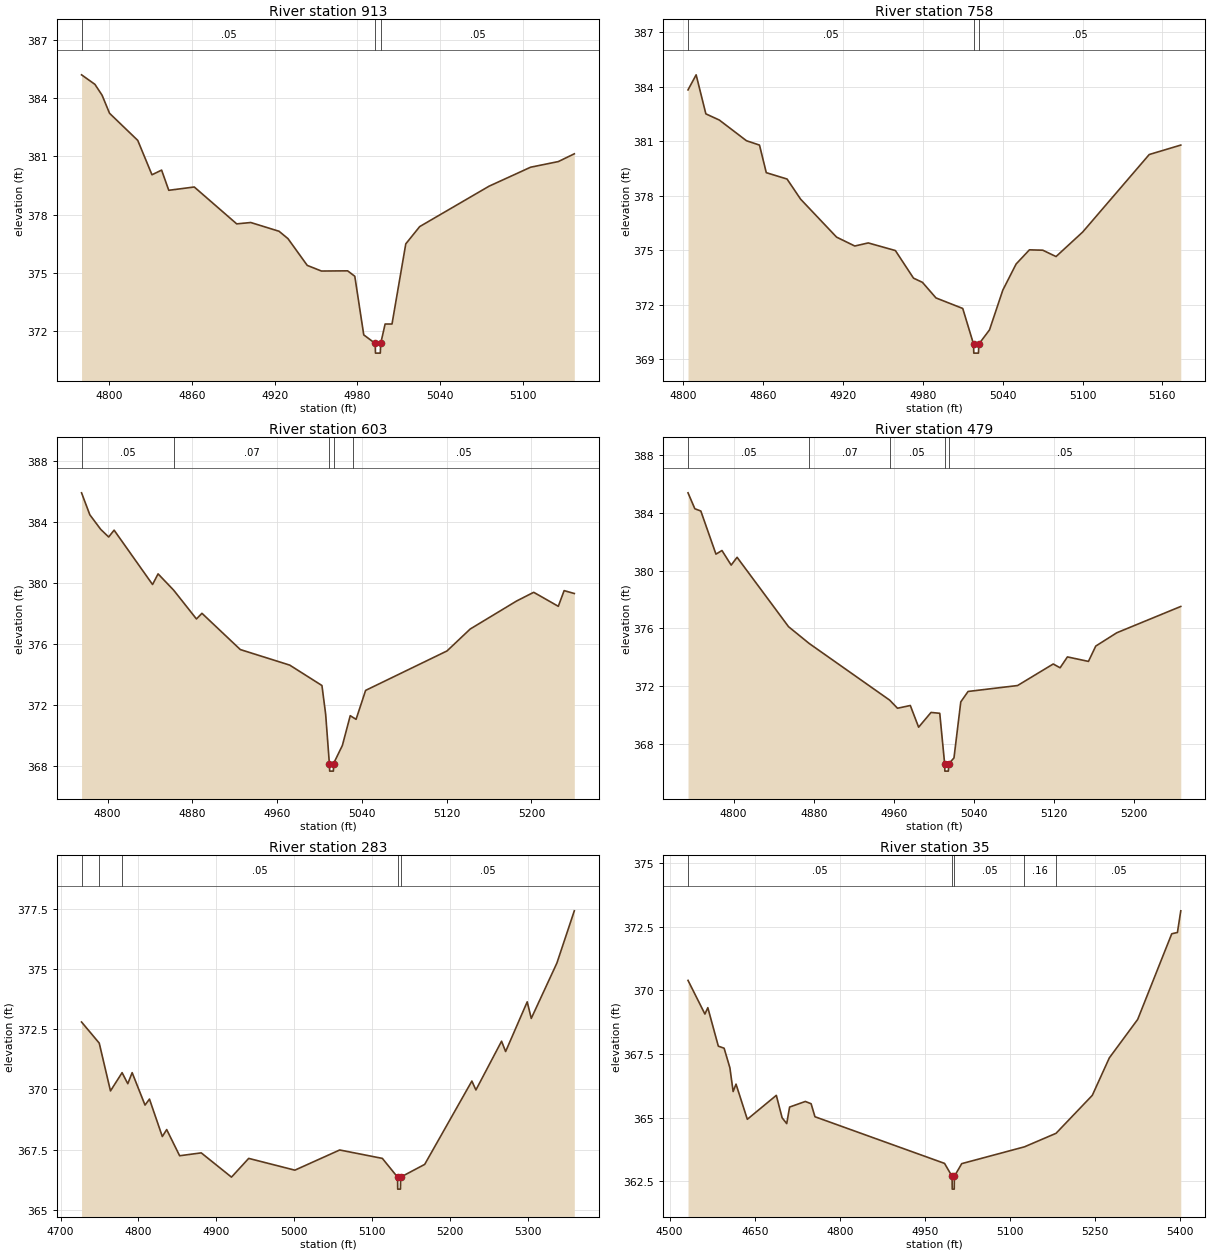
Type RM Length L Ch R = 1,913,155,155,155
BEGIN DESCRIPTION:
Twin Creek225912.89
END DESCRIPTION:
XS GIS Cut Line= 3
      2729856.17      6819712.81      2730071.17      6819761.16
      2730207.55      6819776.49
#Sta/Elev= 30
  4779.9  385.20  4789.6  384.71  4794.8  384.15  4800.2  383.22  4820.7  381.82
  4831.0  380.05  4838.0  380.29  4843.2  379.25  4861.7  379.42  4892.5  377.52
  4902.7  377.59  4923.2  377.14  4929.7  376.76  4943.7  375.38  4954.0  375.09
  4973.0  375.10  4978.2  374.82  4984.7  371.80  4993.0  371.36  4993.2  370.86
  4996.7  370.86  4997.0  371.36  5000.2  372.36  5005.2  372.36  5015.2  376.49
  5025.3  377.38  5075.6  379.46  5105.8  380.44  5125.9  380.73  5137.5  381.13
#Mann=3,-1,0
  4779.9    0.05       0  4993.0    0.05       0  4997.0    0.05       0
Bank Sta=4993,4997
Exp/Cntr=0.3,0.1

Type RM Length L Ch R = 1,758,155,155,155
BEGIN DESCRIPTION:
Twin Creek225758.33
END DESCRIPTION:
XS GIS Cut Line= 3
      2729802.85      6819855.30      2729994.63      6819890.98
      2730169.70      6819886.43
#Sta/Elev= 30
  4803.6  383.83  4809.7  384.66  4817.0  382.51  4827.1  382.17  4847.5  381.03
  4857.3  380.79  4862.4  379.27  4878.0  378.92  4888.2  377.81  4915.2  375.72
  4928.9  375.23  4939.0  375.40  4959.4  374.98  4973.0  373.46  4979.7  373.23
  4989.9  372.37  5010.0  371.79  5018.1  369.83  5018.3  369.33  5021.8  369.33
  5022.1  369.83  5030.1  370.61  5040.1  372.80  5050.1  374.24  5060.1  375.02
  5070.1  375.00  5080.1  374.65  5100.1  376.00  5150.1  380.27  5173.8  380.79
#Mann=3,-1,0
  4803.6    0.05       0  5018.1    0.05       0  5022.1    0.05       0
Bank Sta=5018.1,5022.1
Exp/Cntr=0.3,0.1

Type RM Length L Ch R = 1,603,124,124,124
BEGIN DESCRIPTION:
Twin Creek225602.82
END DESCRIPTION:
XS GIS Cut Line= 3
      2729768.41      6820072.70      2729985.74      6820018.93
      2730205.60      6819920.19
#Sta/Elev= 30
  4775.5  385.93  4783.3  384.49  4793.6  383.53  4801.1  383.03  4806.2  383.48
  4842.5  379.91  4847.7  380.61  4862.4  379.54  4883.9  377.65  4889.1  378.02
  4925.3  375.64  4971.9  374.62  5002.3  373.28  5005.8  371.40  5009.3  368.16
  5009.6  367.66  5013.1  367.66  5013.3  368.16  5021.6  369.35  5029.0  371.30
  5031.5  371.19  5034.5  371.06  5043.5  372.96  5120.3  375.55  5142.2  376.99
  5186.0  378.83  5202.1  379.40  5225.3  378.48  5230.8  379.51  5240.4  379.32
#Mann=5,-1,0
  4775.5    0.05       0  4862.4    0.07       0  5009.3    0.07       0
  5013.3    0.07       0  5031.5    0.05       0
Bank Sta=5009.3,5013.3
Exp/Cntr=0.3,0.1

Type RM Length L Ch R = 1,479,196,196,196
BEGIN DESCRIPTION:
Twin Creek225479.21
END DESCRIPTION:
XS GIS Cut Line= 3
      2729819.80      6820262.67      2730025.79      6820128.97
      2730194.66      6819949.35
#Sta/Elev= 30
  4754.4  385.38  4761.2  384.28  4767.2  384.12  4782.3  381.14  4788.3  381.39
  4797.5  380.38  4803.4  380.92  4854.8  376.12  4875.4  374.96  4955.8  371.04
  4963.6  370.48  4976.4  370.67  4984.7  369.17  4997.1  370.19  5005.8  370.13
  5010.7  366.63  5010.9  366.13  5014.4  366.13  5014.7  366.63  5020.0  367.04
  5026.8  370.92  5034.1  371.64  5083.5  372.05  5119.1  373.54  5126.0  373.28
  5133.3  374.03  5154.3  373.72  5161.6  374.78  5182.6  375.70  5246.5  377.52
#Mann=5,-1,0
  4754.4    0.05       0  4875.4    0.07       0  4955.8    0.05       0
  5010.7    0.05       0  5014.7    0.05       0
Bank Sta=5010.7,5014.7
Exp/Cntr=0.3,0.1

Type RM Length L Ch R = 1,283,248,248,248
BEGIN DESCRIPTION:
Twin Creek225282.97
END DESCRIPTION:
XS GIS Cut Line= 3
      2729901.69      6820404.88      2730142.77      6820280.65
      2730247.77      6819935.47
#Sta/Elev= 30
  4727.0  372.81  4749.7  371.93  4764.1  369.94  4779.0  370.70  4786.3  370.24
  4791.9  370.70  4808.4  369.35  4814.1  369.60  4830.6  368.04  4836.2  368.33
  4852.8  367.24  4880.5  367.36  4919.3  366.35  4941.4  367.13  5000.6  366.64
  5058.1  367.48  5112.8  367.13  5132.3  366.35  5132.5  365.85  5136.0  365.85
  5136.3  366.35  5167.1  366.88  5227.6  370.35  5232.8  369.98  5265.7  372.01
  5270.9  371.58  5298.6  373.65  5303.8  372.96  5336.6  375.26  5359.0  377.44
#Mann=5,-1,0
  4727.0    0.05       0  4749.7    0.07       0  4779.0    0.05       0
  5132.3    0.05       0  5136.3    0.05       0
Bank Sta=5132.3,5136.3
Exp/Cntr=0.3,0.1

Type RM Length L Ch R = 1,35,0,0,0
BEGIN DESCRIPTION:
Twin Creek22535.472
END DESCRIPTION:
XS GIS Cut Line= 3
      2729893.74      6820482.55      2730351.00      6820386.00
      2730346.46      6819985.06
#Sta/Elev= 30
  4532.5  370.39  4562.3  369.07  4567.4  369.32  4585.9  367.81  4596.1  367.73
  4606.3  366.96  4612.0  366.03  4617.1  366.32  4637.0  364.94  4688.1  365.88
  4698.3  365.00  4706.4  364.77  4711.5  365.42  4739.2  365.64  4749.4  365.55
  4756.2  365.04  4984.5  363.21  4997.8  362.70  4998.1  362.20  5001.6  362.20
  5001.8  362.70  5014.8  363.20  5125.4  363.86  5181.0  364.39  5244.9  365.88
  5274.9  367.35  5324.9  368.86  5384.9  372.22  5394.9  372.27  5400.8  373.12
#Mann=5,-1,0
  4532.5    0.05       0  4997.8    0.05       0  5001.8    0.05       0
  5125.4    0.16       0  5181.0    0.05       0
Bank Sta=4997.8,5001.8
Exp/Cntr=0.3,0.1

Chan Stop Cuts=-1