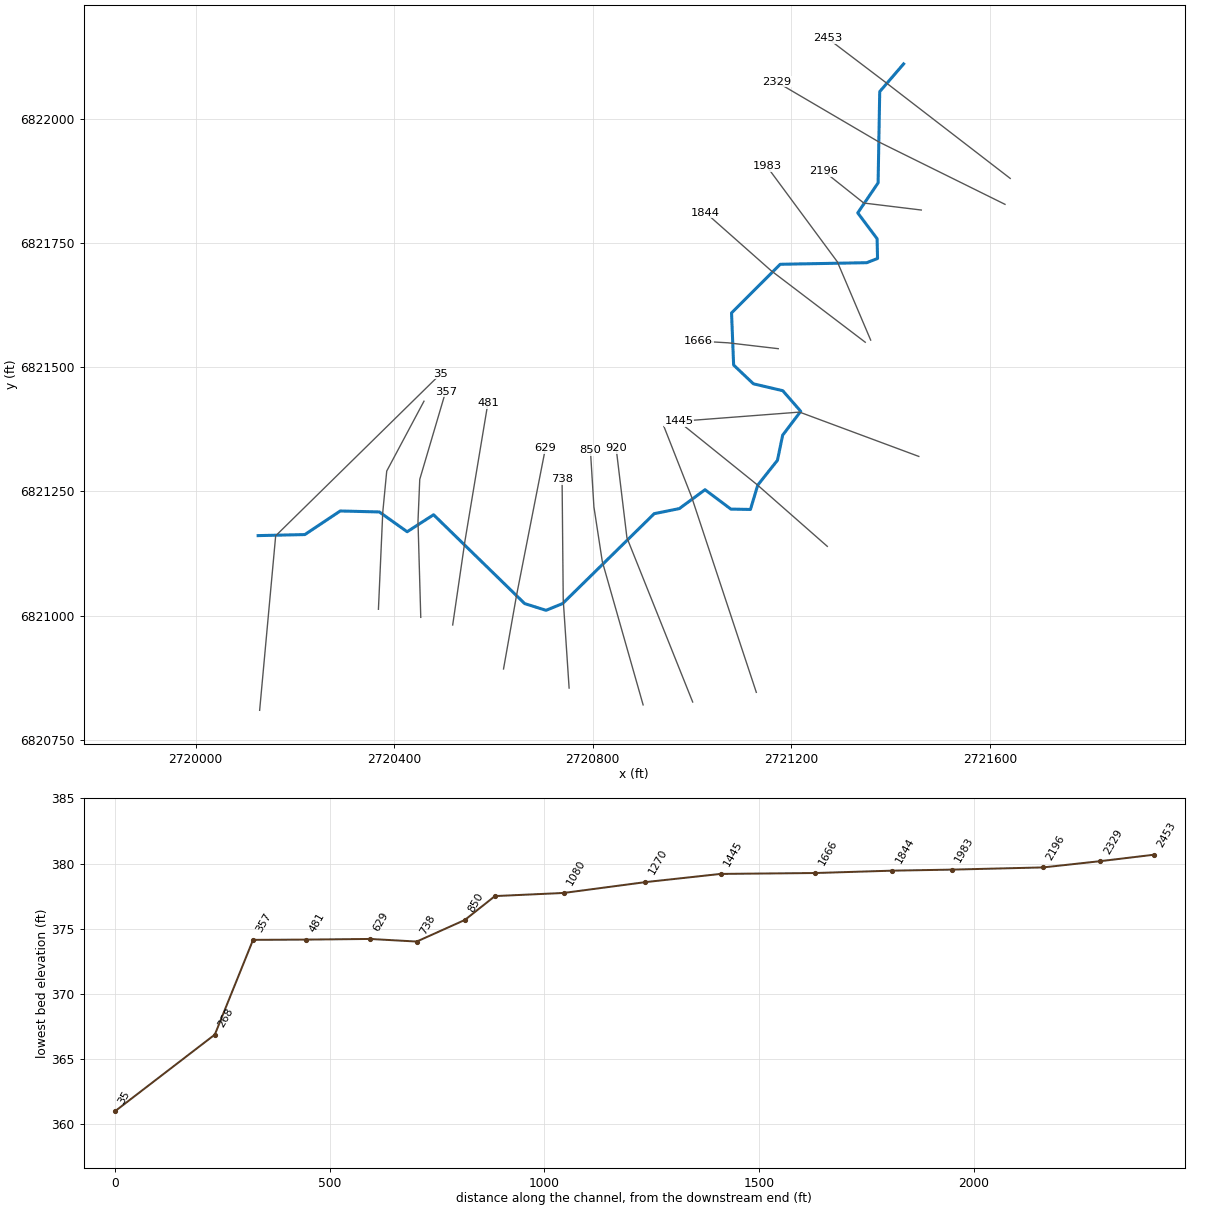
--- Twin Creek228.prj (project) ---

Proj Title=Twin Creek228 Base Level Engineering
Current Plan=p01
Default Exp/Contr=0.3,0.1
English Units
Geom File=g01
Flow File=f01
Plan File=p01
Y Axis Title=Elevation
X Axis Title(PF)=Main Channel Distance
X Axis Title(XS)=Station
BEGIN DESCRIPTION:
Twin Creek228
END DESCRIPTION:
DSS Export Rating Curves= 0
DSS Export Rating Curve Sorted= 0
DSS Export Volume Flow Curves= 0
DXF OffsetX= 0
DXF OffsetY= 0
DXF ScaleX= 1
DXF ScaleY= 10

--- Twin Creek228.p01 (plan) ---

Plan Title=Multiple Run
Short Identifier=Multiple
Geom File=g01
Flow File=f01
Subcritical Flow
K Sum by GR= 0
Std Step Tol= 0.01
Critical Tol= 0.01
Num of Std Step Trials= 20
Max Error Tol= 0.3
Flow Tol Ratio= 0.001
Split Flow NTrial= 30
Split Flow Tol= 0.02
Split Flow Ratio= 0.02
Log Output Level= 0
Friction Slope Method= 1
Unsteady Friction Slope Method= 2
Unsteady Bridges Friction Slope Method= 1
Parabolic Critical Depth
Global Vel Dist=  1 , 1 , 1
Global Log Level= 0
CheckData=True
Encroach Param= -1, 0, 0, 0
BEGIN DESCRIPTION:
Multiple Run
END DESCRIPTION:

--- Twin Creek228.f01 (steady flow) ---

Flow Title=Multiple
Number of Profiles=7
Profile Names=10-year,25-year,50-year,1pct_min,100-year,1pct_plu,500-year
River Rch & RM= Twin Creek228,Reach-1,2453
     105     124     137      76     151     301     182
Boundary for River Rch & Prof#=Twin Creek228,Reach-1,1
Up Type=0
Dn Type=3
Dn Slope=0.005
Boundary for River Rch & Prof#=Twin Creek228,Reach-1,2
Up Type=0
Dn Type=3
Dn Slope=0.005
Boundary for River Rch & Prof#=Twin Creek228,Reach-1,3
Up Type=0
Dn Type=3
Dn Slope=0.005
Boundary for River Rch & Prof#=Twin Creek228,Reach-1,4
Up Type=0
Dn Type=3
Dn Slope=0.005
Boundary for River Rch & Prof#=Twin Creek228,Reach-1,5
Up Type=0
Dn Type=3
Dn Slope=0.005
Boundary for River Rch & Prof#=Twin Creek228,Reach-1,6
Up Type=0
Dn Type=3
Dn Slope=0.005
Boundary for River Rch & Prof#=Twin Creek228,Reach-1,7
Up Type=0
Dn Type=3
Dn Slope=0.005

--- Twin Creek228.g01 (geometry) ---

Geom Title=Existing Conditions
Program Version=4.10

River Reach=Twin Creek228   ,Reach-1
Reach XY= 30
        2721426.        6822111.      2721377.89      6822055.22
      2721374.62      6821871.44      2721333.61      6821810.96
      2721372.61      6821758.91      2721373.49      6821719.11
      2721351.61      6821710.67      2721177.45      6821707.47
      2721079.45      6821609.51      2721083.64      6821504.55
      2721123.47      6821466.74      2721182.67      6821452.84
       2721218.8       6821411.3      2721182.41      6821363.31
      2721171.89       6821312.7      2721132.24      6821262.73
      2721117.52      6821213.66      2721078.02      6821214.42
      2721026.03      6821253.43      2720974.35      6821215.45
      2720923.71      6821205.19      2720739.21      6821024.11
      2720705.84      6821010.52      2720662.79      6821024.11
      2720479.34      6821203.01       2720426.1      6821168.81
      2720370.11      6821208.65      2720291.27      6821210.63
      2720220.13      6821163.11        2720126.        6821161.

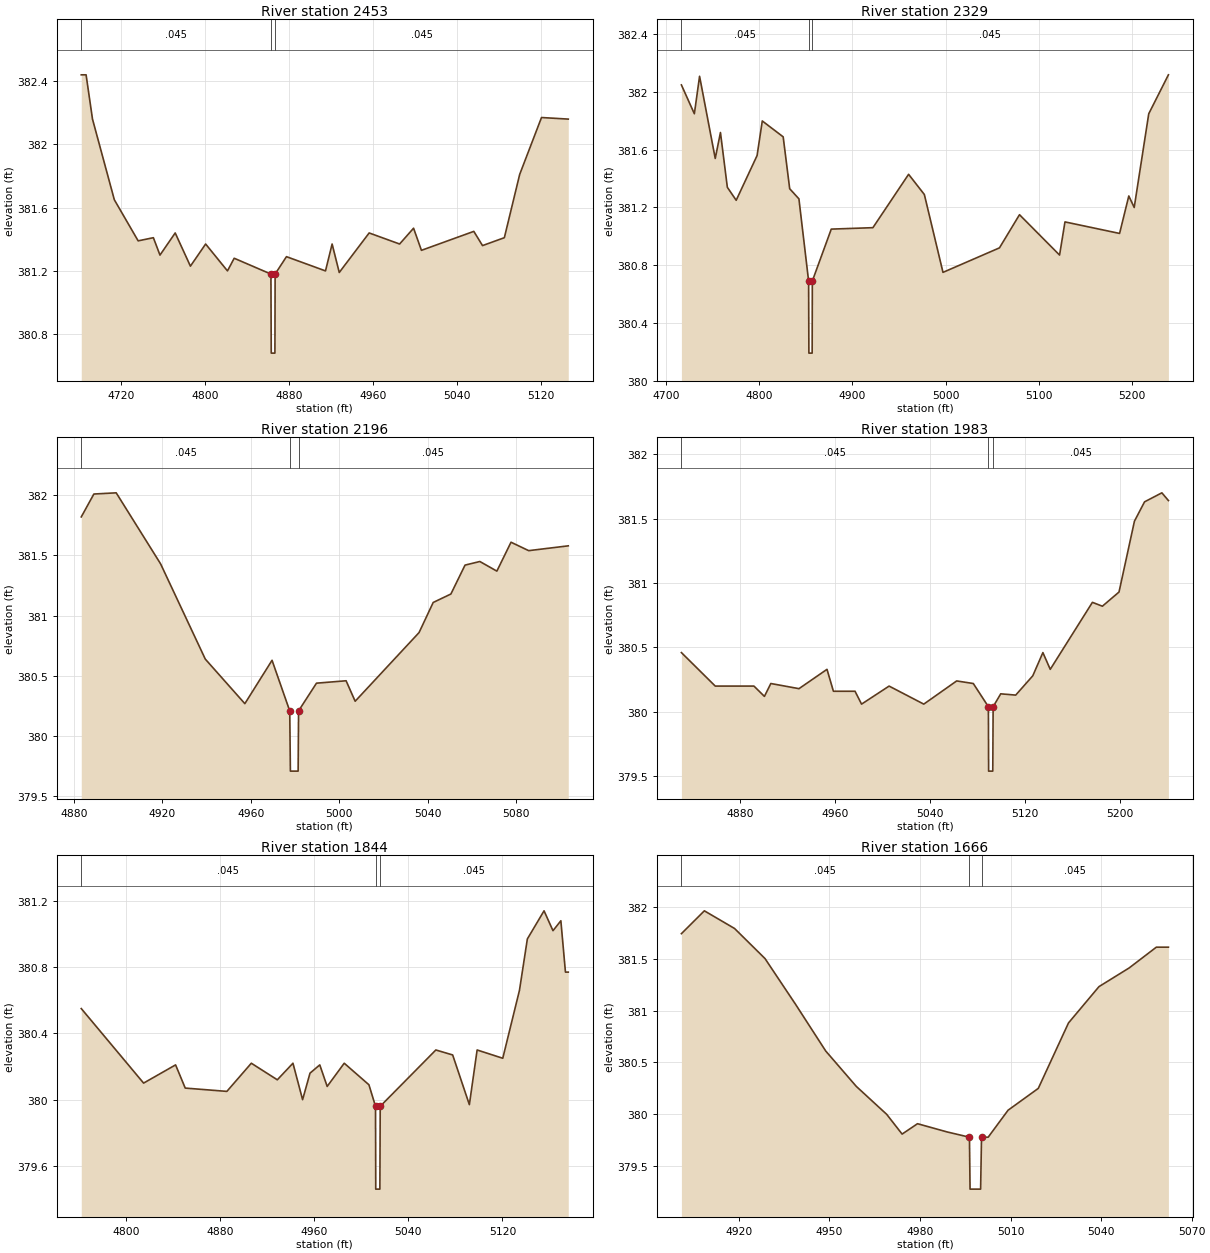
Type RM Length L Ch R = 1 ,2453    ,124,124,124
BEGIN DESCRIPTION:
Twin Creek2282421.069
END DESCRIPTION:
XS GIS Cut Line= 3
       2721640.7      6821880.43      2721388.92       6822074.5
      2721272.54      6822162.83
#Sta/Elev= 30
  4682.1  382.44  4686.7  382.44  4692.8  382.16  4713.6  381.65  4736.3  381.39
  4750.8  381.41  4757.1   381.3  4771.6  381.44  4786.1  381.23  4800.6  381.37
  4821.4   381.2  4827.8  381.28  4862.8  381.18  4863.1  380.68  4866.6  380.68
  4866.8  381.18  4877.6  381.29  4914.8   381.2  4921.1  381.37  4927.9  381.19
  4956.4  381.44  4985.4  381.37  4998.7  381.47  5006.2  381.33  5056.1  381.45
  5064.4  381.36  5085.2  381.41  5099.8  381.81  5120.6  382.17  5146.1  382.16
#Mann= 3 ,-1 , 0
  4682.1    .045       0  4862.8    .045       0  4866.8    .045       0
Bank Sta=4862.8,4866.8
XS Rating Curve= 0 ,0
Exp/Cntr=0.3,0.1

Type RM Length L Ch R = 1 ,2329    ,133,133,133
BEGIN DESCRIPTION:
Twin Creek2282244.15
END DESCRIPTION:
XS GIS Cut Line= 3
      2721630.18      6821828.22      2721376.06       6821953.9
      2721169.85      6822074.91
#Sta/Elev= 30
  4716.5  382.05  4730.4  381.85    4736  382.11  4752.8  381.54  4758.4  381.72
  4765.8  381.34  4775.3  381.25  4797.7  381.56  4803.3   381.8  4825.7  381.69
  4832.7  381.33  4842.6  381.26    4853  380.69  4853.3  380.19  4856.8  380.19
    4857  380.69  4877.3  381.05    4922  381.06  4960.3  381.43  4977.2  381.29
  4997.2  380.75  5057.8  380.92  5079.3  381.15  5122.3  380.87  5128.1   381.1
  5186.7  381.02  5196.6  381.28  5202.4   381.2    5218  381.85  5239.1  382.12
#Mann= 3 ,-1 , 0
  4716.5    .045       0    4853    .045       0    4857    .045       0
Bank Sta=4853,4857
XS Rating Curve= 0 ,0
Exp/Cntr=0.3,0.1

Type RM Length L Ch R = 1 ,2196    ,213,213,213
BEGIN DESCRIPTION:
Twin Creek2282069.91
END DESCRIPTION:
XS GIS Cut Line= 3
      2721461.64      6821816.74      2721345.79      6821830.82
       2721264.7      6821895.29
#Sta/Elev= 23
  4883.3  381.82    4889  382.01  4899.1  382.02  4919.2  381.43  4939.4  380.64
  4957.3  380.27  4969.6  380.63  4977.6  380.21  4977.9  379.71  4981.4  379.71
  4981.6  380.21  4989.7  380.44  5003.1  380.46  5007.2  380.29  5036.1  380.86
  5042.5  381.11  5050.5  381.18  5056.9  381.42  5063.6  381.45  5071.3  381.37
  5077.7  381.61  5085.7  381.54  5103.6  381.58
#Mann= 3 ,-1 , 0
  4883.3    .045       0  4977.6    .045       0  4981.6    .045       0
Bank Sta=4977.6,4981.6
XS Rating Curve= 0 ,0
Exp/Cntr=0.3,0.1

Type RM Length L Ch R = 1 ,1983    ,139,139,139
BEGIN DESCRIPTION:
Mapping XS 7f8cbac4
END DESCRIPTION:
XS GIS Cut Line= 3
      2721359.67      6821554.76      2721292.63      6821712.31
      2721150.69      6821904.45
#Sta/Elev= 30
  4830.4  380.46  4858.9   380.2  4891.5   380.2  4900.3  380.12  4905.7  380.22
  4929.4  380.18    4953  380.33  4958.4  380.16  4976.6  380.16  4982.1  380.06
  5005.3   380.2  5034.5  380.06  5062.2  380.24  5076.2  380.22  5088.9  380.04
  5089.1  379.54  5092.6  379.54  5092.9  380.04  5099.3  380.14  5111.9  380.13
  5126.3  380.28  5134.8  380.46    5141  380.33  5176.5  380.85  5184.9  380.82
  5198.9  380.93  5211.9  381.48  5220.4  381.63    5235   381.7  5240.5  381.64
#Mann= 3 ,-1 , 0
  4830.4    .045       0  5088.9    .045       0  5092.9    .045       0
Bank Sta=5088.9,5092.9
XS Rating Curve= 0 ,0
Exp/Cntr=0.3,0.1

Type RM Length L Ch R = 1 ,1844    ,178,178,178
BEGIN DESCRIPTION:
Twin Creek2281841.52
END DESCRIPTION:
XS GIS Cut Line= 3
      2721348.74      6821550.48       2721159.2      6821694.59
      2721027.38       6821811.2
#Sta/Elev= 30
  4761.9  380.55  4814.9   380.1  4842.1  380.21  4850.3  380.07  4885.7  380.05
  4906.5  380.22  4928.6  380.12  4941.9  380.22  4950.1     380  4956.4  380.16
  4964.7  380.21    4971  380.08  4985.5  380.22  5006.5  380.09  5012.1  379.96
  5012.3  379.46  5015.8  379.46  5016.1  379.96  5063.4   380.3  5077.7  380.27
  5091.9  379.97  5098.5   380.3  5120.3  380.25  5134.5  380.66  5141.2  380.97
  5155.4  381.14    5163  381.02  5169.7  381.08  5173.6  380.77    5176  380.77
#Mann= 3 ,-1 , 0
  4761.9    .045       0  5012.1    .045       0  5016.1    .045       0
Bank Sta=5012.1,5016.1
XS Rating Curve= 0 ,0
Exp/Cntr=0.3,0.1

Type RM Length L Ch R = 1 ,1666    ,221,221,221
BEGIN DESCRIPTION:
Twin Creek2281666.15
END DESCRIPTION:
XS GIS Cut Line= 3
       2721173.5      6821537.49       2721072.6      6821549.29
      2721012.99      6821552.76
#Sta/Elev= 23
    4901  381.74  4908.6  381.96  4918.6  381.79  4928.7   381.5  4938.8  381.06
  4948.8  380.61  4958.9  380.27    4969     380  4974.1  379.81  4979.2  379.91
  4989.1  379.83  4996.4  379.78  4996.6  379.28  5000.1  379.28  5000.4  379.78
  5002.6  379.78  5009.2  380.04  5019.2  380.25  5029.2  380.88  5039.3  381.23
  5049.3  381.41  5058.3  381.61  5062.3  381.61
#Mann= 3 ,-1 , 0
    4901    .045       0  4996.4    .045       0  5000.4    .045       0
Bank Sta=4996.4,5000.4
XS Rating Curve= 0 ,0
Exp/Cntr=0.3,0.1

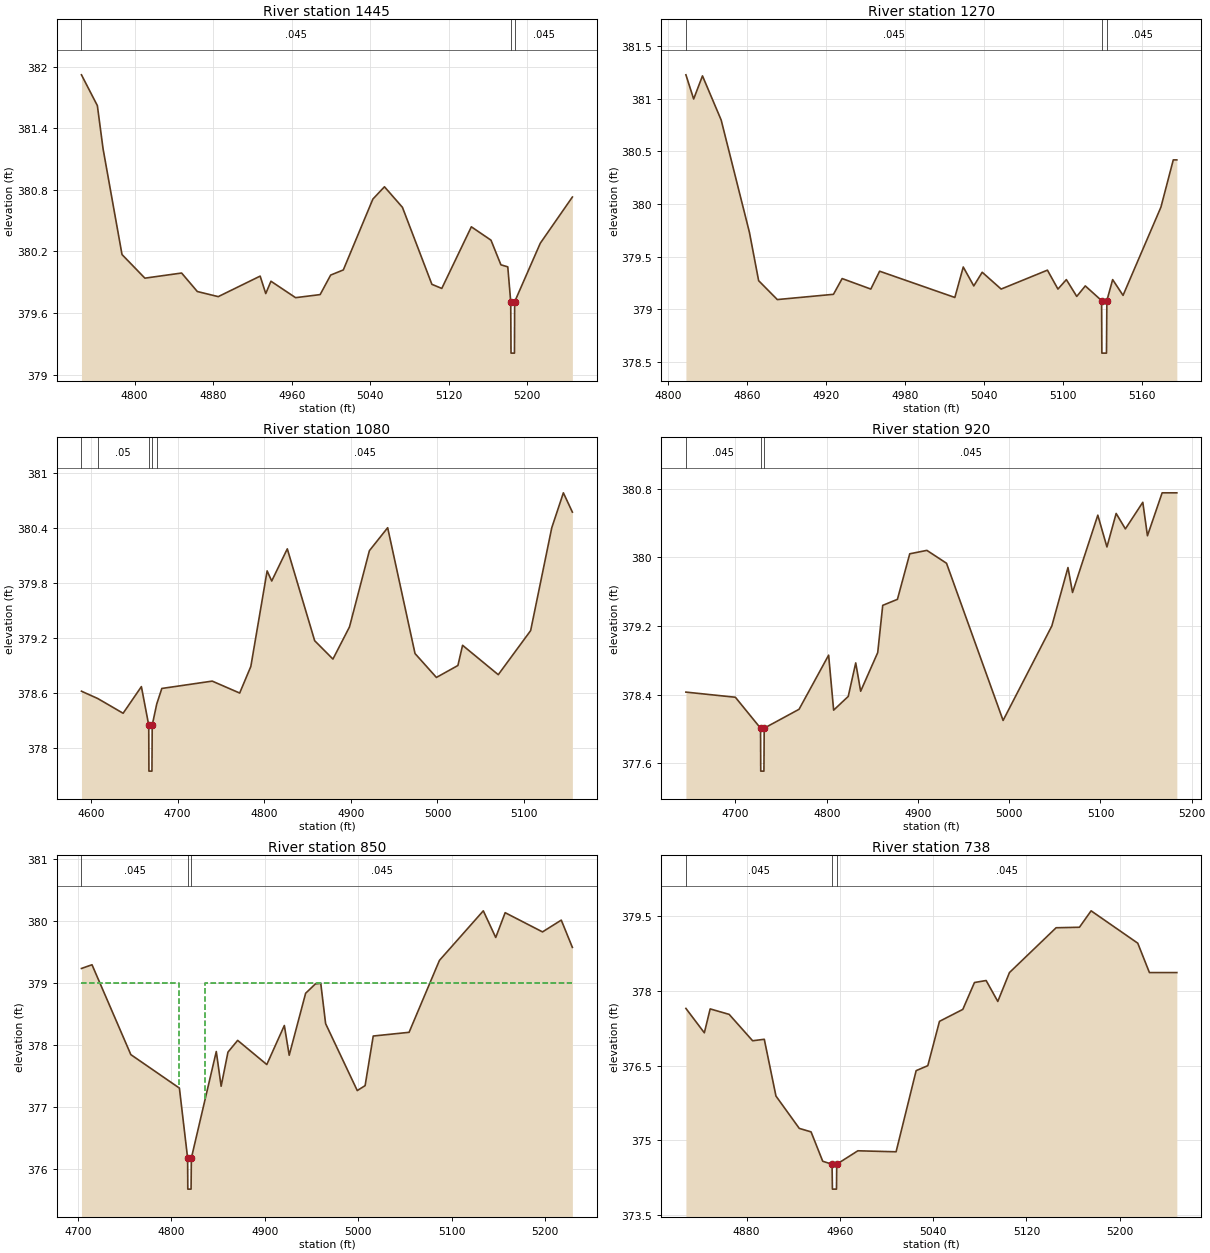
Type RM Length L Ch R = 1 ,1445    ,175,175,175
BEGIN DESCRIPTION:
Twin Creek2281446.01
END DESCRIPTION:
XS GIS Cut Line= 3
       2721456.6      6821320.49       2721216.4      6821409.76
      2720973.36      6821391.13
#Sta/Elev= 30
  4745.9  381.92  4762.1  381.62  4767.9   381.2  4787.2  380.17  4810.5  379.94
  4847.9  379.99  4863.9  379.81  4885.2  379.76  4927.9  379.96  4933.6  379.79
  4938.9  379.91    4964  379.75    4989  379.78  4999.7  379.97  5012.6  380.02
  5042.7  380.71  5054.5  380.83  5072.8  380.63  5102.8  379.88  5112.9  379.84
    5143  380.44    5163  380.31  5173.1  380.07  5180.1  380.05  5183.1  379.71
  5183.4  379.21  5186.9  379.21  5187.1  379.71  5213.2  380.28  5245.9  380.73
#Mann= 3 ,-1 , 0
  4745.9    .045       0  5183.1    .045       0  5187.1    .045       0
Bank Sta=5183.1,5187.1
XS Rating Curve= 0 ,0
Exp/Cntr=0.3,0.1

Type RM Length L Ch R = 1 ,1270    ,190,190,190
BEGIN DESCRIPTION:
Twin Creek2281269.98
END DESCRIPTION:
XS GIS Cut Line= 3
      2721272.32      6821139.35      2721130.67      6821263.81
      2720986.83      6821379.74
#Sta/Elev= 30
  4813.4  381.23  4819.3     381    4826  381.22  4840.2   380.8  4861.7  379.73
  4868.7  379.27  4882.9  379.09  4925.6  379.14  4932.2  379.29    4954  379.19
  4960.7  379.36  5017.9  379.11  5024.3   379.4  5032.3  379.22  5038.7  379.35
  5053.1  379.19  5088.3  379.37  5096.3  379.19  5102.7  379.28  5110.6  379.12
  5117.1  379.22  5129.5  379.08  5129.7  378.58  5133.2  378.58  5133.5  379.08
  5137.9  379.28  5145.8  379.13  5174.6  379.97    5184  380.42  5186.7  380.42
#Mann= 3 ,-1 , 0
  4813.4    .045       0  5129.5    .045       0  5133.5    .045       0
Bank Sta=5129.5,5133.5
XS Rating Curve= 0 ,0
Exp/Cntr=0.3,0.1

Type RM Length L Ch R = 1 ,1080    ,160,160,160
BEGIN DESCRIPTION:
Twin Creek2281079.5
END DESCRIPTION:
XS GIS Cut Line= 3
      2721129.34      6820845.34      2720998.95      6821239.11
      2720943.31      6821380.67
#Sta/Elev= 30
  4588.9  378.62  4607.8  378.54    4637  378.38  4658.1  378.67  4666.6  378.25
  4666.8  377.75  4670.3  377.75  4670.6  378.25  4675.8  378.48  4681.7  378.65
  4739.9  378.73  4771.6   378.6  4784.5  378.89  4803.3  379.93  4808.6  379.82
  4826.6  380.17  4858.2  379.17  4879.3  378.97  4898.4  379.32  4921.4  380.15
  4942.5   380.4  4974.1  379.03  4998.8  378.77  5023.6   378.9    5029  379.12
  5070.2   378.8  5107.6  379.28    5132   380.4  5145.4  380.78  5155.8  380.57
#Mann= 5 ,-1 , 0
  4588.9    .045       0  4607.8     .05       0  4666.6    .045       0
  4670.6     .05       0  4675.8    .045       0
Bank Sta=4666.6,4670.6
XS Rating Curve= 0 ,0
Exp/Cntr=0.3,0.1

Type RM Length L Ch R = 1 ,920     ,70,70,70
BEGIN DESCRIPTION:
Twin Creek228920.4
END DESCRIPTION:
XS GIS Cut Line= 3
      2721001.19      6820825.84      2720868.75      6821156.72
      2720847.03      6821337.02
#Sta/Elev= 30
  4645.7  378.43  4699.9  378.37  4727.5  378.01  4727.7  377.51  4731.2  377.51
  4731.5  378.01  4769.7  378.23  4802.1  378.86  4807.6  378.22  4823.6  378.38
  4831.8  378.77  4837.2  378.44  4855.9  378.89  4861.4  379.44  4877.5  379.51
    4891  380.04  4909.8  380.08  4931.3  379.93  4993.3   378.1  5046.7   379.2
  5064.4  379.88  5069.4  379.59  5097.1  380.49  5107.1  380.12  5117.2  380.51
  5127.3  380.33  5146.4  380.64  5151.5  380.25  5167.6  380.75  5183.7  380.75
#Mann= 3 ,-1 , 0
  4645.7    .045       0  4727.5    .045       0  4731.5    .045       0
Bank Sta=4727.5,4731.5
XS Rating Curve= 0 ,0
Exp/Cntr=0.3,0.1

Type RM Length L Ch R = 1 ,850     ,112,112,112
BEGIN DESCRIPTION:
Twin Creek228850.48
END DESCRIPTION:
XS GIS Cut Line= 4
      2720901.36      6820820.08      2720819.15      6821108.81
      2720802.27      6821218.82      2720795.21       6821332.9
#Sta/Elev= 30
  4703.6  379.24  4714.9   379.3  4756.5  377.85  4808.5  377.31  4817.3  376.18
  4817.5  375.68    4821  375.68  4821.3  376.18    4848   377.9  4853.2  377.34
  4860.5  377.89  4870.9  378.08  4902.1  377.69  4920.9  378.32  4926.1  377.84
  4943.7  378.84  4954.1  378.99  4959.9     379  4965.1  378.35    4999  377.27
  5007.4  377.35  5016.1  378.15  5054.5  378.21    5087  379.37    5134  380.17
  5147.3  379.74  5157.4  380.14  5197.4  379.83  5217.5  380.02  5229.4  379.58
#Mann= 3 ,-1 , 0
  4703.6    .045       0  4817.3    .045       0  4821.3    .045       0
#XS Ineff= 2 , 0
       0    4808     379    4836       0     379
Permanent Ineff=
       F       F
Bank Sta=4817.3,4821.3
XS Rating Curve= 0 ,0
Exp/Cntr=0.3,0.1

Type RM Length L Ch R = 1 ,738     ,109,109,109
BEGIN DESCRIPTION:
Twin Creek228738.07
END DESCRIPTION:
XS GIS Cut Line= 3
       2720752.3      6820853.97      2720740.46      6821031.65
      2720738.14      6821274.47
#Sta/Elev= 30
    4828  377.65  4843.8  377.16  4848.8  377.64  4865.1  377.53  4885.2     377
  4895.2  377.03  4905.2  375.89  4925.2  375.24  4935.3  375.17  4945.3  374.58
  4953.3  374.52  4953.6  374.02  4957.1  374.02  4957.3  374.52  4975.4  374.79
  5008.2  374.77  5025.4   376.4  5035.4   376.5  5045.4  377.39  5065.4  377.63
  5075.4  378.17  5085.4  378.21  5095.4  377.79  5105.4  378.37  5145.4  379.27
  5165.4  379.28  5175.4  379.61  5215.4  378.96  5225.4  378.37  5248.9  378.37
#Mann= 3 ,-1 , 0
    4828    .045       0  4953.3    .045       0  4957.3    .045       0
Bank Sta=4953.3,4957.3
XS Rating Curve= 0 ,0
Exp/Cntr=0.3,0.1

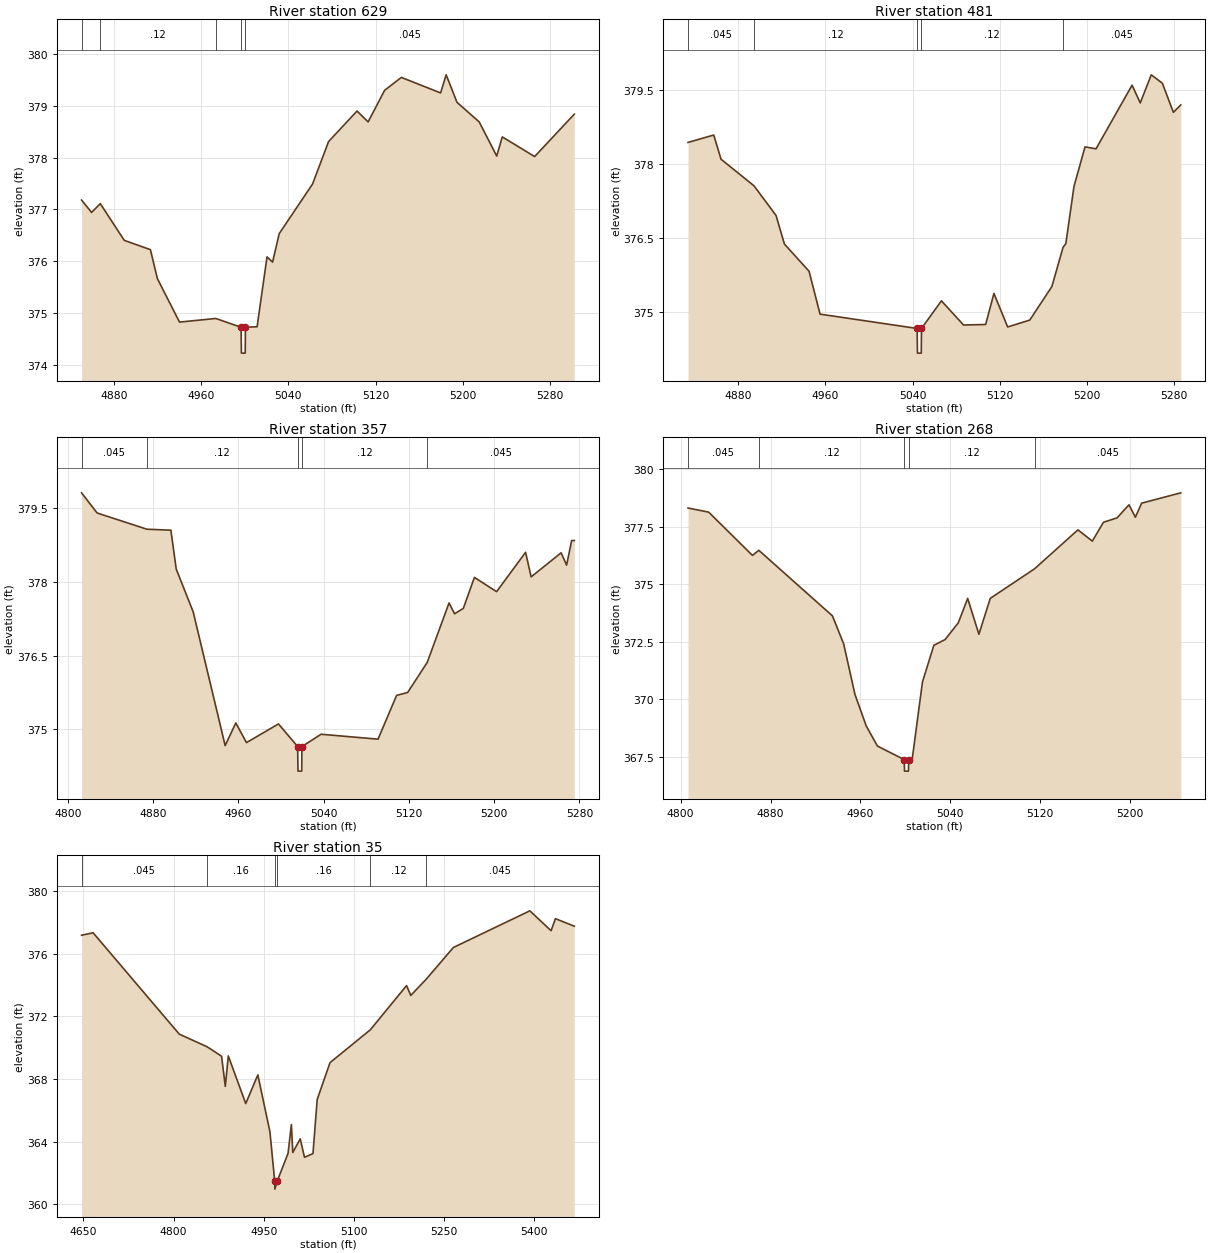
Type RM Length L Ch R = 1 ,629     ,148,148,148
BEGIN DESCRIPTION:
Twin Creek228629.46
END DESCRIPTION:
XS GIS Cut Line= 3
      2720620.21      6820892.44      2720646.53      6821041.16
      2720704.58      6821336.68
#Sta/Elev= 30
  4850.2  377.18  4859.4  376.94  4867.4  377.11  4889.4   376.4  4913.4  376.22
  4919.8  375.66  4940.1  374.82  4973.4  374.89  4996.6  374.72  4996.9  374.22
  5000.4  374.22  5000.6  374.72  5011.3  374.73  5020.4  376.08  5025.5  375.98
  5031.6  376.53  5062.2  377.49  5076.9  378.31    5103   378.9  5113.2  378.69
  5128.3   379.3  5143.7  379.55  5179.7  379.25  5184.8   379.6  5194.7  379.07
  5215.1  378.69  5231.2  378.03  5236.3   378.4    5266  378.02  5302.4  378.84
#Mann= 5 ,-1 , 0
  4850.2    .045       0  4867.4     .12       0  4973.4    .045       0
  4996.6    .045       0  5000.6    .045       0
Bank Sta=4996.6,5000.6
XS Rating Curve= 0 ,0
Exp/Cntr=0.3,0.1

Type RM Length L Ch R = 1 ,481     ,124,124,124
BEGIN DESCRIPTION:
Twin Creek228481.02
END DESCRIPTION:
XS GIS Cut Line= 3
      2720517.84      6820981.03      2720542.57      6821150.45
      2720588.73      6821427.72
#Sta/Elev= 30
  4833.9  378.44  4857.5  378.59  4864.2   378.1  4894.5  377.56  4914.7  376.96
  4922.4  376.38    4945  375.83  4955.1  374.96  5044.2  374.67  5044.5  374.17
    5048  374.17  5048.2  374.67  5066.5  375.23  5086.8  374.74  5107.1  374.75
  5114.7  375.38  5127.3   374.7  5147.6  374.84  5167.9  375.52  5178.1  376.31
  5180.7  376.39  5188.2  377.55  5198.3  378.35  5208.4  378.31  5241.5   379.6
    5249  379.24  5259.1  379.81  5269.3  379.64  5279.4  379.05  5286.2   379.2
#Mann= 5 ,-1 , 0
  4833.9    .045       0  4894.5     .12       0  5044.2     .07       0
  5048.2     .12       0  5178.1    .045       0
Bank Sta=5044.2,5048.2
XS Rating Curve= 0 ,0
Exp/Cntr=0.3,0.1

Type RM Length L Ch R = 1 ,357     ,89,89,89
BEGIN DESCRIPTION:
Twin Creek228357.24
END DESCRIPTION:
XS GIS Cut Line= 4
      2720453.54      6820996.37      2720447.95      6821189.82
       2720451.5      6821274.33      2720503.64      6821450.88
#Sta/Elev= 30
    4813  379.81  4827.6   379.4  4874.3  379.07  4896.8  379.05  4901.8  378.26
  4917.7  377.39  4947.7  374.67  4957.7  375.13  4967.7  374.73  4997.7  375.11
  5015.7  374.65    5016  374.15  5019.5  374.15  5019.7  374.65  5037.7   374.9
  5091.1   374.8  5108.5  375.69  5118.9  375.75  5137.2  376.36  5157.7  377.57
  5162.9  377.35  5171.1  377.46  5181.5  378.09  5202.3   377.8  5229.5   378.6
  5234.7   378.1  5262.8  378.59    5268  378.34  5272.7  378.84  5275.2  378.84
#Mann= 5 ,-1 , 0
    4813    .045       0  4874.3     .12       0  5015.7     .07       0
  5019.7     .12       0  5137.2    .045       0
Bank Sta=5015.7,5019.7
XS Rating Curve= 0 ,0
Exp/Cntr=0.3,0.1

Type RM Length L Ch R = 1 ,268     ,233,233,233
BEGIN DESCRIPTION:
Twin Creek228268.02
END DESCRIPTION:
XS GIS Cut Line= 4
      2720368.27      6821012.64      2720376.98      6821207.66
      2720384.97      6821290.97        2720460.      6821431.71
#Sta/Elev= 30
  4806.6  378.32    4825  378.14  4863.9  376.26  4869.6  376.48  4935.1  373.63
  4945.1  372.41  4955.1  370.22  4965.1  368.85  4975.1  367.97    4999  367.38
  4999.2  366.88  5002.7  366.88    5003  367.38    5006  367.38  5015.2  370.76
  5025.3  372.35  5035.3   372.6  5047.1  373.33  5055.4  374.39  5065.4  372.83
  5075.5  374.39    5115  375.68  5153.5  377.37  5166.3  376.88  5176.2   377.7
  5188.3  377.89  5198.9  378.46  5204.6  377.92  5210.2  378.53    5245  378.98
#Mann= 5 ,-1 , 0
  4806.6    .045       0  4869.6     .12       0    4999     .07       0
    5003     .12       0    5115    .045       0
Bank Sta=4999,5003
XS Rating Curve= 0 ,0
Exp/Cntr=0.3,0.1

Type RM Length L Ch R = 1 ,35      ,0,0,0
BEGIN DESCRIPTION:
Twin Creek22835.31
END DESCRIPTION:
XS GIS Cut Line= 3
      2720129.03      6820809.16      2720161.31      6821160.58
       2720494.1      6821487.35
#Sta/Elev= 30
  4647.1  377.18  4666.3  377.34  4809.6  370.87  4856.1  370.06  4879.9  369.46
  4886.1  367.54  4891.1  369.48  4920.1  366.44  4940.2  368.27  4960.3  364.64
  4968.3  361.48  4968.5  360.98  4972.3  361.48  4990.4  363.26    4996   365.1
  4998.3  363.32  5010.7  364.19  5017.8  363.01  5031.9  363.25  5038.9   366.7
  5060.2  369.05  5127.3  371.15  5187.5  373.97  5194.5  373.34  5220.5  374.39
  5265.3   376.4  5392.5  378.74  5427.8  377.47    5435  378.24  5466.4  377.76
#Mann= 6 ,-1 , 0
  4647.1    .045       0  4856.1     .16       0  4968.3     .07       0
  4972.3     .16       0  5127.3     .12       0  5220.5    .045       0
Bank Sta=4968.3,4972.3
XS Rating Curve= 0 ,0
Exp/Cntr=0.3,0.1

Chan Stop Cuts=-1
Use User Specified Reach Order=0
Composite Channel Slope=5