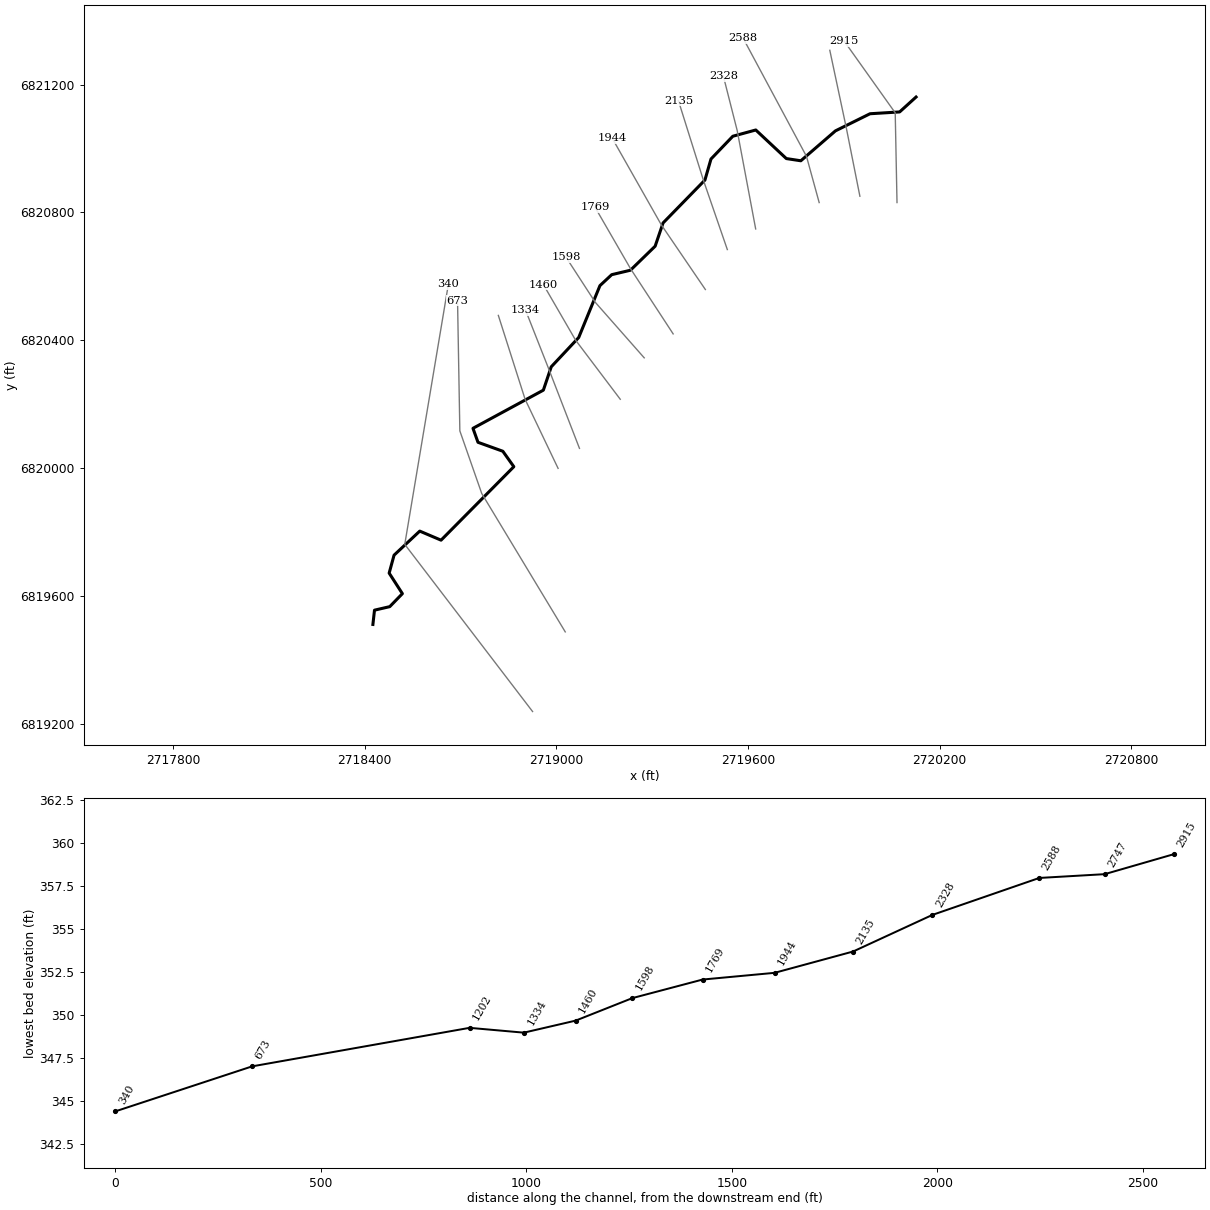
--- Twin Creek229.prj (project) ---

Proj Title=Twin Creek229 Base Level Engineering
Current Plan=p01
Default Exp/Contr=0.3,0.1
English Units
Geom File=g01
Flow File=f01
Plan File=p01
BEGIN DESCRIPTION:
Twin Creek229
END DESCRIPTION:

--- Twin Creek229.p01 (plan) ---

Plan Title=Multiple Run
Short Identifier=Multiple
Geom File=g01
Flow File=f01
Subcritical Flow
K Sum by GR= 0
Std Step Tol= 0.01
Critical Tol= 0.01
Num of Std Step Trials= 20
Max Error Tol= 0.3
Flow Tol Ratio= 0.001
Split Flow NTrial= 30
Split Flow Tol= 0.02
Split Flow Ratio= 0.02
Log Output Level= 0
Friction Slope Method= 1
Unsteady Friction Slope Method= 2
Unsteady Bridges Friction Slope Method= 1
Parabolic Critical Depth
Global Vel Dist=  1 , 1 , 1
Global Log Level= 0
CheckData=True
Encroach Param= -1, 0, 0, 0
BEGIN DESCRIPTION:
Multiple Run
END DESCRIPTION:

--- Twin Creek229.f01 (steady flow) ---

Flow Title=Multiple
Number of Profiles=7
Profile Names=10-year,25-year,50-year,1pct_min,100-year,1pct_plu,500-year
River Rch & RM= Twin Creek229,Reach-1,2915
     379     493     582     342     682    1361     935
Boundary for River Rch & Prof#=Twin Creek229,Reach-1,1
Up Type=0
Dn Type=3
Dn Slope=0.005
Boundary for River Rch & Prof#=Twin Creek229,Reach-1,2
Up Type=0
Dn Type=3
Dn Slope=0.005
Boundary for River Rch & Prof#=Twin Creek229,Reach-1,3
Up Type=0
Dn Type=3
Dn Slope=0.005
Boundary for River Rch & Prof#=Twin Creek229,Reach-1,4
Up Type=0
Dn Type=3
Dn Slope=0.005
Boundary for River Rch & Prof#=Twin Creek229,Reach-1,5
Up Type=0
Dn Type=3
Dn Slope=0.005
Boundary for River Rch & Prof#=Twin Creek229,Reach-1,6
Up Type=0
Dn Type=3
Dn Slope=0.005
Boundary for River Rch & Prof#=Twin Creek229,Reach-1,7
Up Type=0
Dn Type=3
Dn Slope=0.005

--- Twin Creek229.g01 (geometry) ---

Geom Title=Existing Conditions

River Reach=Twin Creek229,Reach-1
Reach XY= 30
      2720126.00      6821161.00      2720074.60      6821114.39
      2719981.95      6821108.70      2719873.71      6821055.15
      2719765.36      6820961.56      2719719.96      6820968.48
      2719624.35      6821057.89      2719552.49      6821038.32
      2719484.15      6820967.07      2719465.22      6820901.32
      2719334.16      6820767.05      2719309.36      6820694.29
      2719232.05      6820619.16      2719173.46      6820605.25
      2719136.63      6820571.00      2719070.15      6820408.71
      2718984.18      6820317.02      2718959.51      6820243.95
      2718739.22      6820124.58      2718754.93      6820080.83
      2718832.67      6820052.84      2718867.11      6820004.49
      2718639.33      6819774.65      2718572.65      6819803.00
      2718492.23      6819727.74      2718476.89      6819671.64
      2718518.30      6819607.36      2718478.77      6819566.71
      2718431.01      6819555.67      2718426.00      6819511.00

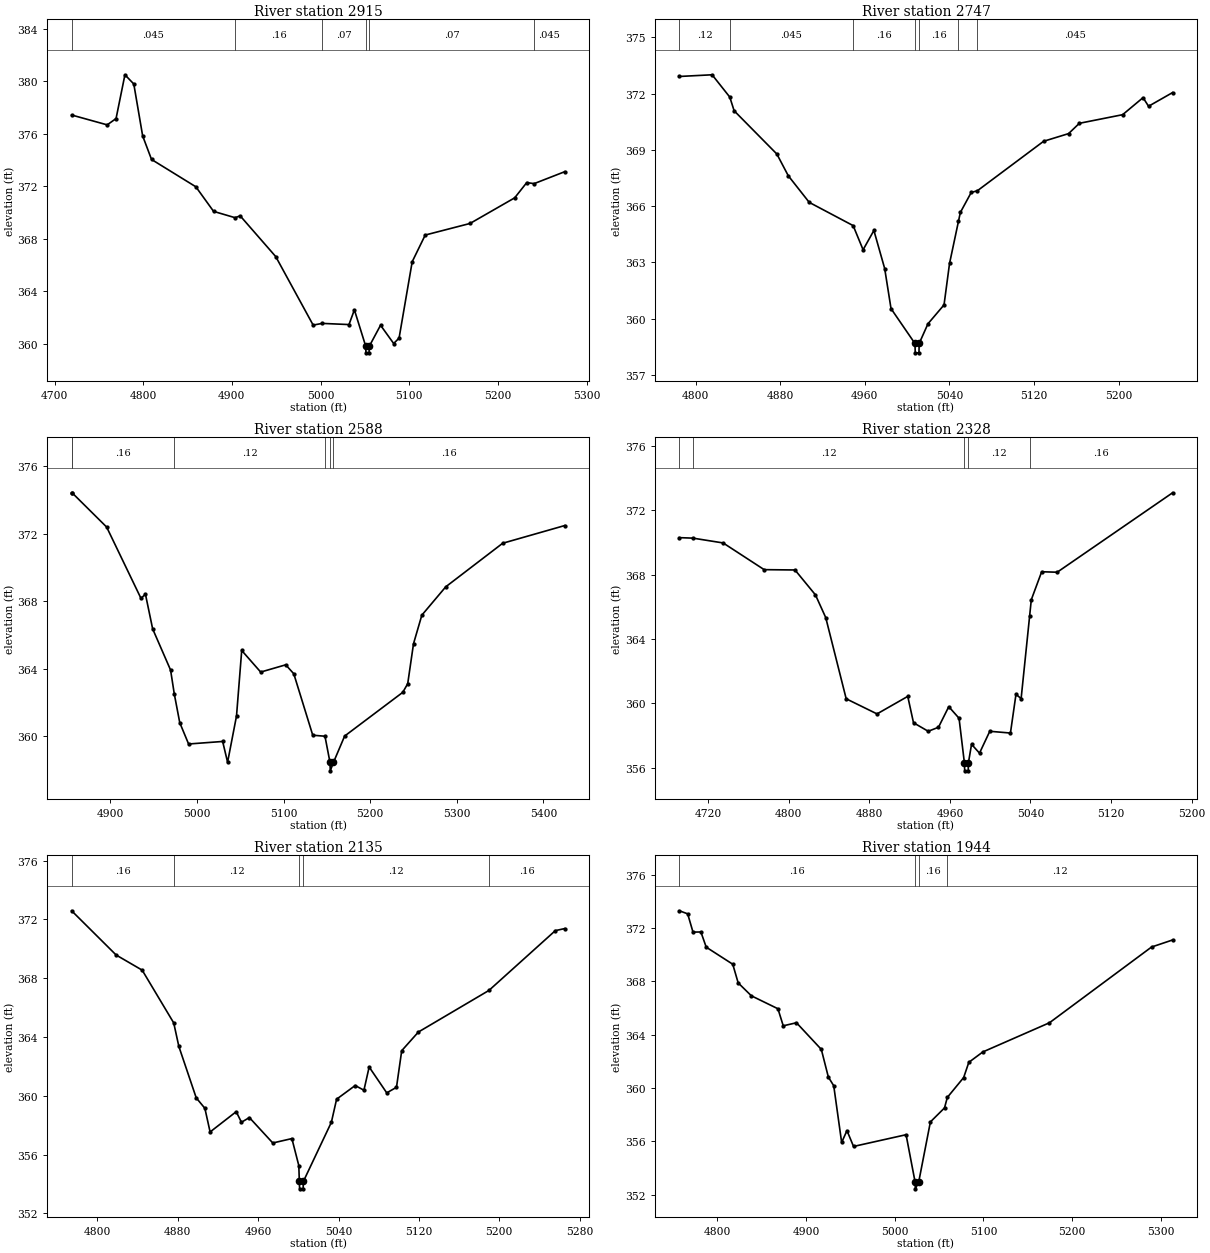
Type RM Length L Ch R = 1,2915,168,168,168
BEGIN DESCRIPTION:
Twin Creek2292914.951
END DESCRIPTION:
XS GIS Cut Line= 3
      2720066.36      6820830.89      2720060.78      6821111.53
      2719901.02      6821335.98
#Sta/Elev= 30
  4719.3  377.42  4759.4  376.67  4769.4  377.15  4779.4  380.48  4789.4  379.78
  4799.4  375.83  4809.4  374.04  4859.4  371.96  4879.4  370.09  4903.6  369.61
  4909.4  369.75  4949.5  366.65  4991.7  361.44  5001.9  361.57  5032.1  361.48
  5038.2  362.60  5051.0  359.83  5051.2  359.33  5054.7  359.33  5055.0  359.83
  5067.7  361.43  5082.5  360.04  5088.6  360.45  5103.4  366.26  5118.1  368.29
  5168.6  369.17  5219.0  371.12  5232.6  372.28  5240.9  372.20  5275.5  373.11
#Mann=6,-1,0
  4719.3   0.045       0  4903.6    0.16       0  5001.9    0.07       0
  5051.0    0.07       0  5055.0    0.07       0  5240.9   0.045       0
Bank Sta=5051,5055
Exp/Cntr=0.3,0.1

Type RM Length L Ch R = 1,2747,159,159,159
BEGIN DESCRIPTION:
Twin Creek2292746.6
END DESCRIPTION:
XS GIS Cut Line= 3
      2719950.19      6820850.69      2719907.76      6821064.01
      2719856.04      6821307.17
#Sta/Elev= 30
  4784.8  372.92  4815.7  373.01  4832.4  371.82  4836.5  371.09  4876.9  368.78
  4887.7  367.62  4907.5  366.20  4949.0  364.96  4958.4  363.67  4968.6  364.70
  4978.8  362.67  4984.8  360.53  5007.4  358.67  5007.7  358.17  5011.2  358.17
  5011.4  358.67  5019.7  359.72  5034.9  360.73  5040.1  362.94  5048.5  365.18
  5050.3  365.66  5060.6  366.73  5066.4  366.82  5129.0  369.46  5152.6  369.87
  5162.8  370.42  5203.7  370.88  5223.0  371.79  5228.2  371.33  5250.9  372.06
#Mann=7,-1,0
  4784.8    0.12       0  4832.4   0.045       0  4949.0    0.16       0
  5007.4    0.07       0  5011.4    0.16       0  5048.5    0.07       0
  5066.4   0.045       0
Bank Sta=5007.4,5011.4
Exp/Cntr=0.3,0.1

Type RM Length L Ch R = 1,2588,260,260,260
BEGIN DESCRIPTION:
Twin Creek2292587.8
END DESCRIPTION:
XS GIS Cut Line= 3
      2719822.76      6820830.85      2719783.04      6820975.39
      2719584.84      6821344.89
#Sta/Elev= 30
  4855.4  374.42  4855.9  374.42  4895.8  372.39  4935.4  368.17  4940.6  368.41
  4948.9  366.36  4969.6  363.92  4973.9  362.50  4980.2  360.80  4990.4  359.54
  5029.7  359.69  5035.4  358.46  5045.7  361.20  5051.7  365.08  5073.6  363.80
  5102.5  364.23  5111.8  363.70  5133.7  360.06  5147.8  360.00  5153.6  358.45
  5153.9  357.95  5157.6  358.45  5170.5  360.01  5237.6  362.60  5243.3  363.11
  5250.0  365.48  5259.6  367.17  5287.2  368.85  5352.9  371.43  5424.6  372.48
#Mann=6,-1,0
  4855.4    0.12       0  4855.9    0.16       0  4973.9    0.12       0
  5147.8    0.16       0  5153.6    0.07       0  5157.6    0.16       0
Bank Sta=5153.6,5157.6
Exp/Cntr=0.3,0.1

Type RM Length L Ch R = 1,2328,193,193,193
BEGIN DESCRIPTION:
Twin Creek2292328.2
END DESCRIPTION:
XS GIS Cut Line= 3
      2719624.03      6820748.31      2719566.19      6821056.09
      2719522.76      6821226.89
#Sta/Elev= 30
  4691.6  370.30  4705.0  370.27  4735.0  369.97  4775.7  368.31  4806.3  368.29
  4826.6  366.74  4836.8  365.33  4857.1  360.28  4887.7  359.34  4918.2  360.43
  4923.9  358.79  4938.5  358.26  4948.7  358.51  4958.9  359.79  4969.1  359.07
  4974.4  356.30  4974.7  355.80  4978.2  355.80  4978.4  356.30  4981.5  357.45
  4989.4  356.90  4999.6  358.26  5020.1  358.15  5025.6  360.56  5030.7  360.29
  5039.1  365.40  5040.8  366.44  5051.1  368.18  5066.5  368.15  5181.0  373.09
#Mann=5,-1,0
  4691.6    0.16       0  4705.0    0.12       0  4974.4    0.07       0
  4978.4    0.12       0  5039.1    0.16       0
Bank Sta=4974.4,4978.4
Exp/Cntr=0.3,0.1

Type RM Length L Ch R = 1,2135,191,191,191
BEGIN DESCRIPTION:
Twin Creek2292134.68
END DESCRIPTION:
XS GIS Cut Line= 3
      2719535.31      6820683.79      2719460.45      6820900.73
      2719382.10      6821150.01
#Sta/Elev= 30
  4774.4  372.59  4818.7  369.58  4844.6  368.55  4876.0  364.96  4881.1  363.36
  4898.4  359.86  4907.0  359.15  4912.2  357.54  4938.2  358.92  4943.4  358.20
  4951.3  358.52  4974.6  356.79  4993.6  357.09  5000.5  355.25  5001.0  354.17
  5001.3  353.67  5004.8  353.67  5005.0  354.17  5032.9  358.20  5038.1  359.77
  5056.6  360.70  5065.3  360.38  5070.5  361.96  5088.0  360.20  5097.7  360.58
  5102.9  363.07  5119.5  364.34  5189.7  367.17  5255.8  371.24  5265.2  371.38
#Mann=5,-1,0
  4774.4    0.16       0  4876.0    0.12       0  5001.0    0.07       0
  5005.0    0.12       0  5189.7    0.16       0
Bank Sta=5001,5005
Exp/Cntr=0.3,0.1

Type RM Length L Ch R = 1,1944,175,175,175
BEGIN DESCRIPTION:
Twin Creek2291943.65
END DESCRIPTION:
XS GIS Cut Line= 3
      2719466.54      6820558.82      2719328.62      6820761.30
      2719175.37      6821031.59
#Sta/Elev= 30
  4757.4  373.29  4766.7  373.06  4772.7  371.69  4781.6  371.70  4787.6  370.56
  4817.5  369.28  4823.6  367.88  4838.5  366.91  4868.4  365.94  4874.4  364.66
  4889.3  364.89  4917.3  362.89  4925.2  360.82  4931.3  360.16  4940.2  355.91
  4946.2  356.80  4953.6  355.61  5012.8  356.49  5023.0  352.93  5023.3  352.43
  5027.0  352.93  5040.2  357.45  5056.1  358.50  5059.3  359.29  5077.7  360.78
  5083.5  361.92  5099.3  362.70  5174.4  364.89  5289.4  370.57  5313.1  371.10
#Mann=4,-1,0
  4757.4    0.16       0  5023.0    0.07       0  5027.0    0.16       0
  5059.3    0.12       0
Bank Sta=5023,5027
Exp/Cntr=0.3,0.1

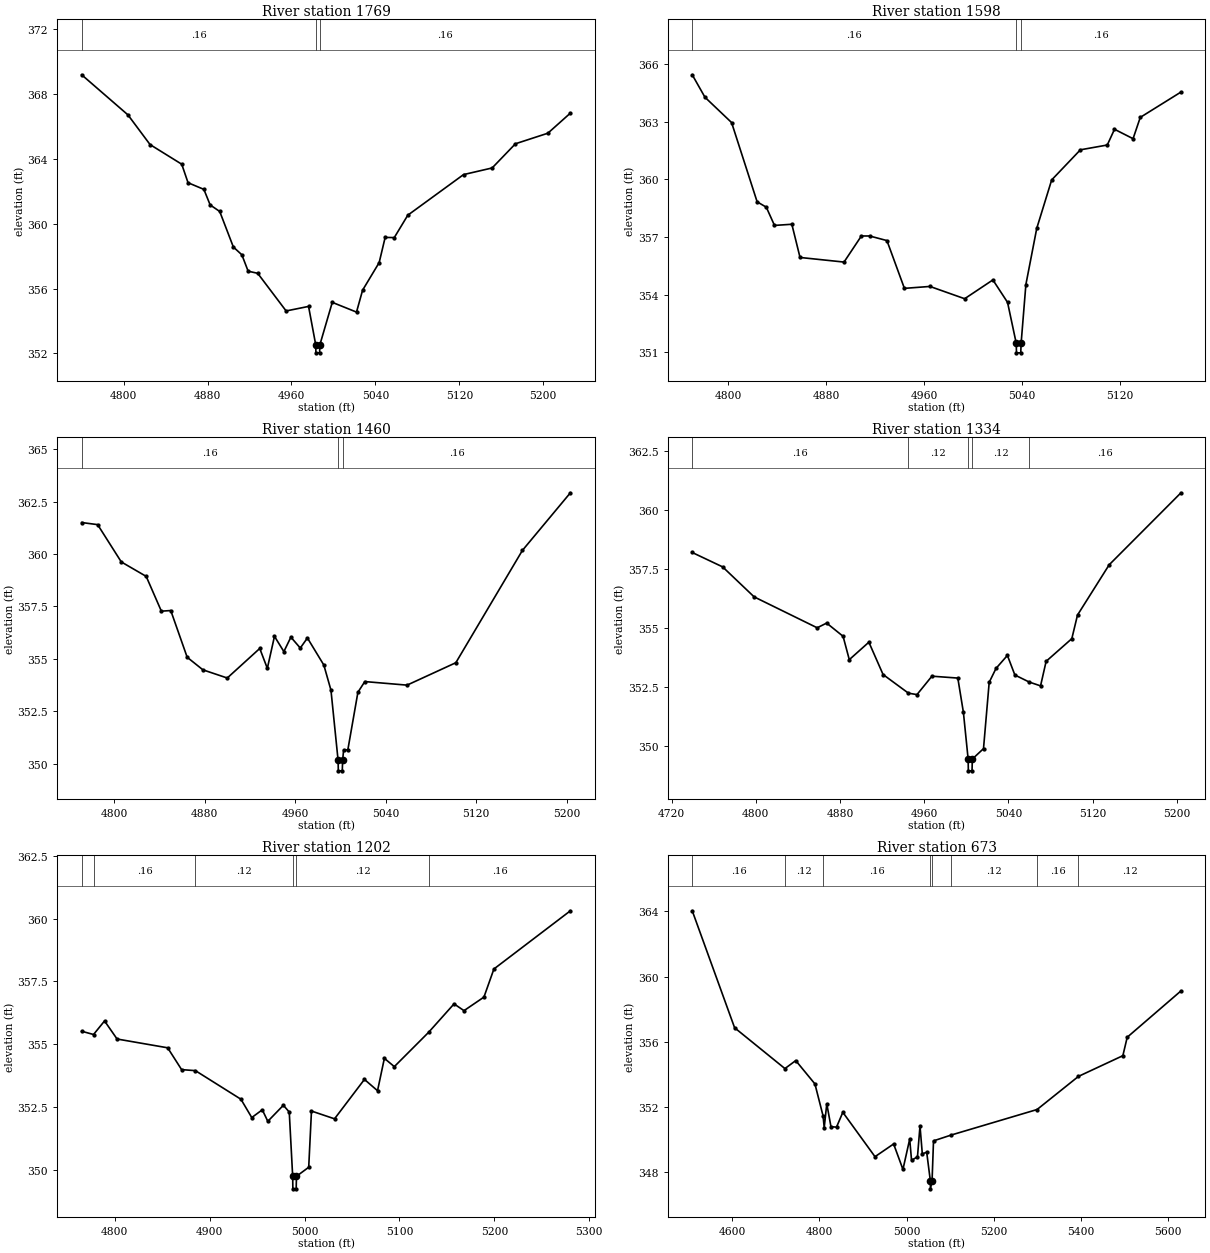
Type RM Length L Ch R = 1,1769,171,171,171
BEGIN DESCRIPTION:
Twin Creek2291768.7
END DESCRIPTION:
XS GIS Cut Line= 3
      2719365.76      6820419.99      2719232.44      6820623.82
      2719121.21      6820816.34
#Sta/Elev= 30
  4760.0  369.17  4804.1  366.70  4825.2  364.87  4855.4  363.66  4861.4  362.52
  4876.5  362.11  4882.5  361.15  4891.6  360.75  4904.6  358.56  4912.7  358.08
  4918.7  357.07  4927.8  356.94  4954.9  354.62  4976.3  354.90  4983.1  352.54
  4983.3  352.04  4986.8  352.04  4987.1  352.54  4998.9  355.15  5022.0  354.55
  5027.8  355.90  5043.6  357.60  5049.3  359.15  5058.0  359.14  5070.9  360.52
  5124.0  363.02  5151.3  363.43  5173.5  364.92  5204.4  365.57  5225.9  366.81
#Mann=3,-1,0
  4760.0    0.16       0  4983.1    0.07       0  4987.1    0.16       0
Bank Sta=4983.1,4987.1
Exp/Cntr=0.3,0.1

Type RM Length L Ch R = 1,1598,138,138,138
BEGIN DESCRIPTION:
Twin Creek2291598.19
END DESCRIPTION:
XS GIS Cut Line= 3
      2719275.15      6820345.10      2719122.05      6820518.75
      2719030.36      6820660.00
#Sta/Elev= 30
  4770.4  365.45  4780.8  364.28  4802.6  362.96  4823.5  358.83  4831.0  358.55
  4837.7  357.60  4851.9  357.66  4858.6  355.93  4894.6  355.69  4908.8  357.05
  4915.5  357.05  4929.7  356.81  4944.0  354.32  4964.9  354.42  4993.3  353.78
  5016.4  354.76  5028.4  353.59  5035.5  351.46  5035.7  350.96  5039.2  350.96
  5039.5  351.46  5043.4  354.52  5052.3  357.45  5064.5  359.97  5088.0  361.54
  5110.0  361.79  5115.9  362.61  5131.1  362.12  5137.0  363.23  5170.3  364.55
#Mann=3,-1,0
  4770.4    0.16       0  5035.5    0.07       0  5039.5    0.16       0
Bank Sta=5035.5,5039.5
Exp/Cntr=0.3,0.1

Type RM Length L Ch R = 1,1460,126,126,126
BEGIN DESCRIPTION:
Twin Creek2291459.98
END DESCRIPTION:
XS GIS Cut Line= 3
      2719200.15      6820215.53      2719060.25      6820400.63
      2718960.10      6820573.38
#Sta/Elev= 30
  4771.5  361.50  4785.6  361.40  4806.5  359.62  4828.5  358.93  4841.9  357.27
  4850.2  357.30  4864.7  355.07  4878.6  354.47  4900.1  354.08  4928.8  355.49
  4935.5  354.54  4941.8  356.07  4950.1  355.34  4956.3  356.03  4964.6  355.51
  4970.9  355.99  4985.4  354.70  4991.7  353.50  4998.0  350.15  4998.2  349.65
  5001.7  349.65  5002.0  350.15  5002.9  350.65  5006.6  350.65  5015.5  353.40
  5021.6  353.91  5058.9  353.74  5102.0  354.81  5160.8  360.17  5203.2  362.92
#Mann=3,-1,0
  4771.5    0.16       0  4998.0    0.07       0  5002.0    0.16       0
Bank Sta=4998,5002
Exp/Cntr=0.3,0.1

Type RM Length L Ch R = 1,1334,132,132,132
BEGIN DESCRIPTION:
Twin Creek2291333.86
END DESCRIPTION:
XS GIS Cut Line= 3
      2719072.51      6820061.90      2718976.35      6820310.37
      2718903.73      6820494.44
#Sta/Elev= 30
  4739.6  358.20  4768.5  357.59  4798.4  356.32  4858.3  355.01  4867.3  355.21
  4882.9  354.65  4888.8  353.66  4907.4  354.40  4920.9  353.03  4945.0  352.24
  4953.1  352.18  4967.3  352.96  4991.9  352.88  4997.2  351.43  5001.7  349.45
  5001.9  348.95  5005.4  348.95  5005.7  349.45  5016.3  349.89  5021.7  352.70
  5028.2  353.29  5039.0  353.84  5046.1  353.01  5059.8  352.71  5070.5  352.55
  5075.8  353.59  5100.2  354.55  5105.6  355.55  5135.7  357.68  5203.9  360.73
#Mann=5,-1,0
  4739.6    0.16       0  4945.0    0.12       0  5001.7    0.07       0
  5005.7    0.12       0  5059.8    0.16       0
Bank Sta=5001.7,5005.7
Exp/Cntr=0.3,0.1

Type RM Length L Ch R = 1,1202,529,529,529
BEGIN DESCRIPTION:
Twin Creek2291202.1
END DESCRIPTION:
XS GIS Cut Line= 3
      2719005.62      6819999.29      2718902.48      6820215.14
      2718818.63      6820477.75
#Sta/Elev= 30
  4765.2  355.51  4777.7  355.38  4789.3  355.92  4802.5  355.20  4855.8  354.85
  4870.5  353.98  4885.0  353.94  4933.0  352.80  4944.4  352.07  4955.5  352.38
  4961.3  351.92  4977.7  352.56  4983.9  352.29  4987.5  349.73  4987.7  349.23
  4991.2  349.23  4991.5  349.73  5004.4  350.09  5007.3  352.33  5031.6  352.02
  5063.1  353.59  5076.9  353.14  5084.1  354.43  5094.6  354.10  5130.8  355.47
  5157.5  356.60  5168.0  356.33  5189.0  356.87  5199.5  357.99  5280.1  360.31
#Mann=6,-1,0
  4765.2    0.12       0  4777.7    0.16       0  4885.0    0.12       0
  4987.5    0.07       0  4991.5    0.12       0  5130.8    0.16       0
Bank Sta=4987.5,4991.5
Exp/Cntr=0.3,0.1

Type RM Length L Ch R = 1,673,333,333,333
BEGIN DESCRIPTION:
Twin Creek229673.17
END DESCRIPTION:
XS GIS Cut Line= 4
      2719028.02      6819487.75      2718766.61      6819920.74
      2718698.14      6820116.58      2718690.91      6820524.27
#Sta/Elev= 30
  4508.2  364.03  4605.4  356.86  4720.8  354.36  4745.6  354.85  4789.6  353.42
  4808.3  351.46  4810.9  350.74  4816.8  352.20  4826.4  350.80  4839.1  350.77
  4853.6  351.68  4927.4  348.96  4970.1  349.74  4991.5  348.18  5007.0  350.04
  5011.2  348.74  5024.8  348.95  5030.6  350.84  5035.9  349.14  5046.0  349.23
  5054.3  347.49  5054.6  346.99  5058.3  347.49  5061.6  349.93  5102.5  350.29
  5299.1  351.85  5394.0  353.88  5495.9  355.15  5505.9  356.28  5629.2  359.12
#Mann=8,-1,0
  4508.2    0.16       0  4720.8    0.12       0  4808.3    0.16       0
  5054.3    0.07       0  5058.3    0.16       0  5102.5    0.12       0
  5299.1    0.16       0  5394.0    0.12       0
Bank Sta=5054.3,5058.3
Exp/Cntr=0.3,0.1

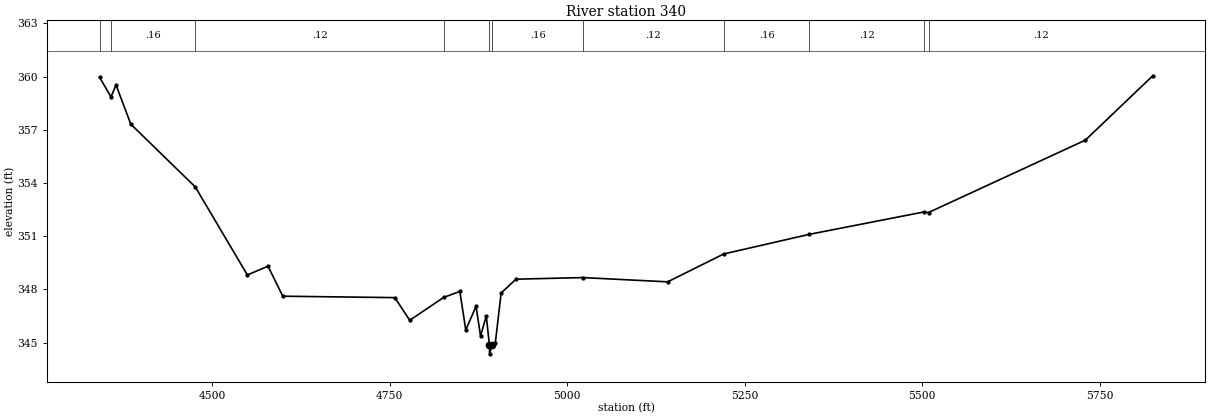
Type RM Length L Ch R = 1,340,0,0,0
BEGIN DESCRIPTION:
Twin Creek229339.861
END DESCRIPTION:
XS GIS Cut Line= 3
      2718925.74      6819238.61      2718525.72      6819761.55
      2718662.12      6820574.59
#Sta/Elev= 30
  4341.6  359.96  4357.6  358.86  4364.7  359.53  4385.5  357.32  4476.3  353.78
  4549.6  348.82  4578.7  349.31  4599.5  347.62  4757.3  347.54  4778.2  346.26
  4825.9  347.55  4848.8  347.89  4857.1  345.72  4871.6  347.05  4877.9  345.38
  4886.0  346.50  4890.4  344.87  4890.7  344.37  4894.4  344.87  4898.7  344.97
  4906.9  347.80  4927.8  348.58  5022.0  348.67  5141.4  348.43  5220.2  350.00
  5341.0  351.11  5502.0  352.37  5508.7  352.34  5729.5  356.42  5824.4  360.05
#Mann=11,-1,0
  4341.6    0.12       0  4357.6    0.16       0  4476.3    0.12       0
  4825.9    0.16       0  4890.4    0.07       0  4894.4    0.16       0
  5022.0    0.12       0  5220.2    0.16       0  5341.0    0.12       0
  5502.0    0.16       0  5508.7    0.12       0
Bank Sta=4890.4,4894.4
Exp/Cntr=0.3,0.1

Chan Stop Cuts=-1