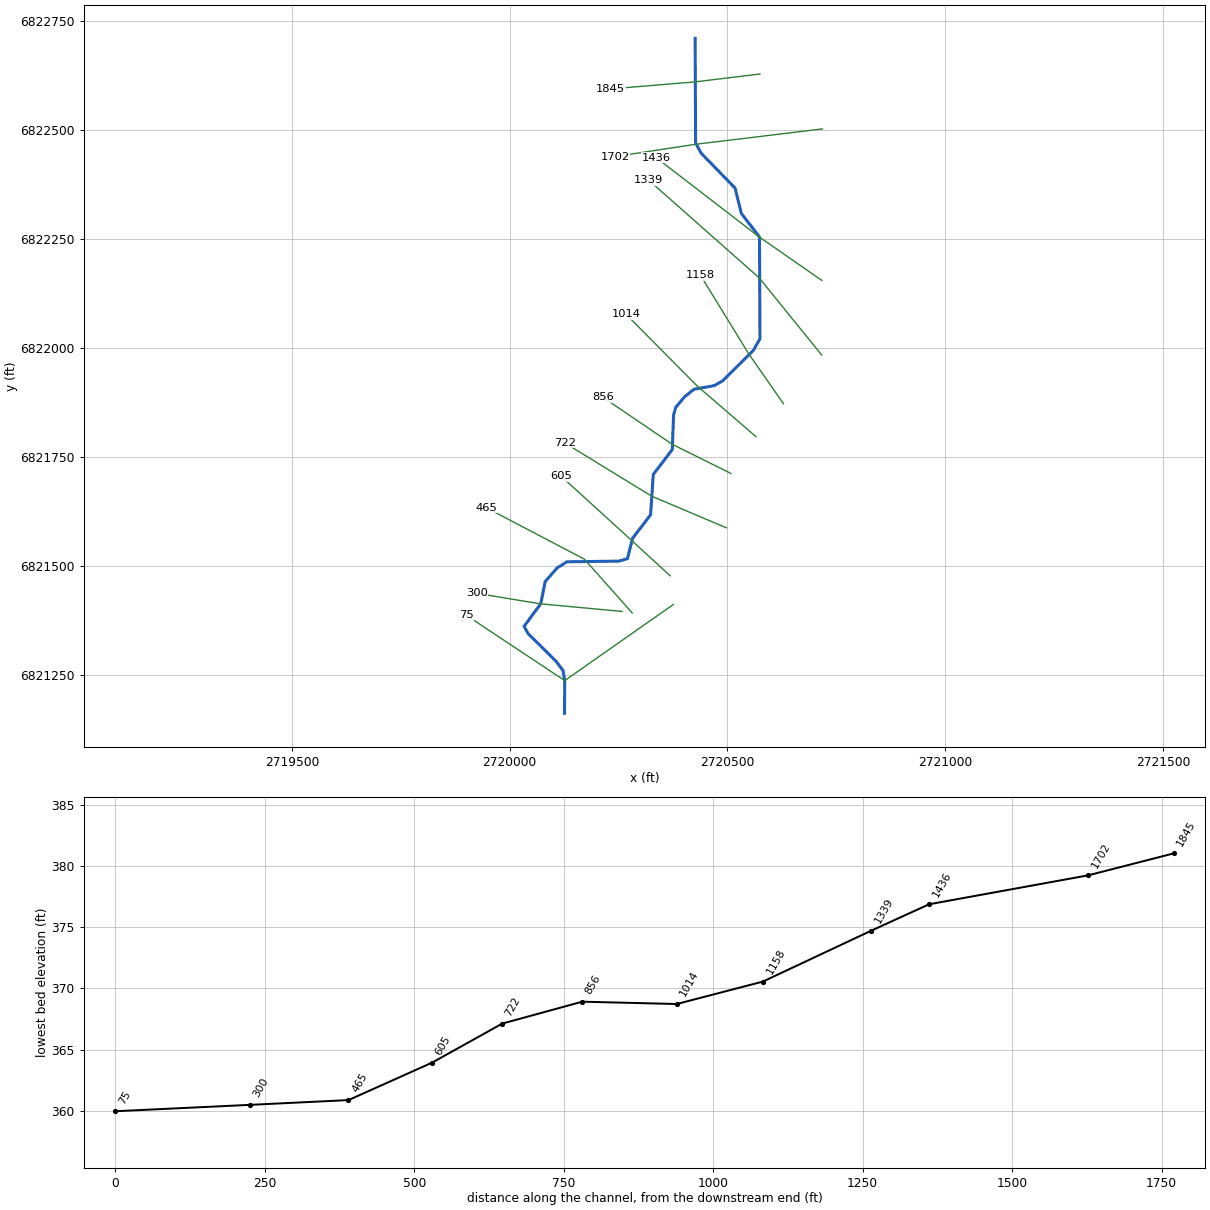
--- Twin Creek230.prj (project) ---

Proj Title=Twin Creek230 Base Level Engineering
Current Plan=p01
Default Exp/Contr=0.3,0.1
English Units
Geom File=g01
Flow File=f01
Plan File=p01
BEGIN DESCRIPTION:
Twin Creek230
END DESCRIPTION:

--- Twin Creek230.p01 (plan) ---

Plan Title=Multiple Run
Short Identifier=Multiple
Geom File=g01
Flow File=f01
Subcritical Flow
K Sum by GR= 0
Std Step Tol= 0.01
Critical Tol= 0.01
Num of Std Step Trials= 20
Max Error Tol= 0.3
Flow Tol Ratio= 0.001
Split Flow NTrial= 30
Split Flow Tol= 0.02
Split Flow Ratio= 0.02
Log Output Level= 0
Friction Slope Method= 1
Unsteady Friction Slope Method= 2
Unsteady Bridges Friction Slope Method= 1
Parabolic Critical Depth
Global Vel Dist=  1 , 1 , 1
Global Log Level= 0
CheckData=True
Encroach Param= -1, 0, 0, 0
BEGIN DESCRIPTION:
Multiple Run
END DESCRIPTION:

--- Twin Creek230.f01 (steady flow) ---

Flow Title=Multiple
Number of Profiles=7
Profile Names=10-year,25-year,50-year,1pct_min,100-year,1pct_plu,500-year
River Rch & RM= Twin Creek230,Reach-1,1845
     160     196     222     126     251     501     319
Boundary for River Rch & Prof#=Twin Creek230,Reach-1,1
Up Type=0
Dn Type=3
Dn Slope=0.005
Boundary for River Rch & Prof#=Twin Creek230,Reach-1,2
Up Type=0
Dn Type=3
Dn Slope=0.005
Boundary for River Rch & Prof#=Twin Creek230,Reach-1,3
Up Type=0
Dn Type=3
Dn Slope=0.005
Boundary for River Rch & Prof#=Twin Creek230,Reach-1,4
Up Type=0
Dn Type=3
Dn Slope=0.005
Boundary for River Rch & Prof#=Twin Creek230,Reach-1,5
Up Type=0
Dn Type=3
Dn Slope=0.005
Boundary for River Rch & Prof#=Twin Creek230,Reach-1,6
Up Type=0
Dn Type=3
Dn Slope=0.005
Boundary for River Rch & Prof#=Twin Creek230,Reach-1,7
Up Type=0
Dn Type=3
Dn Slope=0.005

--- Twin Creek230.g01 (geometry) ---

Geom Title=Existing Conditions

River Reach=Twin Creek230,Reach-1
Reach XY= 30
      2720426.00      6822711.00      2720427.05      6822471.44
      2720439.40      6822447.69      2720517.84      6822367.05
      2720532.14      6822308.83      2720573.76      6822255.07
      2720574.96      6822021.43      2720559.58      6821994.20
      2720489.23      6821924.62      2720469.92      6821913.55
      2720423.43      6821905.26      2720402.05      6821888.19
      2720381.42      6821863.67      2720376.47      6821845.91
      2720373.64      6821766.98      2720329.85      6821709.40
      2720323.68      6821616.94      2720282.30      6821562.78
      2720270.59      6821516.18      2720251.21      6821510.69
      2720131.68      6821509.00      2720108.86      6821494.72
      2720081.69      6821463.57      2720071.52      6821412.68
      2720033.29      6821360.92      2720042.31      6821344.31
      2720106.29      6821281.16      2720122.59      6821259.60
      2720126.59      6821236.25      2720126.00      6821161.00

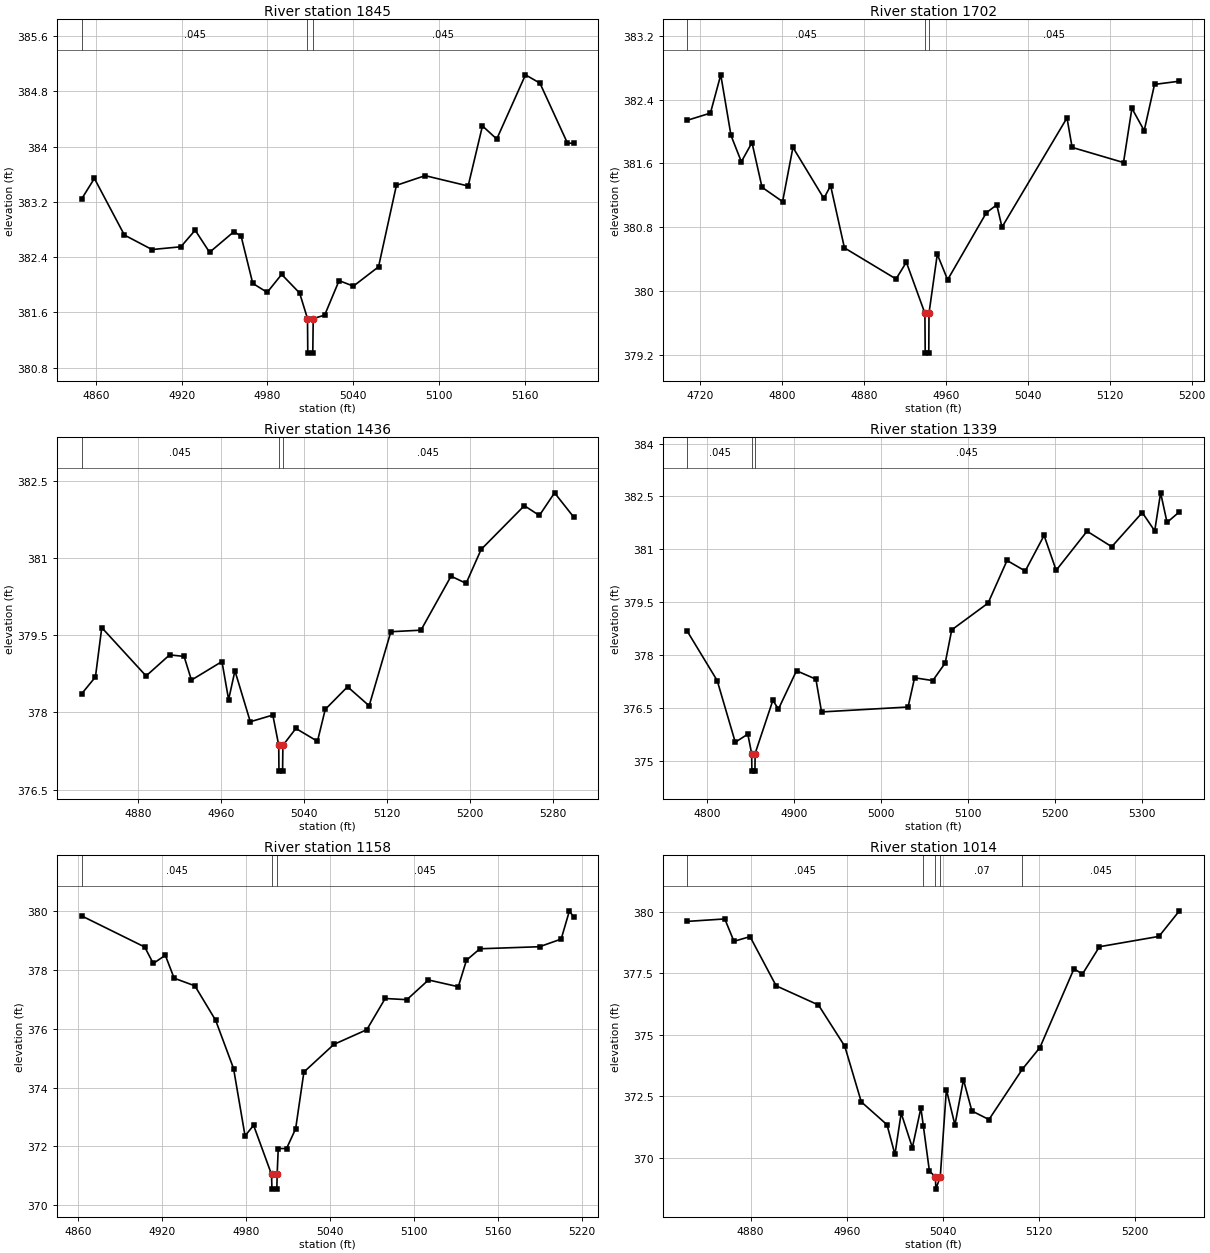
Type RM Length L Ch R = 1,1845,143,143,143
BEGIN DESCRIPTION:
Twin Creek2301845.351
END DESCRIPTION:
XS GIS Cut Line= 3
      2720574.96      6822629.12      2720426.00      6822611.00
      2720232.43      6822594.87
#Sta/Elev= 30
  4849.9  383.24  4858.9  383.54  4879.9  382.72  4899.2  382.51  4919.4  382.55
  4929.4  382.79  4939.5  382.47  4956.6  382.77  4961.6  382.70  4969.7  382.02
  4979.8  381.89  4989.9  382.15  5002.5  381.88  5008.0  381.51  5008.2  381.01
  5011.7  381.01  5012.0  381.51  5020.0  381.56  5030.1  382.06  5040.1  381.98
  5057.7  382.26  5070.2  383.44  5090.3  383.58  5120.4  383.43  5130.4  384.30
  5140.4  384.11  5160.5  385.04  5170.6  384.92  5189.9  384.05  5194.2  384.05
#Mann=3,-1,0
  4849.9   0.045       0  5008.0   0.045       0  5012.0   0.045       0
Bank Sta=5008,5012
Exp/Cntr=0.3,0.1

Type RM Length L Ch R = 1,1702,266,266,266
BEGIN DESCRIPTION:
Twin Creek2301702.05
END DESCRIPTION:
XS GIS Cut Line= 3
      2720718.43      6822503.03      2720425.97      6822467.57
      2720242.00      6822439.49
#Sta/Elev= 30
  4707.3  382.14  4729.9  382.23  4740.0  382.71  4750.0  381.95  4760.1  381.62
  4770.5  381.86  4780.3  381.30  4800.4  381.12  4810.5  381.80  4840.7  381.16
  4847.3  381.32  4860.8  380.54  4911.2  380.15  4921.3  380.36  4939.4  379.72
  4939.7  379.22  4943.2  379.22  4943.4  379.72  4951.5  380.46  4961.6  380.14
  4999.4  380.98  5009.6  381.08  5014.7  380.80  5078.2  382.17  5083.2  381.80
  5133.4  381.61  5141.6  382.29  5153.6  382.01  5163.7  382.59  5188.0  382.63
#Mann=3,-1,0
  4707.3   0.045       0  4939.4   0.045       0  4943.4   0.045       0
Bank Sta=4939.4,4943.4
Exp/Cntr=0.3,0.1

Type RM Length L Ch R = 1,1436,97,97,97
BEGIN DESCRIPTION:
Twin Creek2301436.24
END DESCRIPTION:
XS GIS Cut Line= 3
      2720717.12      6822155.00      2720572.36      6822255.57
      2720336.32      6822437.21
#Sta/Elev= 30
  4825.6  378.36  4839.0  378.69  4845.1  379.65  4887.8  378.71  4910.5  379.12
  4924.4  379.09  4931.5  378.63  4960.9  378.99  4967.3  378.25  4973.4  378.81
  4988.2  377.82  5009.9  377.95  5015.6  377.36  5015.8  376.86  5019.3  376.86
  5019.6  377.36  5032.1  377.69  5052.9  377.44  5060.4  378.06  5081.9  378.50
  5102.7  378.13  5123.6  379.57  5152.6  379.60  5181.6  380.65  5196.1  380.51
  5210.6  381.17  5252.2  382.02  5266.7  381.83  5281.3  382.27  5299.7  381.80
#Mann=3,-1,0
  4825.6   0.045       0  5015.6   0.045       0  5019.6   0.045       0
Bank Sta=5015.6,5019.6
Exp/Cntr=0.3,0.1

Type RM Length L Ch R = 1,1339,181,181,181
BEGIN DESCRIPTION:
Twin Creek2301338.78
END DESCRIPTION:
XS GIS Cut Line= 3
      2720716.48      6821983.97      2720572.71      6822161.41
      2720319.81      6822384.93
#Sta/Elev= 30
  4777.0  378.67  4811.4  377.27  4832.2  375.52  4846.6  375.75  4851.0  375.20
  4851.3  374.70  4854.8  374.70  4855.0  375.20  4875.4  376.71  4881.8  376.46
  4902.6  377.55  4924.9  377.31  4931.4  376.38  5030.9  376.52  5038.4  377.35
  5059.3  377.27  5073.6  377.77  5081.1  378.71  5122.9  379.47  5144.7  380.68
  5165.6  380.38  5187.3  381.39  5201.2  380.40  5236.7  381.51  5265.1  381.07
  5300.2  382.04  5314.5  381.52  5321.3  382.60  5328.7  381.76  5342.9  382.06
#Mann=3,-1,0
  4777.0   0.045       0  4851.0   0.045       0  4855.0   0.045       0
Bank Sta=4851,4855
Exp/Cntr=0.3,0.1

Type RM Length L Ch R = 1,1158,144,144,144
BEGIN DESCRIPTION:
Twin Creek2301157.9
END DESCRIPTION:
XS GIS Cut Line= 3
      2720628.87      6821871.96      2720547.87      6821988.31
      2720438.36      6822166.83
#Sta/Elev= 30
  4862.7  379.84  4907.8  378.78  4913.9  378.22  4922.5  378.50  4928.8  377.72
  4943.6  377.46  4958.4  376.29  4971.2  374.65  4979.4  372.36  4985.5  372.72
  4998.3  371.05  4998.6  370.55  5002.1  370.55  5002.3  371.05  5003.1  371.93
  5009.0  371.93  5015.5  372.60  5021.4  374.53  5042.8  375.47  5066.3  375.97
  5079.4  377.03  5094.9  376.99  5110.3  377.66  5131.6  377.43  5137.4  378.33
  5147.0  378.72  5189.6  378.79  5205.0  379.05  5210.9  380.01  5213.9  379.79
#Mann=3,-1,0
  4862.7   0.045       0  4998.3   0.045       0  5002.3   0.045       0
Bank Sta=4998.3,5002.3
Exp/Cntr=0.3,0.1

Type RM Length L Ch R = 1,1014,158,158,158
BEGIN DESCRIPTION:
Twin Creek2301014.32
END DESCRIPTION:
XS GIS Cut Line= 3
      2720565.56      6821796.48      2720430.56      6821912.86
      2720267.86      6822076.93
#Sta/Elev= 30
  4827.4  379.61  4858.6  379.71  4866.2  378.80  4879.6  378.99  4901.3  376.99
  4936.5  376.21  4958.4  374.53  4972.1  372.27  4993.5  371.34  5000.1  370.13
  5005.3  371.81  5014.6  370.41  5021.7  372.02  5023.7  371.30  5028.8  369.45
  5033.8  369.22  5034.1  368.72  5037.8  369.22  5042.9  372.77  5050.0  371.33
  5057.1  373.17  5064.1  371.90  5078.3  371.55  5106.1  373.60  5120.7  374.48
  5149.0  377.68  5156.1  377.47  5170.2  378.58  5219.7  379.00  5236.7  380.04
#Mann=5,-1,0
  4827.4   0.045       0  5023.7    0.07       0  5033.8   0.045       0
  5037.8    0.07       0  5106.1   0.045       0
Bank Sta=5033.8,5037.8
Exp/Cntr=0.3,0.1

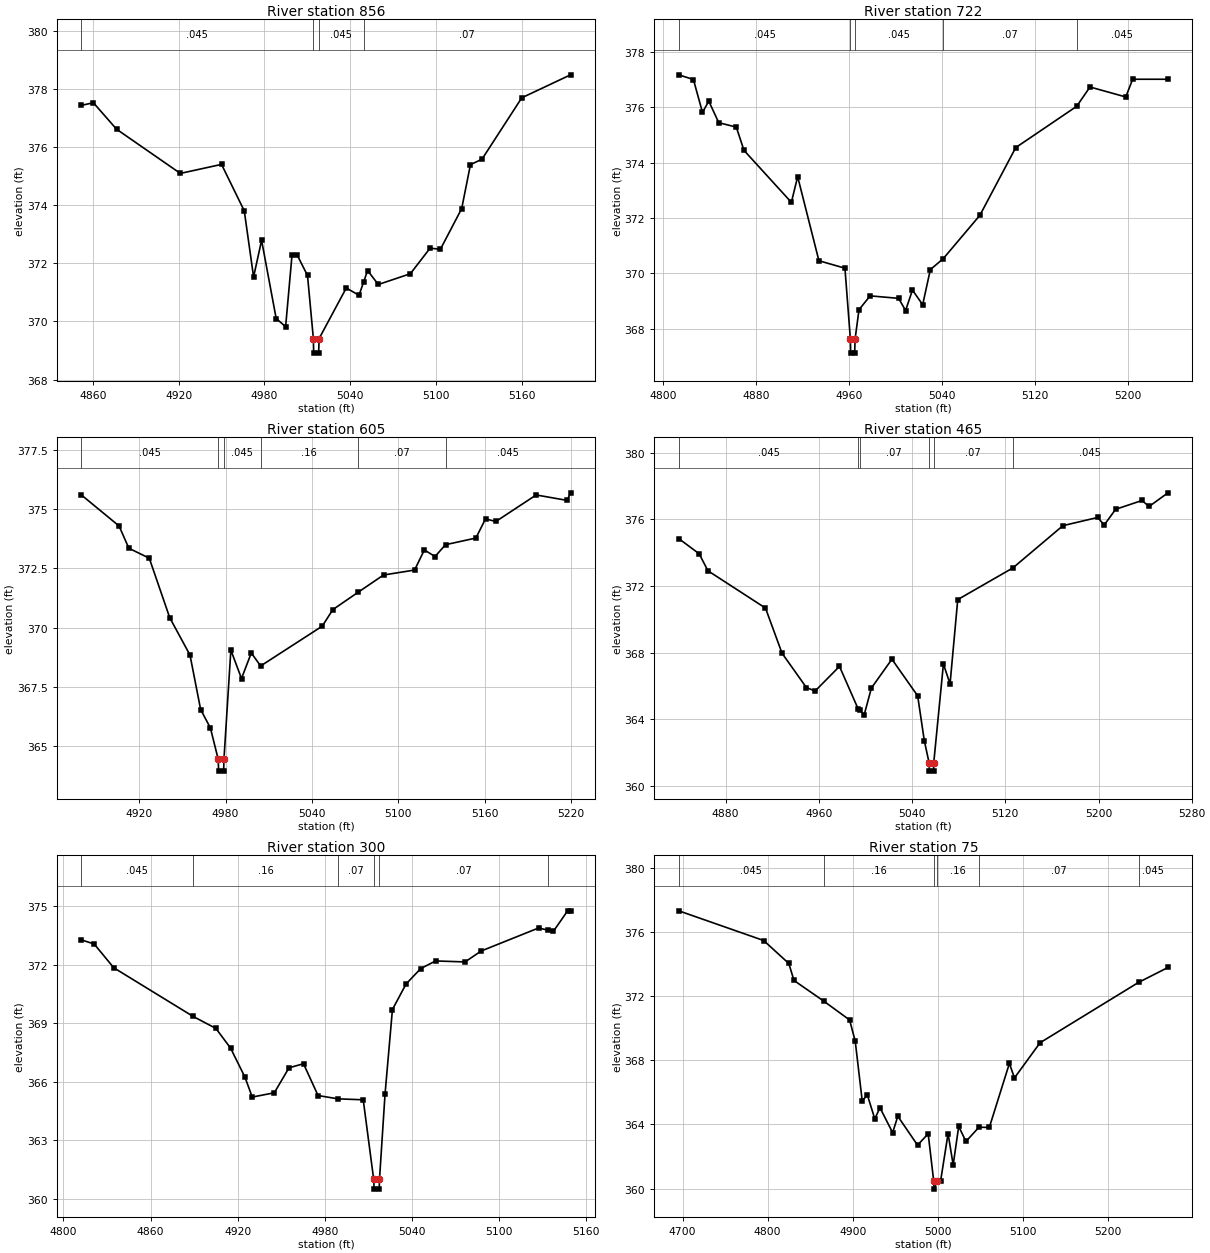
Type RM Length L Ch R = 1,856,134,134,134
BEGIN DESCRIPTION:
Twin Creek230855.95
END DESCRIPTION:
XS GIS Cut Line= 3
      2720508.02      6821712.01      2720373.03      6821779.04
      2720214.79      6821886.51
#Sta/Elev= 30
  4852.0  377.43  4860.4  377.52  4876.6  376.61  4921.2  375.09  4950.0  375.40
  4965.9  373.80  4972.4  371.53  4978.0  372.79  4988.2  370.10  4994.8  369.82
  4999.3  372.30  5002.7  372.30  5010.1  371.58  5014.2  369.41  5014.4  368.91
  5017.9  368.91  5018.2  369.41  5037.2  371.15  5046.1  370.90  5049.3  371.35
  5052.1  371.75  5059.6  371.27  5082.0  371.64  5095.8  372.52  5103.0  372.48
  5117.9  373.88  5124.0  375.39  5132.1  375.58  5159.9  377.69  5194.0  378.48
#Mann=4,-1,0
  4852.0   0.045       0  5014.2   0.045       0  5018.2   0.045       0
  5049.3    0.07       0
Bank Sta=5014.2,5018.2
Exp/Cntr=0.3,0.1

Type RM Length L Ch R = 1,722,117,117,117
BEGIN DESCRIPTION:
Twin Creek230722.01
END DESCRIPTION:
XS GIS Cut Line= 3
      2720497.63      6821587.11      2720326.19      6821659.76
      2720125.98      6821782.43
#Sta/Elev= 30
  4813.6  377.18  4826.2  377.01  4834.0  375.82  4839.4  376.23  4848.0  375.45
  4863.1  375.29  4869.7  374.45  4910.5  372.57  4915.9  373.50  4934.2  370.46
  4956.6  370.19  4961.3  367.62  4961.5  367.12  4965.0  367.12  4965.3  367.62
  4968.7  368.69  4978.3  369.19  5002.8  369.10  5008.8  368.66  5014.7  369.40
  5023.5  368.87  5030.1  370.14  5041.1  370.53  5072.7  372.10  5103.6  374.55
  5156.0  376.04  5167.5  376.74  5198.3  376.38  5204.2  377.02  5234.6  377.02
#Mann=5,-1,0
  4813.6   0.045       0  4961.3   0.045       0  4965.3   0.045       0
  5041.1    0.07       0  5156.0   0.045       0
Bank Sta=4961.3,4965.3
Exp/Cntr=0.3,0.1

Type RM Length L Ch R = 1,605,140,140,140
BEGIN DESCRIPTION:
Twin Creek230605.04
END DESCRIPTION:
XS GIS Cut Line= 3
      2720368.77      6821476.86      2720277.56      6821560.44
      2720117.66      6821706.08
#Sta/Elev= 30
  4879.8  375.60  4906.0  374.29  4912.8  373.35  4927.0  372.93  4941.2  370.42
  4955.3  368.84  4962.7  366.54  4969.5  365.76  4974.9  364.44  4975.2  363.94
  4978.7  363.94  4978.9  364.44  4983.7  369.05  4991.1  367.85  4997.9  368.93
  5004.4  368.38  5047.2  370.06  5054.6  370.76  5072.1  371.49  5089.8  372.22
  5111.4  372.43  5118.2  373.28  5125.6  373.00  5132.9  373.50  5154.0  373.78
  5160.7  374.59  5167.9  374.48  5195.9  375.60  5217.5  375.37  5219.8  375.69
#Mann=6,-1,0
  4879.8   0.045       0  4974.9   0.045       0  4978.9   0.045       0
  5004.4    0.16       0  5072.1    0.07       0  5132.9   0.045       0
Bank Sta=4974.9,4978.9
Exp/Cntr=0.3,0.1

Type RM Length L Ch R = 1,465,165,165,165
BEGIN DESCRIPTION:
Twin Creek230464.91
END DESCRIPTION:
XS GIS Cut Line= 3
      2720281.50      6821391.65      2720171.67      6821515.13
      2719946.22      6821633.30
#Sta/Elev= 30
  4839.8  374.84  4857.3  373.93  4864.8  372.91  4914.2  370.67  4928.4  367.96
  4949.3  365.90  4956.8  365.69  4977.7  367.17  4993.7  364.62  4994.9  364.54
  4998.9  364.26  5005.1  365.87  5022.7  367.60  5044.8  365.40  5050.5  362.71
  5054.6  361.38  5054.9  360.88  5058.4  360.88  5058.6  361.38  5066.9  367.31
  5072.6  366.12  5079.2  371.18  5126.5  373.08  5169.5  375.62  5199.3  376.11
  5204.9  375.66  5214.7  376.60  5237.3  377.13  5243.4  376.77  5259.6  377.59
#Mann=6,-1,0
  4839.8   0.045       0  4993.7    0.16       0  4994.9    0.07       0
  5054.6    0.07       0  5058.6    0.07       0  5126.5   0.045       0
Bank Sta=5054.6,5058.6
Exp/Cntr=0.3,0.1

Type RM Length L Ch R = 1,300,225,225,225
BEGIN DESCRIPTION:
Twin Creek230300.35
END DESCRIPTION:
XS GIS Cut Line= 3
      2720258.24      6821395.05      2720069.31      6821412.75
      2719924.32      6821436.66
#Sta/Elev= 30
  4812.4  373.27  4821.2  373.06  4834.7  371.84  4889.2  369.35  4905.0  368.73
  4915.1  367.72  4925.0  366.23  4930.0  365.21  4945.2  365.43  4955.3  366.71
  4965.3  366.92  4975.3  365.29  4988.9  365.12  5006.4  365.07  5013.6  360.99
  5013.9  360.49  5017.4  360.49  5017.6  360.99  5021.4  365.35  5026.5  369.70
  5035.9  371.01  5046.0  371.80  5056.2  372.19  5076.5  372.14  5087.6  372.70
  5127.1  373.88  5133.5  373.77  5137.3  373.71  5147.1  374.76  5149.1  374.76
#Mann=6,-1,0
  4812.4   0.045       0  4889.2    0.16       0  4988.9    0.07       0
  5013.6    0.07       0  5017.6    0.07       0  5133.5   0.045       0
Bank Sta=5013.6,5017.6
Exp/Cntr=0.3,0.1

Type RM Length L Ch R = 1,75,0,0,0
BEGIN DESCRIPTION:
Twin Creek23075.254
END DESCRIPTION:
XS GIS Cut Line= 3
      2720375.96      6821410.98      2720126.59      6821236.25
      2719900.97      6821386.02
#Sta/Elev= 30
  4695.5  377.31  4795.3  375.46  4824.9  374.03  4831.0  372.97  4866.1  371.68
  4896.4  370.51  4903.0  369.19  4911.2  365.48  4917.3  365.83  4926.0  364.35
  4932.1  365.04  4947.0  363.49  4953.1  364.51  4976.3  362.71  4988.8  363.42
  4995.3  360.47  4995.6  359.97  4999.3  360.47  5003.4  360.47  5012.2  363.43
  5018.2  361.48  5024.7  363.88  5033.2  362.94  5048.6  363.83  5060.7  363.81
  5084.3  367.80  5090.3  366.90  5120.4  369.09  5236.2  372.85  5270.8  373.78
#Mann=6,-1,0
  4695.5   0.045       0  4866.1    0.16       0  4995.3    0.07       0
  4999.3    0.16       0  5048.6    0.07       0  5236.2   0.045       0
Bank Sta=4995.3,4999.3
Exp/Cntr=0.3,0.1

Chan Stop Cuts=-1