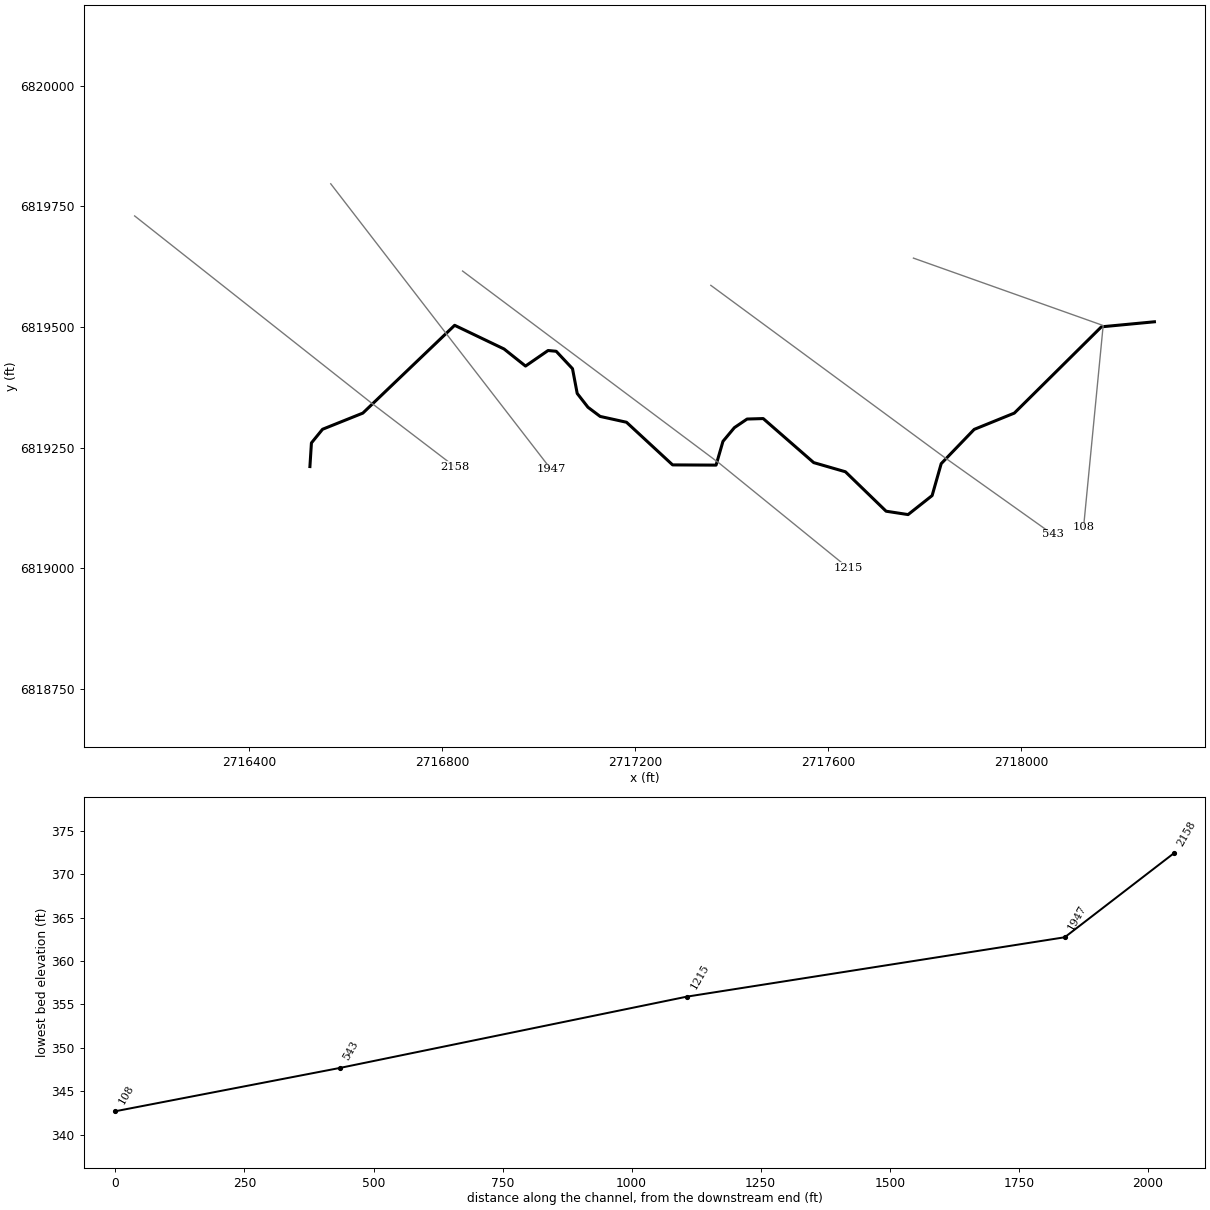
--- Twin Creek233.prj (project) ---

Proj Title=Twin Creek233 Base Level Engineering
Current Plan=p01
Default Exp/Contr=0.3,0.1
English Units
Geom File=g01
Flow File=f01
Plan File=p01
BEGIN DESCRIPTION:
Twin Creek233
END DESCRIPTION:

--- Twin Creek233.p01 (plan) ---

Plan Title=Multiple Run
Short Identifier=Multiple
Geom File=g01
Flow File=f01
Subcritical Flow
K Sum by GR= 0
Std Step Tol= 0.01
Critical Tol= 0.01
Num of Std Step Trials= 20
Max Error Tol= 0.3
Flow Tol Ratio= 0.001
Split Flow NTrial= 30
Split Flow Tol= 0.02
Split Flow Ratio= 0.02
Log Output Level= 0
Friction Slope Method= 1
Unsteady Friction Slope Method= 2
Unsteady Bridges Friction Slope Method= 1
Parabolic Critical Depth
Global Vel Dist=  1 , 1 , 1
Global Log Level= 0
CheckData=True
Encroach Param= -1, 0, 0, 0
BEGIN DESCRIPTION:
Multiple Run
END DESCRIPTION:

--- Twin Creek233.f01 (steady flow) ---

Flow Title=Multiple
Number of Profiles=7
Profile Names=10-year,25-year,50-year,1pct_min,100-year,1pct_plu,500-year
River Rch & RM= Twin Creek233,Reach-1,2158
     259     330     386     225     449     895     604
Boundary for River Rch & Prof#=Twin Creek233,Reach-1,1
Up Type=0
Dn Type=3
Dn Slope=0.005
Boundary for River Rch & Prof#=Twin Creek233,Reach-1,2
Up Type=0
Dn Type=3
Dn Slope=0.005
Boundary for River Rch & Prof#=Twin Creek233,Reach-1,3
Up Type=0
Dn Type=3
Dn Slope=0.005
Boundary for River Rch & Prof#=Twin Creek233,Reach-1,4
Up Type=0
Dn Type=3
Dn Slope=0.005
Boundary for River Rch & Prof#=Twin Creek233,Reach-1,5
Up Type=0
Dn Type=3
Dn Slope=0.005
Boundary for River Rch & Prof#=Twin Creek233,Reach-1,6
Up Type=0
Dn Type=3
Dn Slope=0.005
Boundary for River Rch & Prof#=Twin Creek233,Reach-1,7
Up Type=0
Dn Type=3
Dn Slope=0.005

--- Twin Creek233.g01 (geometry) ---

Geom Title=Existing Conditions

River Reach=Twin Creek233,Reach-1
Reach XY= 30
      2716526.00      6819211.00      2716529.14      6819259.97
      2716552.15      6819288.27      2716635.67      6819321.77
      2716825.91      6819503.71      2716928.29      6819454.65
      2716972.78      6819419.26      2717019.49      6819451.46
      2717036.32      6819449.89      2717070.13      6819413.81
      2717079.89      6819362.49      2717102.16      6819333.87
      2717127.43      6819314.89      2717182.02      6819302.81
      2717277.57      6819214.44      2717367.65      6819214.00
      2717381.91      6819263.21      2717405.57      6819291.63
      2717431.88      6819309.47      2717465.31      6819310.46
      2717569.96      6819219.18      2717635.67      6819200.20
      2717719.98      6819118.47      2717765.51      6819111.49
      2717815.35      6819150.89      2717834.16      6819217.04
      2717902.49      6819288.01      2717985.68      6819321.78
      2718166.18      6819500.57      2718276.00      6819511.00

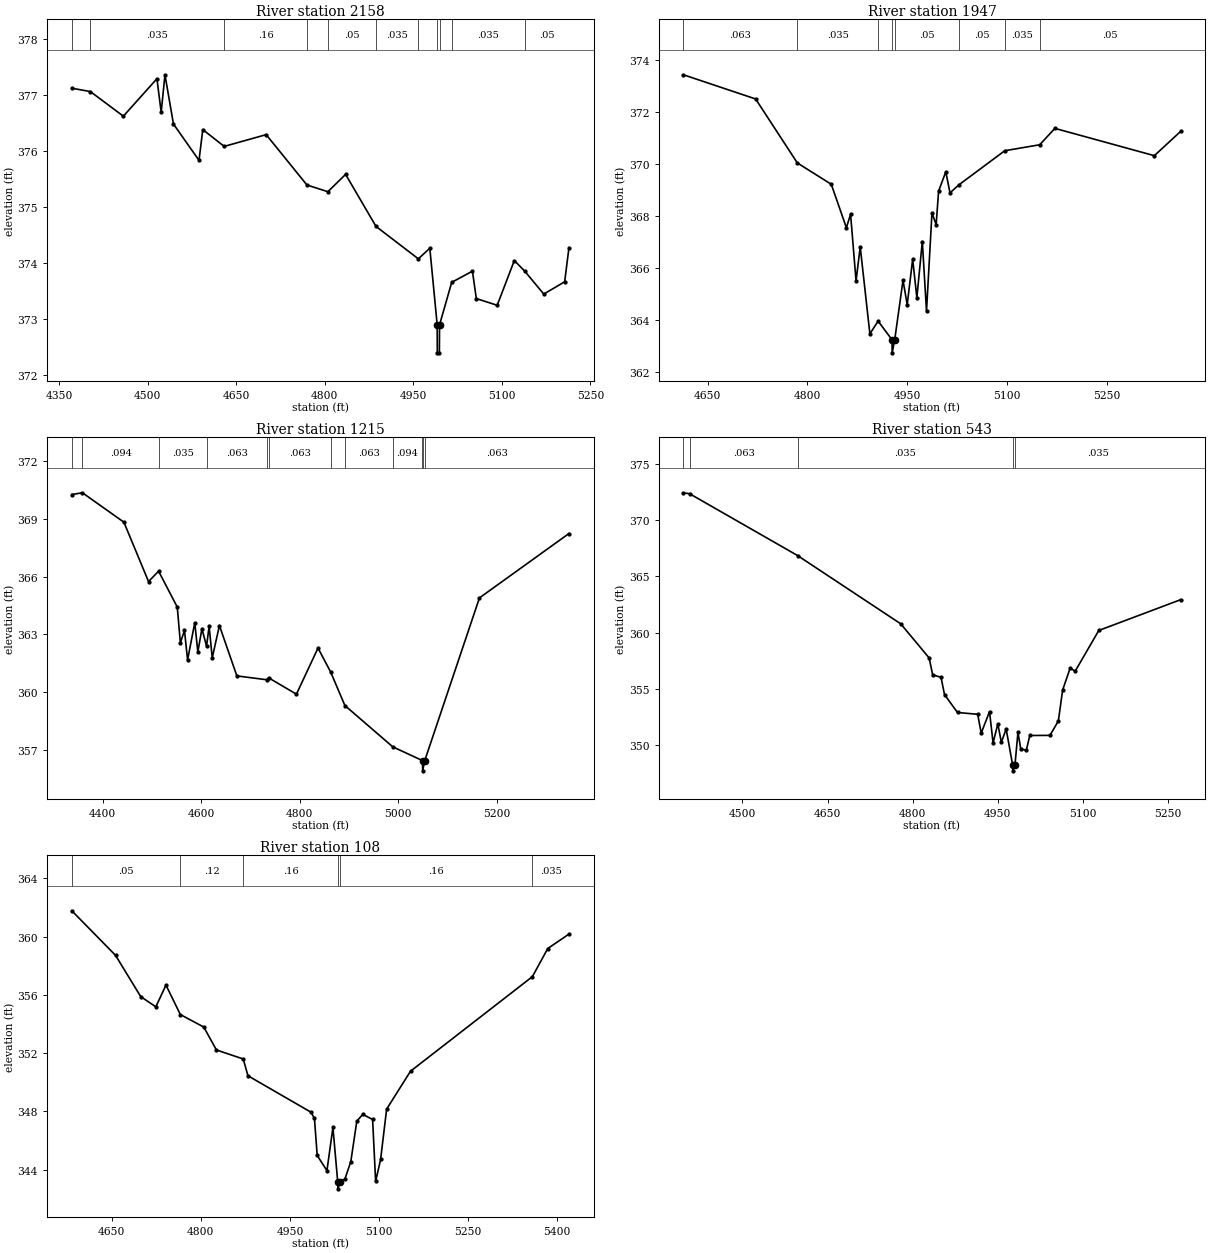
Type RM Length L Ch R = 1,2158,211,211,211
BEGIN DESCRIPTION:
Twin Creek2332158.232
END DESCRIPTION:
XS GIS Cut Line= 3
      2716162.83      6819730.35      2716656.16      6819340.62
      2716826.04      6819210.97
#Sta/Elev= 30
  4371.3  377.12  4402.7  377.06  4458.6  376.62  4515.5  377.29  4522.7  376.69
  4529.1  377.36  4543.5  376.48  4586.8  375.83  4593.2  376.38  4629.5  376.08
  4700.6  376.29  4769.7  375.39  4805.2  375.27  4835.2  375.58  4886.7  374.65
  4958.5  374.07  4977.9  374.26  4990.4  372.89  4990.6  372.39  4994.1  372.39
  4994.4  372.89  5015.0  373.65  5050.1  373.85  5056.7  373.36  5092.1  373.24
  5121.1  374.04  5138.8  373.85  5171.0  373.44  5206.4  373.66  5213.7  374.27
#Mann=11,-1,0
  4371.3    0.16       0  4402.7   0.035       0  4629.5    0.16       0
  4769.7   0.035       0  4805.2    0.05       0  4886.7   0.035       0
  4958.5    0.05       0  4990.4    0.05       0  4994.4    0.05       0
  5015.0   0.035       0  5138.8    0.05       0
Bank Sta=4990.4,4994.4
Exp/Cntr=0.3,0.1

Type RM Length L Ch R = 1,1947,732,732,732
BEGIN DESCRIPTION:
Twin Creek2331946.67
END DESCRIPTION:
XS GIS Cut Line= 3
      2716569.18      6819796.91      2716803.31      6819493.18
      2717025.57      6819205.41
#Sta/Elev= 30
  4613.6  373.42  4722.1  372.49  4784.8  370.03  4835.8  369.21  4858.5  367.54
  4864.8  368.06  4873.0  365.50  4879.3  366.80  4893.8  363.46  4906.2  363.95
  4927.1  363.23  4927.3  362.73  4931.1  363.23  4943.6  365.52  4949.9  364.58
  4958.1  366.33  4964.4  364.85  4972.6  367.01  4978.9  364.33  4987.1  368.11
  4993.4  367.66  4997.1  368.95  5007.9  369.69  5014.2  368.88  5027.6  369.19
  5096.5  370.50  5149.1  370.73  5171.8  371.36  5321.3  370.31  5360.7  371.24
#Mann=8,-1,0
  4613.6   0.063       0  4784.8   0.035       0  4906.2    0.05       0
  4927.1   0.035       0  4931.1    0.05       0  5027.6    0.05       0
  5096.5   0.035       0  5149.1    0.05       0
Bank Sta=4927.1,4931.1
Exp/Cntr=0.3,0.1

Type RM Length L Ch R = 1,1215,672,672,672
BEGIN DESCRIPTION:
Twin Creek2331215.06
END DESCRIPTION:
XS GIS Cut Line= 3
      2716842.36      6819616.17      2717374.14      6819218.01
      2717641.29      6819001.01
#Sta/Elev= 30
  4337.6  370.27  4359.1  370.36  4443.2  368.83  4493.2  365.74  4513.6  366.28
  4551.5  364.41  4557.8  362.55  4566.1  363.20  4572.4  361.66  4587.0  363.60
  4593.2  362.08  4601.5  363.28  4610.9  362.38  4616.1  363.41  4622.4  361.77
  4637.0  363.45  4672.4  360.83  4733.1  360.63  4736.8  360.73  4793.2  359.88
  4837.0  362.28  4862.7  361.03  4891.5  359.29  4988.6  357.14  5047.5  356.44
  5049.1  356.39  5049.3  355.89  5053.1  356.39  5164.5  364.89  5346.1  368.24
#Mann=12,-1,0
  4337.6   0.063       0  4359.1   0.094       0  4513.6   0.035       0
  4610.9   0.063       0  4733.1   0.035       0  4736.8   0.063       0
  4862.7   0.094       0  4891.5   0.063       0  4988.6   0.094       0
  5047.5   0.063       0  5049.1    0.07       0  5053.1   0.063       0
Bank Sta=5049.1,5053.1
Exp/Cntr=0.3,0.1

Type RM Length L Ch R = 1,543,435,435,435
BEGIN DESCRIPTION:
Twin Creek233543.03
END DESCRIPTION:
XS GIS Cut Line= 3
      2717356.78      6819586.51      2717839.10      6819231.35
      2718065.51      6819070.34
#Sta/Elev= 30
  4395.9  372.46  4407.0  372.37  4597.1  366.87  4779.2  360.78  4829.3  357.74
  4835.5  356.23  4850.2  356.02  4856.4  354.47  4879.3  352.88  4914.9  352.72
  4921.1  351.04  4935.8  352.96  4942.0  350.16  4950.4  351.87  4956.6  350.22
  4965.1  351.41  4976.6  348.18  4976.9  347.68  4980.6  348.18  4985.9  351.11
  4990.9  349.62  5000.7  349.52  5006.8  350.83  5042.4  350.84  5057.2  352.13
  5064.7  354.88  5078.1  356.85  5086.7  356.55  5128.5  360.19  5272.7  362.93
#Mann=5,-1,0
  4395.9    0.05       0  4407.0   0.063       0  4597.1   0.035       0
  4976.6   0.035       0  4980.6   0.035       0
Bank Sta=4976.6,4980.6
Exp/Cntr=0.3,0.1

Type RM Length L Ch R = 1,108,0,0,0
BEGIN DESCRIPTION:
Twin Creek233107.854
END DESCRIPTION:
XS GIS Cut Line= 3
      2717776.65      6819642.94      2718169.78      6819503.26
      2718129.20      6819085.43
#Sta/Elev= 30
  4582.8  361.77  4656.4  358.71  4698.8  355.88  4724.2  355.18  4741.3  356.67
  4765.5  354.65  4805.0  353.79  4826.2  352.22  4871.4  351.60  4879.3  350.45
  4985.4  347.95  4991.3  347.52  4995.9  344.98  5012.3  343.94  5022.4  346.90
  5030.4  343.19  5030.7  342.69  5034.4  343.19  5042.5  343.35  5052.5  344.56
  5062.6  347.33  5072.6  347.80  5089.2  347.45  5094.3  343.20  5102.7  344.71
  5112.8  348.16  5153.0  350.76  5358.2  357.25  5384.1  359.18  5419.8  360.17
#Mann=6,-1,0
  4582.8    0.05       0  4765.5    0.12       0  4871.4    0.16       0
  5030.4    0.07       0  5034.4    0.16       0  5358.2   0.035       0
Bank Sta=5030.4,5034.4
Exp/Cntr=0.3,0.1

Chan Stop Cuts=-1