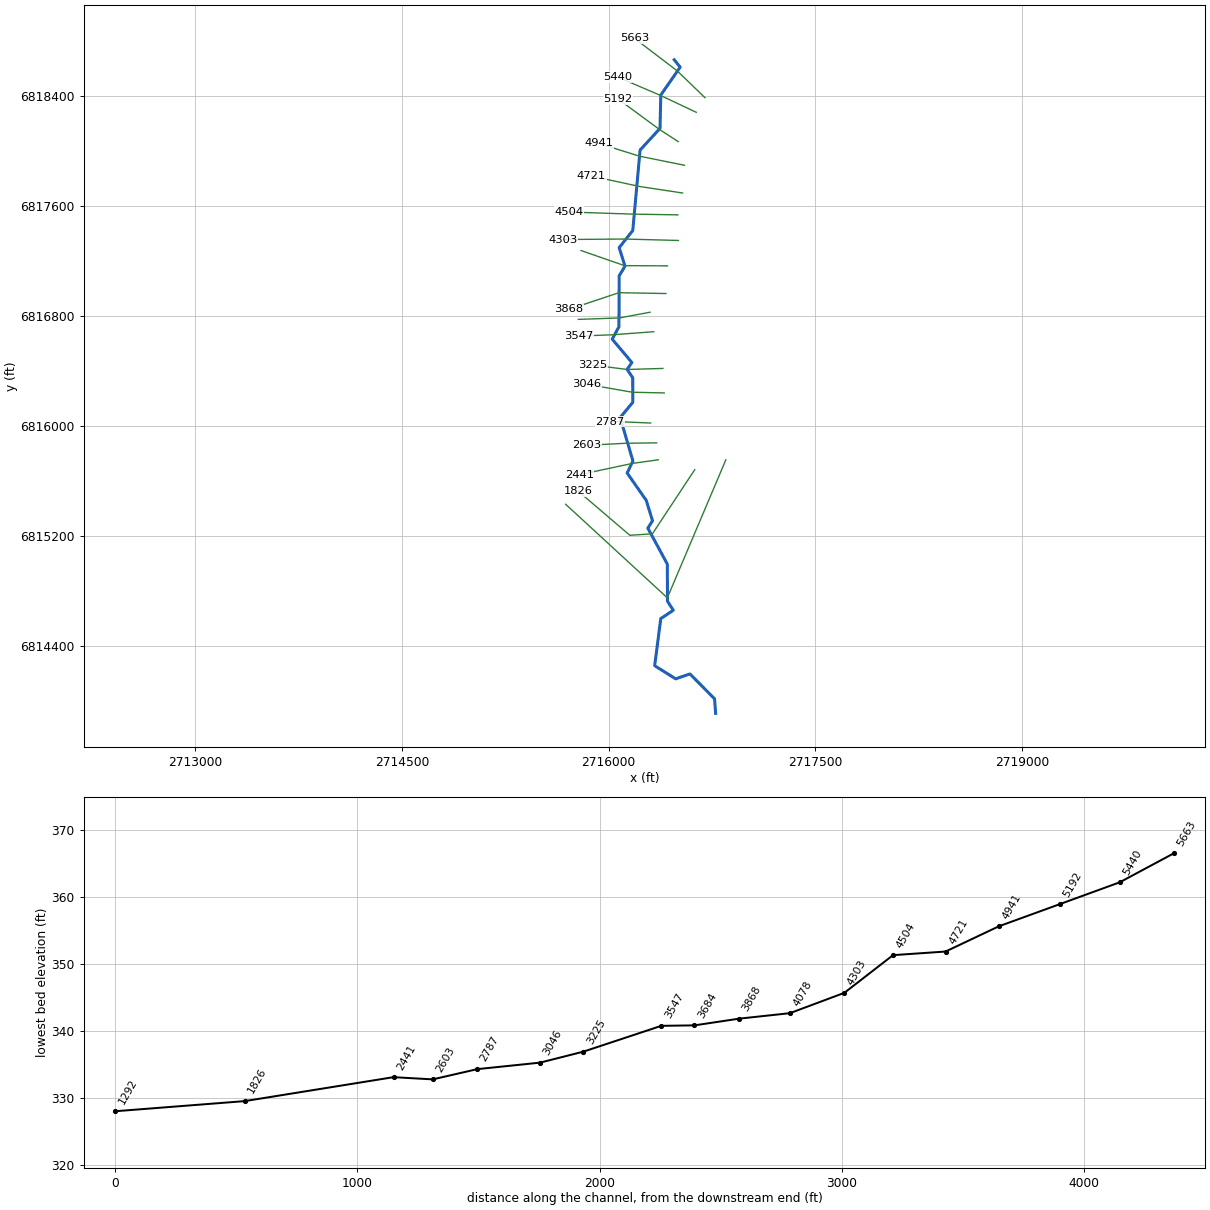
--- Twin Creek234.prj (project) ---

Proj Title=Twin Creek234 Base Level Engineering
Current Plan=p01
Default Exp/Contr=0.3,0.1
English Units
Geom File=g01
Flow File=f01
Plan File=p01
BEGIN DESCRIPTION:
Twin Creek234
END DESCRIPTION:

--- Twin Creek234.p01 (plan) ---

Plan Title=Multiple Run
Short Identifier=Multiple
Geom File=g01
Flow File=f01
Subcritical Flow
K Sum by GR= 0
Std Step Tol= 0.01
Critical Tol= 0.01
Num of Std Step Trials= 20
Max Error Tol= 0.3
Flow Tol Ratio= 0.001
Split Flow NTrial= 30
Split Flow Tol= 0.02
Split Flow Ratio= 0.02
Log Output Level= 0
Friction Slope Method= 1
Unsteady Friction Slope Method= 2
Unsteady Bridges Friction Slope Method= 1
Parabolic Critical Depth
Global Vel Dist=  1 , 1 , 1
Global Log Level= 0
CheckData=True
Encroach Param= -1, 0, 0, 0
BEGIN DESCRIPTION:
Multiple Run
END DESCRIPTION:

--- Twin Creek234.f01 (steady flow) ---

Flow Title=Multiple
Number of Profiles=7
Profile Names=10-year,25-year,50-year,1pct_min,100-year,1pct_plu,500-year
River Rch & RM= Twin Creek234,Reach-1,5663
     387     504     596     350     698    1393     958
Boundary for River Rch & Prof#=Twin Creek234,Reach-1,1
Up Type=0
Dn Type=3
Dn Slope=0.005
Boundary for River Rch & Prof#=Twin Creek234,Reach-1,2
Up Type=0
Dn Type=3
Dn Slope=0.005
Boundary for River Rch & Prof#=Twin Creek234,Reach-1,3
Up Type=0
Dn Type=3
Dn Slope=0.005
Boundary for River Rch & Prof#=Twin Creek234,Reach-1,4
Up Type=0
Dn Type=3
Dn Slope=0.005
Boundary for River Rch & Prof#=Twin Creek234,Reach-1,5
Up Type=0
Dn Type=3
Dn Slope=0.005
Boundary for River Rch & Prof#=Twin Creek234,Reach-1,6
Up Type=0
Dn Type=3
Dn Slope=0.005
Boundary for River Rch & Prof#=Twin Creek234,Reach-1,7
Up Type=0
Dn Type=3
Dn Slope=0.005

--- Twin Creek234.g01 (geometry) ---

Geom Title=Existing Conditions

River Reach=Twin Creek234,Reach-1
Reach XY= 30
      2716476.00      6818661.00      2716518.73      6818607.67
      2716378.24      6818405.07      2716372.46      6818162.46
      2716228.06      6818005.15      2716174.79      6817420.59
      2716076.25      6817295.78      2716118.44      6817161.00
      2716076.18      6817091.02      2716074.60      6816720.65
      2716025.60      6816631.13      2716168.45      6816461.00
      2716133.81      6816411.10      2716174.63      6816350.57
      2716174.94      6816171.43      2716083.55      6816061.00
      2716175.85      6815745.58      2716134.07      6815657.69
      2716272.38      6815459.50      2716318.20      6815310.90
      2716284.02      6815257.66      2716425.61      6814995.84
      2716426.67      6814726.15      2716468.74      6814660.70
      2716377.99      6814599.81      2716333.88      6814257.42
      2716485.86      6814161.96      2716589.38      6814197.46
      2716768.26      6814017.22      2716776.00      6813911.00

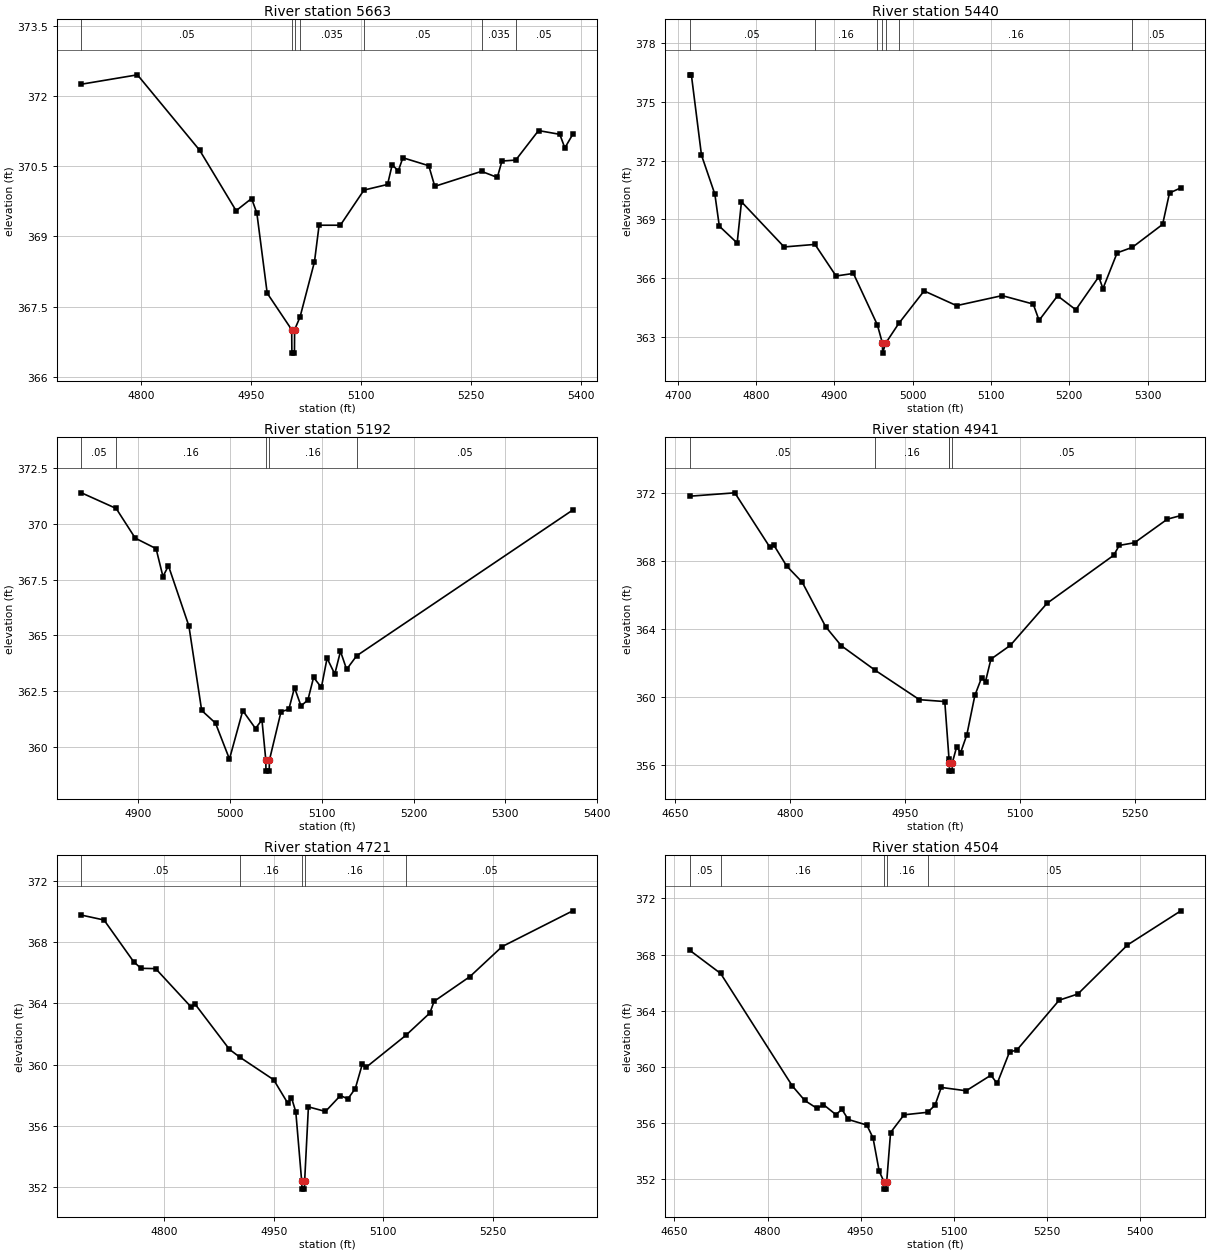
Type RM Length L Ch R = 1,5663,223,223,223
BEGIN DESCRIPTION:
Twin Creek2345662.838
END DESCRIPTION:
XS GIS Cut Line= 3
      2716698.79      6818385.75      2716496.74      6818581.03
      2716187.42      6818817.09
#Sta/Elev= 30
  4719.0  372.25  4795.3  372.45  4880.2  370.84  4929.9  369.55  4951.0  369.81
  4958.2  369.50  4972.3  367.79  5005.7  367.01  5006.0  366.51  5009.5  366.51
  5009.7  367.01  5017.1  367.28  5036.8  368.46  5043.1  369.24  5072.1  369.24
  5104.3  369.99  5136.5  370.11  5142.8  370.53  5151.1  370.40  5157.4  370.68
  5192.7  370.51  5200.9  370.07  5264.7  370.39  5286.2  370.26  5292.5  370.61
  5311.3  370.63  5342.4  371.26  5371.4  371.18  5378.3  370.89  5389.1  371.18
#Mann=7,-1,0
  4719.0    0.05       0  5005.7    0.05       0  5009.7    0.05       0
  5017.1   0.035       0  5104.3    0.05       0  5264.7   0.035       0
  5311.3    0.05       0
Bank Sta=5005.7,5009.7
Exp/Cntr=0.3,0.1

Type RM Length L Ch R = 1,5440,248,248,248
BEGIN DESCRIPTION:
Twin Creek2345440.47
END DESCRIPTION:
XS GIS Cut Line= 3
      2716635.18      6818279.67      2716373.20      6818403.52
      2716062.66      6818536.51
#Sta/Elev= 30
  4714.9  376.37  4717.2  376.37  4730.1  372.28  4747.2  370.29  4752.9  368.66
  4775.7  367.80  4781.2  369.90  4835.7  367.60  4875.1  367.73  4902.0  366.12
  4924.2  366.25  4954.8  363.63  4961.3  362.69  4961.5  362.19  4965.3  362.69
  4982.1  363.70  5014.5  365.36  5056.0  364.61  5114.2  365.12  5153.9  364.69
  5161.4  363.86  5185.0  365.11  5208.3  364.40  5237.6  366.08  5243.0  365.48
  5261.1  367.30  5280.5  367.58  5319.2  368.75  5328.0  370.35  5342.5  370.61
#Mann=7,-1,0
  4714.9    0.05       0  4875.1    0.16       0  4954.8   0.035       0
  4961.3    0.07       0  4965.3   0.035       0  4982.1    0.16       0
  5280.5    0.05       0
Bank Sta=4961.3,4965.3
Exp/Cntr=0.3,0.1

Type RM Length L Ch R = 1,5192,251,251,251
BEGIN DESCRIPTION:
Twin Creek2345192.4
END DESCRIPTION:
XS GIS Cut Line= 3
      2716504.11      6818066.67      2716366.03      6818156.58
      2716067.58      6818376.51
#Sta/Elev= 30
  4838.0  371.39  4875.8  370.69  4896.6  369.36  4919.3  368.89  4926.8  367.64
  4932.8  368.12  4955.1  365.42  4969.0  361.64  4984.1  361.07  4999.3  359.46
  5013.8  361.63  5027.7  360.83  5034.7  361.22  5038.9  359.42  5039.1  358.92
  5042.6  358.92  5042.9  359.42  5055.5  361.58  5064.0  361.69  5070.2  362.66
  5077.3  361.84  5084.8  362.11  5091.0  363.12  5099.5  362.67  5105.7  363.98
  5114.1  363.27  5120.3  364.29  5127.0  363.48  5138.0  364.09  5373.5  370.62
#Mann=5,-1,0
  4838.0    0.05       0  4875.8    0.16       0  5038.9    0.07       0
  5042.9    0.16       0  5138.0    0.05       0
Bank Sta=5038.9,5042.9
Exp/Cntr=0.3,0.1

Type RM Length L Ch R = 1,4941,220,220,220
BEGIN DESCRIPTION:
Twin Creek2344941.08
END DESCRIPTION:
XS GIS Cut Line= 3
      2716550.30      6817894.58      2716223.54      6817960.64
      2715929.21      6818052.82
#Sta/Elev= 30
  4668.7  371.82  4727.8  372.02  4773.4  368.83  4778.5  368.96  4795.5  367.71
  4815.9  366.75  4846.5  364.13  4866.9  363.01  4911.3  361.56  4969.0  359.83
  5002.1  359.72  5007.6  356.36  5008.0  356.12  5008.2  355.62  5011.7  355.62
  5012.0  356.12  5017.6  357.05  5022.8  356.71  5030.9  357.76  5041.4  360.08
  5050.1  361.11  5055.3  360.90  5062.4  362.22  5087.7  363.03  5135.7  365.51
  5222.8  368.34  5230.0  368.92  5250.0  369.08  5292.9  370.47  5310.5  370.68
#Mann=5,-1,0
  4668.7    0.05       0  4911.3    0.16       0  5007.6    0.05       0
  5008.0    0.07       0  5012.0    0.05       0
Bank Sta=5008,5012
Exp/Cntr=0.3,0.1

Type RM Length L Ch R = 1,4721,217,217,217
BEGIN DESCRIPTION:
Twin Creek2344720.86
END DESCRIPTION:
XS GIS Cut Line= 3
      2716536.58      6817692.94      2716226.79      6817739.91
      2715874.56      6817816.10
#Sta/Elev= 30
  4686.2  369.77  4717.1  369.45  4757.6  366.73  4767.7  366.29  4787.9  366.27
  4836.7  363.75  4841.8  363.96  4889.1  360.99  4903.6  360.47  4949.8  359.00
  4969.2  357.46  4974.2  357.83  4980.1  356.90  4988.2  352.35  4988.5  351.85
  4992.0  351.85  4992.2  352.35  4997.4  357.23  5020.8  356.93  5041.3  357.97
  5051.5  357.75  5061.7  358.43  5071.2  360.01  5076.3  359.81  5131.1  361.91
  5164.0  363.37  5169.7  364.13  5218.9  365.75  5263.0  367.71  5359.9  370.05
#Mann=5,-1,0
  4686.2    0.05       0  4903.6    0.16       0  4988.2    0.07       0
  4992.2    0.16       0  5131.1    0.05       0
Bank Sta=4988.2,4992.2
Exp/Cntr=0.3,0.1

Type RM Length L Ch R = 1,4504,201,201,201
BEGIN DESCRIPTION:
Twin Creek2344504.23
END DESCRIPTION:
XS GIS Cut Line= 3
      2716501.65      6817534.11      2716174.45      6817539.55
      2715710.04      6817554.78
#Sta/Elev= 30
  4674.3  368.32  4724.4  366.66  4840.0  358.65  4860.0  357.62  4880.0  357.05
  4890.0  357.33  4910.0  356.62  4920.0  356.98  4930.0  356.27  4960.0  355.87
  4970.0  354.96  4980.0  352.58  4988.0  351.81  4988.2  351.31  4991.7  351.31
  4992.0  351.81  4998.3  355.34  5020.0  356.60  5058.2  356.78  5070.0  357.29
  5080.0  358.55  5120.1  358.31  5160.1  359.42  5170.1  358.83  5190.1  361.08
  5201.7  361.20  5270.1  364.76  5300.2  365.20  5380.2  368.69  5466.2  371.12
#Mann=5,-1,0
  4674.3    0.05       0  4724.4    0.16       0  4988.0    0.07       0
  4992.0    0.16       0  5058.2    0.05       0
Bank Sta=4988,4992
Exp/Cntr=0.3,0.1

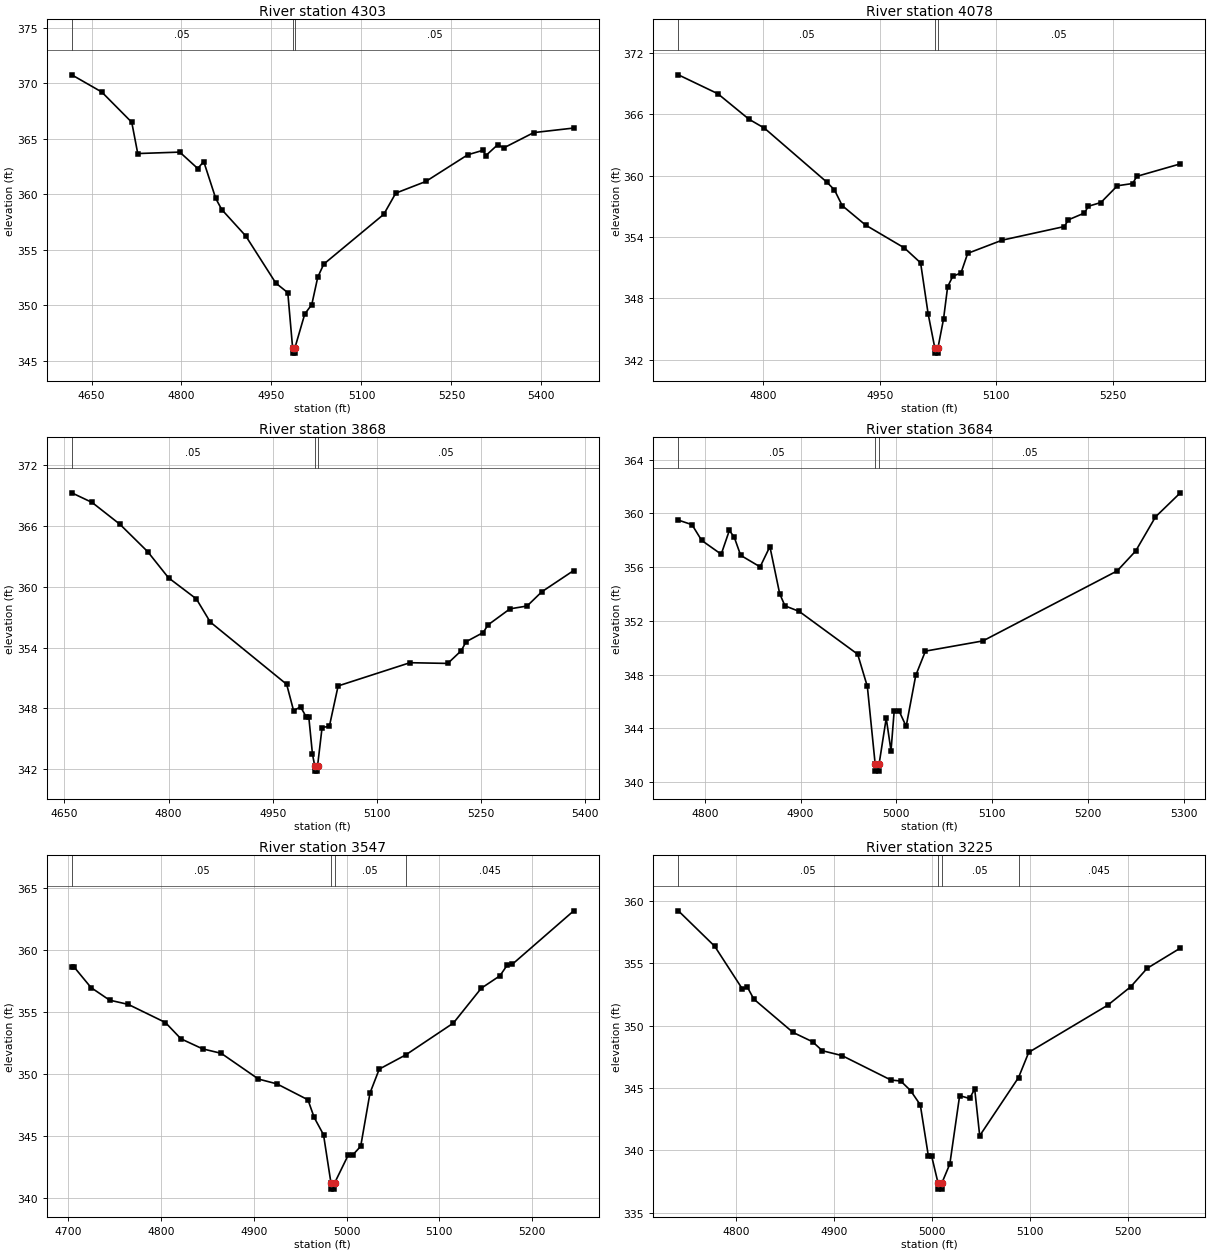
Type RM Length L Ch R = 1,4303,225,225,225
BEGIN DESCRIPTION:
Twin Creek2344303.15
END DESCRIPTION:
XS GIS Cut Line= 3
      2716505.94      6817348.04      2716114.30      6817358.50
      2715669.40      6817354.72
#Sta/Elev= 30
  4617.1  370.78  4667.1  369.23  4717.1  366.50  4727.1  363.68  4797.1  363.81
  4827.1  362.33  4837.1  362.96  4857.1  359.63  4867.1  358.63  4907.1  356.25
  4957.2  352.00  4977.2  351.13  4985.2  346.18  4985.4  345.68  4988.9  345.68
  4989.2  346.18  5005.5  349.21  5017.2  350.06  5027.2  352.54  5037.2  353.71
  5137.2  358.20  5157.2  360.11  5207.2  361.16  5277.2  363.57  5302.4  363.97
  5307.4  363.50  5327.2  364.48  5337.2  364.19  5387.2  365.57  5453.8  365.98
#Mann=3,-1,0
  4617.1    0.05       0  4985.2    0.05       0  4989.2    0.05       0
Bank Sta=4985.2,4989.2
Exp/Cntr=0.3,0.1

Type RM Length L Ch R = 1,4078,210,210,210
BEGIN DESCRIPTION:
Twin Creek2344078.38
END DESCRIPTION:
XS GIS Cut Line= 3
      2716426.83      6817163.52      2716115.14      6817164.99
      2715799.53      6817274.91
#Sta/Elev= 30
  4690.8  369.86  4741.6  368.01  4781.6  365.52  4801.6  364.64  4881.6  359.38
  4891.6  358.61  4901.6  357.07  4931.6  355.17  4981.6  352.93  5002.5  351.47
  5012.2  346.48  5020.8  343.14  5021.0  342.64  5024.5  342.64  5024.8  343.14
  5032.0  345.97  5037.3  349.14  5043.9  350.15  5054.5  350.49  5063.1  352.40
  5107.5  353.69  5187.4  355.02  5192.7  355.68  5213.2  356.34  5218.5  357.01
  5234.5  357.37  5255.7  359.01  5275.4  359.23  5280.7  359.93  5336.7  361.15
#Mann=3,-1,0
  4690.8    0.05       0  5020.8    0.05       0  5024.8    0.05       0
Bank Sta=5020.8,5024.8
Exp/Cntr=0.3,0.1

Type RM Length L Ch R = 1,3868,184,184,184
BEGIN DESCRIPTION:
Twin Creek2343867.6
END DESCRIPTION:
XS GIS Cut Line= 3
      2716415.32      6816962.37      2716074.10      6816968.35
      2715712.34      6816847.47
#Sta/Elev= 30
  4660.6  369.26  4689.9  368.31  4729.9  366.16  4769.9  363.46  4799.9  360.88
  4840.0  358.80  4860.0  356.52  4970.0  350.38  4980.0  347.78  4990.0  348.16
  4998.4  347.14  5001.9  347.14  5007.2  343.47  5010.5  342.32  5010.7  341.82
  5014.2  341.82  5014.5  342.32  5021.0  346.12  5031.5  346.24  5044.1  350.22
  5147.5  352.51  5202.0  352.44  5221.3  353.69  5228.4  354.58  5252.9  355.48
  5260.0  356.24  5291.5  357.82  5316.2  358.10  5337.3  359.50  5383.3  361.60
#Mann=3,-1,0
  4660.6    0.05       0  5010.5    0.05       0  5014.5    0.05       0
Bank Sta=5010.5,5014.5
Exp/Cntr=0.3,0.1

Type RM Length L Ch R = 1,3684,137,137,137
BEGIN DESCRIPTION:
Twin Creek2343684.14
END DESCRIPTION:
XS GIS Cut Line= 3
      2716299.92      6816826.34      2716075.90      6816784.80
      2715780.11      6816774.53
#Sta/Elev= 30
  4772.5  359.50  4786.7  359.16  4796.8  357.99  4817.2  356.96  4825.7  358.73
  4830.8  358.23  4837.5  356.88  4857.8  356.02  4868.0  357.53  4878.2  354.03
  4883.7  353.12  4898.5  352.71  4959.6  349.52  4969.7  347.12  4977.9  341.32
  4978.1  340.82  4981.6  340.82  4981.9  341.32  4989.4  344.76  4994.4  342.33
  4997.7  345.30  5002.8  345.30  5010.2  344.15  5020.2  347.94  5030.3  349.75
  5090.3  350.51  5230.4  355.72  5249.7  357.20  5270.4  359.74  5296.3  361.53
#Mann=3,-1,0
  4772.5    0.05       0  4977.9    0.05       0  4981.9    0.05       0
Bank Sta=4977.9,4981.9
Exp/Cntr=0.3,0.1

Type RM Length L Ch R = 1,3547,322,322,322
BEGIN DESCRIPTION:
Twin Creek2343546.55
END DESCRIPTION:
XS GIS Cut Line= 3
      2716326.70      6816684.95      2716027.27      6816662.46
      2715786.41      6816653.44
#Sta/Elev= 30
  4703.6  358.59  4706.5  358.59  4724.4  356.97  4744.4  355.96  4764.5  355.62
  4804.6  354.16  4821.3  352.85  4844.7  352.04  4864.8  351.68  4904.9  349.61
  4924.9  349.22  4958.3  347.94  4965.0  346.52  4975.1  345.13  4983.1  341.25
  4983.3  340.75  4986.8  340.75  4987.1  341.25  5002.0  343.53  5007.0  343.53
  5015.2  344.20  5025.2  348.48  5035.2  350.41  5063.9  351.56  5115.2  354.12
  5145.2  356.92  5165.3  357.92  5173.4  358.80  5178.4  358.83  5244.9  363.15
#Mann=4,-1,0
  4703.6    0.05       0  4983.1    0.05       0  4987.1    0.05       0
  5063.9   0.045       0
Bank Sta=4983.1,4987.1
Exp/Cntr=0.3,0.1

Type RM Length L Ch R = 1,3225,179,179,179
BEGIN DESCRIPTION:
Twin Creek2343225.27
END DESCRIPTION:
XS GIS Cut Line= 3
      2716393.08      6816418.05      2716134.52      6816410.36
      2715882.36      6816442.65
#Sta/Elev= 30
  4740.7  359.21  4777.8  356.37  4806.2  352.93  4811.2  353.09  4817.8  352.13
  4857.8  349.46  4877.8  348.71  4887.8  347.99  4907.9  347.60  4957.9  345.64
  4967.9  345.56  4977.9  344.80  4987.9  343.65  4996.1  339.57  4999.4  339.57
  5006.0  337.39  5006.2  336.89  5009.7  336.89  5010.0  337.39  5018.1  338.91
  5028.1  344.39  5038.2  344.16  5043.5  344.91  5048.6  341.17  5088.3  345.84
  5098.7  347.86  5179.4  351.64  5202.9  353.12  5219.7  354.60  5253.6  356.22
#Mann=4,-1,0
  4740.7    0.05       0  5006.0    0.05       0  5010.0    0.05       0
  5088.3   0.045       0
Bank Sta=5006,5010
Exp/Cntr=0.3,0.1

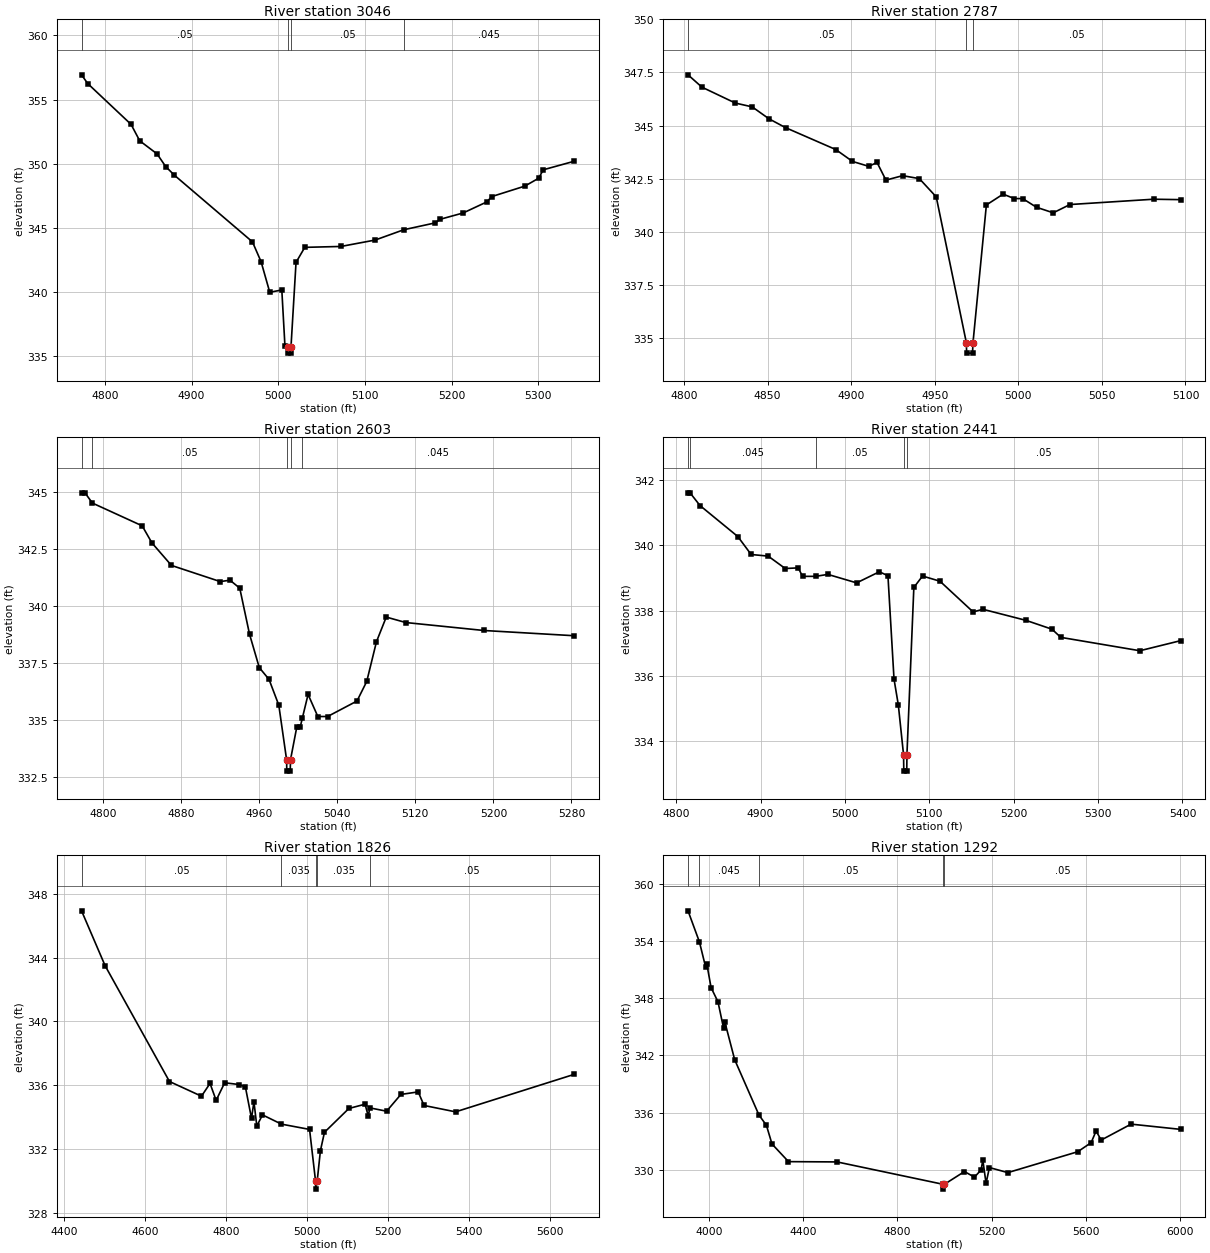
Type RM Length L Ch R = 1,3046,259,259,259
BEGIN DESCRIPTION:
Twin Creek2343045.83
END DESCRIPTION:
XS GIS Cut Line= 3
      2716403.08      6816239.91      2716172.14      6816244.98
      2715839.74      6816302.89
#Sta/Elev= 30
  4773.1  356.93  4780.2  356.25  4830.2  353.07  4840.2  351.79  4860.2  350.77
  4870.2  349.78  4880.2  349.11  4970.2  343.92  4980.2  342.37  4990.2  339.99
  5004.1  340.17  5007.7  335.82  5010.7  335.75  5011.0  335.25  5014.5  335.25
  5014.7  335.75  5020.5  342.32  5030.6  343.49  5072.3  343.56  5111.8  344.06
  5144.7  344.86  5181.3  345.40  5186.4  345.67  5213.3  346.17  5240.9  347.04
  5246.0  347.44  5284.4  348.26  5300.5  348.88  5305.6  349.53  5341.5  350.20
#Mann=4,-1,0
  4773.1    0.05       0  5010.7    0.05       0  5014.7    0.05       0
  5144.7   0.045       0
Bank Sta=5010.7,5014.7
Exp/Cntr=0.3,0.1

Type RM Length L Ch R = 1,2787,184,184,184
BEGIN DESCRIPTION:
Twin Creek2342787.04
END DESCRIPTION:
XS GIS Cut Line= 3
      2716304.32      6816021.16      2716107.51      6816029.61
      2716009.73      6816032.21
#Sta/Elev= 27
  4802.4  347.39  4810.7  346.81  4830.7  346.06  4840.8  345.88  4850.8  345.32
  4860.8  344.90  4890.8  343.87  4900.8  343.31  4910.5  343.08  4915.5  343.26
  4920.8  342.43  4930.8  342.64  4940.8  342.50  4950.9  341.64  4968.9  334.78
  4969.1  334.28  4972.6  334.28  4972.9  334.78  4980.9  341.26  4990.9  341.77
  4997.6  341.56  5002.6  341.56  5010.9  341.15  5020.9  340.89  5030.9  341.28
  5080.9  341.53  5097.2  341.51
#Mann=3,-1,0
  4802.4    0.05       0  4968.9    0.05       0  4972.9    0.05       0
Bank Sta=4968.9,4972.9
Exp/Cntr=0.3,0.1

Type RM Length L Ch R = 1,2603,162,162,162
BEGIN DESCRIPTION:
Twin Creek2342602.59
END DESCRIPTION:
XS GIS Cut Line= 3
      2716348.07      6815877.13      2716123.96      6815874.13
      2715843.57      6815859.46
#Sta/Elev= 30
  4778.0  344.98  4781.5  344.98  4789.1  344.53  4840.1  343.53  4850.1  342.78
  4870.1  341.79  4920.1  341.08  4930.1  341.14  4940.1  340.79  4950.1  338.77
  4960.1  337.30  4970.1  336.78  4980.1  335.65  4988.1  333.25  4988.3  332.75
  4991.8  332.75  4992.1  333.25  4998.6  334.70  5002.1  334.70  5004.3  335.09
  5010.1  336.12  5020.1  335.15  5030.1  335.15  5060.2  335.83  5070.2  336.69
  5080.2  338.44  5090.2  339.52  5110.2  339.28  5190.3  338.93  5282.9  338.70
#Mann=5,-1,0
  4778.0   0.045       0  4789.1    0.05       0  4988.1    0.05       0
  4992.1    0.05       0  5004.3   0.045       0
Bank Sta=4988.1,4992.1
Exp/Cntr=0.3,0.1

Type RM Length L Ch R = 1,2441,615,615,615
BEGIN DESCRIPTION:
Twin Creek2342440.61
END DESCRIPTION:
XS GIS Cut Line= 3
      2716360.08      6815754.02      2716173.27      6815728.07
      2715786.77      6815645.15
#Sta/Elev= 30
  4814.1  341.61  4816.5  341.61  4828.3  341.22  4873.1  340.27  4888.9  339.72
  4909.1  339.67  4929.3  339.29  4944.7  339.31  4949.8  339.05  4965.3  339.05
  4979.8  339.11  5013.9  338.85  5040.8  339.19  5051.0  339.07  5058.2  335.90
  5063.3  335.11  5069.5  333.58  5069.8  333.08  5073.3  333.08  5073.5  333.58
  5081.7  338.71  5092.0  339.06  5112.7  338.90  5151.9  337.96  5163.6  338.04
  5214.7  337.70  5245.4  337.43  5255.8  337.18  5349.5  336.77  5398.0  337.08
#Mann=5,-1,0
  4814.1    0.05       0  4816.5   0.045       0  4965.3    0.05       0
  5069.5    0.05       0  5073.5    0.05       0
Bank Sta=5069.5,5073.5
Exp/Cntr=0.3,0.1

Type RM Length L Ch R = 1,1826,534,534,534
BEGIN DESCRIPTION:
Twin Creek2341826.23
END DESCRIPTION:
XS GIS Cut Line= 4
      2716624.57      6815682.20      2716317.39      6815216.19
      2716153.85      6815205.25      2715778.21      6815526.46
#Sta/Elev= 30
  4444.1  346.93  4502.3  343.49  4661.1  336.24  4740.1  335.32  4761.2  336.12
  4776.3  335.06  4797.3  336.16  4833.5  336.05  4848.5  335.90  4863.6  333.93
  4869.6  334.97  4876.7  333.45  4890.7  334.15  4937.6  333.57  5006.9  333.24
  5021.7  330.00  5021.9  329.50  5025.7  330.00  5033.7  331.91  5043.7  333.06
  5103.9  334.55  5143.9  334.82  5151.9  334.07  5155.5  334.59  5197.1  334.38
  5232.3  335.43  5275.1  335.59  5289.4  334.74  5367.3  334.34  5660.4  336.69
#Mann=5,-1,0
  4444.1    0.05       0  4937.6   0.035       0  5021.7   0.035       0
  5025.7   0.035       0  5155.5    0.05       0
Bank Sta=5021.7,5025.7
Exp/Cntr=0.3,0.1

Type RM Length L Ch R = 1,1292,0,0,0
BEGIN DESCRIPTION:
Twin Creek2341292.059
END DESCRIPTION:
XS GIS Cut Line= 3
      2716850.22      6815753.92      2716425.60      6814750.79
      2715687.73      6815430.91
#Sta/Elev= 30
  3910.7  357.15  3959.3  353.88  3985.1  351.29  3990.5  351.58  4008.7  349.10
  4037.9  347.62  4061.5  344.87  4067.0  345.51  4108.9  341.55  4212.1  335.75
  4243.6  334.68  4267.3  332.72  4337.4  330.87  4543.7  330.84  4995.2  328.49
  4995.4  327.99  4999.2  328.49  5084.7  329.83  5127.2  329.25  5155.5  330.00
  5162.7  331.04  5176.5  328.60  5190.7  330.25  5269.0  329.72  5566.1  331.91
  5622.8  332.86  5643.8  334.08  5665.4  333.13  5792.4  334.80  6003.5  334.25
#Mann=5,-1,0
  3910.7    0.05       0  3959.3   0.045       0  4212.1    0.05       0
  4995.2    0.05       0  4999.2    0.05       0
Bank Sta=4995.2,4999.2
Exp/Cntr=0.3,0.1

Chan Stop Cuts=-1