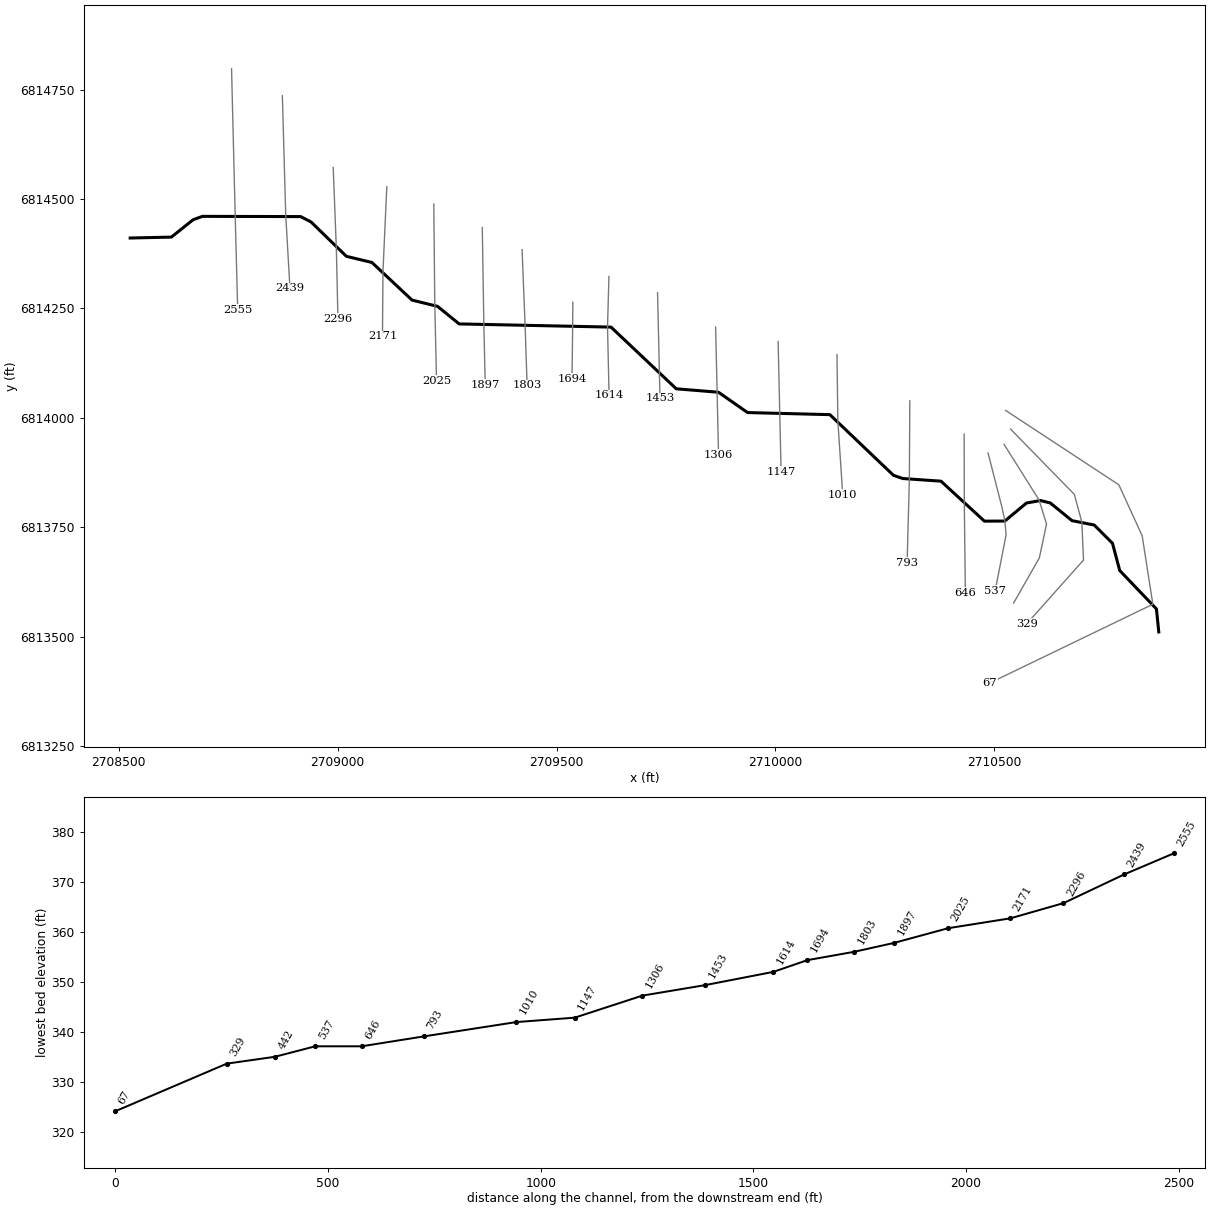
--- Twin Creek236.prj (project) ---

Proj Title=Twin Creek236 Base Level Engineering
Current Plan=p01
Default Exp/Contr=0.3,0.1
English Units
Geom File=g01
Flow File=f01
Plan File=p01
Y Axis Title=Elevation
X Axis Title(PF)=Main Channel Distance
X Axis Title(XS)=Station
BEGIN DESCRIPTION:
Twin Creek236
END DESCRIPTION:
DSS Export Rating Curves= 0
DSS Export Rating Curve Sorted= 0
DSS Export Volume Flow Curves= 0
DXF OffsetX= 0
DXF OffsetY= 0
DXF ScaleX= 1
DXF ScaleY= 10

--- Twin Creek236.p01 (plan) ---

Plan Title=Multiple Run
Short Identifier=Multiple
Geom File=g01
Flow File=f01
Subcritical Flow
K Sum by GR= 0
Std Step Tol= 0.01
Critical Tol= 0.01
Num of Std Step Trials= 20
Max Error Tol= 0.3
Flow Tol Ratio= 0.001
Split Flow NTrial= 30
Split Flow Tol= 0.02
Split Flow Ratio= 0.02
Log Output Level= 0
Friction Slope Method= 1
Unsteady Friction Slope Method= 2
Unsteady Bridges Friction Slope Method= 1
Parabolic Critical Depth
Global Vel Dist=  1 , 1 , 1
Global Log Level= 0
CheckData=True
Encroach Param= -1, 0, 0, 0
BEGIN DESCRIPTION:
Multiple Run
END DESCRIPTION:

--- Twin Creek236.f01 (steady flow) ---

Flow Title=Multiple
Number of Profiles=7
Profile Names=10-year,25-year,50-year,1pct_min,100-year,1pct_plu,500-year
River Rch & RM= Twin Creek236,Reach-1,2555
     155     190     216     123     246     490     314
Boundary for River Rch & Prof#=Twin Creek236,Reach-1,1
Up Type=0
Dn Type=3
Dn Slope=0.005
Boundary for River Rch & Prof#=Twin Creek236,Reach-1,2
Up Type=0
Dn Type=3
Dn Slope=0.005
Boundary for River Rch & Prof#=Twin Creek236,Reach-1,3
Up Type=0
Dn Type=3
Dn Slope=0.005
Boundary for River Rch & Prof#=Twin Creek236,Reach-1,4
Up Type=0
Dn Type=3
Dn Slope=0.005
Boundary for River Rch & Prof#=Twin Creek236,Reach-1,5
Up Type=0
Dn Type=3
Dn Slope=0.005
Boundary for River Rch & Prof#=Twin Creek236,Reach-1,6
Up Type=0
Dn Type=3
Dn Slope=0.005
Boundary for River Rch & Prof#=Twin Creek236,Reach-1,7
Up Type=0
Dn Type=3
Dn Slope=0.005

--- Twin Creek236.g01 (geometry) ---

Geom Title=Existing Conditions
Program Version=4.10

River Reach=Twin Creek236   ,Reach-1
Reach XY= 30
        2708526.        6814411.      2708620.13       6814413.1
      2708669.93       6814452.9      2708691.21      6814460.49
      2708915.56      6814459.95      2708939.31       6814447.6
      2709019.96      6814369.18      2709078.28      6814355.13
      2709169.95      6814269.16      2709228.17      6814254.86
      2709277.55      6814214.75      2709624.54      6814207.46
      2709773.57      6814066.52      2709870.02      6814058.64
       2709936.5      6814012.22      2710124.54      6814007.46
      2710269.83      6813868.86      2710291.22      6813861.53
      2710378.42      6813855.46      2710477.64      6813764.14
      2710524.26      6813764.37       2710573.8      6813805.59
      2710605.82      6813811.29       2710628.2      6813805.66
      2710677.76      6813765.26      2710728.55      6813755.27
      2710770.25      6813713.54      2710786.79      6813651.34
      2710870.67      6813563.51        2710876.        6813511.

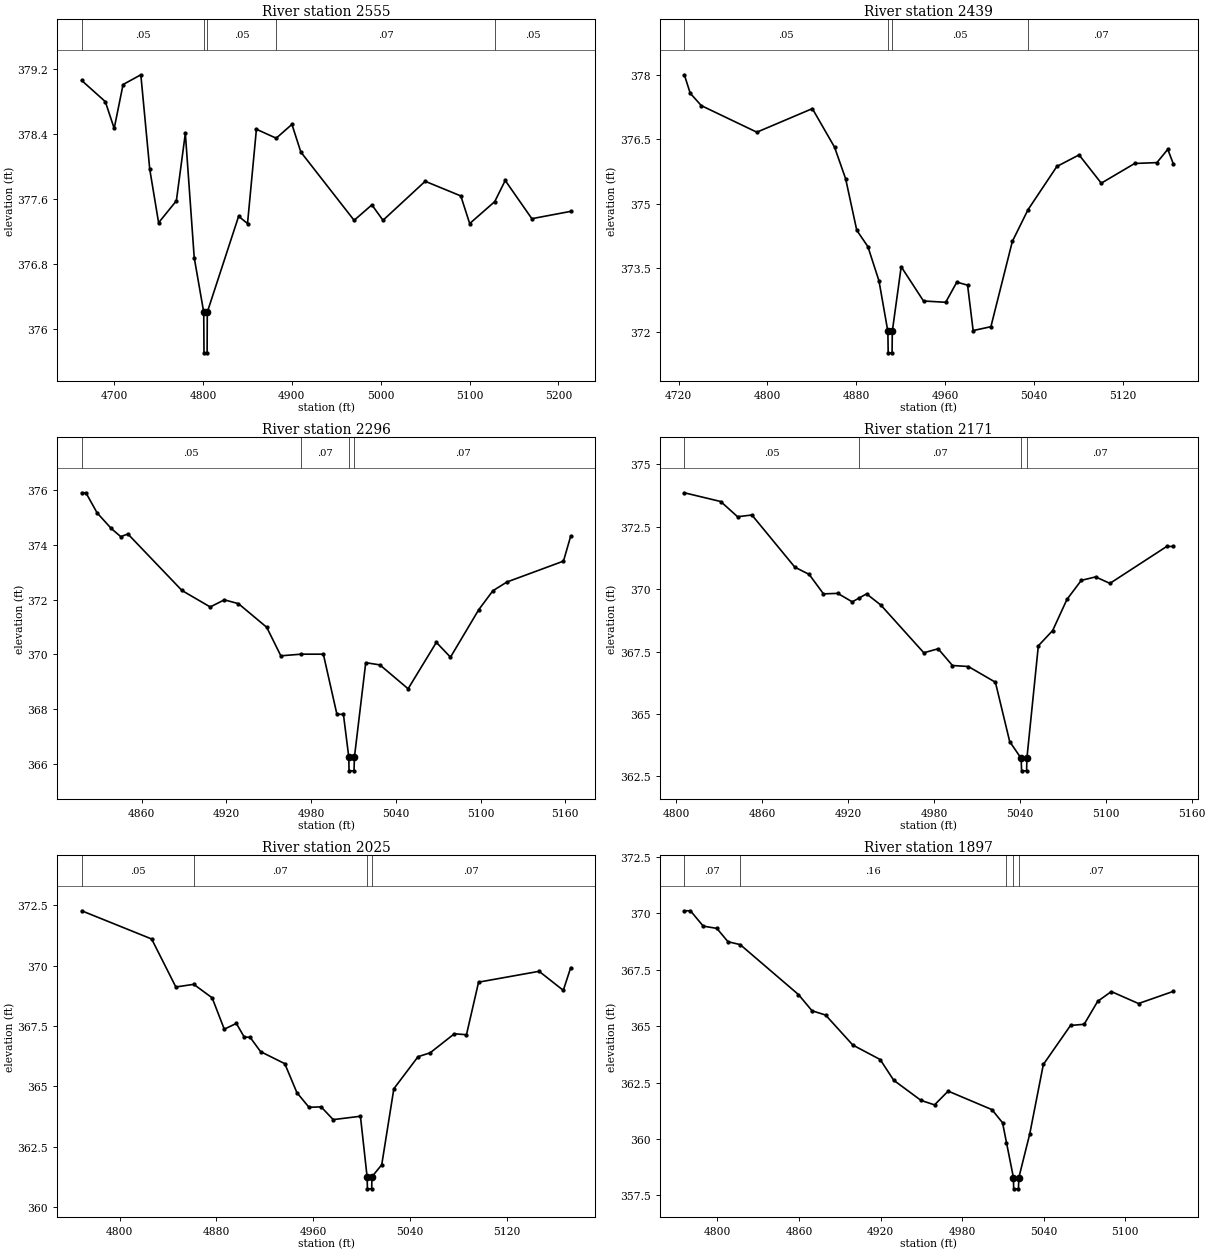
Type RM Length L Ch R = 1 ,2555    ,116,116,116
BEGIN DESCRIPTION:
Twin Creek2362506.04
END DESCRIPTION:
XS GIS Cut Line= 3
      2708757.59      6814797.62      2708765.95      6814461.12
      2708771.62      6814247.29
#Sta/Elev= 30
  4663.4  379.06    4690   378.8    4700  378.47    4710  379.01    4730  379.13
    4740  377.97    4750  377.31    4770  377.58  4780.1  378.41  4790.1  376.88
  4800.8  376.21  4801.1  375.71  4804.6  375.71  4804.8  376.21  4840.1  377.39
  4850.1   377.3  4860.1  378.46  4882.4  378.35  4900.1  378.52  4910.1  378.18
  4970.1  377.34  4990.1  377.53  5002.6  377.34  5050.1  377.82  5090.2  377.64
  5100.2   377.3  5128.4  377.57  5140.2  377.83  5170.2  377.36  5213.9  377.45
#Mann= 5 ,-1 , 0
  4663.4     .05       0  4800.8     .07       0  4804.8     .05       0
  4882.4     .07       0  5128.4     .05       0
Bank Sta=4800.8,4804.8
XS Rating Curve= 0 ,0
Exp/Cntr=0.3,0.1

Type RM Length L Ch R = 1 ,2439    ,143,143,143
BEGIN DESCRIPTION:
Mapping XS 6c88033a
END DESCRIPTION:
XS GIS Cut Line= 3
      2708873.67      6814736.27      2708881.34      6814464.51
      2708891.02      6814296.25
#Sta/Elev= 30
  4725.1  378.01  4730.4  377.58  4740.4  377.29  4790.4  376.67  4840.4  377.22
  4860.4  376.32  4870.4  375.58  4880.4  374.38  4890.4     374  4900.4   373.2
  4908.4  372.02  4908.7  371.52  4912.2  371.52  4912.4  372.02  4920.4  373.53
  4940.5  372.73  4960.5   372.7  4970.5  373.17  4980.2   373.1  4985.2  372.04
  5001.2  372.13  5020.5  374.12  5034.6  374.86  5060.6  375.87  5080.6  376.14
  5100.6  375.48  5130.7  375.94  5150.7  375.96  5160.5  376.27  5165.5  375.93
#Mann= 4 ,-1 , 0
  4725.1     .05       0  4908.4     .05       0  4912.4     .05       0
  5034.6     .07       0
Bank Sta=4908.4,4912.4
XS Rating Curve= 0 ,0
Exp/Cntr=0.3,0.1

Type RM Length L Ch R = 1 ,2296    ,125,125,125
BEGIN DESCRIPTION:
Twin Creek2362296.02
END DESCRIPTION:
XS GIS Cut Line= 3
      2708989.86      6814571.93      2708997.02      6814386.79
       2709000.7      6814225.91
#Sta/Elev= 30
  4817.6  375.89  4820.6  375.89  4828.5  375.16  4838.5  374.59  4845.3  374.29
  4850.3  374.39  4888.6  372.33  4908.6  371.73  4918.6  371.99  4928.6  371.85
  4948.6  370.99  4958.6  369.95  4972.9  370.01  4988.7  370.01  4998.3  367.82
  5002.9  367.82  5006.7  366.26  5006.9  365.76  5010.4  365.76  5010.7  366.26
  5018.7   369.7  5028.7  369.62  5048.7  368.75  5068.7  370.44  5078.7   369.9
  5098.7  371.63  5108.7  372.32  5118.7  372.64  5158.7   373.4  5163.8  374.31
#Mann= 4 ,-1 , 0
  4817.6     .05       0  4972.9     .07       0  5006.7     .07       0
  5010.7     .07       0
Bank Sta=5006.7,5010.7
XS Rating Curve= 0 ,0
Exp/Cntr=0.3,0.1

Type RM Length L Ch R = 1 ,2171    ,146,146,146
BEGIN DESCRIPTION:
Twin Creek2362171.43
END DESCRIPTION:
XS GIS Cut Line= 3
       2709112.3      6814528.14       2709103.5      6814333.93
      2709102.45      6814186.74
#Sta/Elev= 30
  4805.6  373.86    4831  373.51  4842.8   372.9  4852.8  372.97  4882.8  370.88
  4892.8  370.59  4902.8  369.81  4912.8  369.83  4922.9  369.49  4927.3  369.63
  4932.9  369.81  4942.9  369.36  4972.9  367.45  4982.9  367.61  4992.9  366.94
    5004   366.9  5022.9  366.27  5032.9  363.89  5040.9  363.22  5041.2  362.72
  5044.7  362.72  5044.9  363.22  5052.9  367.73  5062.9  368.34  5072.9  369.59
  5082.9  370.35  5092.9  370.49  5102.9  370.23  5142.6  371.71  5147.2  371.71
#Mann= 4 ,-1 , 0
  4805.6     .05       0  4927.3     .07       0  5040.9     .07       0
  5044.9     .07       0
Bank Sta=5040.9,5044.9
XS Rating Curve= 0 ,0
Exp/Cntr=0.3,0.1

Type RM Length L Ch R = 1 ,2025    ,128,128,128
BEGIN DESCRIPTION:
Twin Creek2362024.66
END DESCRIPTION:
XS GIS Cut Line= 3
      2709219.64      6814488.84      2709221.95      6814258.58
      2709225.92      6814084.89
#Sta/Elev= 30
  4768.7  372.28  4826.5  371.11  4846.5  369.12  4861.3  369.23  4876.5  368.67
  4886.5  367.37  4896.5  367.61  4902.9  367.05  4907.9  367.03  4916.5  366.44
  4936.5  365.94  4946.5  364.74  4956.5  364.13  4966.5  364.15  4976.5  363.62
    4999  363.76  5004.5  361.25  5004.8  360.75  5008.3  360.75  5008.5  361.25
  5016.6  361.75  5026.6   364.9  5046.6  366.23  5056.6  366.39  5076.6  367.18
  5086.6  367.14  5096.6  369.32  5146.6  369.77  5166.6  368.98  5172.7  369.92
#Mann= 4 ,-1 , 0
  4768.7     .05       0  4861.3     .07       0  5004.5     .07       0
  5008.5     .07       0
Bank Sta=5004.5,5008.5
XS Rating Curve= 0 ,0
Exp/Cntr=0.3,0.1

Type RM Length L Ch R = 1 ,1897    ,94,94,94
BEGIN DESCRIPTION:
Mapping XS 0b53d474
END DESCRIPTION:
XS GIS Cut Line= 3
      2709330.43      6814434.93      2709334.06      6814211.61
      2709337.17       6814075.4
#Sta/Elev= 30
  4775.7  370.11  4780.2  370.11  4789.6  369.43  4799.6  369.33  4807.8  368.74
  4816.8  368.61  4859.6   366.4  4869.6  365.68  4879.6  365.49  4899.6  364.16
  4919.7  363.52  4929.7   362.6  4949.7  361.71  4959.7  361.51  4969.7  362.12
  5001.9   361.3  5009.7  360.72  5012.6  359.84  5017.7  358.29  5017.9  357.79
  5021.4  357.79  5021.7  358.29  5029.7  360.22  5039.7   363.3  5059.7  365.03
  5069.7  365.08  5079.7   366.1  5089.7  366.53  5109.7     366  5135.3  366.54
#Mann= 5 ,-1 , 0
  4775.7     .07       0  4816.8     .16       0  5012.6     .07       0
  5017.7     .07       0  5021.7     .07       0
Bank Sta=5017.7,5021.7
XS Rating Curve= 0 ,0
Exp/Cntr=0.3,0.1

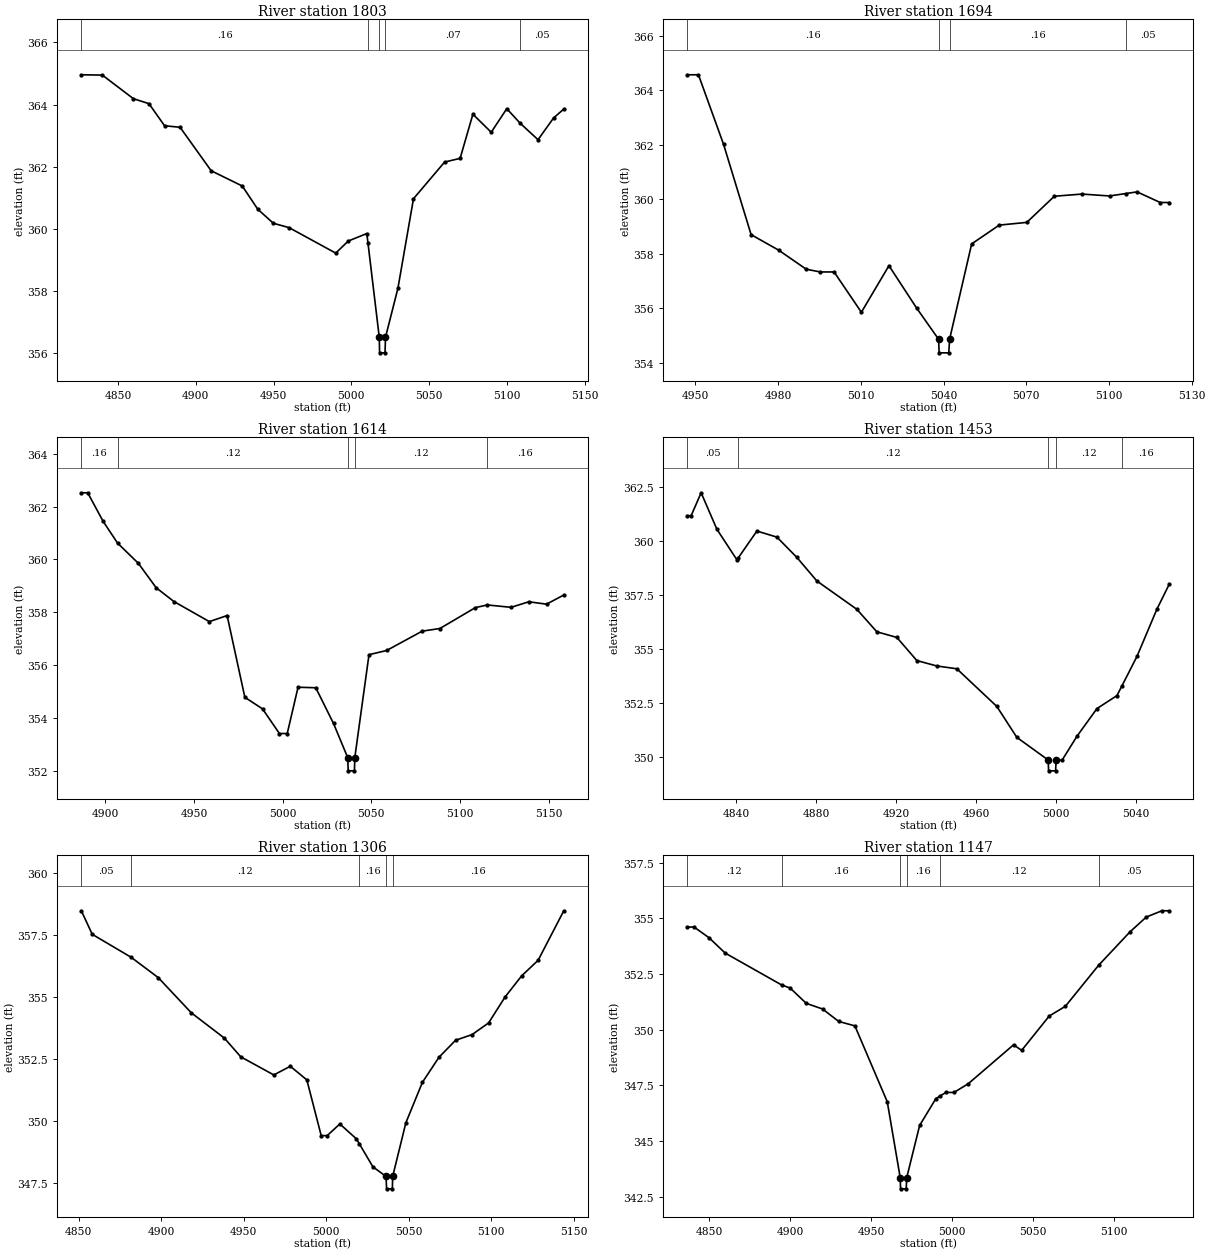
Type RM Length L Ch R = 1 ,1803    ,109,109,109
BEGIN DESCRIPTION:
Twin Creek2361802.86
END DESCRIPTION:
XS GIS Cut Line= 3
      2709421.38      6814384.45      2709428.31      6814209.74
      2709432.85      6814074.56
#Sta/Elev= 30
  4826.4  364.96  4839.9  364.95  4859.9  364.19  4869.9  364.03  4879.9  363.32
  4889.9  363.27  4909.9  361.87  4929.9  361.38  4939.9  360.63  4949.9  360.18
    4960  360.04    4990  359.22  4998.1  359.61    5010  359.85  5010.7  359.56
    5018  356.51  5018.2  356.01  5021.7  356.01    5022  356.51    5030  358.09
    5040  360.97    5060  362.15    5070  362.27  5078.2  363.69    5090  363.11
    5100  363.87  5108.6   363.4  5120.1  362.87  5130.1  363.57  5136.5  363.85
#Mann= 5 ,-1 , 0
  4826.4     .16       0  5010.7     .07       0    5018     .07       0
    5022     .07       0  5108.6     .05       0
Bank Sta=5018,5022
XS Rating Curve= 0 ,0
Exp/Cntr=0.3,0.1

Type RM Length L Ch R = 1 ,1694    ,80,80,80
BEGIN DESCRIPTION:
Twin Creek2361694.2
END DESCRIPTION:
XS GIS Cut Line= 3
      2709537.34      6814264.16      2709536.97      6814215.68
      2709535.45      6814089.27
#Sta/Elev= 25
    4947  364.57  4951.1  364.57  4960.2  362.02  4970.2   358.7  4980.2  358.13
  4990.2  357.43  4995.3  357.33  5000.3  357.33  5010.2  355.85  5020.2  357.56
  5030.2  356.01  5038.2  354.86  5038.4  354.36  5041.9  354.36  5042.2  354.86
  5050.2  358.36  5060.2  359.05  5070.2  359.15  5080.2  360.11  5090.2  360.19
  5100.2  360.12  5106.2  360.21  5110.2  360.27  5118.6  359.88  5121.9  359.88
#Mann= 4 ,-1 , 0
    4947     .16       0  5038.2     .07       0  5042.2     .16       0
  5106.2     .05       0
Bank Sta=5038.2,5042.2
XS Rating Curve= 0 ,0
Exp/Cntr=0.3,0.1

Type RM Length L Ch R = 1 ,1614    ,161,161,161
BEGIN DESCRIPTION:
Twin Creek2361614.39
END DESCRIPTION:
XS GIS Cut Line= 3
      2709619.79      6814323.17      2709616.56      6814207.11
      2709620.12      6814051.36
#Sta/Elev= 30
  4886.5  362.52  4890.1  362.52  4898.7  361.45  4906.9  360.62  4918.7  359.85
  4928.7  358.93  4938.7  358.41  4958.7  357.65  4968.7  357.88  4978.7  354.79
  4988.7  354.35  4998.2  353.42  5002.6  353.42  5008.7  355.17  5018.7  355.15
  5028.7   353.8  5036.7  352.51    5037  352.01  5040.5  352.01  5040.7  352.51
  5048.7   356.4  5058.7  356.56  5078.7  357.29  5088.7  357.39  5108.7  358.18
  5115.4  358.28  5128.8  358.19  5138.8   358.4  5148.8  358.31  5158.4  358.65
#Mann= 5 ,-1 , 0
  4886.5     .16       0  4906.9     .12       0  5036.7     .07       0
  5040.7     .12       0  5115.4     .16       0
Bank Sta=5036.7,5040.7
XS Rating Curve= 0 ,0
Exp/Cntr=0.3,0.1

Type RM Length L Ch R = 1 ,1453    ,147,147,147
BEGIN DESCRIPTION:
Twin Creek2361452.5
END DESCRIPTION:
XS GIS Cut Line= 3
      2709730.91       6814285.9      2709735.14      6814100.72
      2709736.42      6814044.77
#Sta/Elev= 30
  4815.4  361.15  4817.4  361.15  4822.4  362.21  4830.3  360.52  4840.3  359.11
  4840.9  359.19  4850.3  360.44  4860.3  360.16  4870.3  359.22  4880.3  358.13
  4900.3  356.82  4910.3  355.78  4920.3  355.52  4930.3  354.45  4940.3   354.2
  4950.3  354.07  4970.3  352.33  4980.3   350.9    4996  349.85  4996.2  349.35
  4999.7  349.35    5000  349.85    5003  349.85  5010.4  350.95  5020.4  352.23
  5030.4  352.83  5032.9  353.28  5040.4  354.64  5050.4  356.83  5056.6  357.99
#Mann= 5 ,-1 , 0
  4815.4     .05       0  4840.9     .12       0    4996     .07       0
    5000     .12       0  5032.9     .16       0
Bank Sta=4996,5000
XS Rating Curve= 0 ,0
Exp/Cntr=0.3,0.1

Type RM Length L Ch R = 1 ,1306    ,159,159,159
BEGIN DESCRIPTION:
Twin Creek2361306.16
END DESCRIPTION:
XS GIS Cut Line= 3
      2709863.55      6814207.59      2709866.95      6814058.71
      2709870.22      6813915.57
#Sta/Elev= 30
  4851.7  358.49  4858.3  357.54  4881.9  356.61  4898.3  355.79  4918.3  354.37
  4938.3  353.35  4948.3  352.59  4968.3  351.86  4978.3  352.21  4988.3  351.66
    4997  349.41  5000.6  349.41  5008.3  349.88  5018.3  349.28  5020.1  349.08
  5028.3  348.15  5036.3  347.76  5036.6  347.26  5040.1  347.26  5040.3  347.76
  5048.3  349.93  5058.3  351.56  5068.3  352.57  5078.4  353.26  5088.4  353.49
  5098.4  353.96  5108.4  355.01  5118.4  355.86  5128.4  356.49  5143.8  358.47
#Mann= 5 ,-1 , 0
  4851.7     .05       0  4881.9     .12       0  5020.1     .16       0
  5036.3     .07       0  5040.3     .16       0
Bank Sta=5036.3,5040.3
XS Rating Curve= 0 ,0
Exp/Cntr=0.3,0.1

Type RM Length L Ch R = 1 ,1147    ,137,137,137
BEGIN DESCRIPTION:
Twin Creek2361147.08
END DESCRIPTION:
XS GIS Cut Line= 3
      2710006.33      6814174.54      2710010.01       6814013.6
      2710013.13      6813876.82
#Sta/Elev= 30
  4836.3  354.61  4840.6  354.61  4849.8  354.13  4859.8  353.44  4894.6  352.01
  4899.9  351.87  4909.9  351.18  4919.9  350.93  4929.9  350.37  4939.9  350.17
  4959.9  346.76  4967.9  343.35  4968.1  342.85  4971.6  342.85  4971.9  343.35
  4979.9   345.7  4989.9   346.9  4992.5  347.02  4996.1  347.18  5001.1  347.18
  5009.9  347.57  5037.9  349.32  5042.9  349.07  5059.9  350.61  5069.9  351.05
  5090.4  352.89  5109.9   354.4  5119.9  355.06  5129.5  355.34  5134.1  355.34
#Mann= 6 ,-1 , 0
  4836.3     .12       0  4894.6     .16       0  4967.9     .07       0
  4971.9     .16       0  4992.5     .12       0  5090.4     .05       0
Bank Sta=4967.9,4971.9
XS Rating Curve= 0 ,0
Exp/Cntr=0.3,0.1

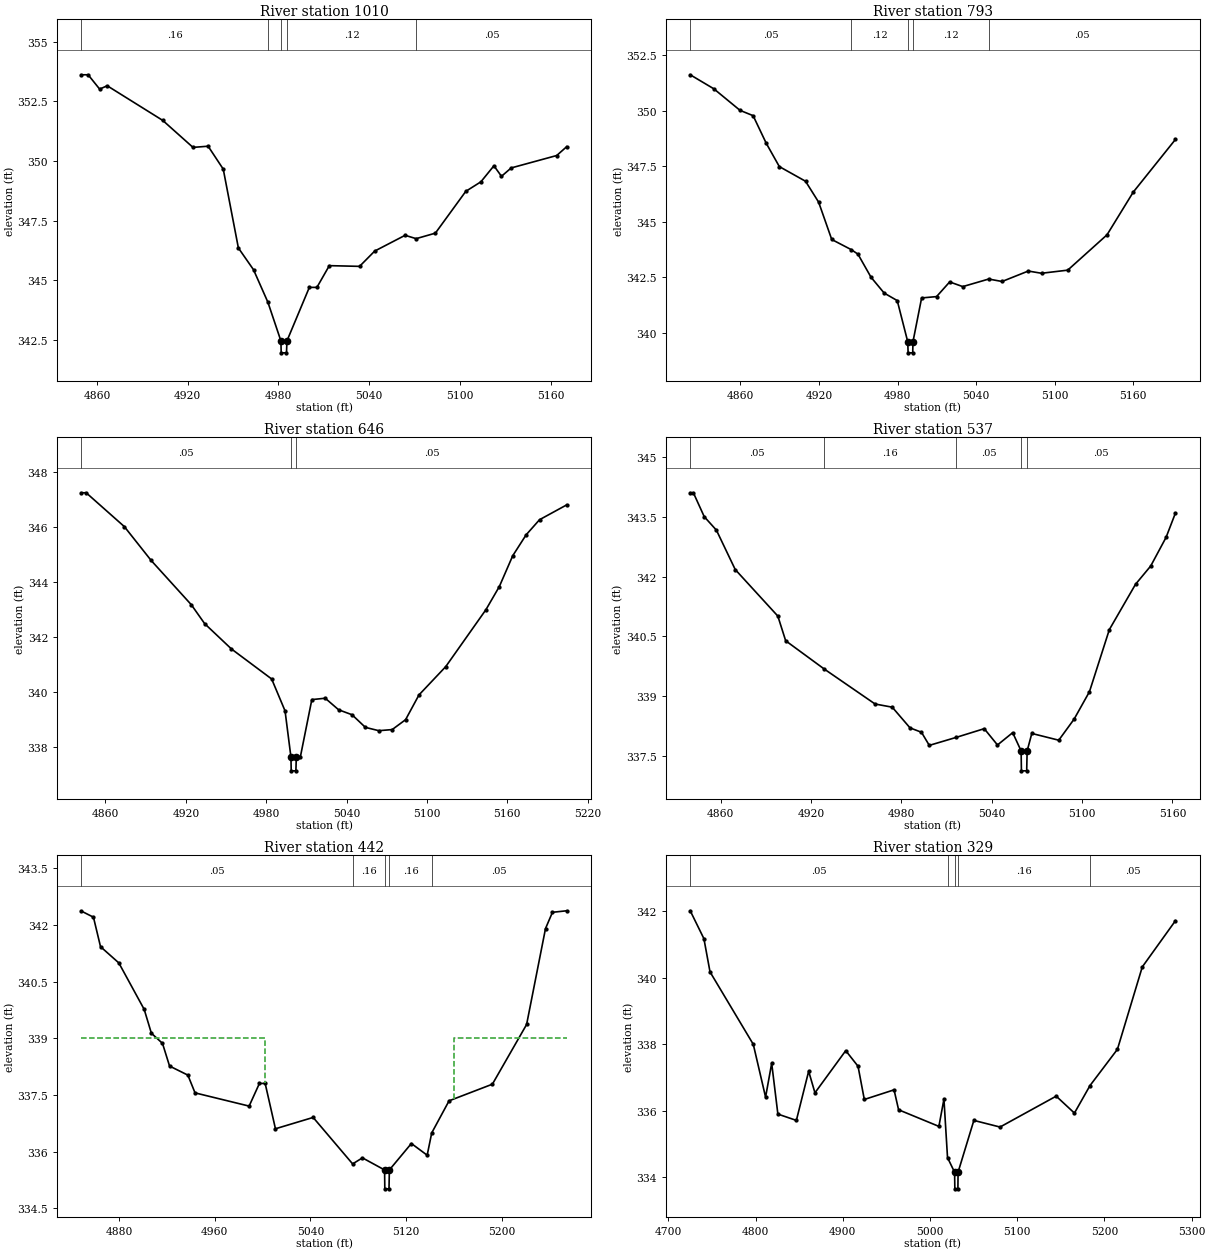
Type RM Length L Ch R = 1 ,1010    ,217,217,217
BEGIN DESCRIPTION:
Twin Creek2361009.72
END DESCRIPTION:
XS GIS Cut Line= 3
       2710140.8      6814144.74      2710142.81      6813992.39
      2710153.94      6813824.42
#Sta/Elev= 30
  4849.8  353.61  4854.2  353.61  4861.8  353.01  4866.8  353.15  4903.5   351.7
  4923.5  350.57  4933.5  350.62  4943.5  349.66  4953.5  346.36  4963.5  345.45
    4973  344.09  4981.6  342.47  4981.8  341.97  4985.3  341.97  4985.6  342.47
  5000.4  344.71  5005.4  344.71  5013.6  345.62  5033.6  345.59  5043.6  346.23
  5063.7  346.89    5071  346.75  5083.7  346.98  5103.8  348.73  5113.8  349.13
  5122.4   349.8  5127.4  349.36  5133.8  349.71  5163.9  350.23  5170.5   350.6
#Mann= 5 ,-1 , 0
  4849.8     .16       0    4973     .12       0  4981.6     .07       0
  4985.6     .12       0    5071     .05       0
Bank Sta=4981.6,4985.6
XS Rating Curve= 0 ,0
Exp/Cntr=0.3,0.1

Type RM Length L Ch R = 1 ,793     ,147,147,147
BEGIN DESCRIPTION:
Twin Creek236793.05
END DESCRIPTION:
XS GIS Cut Line= 3
       2710307.2      6814039.02      2710306.17      6813858.86
      2710300.99      6813668.79
#Sta/Elev= 30
  4821.8  351.62  4839.8  350.99  4859.8  350.02  4869.8  349.78  4879.8  348.54
  4889.8  347.49  4909.8  346.83  4919.8  345.89  4929.8  344.21  4944.8  343.75
  4949.8  343.55  4959.8  342.51  4969.8   341.8  4979.8  341.46  4987.8  339.61
  4988.1  339.11  4991.6  339.11  4991.8  339.61  4998.4  341.58  5009.8  341.64
  5019.8   342.3  5029.8  342.09  5049.6  342.43  5059.8  342.32  5079.8  342.79
  5089.9  342.69  5109.9  342.83  5139.9  344.42  5159.9  346.34  5192.1  348.71
#Mann= 5 ,-1 , 0
  4821.8     .05       0  4944.8     .12       0  4987.8     .07       0
  4991.8     .12       0  5049.6     .05       0
Bank Sta=4987.8,4991.8
XS Rating Curve= 0 ,0
Exp/Cntr=0.3,0.1

Type RM Length L Ch R = 1 ,646     ,109,109,109
BEGIN DESCRIPTION:
Twin Creek236646.48
END DESCRIPTION:
XS GIS Cut Line= 3
      2710431.35      6813963.01       2710431.7       6813803.3
      2710434.13      6813600.72
#Sta/Elev= 30
  4842.1  347.23  4845.6  347.23  4874.1     346  4894.1  344.77  4924.1  343.16
  4934.1  342.47  4954.1  341.55  4984.1  340.46  4994.1   339.3  4998.5  337.62
  4998.7  337.12  5002.2  337.12  5002.5  337.62  5005.5  337.62  5014.1  339.71
  5024.1  339.76  5034.1  339.34  5044.1  339.16  5054.1   338.7  5064.1  338.58
  5074.1  338.62  5084.1  338.98  5094.1  339.88  5114.1  340.91  5144.1  342.98
  5154.1  343.82  5164.1  344.94  5174.1   345.7  5184.1  346.25  5204.4  346.79
#Mann= 3 ,-1 , 0
  4842.1     .05       0  4998.5     .05       0  5002.5     .05       0
Bank Sta=4998.5,5002.5
XS Rating Curve= 0 ,0
Exp/Cntr=0.3,0.1

Type RM Length L Ch R = 1 ,537     ,95,95,95
BEGIN DESCRIPTION:
Mapping XS 32761209
END DESCRIPTION:
XS GIS Cut Line= 5
      2710485.93      6813919.99      2710518.21      6813793.97
      2710524.15       6813765.7      2710527.25      6813733.22
       2710502.2      6813604.94
#Sta/Elev= 30
  4839.7  344.11  4841.8  344.11    4849  343.51  4857.1  343.17  4869.6  342.18
  4897.9  341.01  4903.1  340.39  4928.7  339.68  4962.5   338.8  4973.9  338.72
  4985.7   338.2  4993.3  338.09  4998.5  337.76  5016.3  337.96    5035  338.18
  5043.8  337.77  5053.9  338.08  5059.5  337.62  5059.7  337.12  5063.2  337.12
  5063.5  337.62  5066.6  338.06  5084.5  337.89  5094.7  338.42  5104.9  339.11
  5118.1  340.67  5135.5  341.81  5145.6  342.27  5155.8  342.99    5162   343.6
#Mann= 5 ,-1 , 0
  4839.7     .05       0  4928.7     .16       0  5016.3     .05       0
  5059.5     .07       0  5063.5     .05       0
Bank Sta=5059.5,5063.5
XS Rating Curve= 0 ,0
Exp/Cntr=0.3,0.1

Type RM Length L Ch R = 1 ,442     ,113,113,113
BEGIN DESCRIPTION:
Mapping XS 9320b5a4
END DESCRIPTION:
XS GIS Cut Line= 5
      2710522.53      6813939.54      2710602.48      6813812.52
      2710619.61       6813757.5      2710603.15      6813680.23
      2710544.33      6813577.03
#Sta/Elev= 30
  4848.7  342.37  4858.7  342.21  4864.6  341.43  4879.9     341  4901.1  339.77
  4907.1  339.14  4916.4  338.87  4922.3  338.27  4937.6  338.03  4943.6  337.56
  4988.8  337.21  4997.4  337.81  5002.2  337.81  5010.8  336.61  5042.3  336.91
  5075.3  335.68  5083.5  335.84    5102  335.52  5102.2  335.02  5105.7  335.02
    5106  335.52  5124.4  336.22  5137.6  335.91  5141.4   336.5  5155.9  337.35
  5192.1  337.79  5220.7  339.37  5236.5  341.91  5242.3  342.34  5254.2  342.38
#Mann= 5 ,-1 , 0
  4848.7     .05       0  5075.3     .16       0    5102     .05       0
    5106     .16       0  5141.4     .05       0
#XS Ineff= 2 , 0
       0    5002     339    5160       0     339
Permanent Ineff=
       F       F
Bank Sta=5102,5106
XS Rating Curve= 0 ,0
Exp/Cntr=0.3,0.1

Type RM Length L Ch R = 1 ,329     ,262,262,262
BEGIN DESCRIPTION:
Twin Creek236329.01
END DESCRIPTION:
XS GIS Cut Line= 5
      2710537.35      6813974.45      2710683.16      6813825.21
      2710700.23      6813761.74      2710704.05      6813675.24
      2710574.12      6813529.37
#Sta/Elev= 30
  4725.1  342.02  4740.8  341.18  4747.8  340.18  4797.4     338  4811.5  336.41
  4818.5  337.43  4825.6   335.9  4846.8  335.71  4860.9  337.19  4868.1  336.54
  4903.4  337.81  4917.5  337.34  4924.7  336.34  4958.8  336.63    4964  336.03
  5010.2  335.53    5016  336.35  5020.1  334.59  5028.2  334.15  5028.5  333.65
    5032  333.65  5032.2  334.15  5050.3  335.71  5080.3  335.51  5144.7  336.44
  5165.6  335.93  5183.5  336.76  5214.9  337.85  5243.4  340.33  5281.4  341.72
#Mann= 5 ,-1 , 0
  4725.1     .05       0  5020.1     .16       0  5028.2     .05       0
  5032.2     .16       0  5183.5     .05       0
Bank Sta=5028.2,5032.2
XS Rating Curve= 0 ,0
Exp/Cntr=0.3,0.1

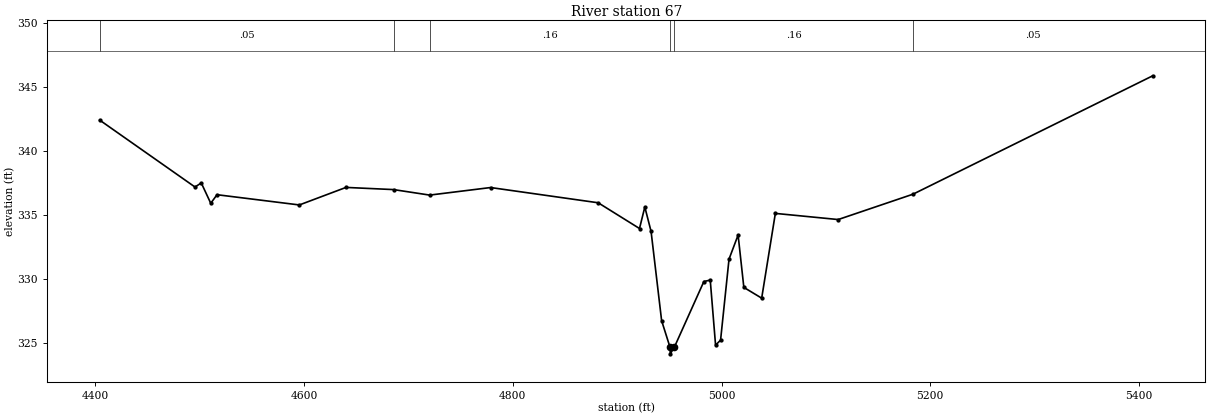
Type RM Length L Ch R = 1 ,67      ,0,0,0
BEGIN DESCRIPTION:
Twin Creek23666.958
END DESCRIPTION:
XS GIS Cut Line= 5
      2710526.04      6814017.17      2710784.82      6813847.11
      2710838.04      6813730.77      2710862.49      6813574.26
      2710490.31      6813394.55
#Sta/Elev= 30
    4404  342.39  4495.4  337.16  4501.4  337.48  4510.5  335.89  4516.5  336.56
  4595.4  335.76  4640.1  337.13  4685.7  336.96  4720.3  336.53  4778.7  337.12
  4881.8  335.93  4921.4  333.92  4926.5   335.6  4932.5  333.69  4942.6  326.72
  4950.7  324.63  4950.9  324.13  4954.7  324.63  4983.1  329.78  4989.2  329.89
  4994.3  324.81  4999.1   325.2  5007.2  331.53  5015.9  333.41  5021.4  329.32
  5038.5  328.48  5051.6   335.1  5111.8  334.62  5183.5   336.6  5413.3  345.85
#Mann= 6 ,-1 , 0
    4404     .05       0  4685.7     .12       0  4720.3     .16       0
  4950.7     .07       0  4954.7     .16       0  5183.5     .05       0
Bank Sta=4950.7,4954.7
XS Rating Curve= 0 ,0
Exp/Cntr=0.3,0.1

Chan Stop Cuts=-1
Use User Specified Reach Order=0
Composite Channel Slope=5