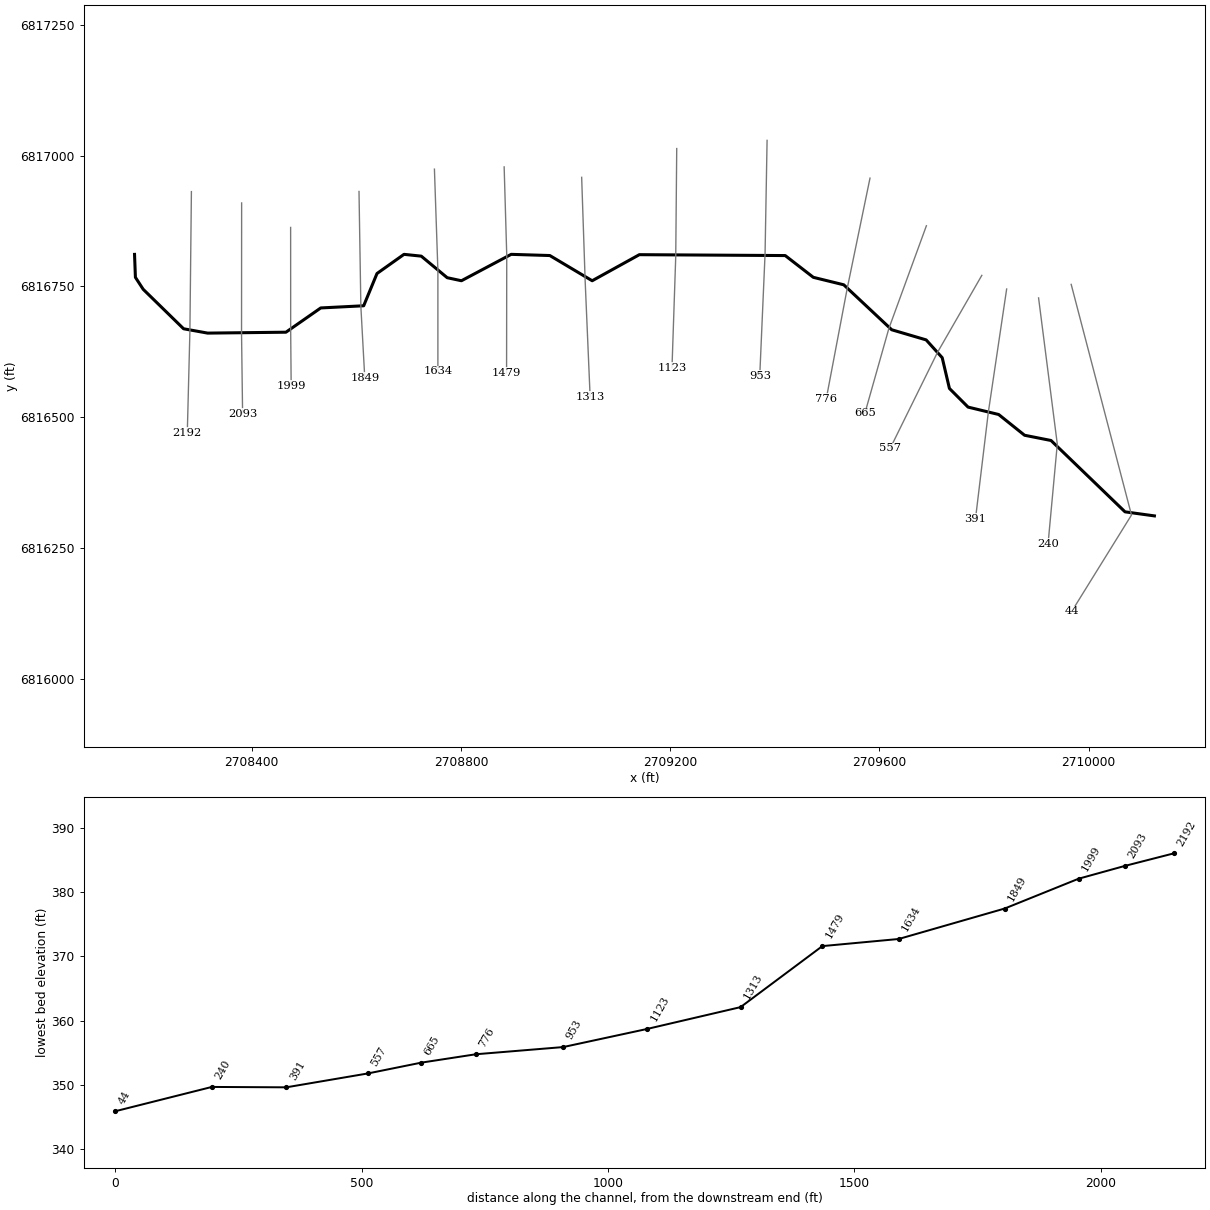
--- Twin Creek240.prj (project) ---

Proj Title=Twin Creek240 Base Level Engineering
Current Plan=p01
Default Exp/Contr=0.3,0.1
English Units
Geom File=g01
Flow File=f01
Plan File=p01
BEGIN DESCRIPTION:
Twin Creek240
END DESCRIPTION:

--- Twin Creek240.p01 (plan) ---

Plan Title=Multiple Run
Short Identifier=Multiple
Geom File=g01
Flow File=f01
Subcritical Flow
K Sum by GR= 0
Std Step Tol= 0.01
Critical Tol= 0.01
Num of Std Step Trials= 20
Max Error Tol= 0.3
Flow Tol Ratio= 0.001
Split Flow NTrial= 30
Split Flow Tol= 0.02
Split Flow Ratio= 0.02
Log Output Level= 0
Friction Slope Method= 1
Unsteady Friction Slope Method= 2
Unsteady Bridges Friction Slope Method= 1
Parabolic Critical Depth
Global Vel Dist=  1 , 1 , 1
Global Log Level= 0
CheckData=True
Encroach Param= -1, 0, 0, 0
BEGIN DESCRIPTION:
Multiple Run
END DESCRIPTION:

--- Twin Creek240.f01 (steady flow) ---

Flow Title=Multiple
Number of Profiles=7
Profile Names=10-year,25-year,50-year,1pct_min,100-year,1pct_plu,500-year
River Rch & RM= Twin Creek240,Reach-1,2192
     173     215     247     141     282     563     366
Boundary for River Rch & Prof#=Twin Creek240,Reach-1,1
Up Type=0
Dn Type=3
Dn Slope=0.005
Boundary for River Rch & Prof#=Twin Creek240,Reach-1,2
Up Type=0
Dn Type=3
Dn Slope=0.005
Boundary for River Rch & Prof#=Twin Creek240,Reach-1,3
Up Type=0
Dn Type=3
Dn Slope=0.005
Boundary for River Rch & Prof#=Twin Creek240,Reach-1,4
Up Type=0
Dn Type=3
Dn Slope=0.005
Boundary for River Rch & Prof#=Twin Creek240,Reach-1,5
Up Type=0
Dn Type=3
Dn Slope=0.005
Boundary for River Rch & Prof#=Twin Creek240,Reach-1,6
Up Type=0
Dn Type=3
Dn Slope=0.005
Boundary for River Rch & Prof#=Twin Creek240,Reach-1,7
Up Type=0
Dn Type=3
Dn Slope=0.005

--- Twin Creek240.g01 (geometry) ---

Geom Title=Existing Conditions

River Reach=Twin Creek240,Reach-1
Reach XY= 30
      2708176.00      6816811.00      2708177.67      6816767.13
      2708192.56      6816744.25      2708269.79      6816668.79
      2708315.79      6816660.49      2708465.50      6816662.22
      2708532.06      6816708.61      2708614.12      6816712.76
      2708639.59      6816774.45      2708691.22      6816811.08
      2708724.24      6816807.64      2708773.80      6816766.42
      2708801.00      6816760.61      2708896.10      6816811.08
      2708970.03      6816808.81      2709051.00      6816760.60
      2709141.21      6816810.46      2709420.07      6816808.76
      2709473.83      6816767.14      2709532.05      6816752.84
      2709623.74      6816666.88      2709689.56      6816647.51
      2709720.24      6816613.51      2709734.05      6816554.69
      2709769.66      6816519.03      2709828.16      6816504.89
      2709877.73      6816465.19      2709928.30      6816455.17
      2710069.79      6816318.76      2710126.00      6816311.00

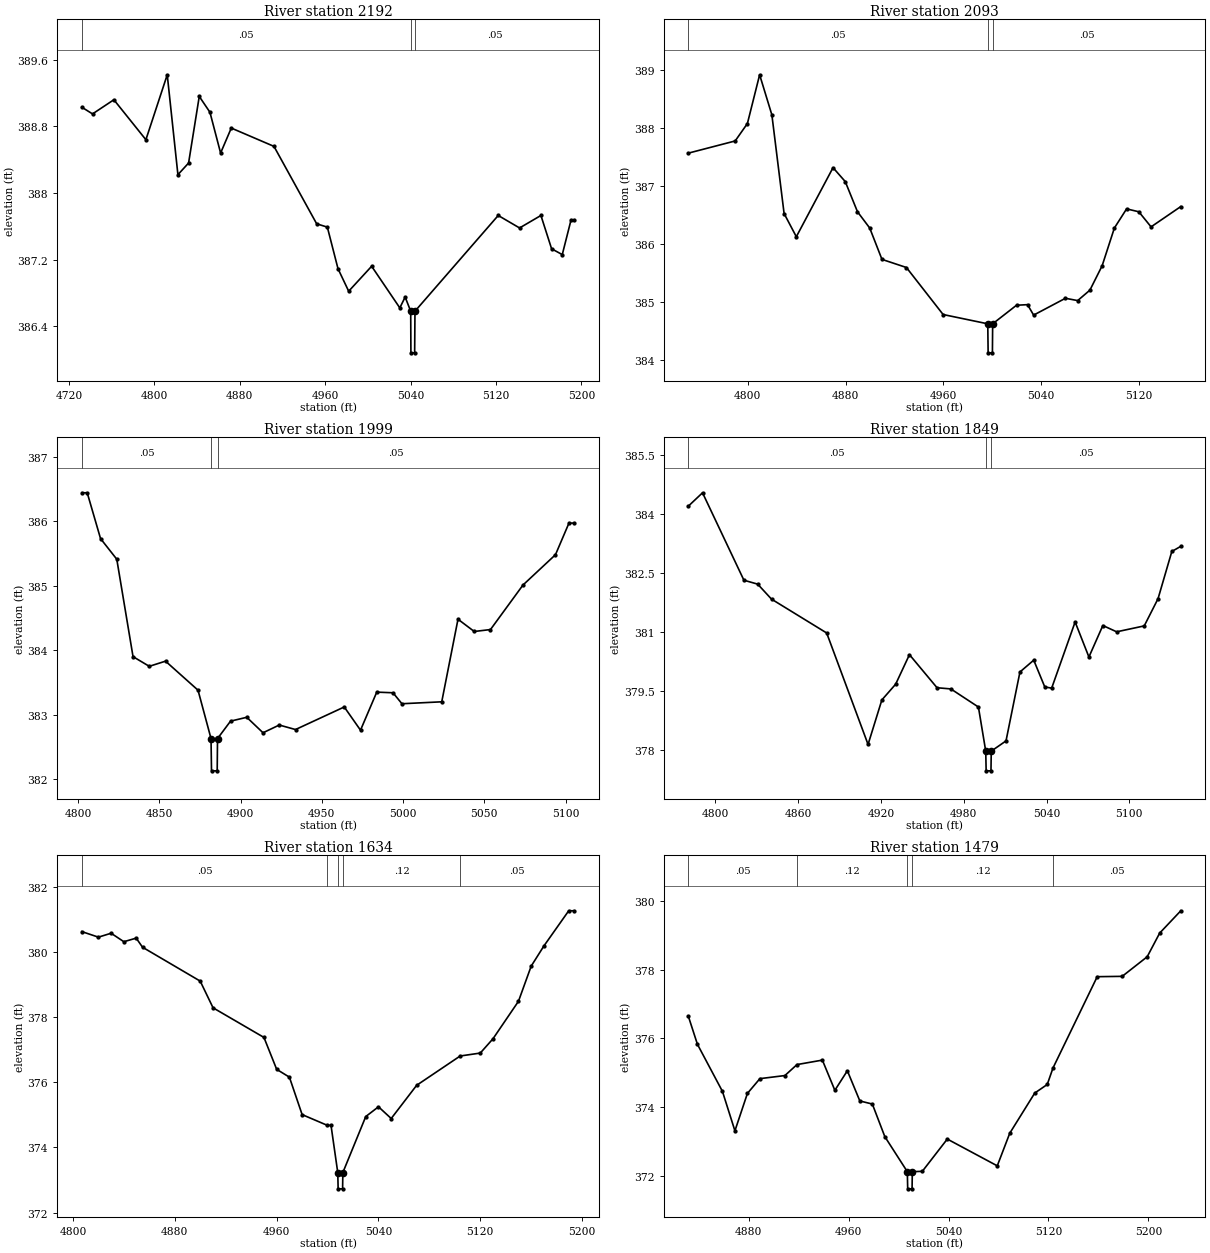
Type RM Length L Ch R = 1,2192,99,99,99
BEGIN DESCRIPTION:
Twin Creek2402192.195
END DESCRIPTION:
XS GIS Cut Line= 3
      2708284.73      6816931.03      2708281.84      6816663.05
      2708276.87      6816469.71
#Sta/Elev= 30
  4732.0  389.03  4742.0  388.95  4762.0  389.12  4792.0  388.64  4812.0  389.42
  4822.0  388.22  4832.0  388.36  4842.0  389.16  4852.0  388.97  4862.0  388.48
  4872.0  388.78  4912.0  388.56  4952.0  387.63  4962.0  387.59  4972.0  387.09
  4982.0  386.82  5003.5  387.12  5029.9  386.62  5034.9  386.75  5040.1  386.58
  5040.3  386.08  5043.8  386.08  5044.1  386.58  5122.1  387.73  5142.1  387.58
  5162.1  387.73  5172.1  387.33  5182.1  387.26  5190.2  387.67  5193.4  387.67
#Mann=3,-1,0
  4732.0    0.05       0  5040.1    0.05       0  5044.1    0.05       0
Bank Sta=5040.1,5044.1
Exp/Cntr=0.3,0.1

Type RM Length L Ch R = 1,2093,94,94,94
BEGIN DESCRIPTION:
Twin Creek2402093.19
END DESCRIPTION:
XS GIS Cut Line= 3
      2708380.77      6816909.33      2708380.59      6816659.03
      2708382.61      6816506.75
#Sta/Elev= 30
  4751.5  387.57  4789.8  387.78  4799.8  388.08  4809.8  388.92  4819.8  388.23
  4829.8  386.53  4839.8  386.13  4869.8  387.32  4879.8  387.08  4889.8  386.56
  4899.8  386.28  4909.8  385.74  4929.8  385.60  4959.8  384.79  4996.3  384.63
  4996.6  384.13  5000.1  384.13  5000.3  384.63  5019.8  384.95  5028.8  384.96
  5033.8  384.78  5059.8  385.07  5069.8  385.03  5079.8  385.21  5089.8  385.63
  5099.8  386.28  5109.8  386.61  5119.8  386.56  5129.8  386.30  5154.1  386.65
#Mann=3,-1,0
  4751.5    0.05       0  4996.3    0.05       0  5000.3    0.05       0
Bank Sta=4996.3,5000.3
Exp/Cntr=0.3,0.1

Type RM Length L Ch R = 1,1999,150,150,150
BEGIN DESCRIPTION:
Twin Creek2401998.84
END DESCRIPTION:
XS GIS Cut Line= 3
      2708474.44      6816862.53      2708474.54      6816665.07
      2708475.48      6816559.43
#Sta/Elev= 30
  4802.3  386.44  4805.6  386.44  4813.8  385.73  4823.8  385.41  4833.8  383.90
  4843.8  383.75  4853.8  383.83  4873.8  383.38  4881.8  382.63  4882.1  382.13
  4885.6  382.13  4885.8  382.63  4893.8  382.90  4903.8  382.96  4913.8  382.72
  4923.8  382.84  4933.8  382.77  4963.8  383.12  4973.8  382.76  4983.8  383.35
  4993.8  383.34  4999.3  383.17  5023.8  383.20  5033.8  384.48  5043.8  384.29
  5053.8  384.32  5073.8  385.01  5093.8  385.48  5102.1  385.97  5105.4  385.97
#Mann=3,-1,0
  4802.3    0.05       0  4881.8    0.05       0  4885.8    0.05       0
Bank Sta=4881.8,4885.8
Exp/Cntr=0.3,0.1

Type RM Length L Ch R = 1,1849,215,215,215
BEGIN DESCRIPTION:
Twin Creek2401849.05
END DESCRIPTION:
XS GIS Cut Line= 3
      2708605.18      6816931.30      2708608.73      6816711.43
      2708616.22      6816574.54
#Sta/Elev= 30
  4780.3  384.20  4790.6  384.54  4820.6  382.32  4830.6  382.22  4840.6  381.84
  4880.6  380.98  4910.6  378.15  4920.6  379.28  4930.6  379.68  4940.6  380.43
  4960.6  379.59  4970.6  379.56  4990.6  379.10  4995.9  377.98  4996.2  377.48
  4999.7  377.48  4999.9  377.98  5010.6  378.24  5020.7  379.99  5030.7  380.29
  5038.7  379.61  5043.7  379.58  5060.7  381.26  5070.7  380.37  5080.8  381.17
  5090.8  381.01  5110.8  381.16  5120.8  381.85  5130.8  383.05  5137.3  383.18
#Mann=3,-1,0
  4780.3    0.05       0  4995.9    0.05       0  4999.9    0.05       0
Bank Sta=4995.9,4999.9
Exp/Cntr=0.3,0.1

Type RM Length L Ch R = 1,1634,155,155,155
BEGIN DESCRIPTION:
Twin Creek2401633.57
END DESCRIPTION:
XS GIS Cut Line= 3
      2708749.38      6816974.00      2708756.00      6816780.59
      2708756.01      6816587.11
#Sta/Elev= 30
  4807.0  380.63  4820.0  380.46  4830.0  380.58  4840.0  380.32  4849.7  380.43
  4854.7  380.15  4900.0  379.11  4910.1  378.29  4950.1  377.38  4960.1  376.40
  4970.1  376.16  4980.1  375.01  4999.9  374.68  5002.8  374.68  5008.1  373.23
  5008.4  372.73  5011.9  372.73  5012.1  373.23  5030.1  374.95  5040.1  375.25
  5050.1  374.89  5070.1  375.91  5104.3  376.81  5120.1  376.90  5130.1  377.34
  5150.1  378.49  5160.1  379.57  5170.1  380.19  5189.6  381.27  5194.0  381.27
#Mann=5,-1,0
  4807.0    0.05       0  4999.9    0.12       0  5008.1    0.07       0
  5012.1    0.12       0  5104.3    0.05       0
Bank Sta=5008.1,5012.1
Exp/Cntr=0.3,0.1

Type RM Length L Ch R = 1,1479,166,166,166
BEGIN DESCRIPTION:
Twin Creek2401479.35
END DESCRIPTION:
XS GIS Cut Line= 3
      2708882.69      6816978.27      2708887.65      6816809.58
      2708887.33      6816584.14
#Sta/Elev= 30
  4831.7  376.65  4839.0  375.83  4859.0  374.46  4869.0  373.31  4879.0  374.40
  4889.0  374.83  4909.0  374.92  4918.7  375.24  4939.0  375.37  4949.0  374.49
  4959.0  375.06  4969.0  374.18  4979.0  374.09  4989.0  373.14  5007.0  372.12
  5007.3  371.62  5010.8  371.62  5011.0  372.12  5019.0  372.13  5039.0  373.07
  5079.0  372.29  5089.0  373.24  5109.0  374.41  5119.0  374.66  5123.6  375.14
  5159.0  377.80  5179.0  377.81  5199.0  378.38  5209.0  379.07  5225.9  379.72
#Mann=5,-1,0
  4831.7    0.05       0  4918.7    0.12       0  5007.0    0.07       0
  5011.0    0.12       0  5123.6    0.05       0
Bank Sta=5007,5011
Exp/Cntr=0.3,0.1

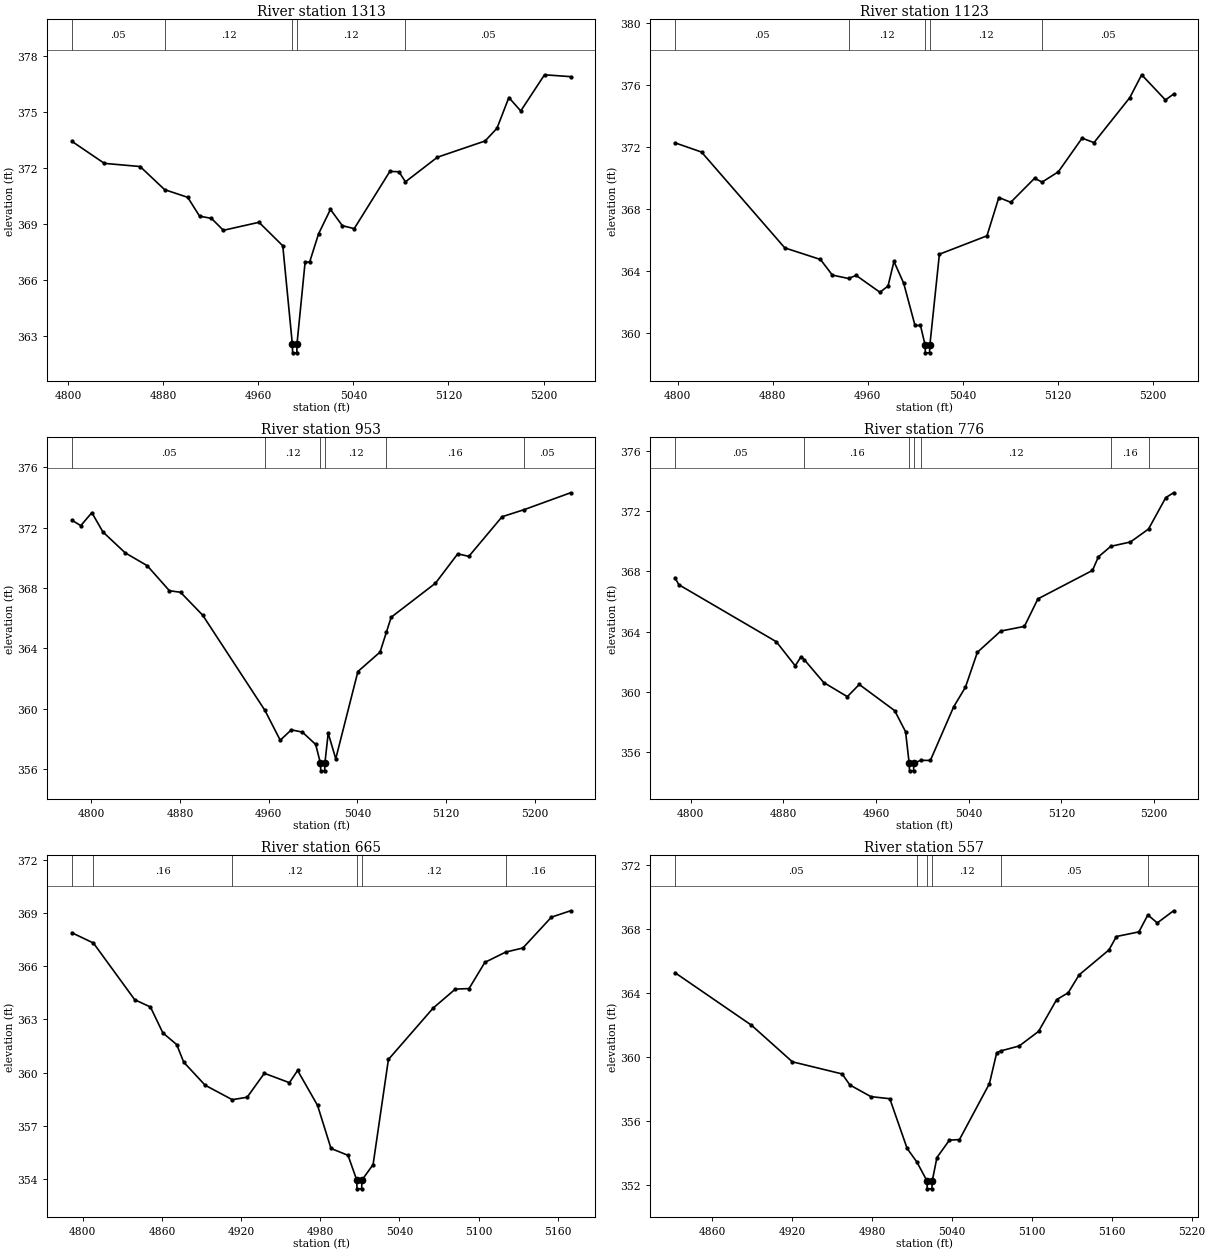
Type RM Length L Ch R = 1,1313,190,190,190
BEGIN DESCRIPTION:
Twin Creek2401313.01
END DESCRIPTION:
XS GIS Cut Line= 3
      2709030.89      6816958.33      2709037.66      6816758.45
      2709047.08      6816539.15
#Sta/Elev= 30
  4803.2  373.44  4830.5  372.26  4860.6  372.09  4881.2  370.85  4900.6  370.44
  4910.6  369.43  4920.6  369.31  4930.6  368.67  4960.6  369.10  4980.6  367.84
  4988.6  362.60  4988.9  362.10  4992.4  362.10  4992.6  362.60  4999.4  366.97
  5003.2  366.97  5010.7  368.48  5020.7  369.79  5030.7  368.92  5040.7  368.76
  5070.7  371.83  5078.3  371.81  5083.8  371.27  5110.7  372.59  5150.8  373.46
  5160.8  374.14  5170.8  375.79  5180.8  375.07  5200.8  377.01  5222.7  376.91
#Mann=5,-1,0
  4803.2    0.05       0  4881.2    0.12       0  4988.6    0.07       0
  4992.6    0.12       0  5083.8    0.05       0
Bank Sta=4988.6,4992.6
Exp/Cntr=0.3,0.1

Type RM Length L Ch R = 1,1123,170,170,170
BEGIN DESCRIPTION:
Twin Creek2401123.36
END DESCRIPTION:
XS GIS Cut Line= 3
      2709212.66      6817013.35      2709210.77      6816806.82
      2709203.60      6816594.18
#Sta/Elev= 30
  4797.8  372.28  4820.2  371.68  4890.2  365.48  4920.2  364.73  4930.2  363.72
  4943.8  363.50  4950.2  363.70  4970.2  362.61  4977.0  363.01  4982.0  364.60
  4990.2  363.19  4999.7  360.46  5004.3  360.46  5008.2  359.19  5008.4  358.69
  5011.9  358.69  5012.2  359.19  5020.2  365.07  5060.2  366.26  5070.2  368.74
  5080.2  368.43  5100.2  369.98  5106.6  369.74  5120.2  370.40  5140.2  372.58
  5150.2  372.29  5180.3  375.20  5190.3  376.68  5210.3  375.05  5217.1  375.43
#Mann=5,-1,0
  4797.8    0.05       0  4943.8    0.12       0  5008.2    0.07       0
  5012.2    0.12       0  5106.6    0.05       0
Bank Sta=5008.2,5012.2
Exp/Cntr=0.3,0.1

Type RM Length L Ch R = 1,953,177,177,177
BEGIN DESCRIPTION:
Twin Creek240952.65
END DESCRIPTION:
XS GIS Cut Line= 3
      2709385.41      6817029.01      2709381.55      6816812.02
      2709371.42      6816579.26
#Sta/Elev= 30
  4782.4  372.50  4790.4  372.14  4800.4  373.00  4810.4  371.72  4830.4  370.34
  4850.4  369.48  4870.4  367.82  4880.4  367.72  4900.4  366.20  4956.6  359.88
  4970.4  357.90  4980.4  358.59  4990.4  358.44  5002.4  357.62  5006.7  356.37
  5007.0  355.87  5010.5  355.87  5010.7  356.37  5013.7  358.37  5020.5  356.67
  5040.5  362.46  5060.5  363.75  5066.3  365.09  5070.5  366.06  5110.5  368.32
  5130.6  370.27  5140.6  370.10  5170.6  372.73  5190.5  373.20  5232.4  374.32
#Mann=6,-1,0
  4782.4    0.05       0  4956.6    0.12       0  5006.7    0.07       0
  5010.7    0.12       0  5066.3    0.16       0  5190.5    0.05       0
Bank Sta=5006.7,5010.7
Exp/Cntr=0.3,0.1

Type RM Length L Ch R = 1,776,111,111,111
BEGIN DESCRIPTION:
Twin Creek240776.05
END DESCRIPTION:
XS GIS Cut Line= 3
      2709582.20      6816956.83      2709538.53      6816745.47
      2709498.49      6816534.46
#Sta/Elev= 30
  4786.3  367.59  4789.7  367.12  4873.9  363.33  4890.2  361.73  4895.3  362.34
  4898.0  362.14  4914.8  360.62  4935.2  359.68  4945.5  360.49  4976.1  358.75
  4985.5  357.35  4988.6  355.25  4988.9  354.75  4992.4  354.75  4992.6  355.25
  4998.5  355.45  5006.9  355.44  5027.0  359.00  5037.2  360.31  5047.5  362.63
  5067.7  364.04  5088.1  364.35  5099.8  366.18  5146.9  368.07  5152.0  368.97
  5162.7  369.67  5179.7  369.96  5195.3  370.82  5210.2  372.91  5216.9  373.23
#Mann=7,-1,0
  4786.3    0.05       0  4898.0    0.16       0  4988.6    0.07       0
  4992.6    0.16       0  4998.5    0.12       0  5162.7    0.16       0
  5195.3    0.05       0
Bank Sta=4988.6,4992.6
Exp/Cntr=0.3,0.1

Type RM Length L Ch R = 1,665,108,108,108
BEGIN DESCRIPTION:
Twin Creek240664.96
END DESCRIPTION:
XS GIS Cut Line= 3
      2709690.02      6816865.75      2709618.25      6816669.29
      2709572.35      6816507.02
#Sta/Elev= 30
  4791.8  367.89  4808.1  367.31  4839.4  364.11  4851.3  363.70  4860.7  362.24
  4871.2  361.58  4876.5  360.59  4892.7  359.29  4913.3  358.47  4924.6  358.61
  4937.6  359.96  4956.6  359.43  4962.8  360.12  4977.9  358.15  4988.1  355.72
  5001.0  355.33  5007.6  353.94  5007.8  353.44  5011.3  353.44  5011.6  353.94
  5020.0  354.81  5031.6  360.74  5065.5  363.64  5082.3  364.71  5092.7  364.74
  5104.7  366.22  5120.5  366.80  5133.5  367.03  5155.1  368.77  5169.6  369.13
#Mann=6,-1,0
  4791.8    0.05       0  4808.1    0.16       0  4913.3    0.12       0
  5007.6    0.07       0  5011.6    0.12       0  5120.5    0.16       0
Bank Sta=5007.6,5011.6
Exp/Cntr=0.3,0.1

Type RM Length L Ch R = 1,557,166,166,166
BEGIN DESCRIPTION:
Twin Creek240557.05
END DESCRIPTION:
XS GIS Cut Line= 3
      2709795.96      6816770.85      2709711.12      6816623.43
      2709620.77      6816440.07
#Sta/Elev= 30
  4831.8  365.29  4889.3  362.00  4920.0  359.71  4957.4  358.95  4963.2  358.26
  4979.0  357.53  4993.2  357.40  5006.2  354.29  5013.6  353.43  5021.1  352.26
  5021.3  351.76  5024.8  351.76  5025.1  352.26  5028.6  353.72  5038.0  354.81
  5045.5  354.84  5068.0  358.34  5073.5  360.28  5076.5  360.39  5090.4  360.70
  5104.9  361.61  5118.5  363.60  5127.2  364.03  5135.4  365.15  5157.8  366.71
  5163.4  367.55  5180.3  367.84  5187.0  368.90  5194.1  368.40  5206.3  369.16
#Mann=6,-1,0
  4831.8    0.05       0  5013.6    0.12       0  5021.1    0.05       0
  5025.1    0.12       0  5076.5    0.05       0  5187.0    0.12       0
Bank Sta=5021.1,5025.1
Exp/Cntr=0.3,0.1

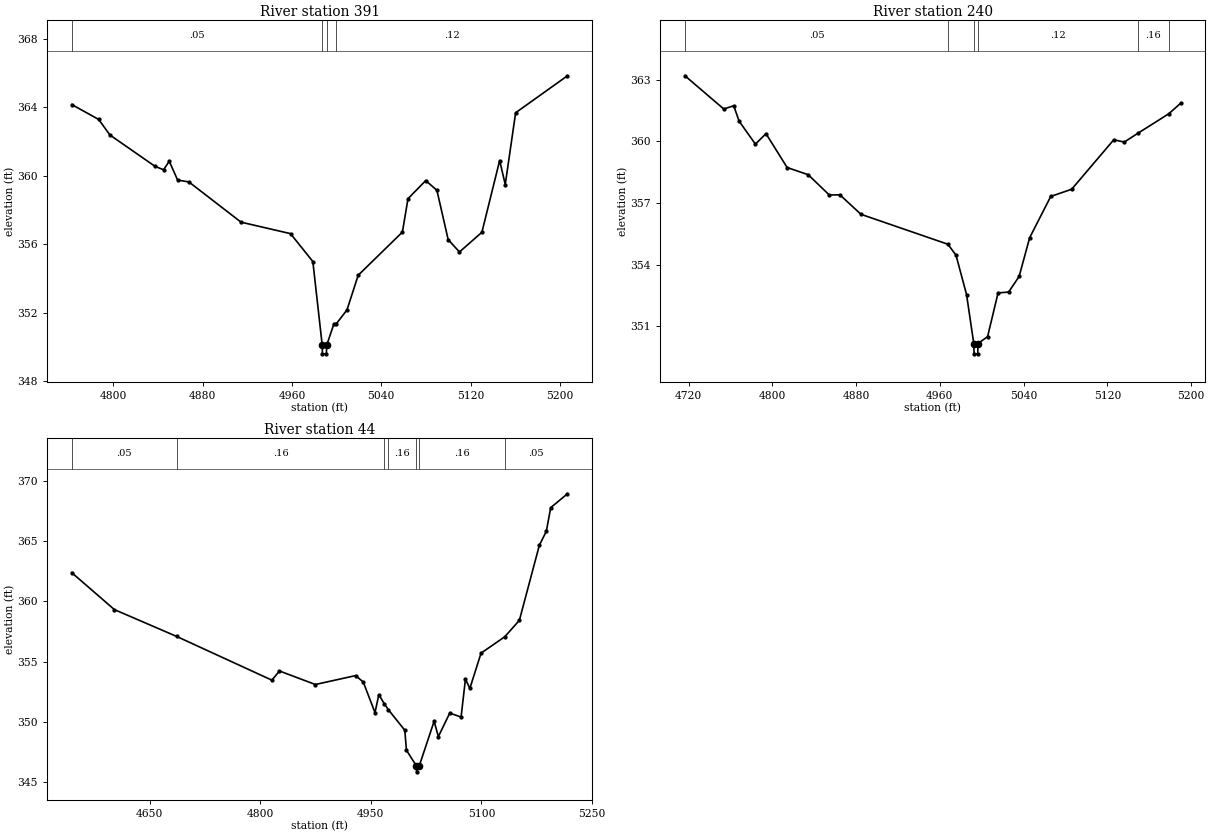
Type RM Length L Ch R = 1,391,151,151,151
BEGIN DESCRIPTION:
Twin Creek240390.72
END DESCRIPTION:
XS GIS Cut Line= 3
      2709843.47      6816744.80      2709808.43      6816509.12
      2709783.83      6816304.97
#Sta/Elev= 30
  4762.8  364.15  4786.9  363.28  4797.0  362.37  4837.4  360.54  4845.0  360.34
  4850.1  360.84  4857.6  359.74  4867.7  359.63  4914.4  357.28  4958.7  356.61
  4978.7  354.98  4987.1  350.09  4987.3  349.59  4990.8  349.59  4991.1  350.09
  4997.6  351.35  4999.8  351.35  5009.3  352.16  5019.3  354.18  5058.9  356.70
  5063.9  358.65  5079.8  359.71  5089.8  359.14  5099.9  356.26  5110.0  355.54
  5130.1  356.69  5146.0  360.88  5151.0  359.48  5160.3  363.67  5206.7  365.83
#Mann=4,-1,0
  4762.8    0.05       0  4987.1    0.07       0  4991.1    0.05       0
  4999.8    0.12       0
Bank Sta=4987.1,4991.1
Exp/Cntr=0.3,0.1

Type RM Length L Ch R = 1,240,196,196,196
BEGIN DESCRIPTION:
Twin Creek240240
END DESCRIPTION:
XS GIS Cut Line= 3
      2709904.50      6816727.79      2709940.29      6816448.28
      2709922.61      6816257.39
#Sta/Elev= 30
  4716.5  363.20  4753.6  361.58  4763.1  361.74  4768.2  360.99  4783.8  359.87
  4793.9  360.38  4814.1  358.73  4834.2  358.38  4854.4  357.39  4864.5  357.40
  4884.6  356.45  4967.7  354.99  4975.4  354.46  4985.5  352.54  4992.4  350.15
  4992.7  349.65  4996.2  349.65  4996.4  350.15  5005.6  350.49  5015.6  352.62
  5025.7  352.66  5035.7  353.42  5045.8  355.31  5065.9  357.32  5085.9  357.67
  5126.1  360.08  5136.2  359.97  5148.9  360.39  5178.7  361.35  5190.0  361.86
#Mann=6,-1,0
  4716.5    0.05       0  4967.7    0.12       0  4992.4    0.07       0
  4996.4    0.12       0  5148.9    0.16       0  5178.7    0.05       0
Bank Sta=4992.4,4996.4
Exp/Cntr=0.3,0.1

Type RM Length L Ch R = 1,44,0,0,0
BEGIN DESCRIPTION:
Twin Creek24044.013
END DESCRIPTION:
XS GIS Cut Line= 3
      2709966.85      6816753.65      2710082.14      6816312.68
      2709967.94      6816128.51
#Sta/Elev= 30
  4544.2  362.37  4602.0  359.31  4686.3  357.09  4815.7  353.46  4826.0  354.22
  4874.7  353.10  4929.4  353.84  4939.7  353.30  4955.6  350.77  4960.8  352.26
  4968.4  351.48  4973.8  351.01  4996.0  349.31  4998.3  347.65  5011.7  346.36
  5012.0  345.86  5015.7  346.36  5035.8  350.05  5041.6  348.78  5057.0  350.73
  5072.4  350.40  5078.3  353.54  5084.3  352.78  5099.5  355.70  5131.7  357.06
  5151.5  358.42  5178.6  364.64  5188.1  365.81  5194.0  367.76  5216.7  368.91
#Mann=7,-1,0
  4544.2    0.05       0  4686.3    0.16       0  4968.4    0.12       0
  4973.8    0.16       0  5011.7    0.07       0  5015.7    0.16       0
  5131.7    0.05       0
Bank Sta=5011.7,5015.7
Exp/Cntr=0.3,0.1

Chan Stop Cuts=-1