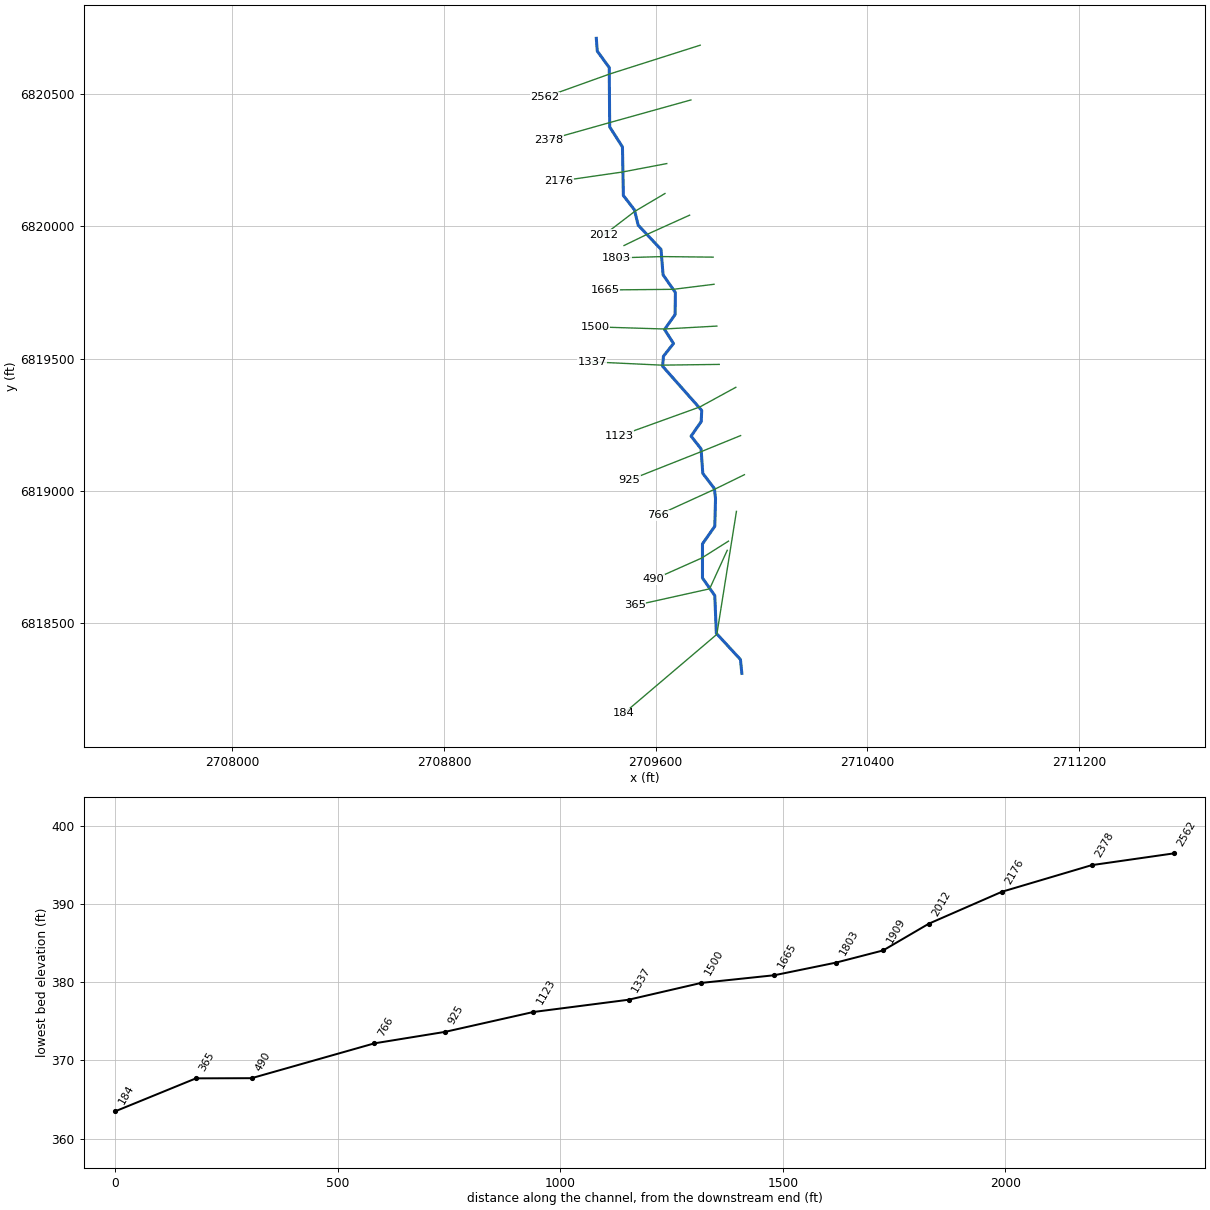
--- Twin Creek242.prj (project) ---

Proj Title=Twin Creek242 Base Level Engineering
Current Plan=p01
Default Exp/Contr=0.3,0.1
English Units
Geom File=g01
Flow File=f01
Plan File=p01
Y Axis Title=Elevation
X Axis Title(PF)=Main Channel Distance
X Axis Title(XS)=Station
BEGIN DESCRIPTION:
Twin Creek242
END DESCRIPTION:
DSS Export Rating Curves= 0
DSS Export Rating Curve Sorted= 0
DSS Export Volume Flow Curves= 0
DXF OffsetX= 0
DXF OffsetY= 0
DXF ScaleX= 1
DXF ScaleY= 10

--- Twin Creek242.p01 (plan) ---

Plan Title=Multiple Run
Short Identifier=Multiple
Geom File=g01
Flow File=f01
Subcritical Flow
K Sum by GR= 0
Std Step Tol= 0.01
Critical Tol= 0.01
Num of Std Step Trials= 20
Max Error Tol= 0.3
Flow Tol Ratio= 0.001
Split Flow NTrial= 30
Split Flow Tol= 0.02
Split Flow Ratio= 0.02
Log Output Level= 0
Friction Slope Method= 1
Unsteady Friction Slope Method= 2
Unsteady Bridges Friction Slope Method= 1
Parabolic Critical Depth
Global Vel Dist=  1 , 1 , 1
Global Log Level= 0
CheckData=True
Encroach Param= -1, 0, 0, 0
BEGIN DESCRIPTION:
Multiple Run
END DESCRIPTION:

--- Twin Creek242.f01 (steady flow) ---

Flow Title=Multiple
Number of Profiles=7
Profile Names=10-year,25-year,50-year,1pct_min,100-year,1pct_plu,500-year
River Rch & RM= Twin Creek242,Reach-1,2562
     215     271     313     181     360     719     475
Boundary for River Rch & Prof#=Twin Creek242,Reach-1,1
Up Type=0
Dn Type=3
Dn Slope=0.005
Boundary for River Rch & Prof#=Twin Creek242,Reach-1,2
Up Type=0
Dn Type=3
Dn Slope=0.005
Boundary for River Rch & Prof#=Twin Creek242,Reach-1,3
Up Type=0
Dn Type=3
Dn Slope=0.005
Boundary for River Rch & Prof#=Twin Creek242,Reach-1,4
Up Type=0
Dn Type=3
Dn Slope=0.005
Boundary for River Rch & Prof#=Twin Creek242,Reach-1,5
Up Type=0
Dn Type=3
Dn Slope=0.005
Boundary for River Rch & Prof#=Twin Creek242,Reach-1,6
Up Type=0
Dn Type=3
Dn Slope=0.005
Boundary for River Rch & Prof#=Twin Creek242,Reach-1,7
Up Type=0
Dn Type=3
Dn Slope=0.005

--- Twin Creek242.g01 (geometry) ---

Geom Title=Existing Conditions
Program Version=4.10

River Reach=Twin Creek242   ,Reach-1
Reach XY= 30
        2709376.        6820711.      2709379.65      6820662.51
      2709424.88      6820600.54      2709426.52      6820376.22
      2709474.78      6820300.49      2709478.24      6820116.93
      2709519.86      6820063.17      2709534.16      6820004.95
      2709620.46      6819913.42      2709628.36      6819816.98
      2709674.89      6819750.45      2709673.64      6819666.89
       2709633.8       6819610.9      2709667.68      6819557.77
      2709629.56      6819509.35      2709626.64      6819471.64
      2709774.34      6819304.95      2709772.43      6819262.65
       2709734.1      6819207.71      2709771.91       6819159.5
      2709778.35      6819066.98      2709822.23      6819009.43
       2709826.5      6818971.17      2709823.75      6818866.94
      2709777.21      6818800.49      2709777.21      6818671.51
      2709823.73      6818605.06      2709829.54      6818462.47
      2709920.67      6818363.51        2709926.        6818311.

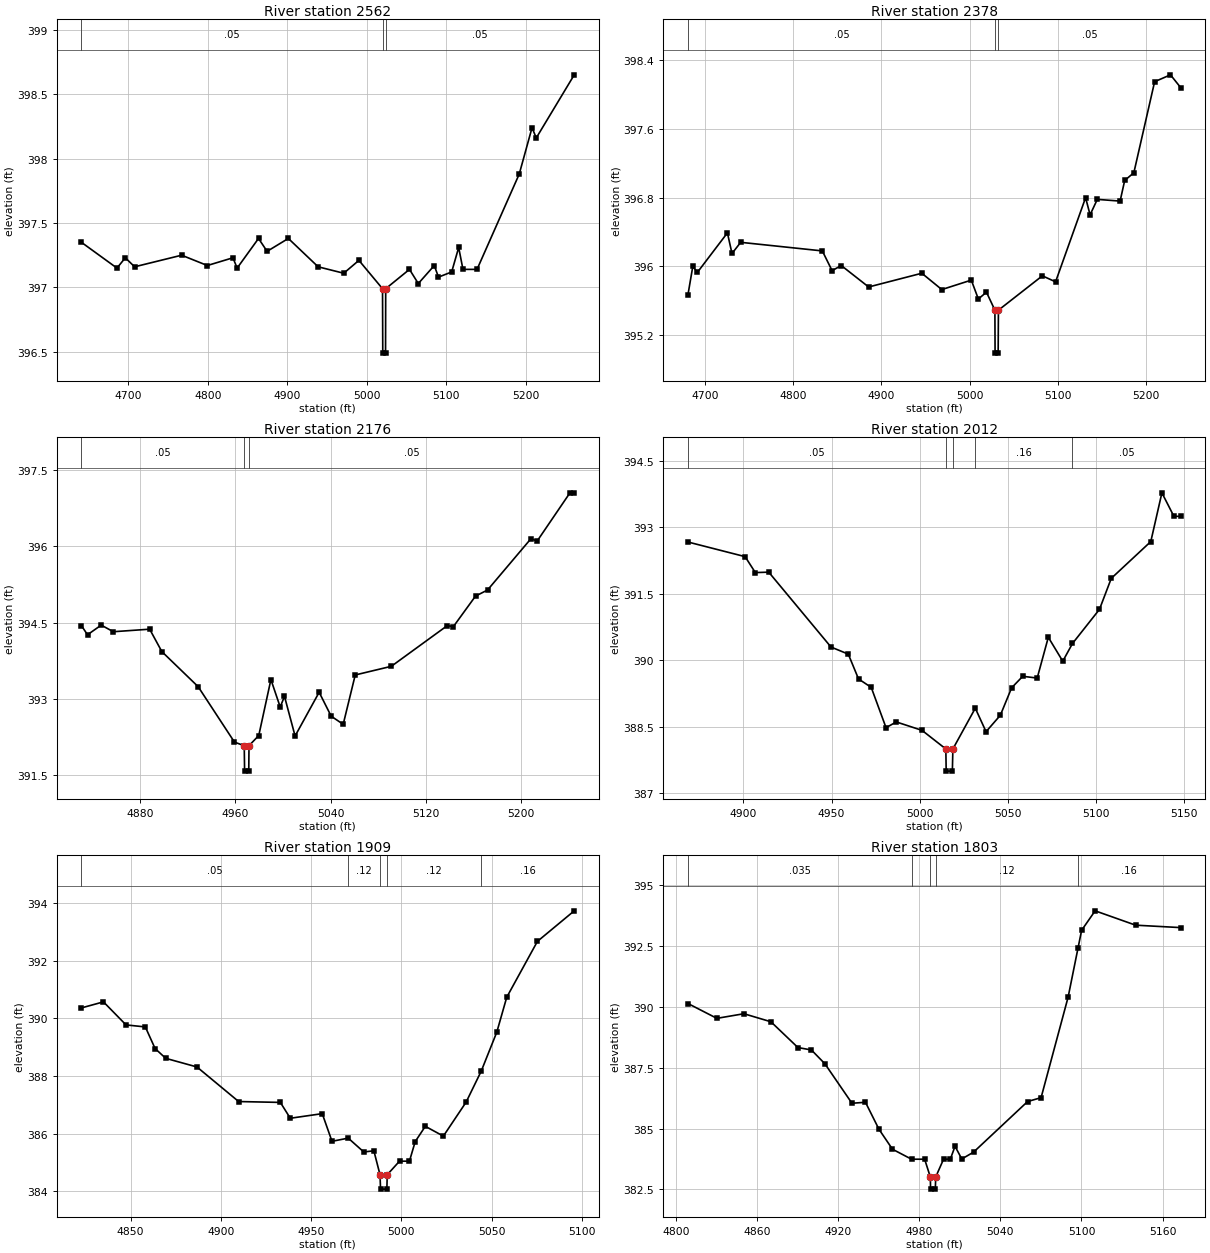
Type RM Length L Ch R = 1 ,2562    ,184,184,184
BEGIN DESCRIPTION:
Twin Creek2422562.337
END DESCRIPTION:
XS GIS Cut Line= 3
      2709768.64      6820685.06      2709426.44      6820576.18
      2709180.85      6820488.14
#Sta/Elev= 30
  4640.9  397.35  4685.6  397.15  4696.1  397.23  4707.8  397.16    4767  397.25
  4799.3  397.17  4831.5  397.23  4836.8  397.15  4863.7  397.38  4874.5  397.28
  4901.2  397.38  4938.7  397.16  4970.9  397.11    4990  397.21  5019.7  396.99
    5020  396.49  5023.5  396.49  5023.7  396.99  5053.6  397.14  5064.7  397.03
  5084.8  397.17  5090.1  397.08  5106.7  397.12  5115.5  397.31  5120.9  397.14
  5138.6  397.14  5191.7  397.88  5207.8  398.24  5213.1  398.16  5260.9  398.65
#Mann= 3 ,-1 , 0
  4640.9     .05       0  5019.7     .05       0  5023.7     .05       0
Bank Sta=5019.7,5023.7
XS Rating Curve= 0 ,0
Exp/Cntr=0.3,0.1

Type RM Length L Ch R = 1 ,2378    ,202,202,202
BEGIN DESCRIPTION:
Twin Creek2422378.6
END DESCRIPTION:
XS GIS Cut Line= 3
      2709733.68      6820478.19      2709423.75      6820391.78
       2709194.7      6820327.33
#Sta/Elev= 30
  4680.2  395.67  4685.7     396  4690.9  395.93    4725  396.39  4730.2  396.15
  4740.1  396.28  4832.8  396.18  4843.9  395.95  4854.3  396.01  4885.4  395.76
  4945.8  395.92  4968.5  395.73    5002  395.84    5010  395.62  5019.2   395.7
  5028.8  395.49    5029  394.99  5032.5  394.99  5032.8  395.49  5082.7  395.89
  5097.7  395.82  5131.8   396.8  5136.9   396.6  5145.1  396.78    5171  396.76
  5176.2     397  5186.6  397.09  5210.2  398.15  5228.2  398.23  5239.9  398.08
#Mann= 3 ,-1 , 0
  4680.2     .05       0  5028.8     .05       0  5032.8     .05       0
Bank Sta=5028.8,5032.8
XS Rating Curve= 0 ,0
Exp/Cntr=0.3,0.1

Type RM Length L Ch R = 1 ,2176    ,164,164,164
BEGIN DESCRIPTION:
Twin Creek2422176.07
END DESCRIPTION:
XS GIS Cut Line= 3
      2709642.29      6820237.67      2709473.94      6820205.68
        2709234.      6820170.97
#Sta/Elev= 30
  4830.7  394.44  4835.8  394.26  4847.3  394.45  4857.5  394.32    4888  394.37
  4898.2  393.93  4928.7  393.24  4959.2  392.15  4967.4  392.08  4967.7  391.58
  4971.2  391.58  4971.4  392.08  4979.6  392.28  4989.8  393.38  4997.6  392.84
  5001.2  393.05  5010.1  392.27  5030.3  393.13  5040.4  392.66  5050.5   392.5
  5060.6  393.47  5090.9  393.64  5137.9  394.44    5143  394.42  5161.6  395.02
  5171.7  395.14  5208.2  396.15  5213.3   396.1  5240.9  397.05  5244.5  397.05
#Mann= 3 ,-1 , 0
  4830.7     .05       0  4967.4     .05       0  4971.4     .05       0
Bank Sta=4967.4,4971.4
XS Rating Curve= 0 ,0
Exp/Cntr=0.3,0.1

Type RM Length L Ch R = 1 ,2012    ,103,103,103
BEGIN DESCRIPTION:
Twin Creek2422012.17
END DESCRIPTION:
XS GIS Cut Line= 3
      2709635.42      6820124.53      2709521.24        6820057.
      2709404.76      6819967.75
#Sta/Elev= 30
  4868.6  392.67    4901  392.34  4906.8  391.98  4914.4  391.99  4949.7   390.3
  4959.5  390.14  4965.3  389.58  4972.5  389.39  4980.9  388.48  4986.7  388.61
  5001.3  388.42  5014.8     388    5015   387.5  5018.5   387.5  5018.8     388
  5031.5  388.92  5037.6  388.39  5045.7  388.76  5052.1  389.38  5058.4  389.64
  5066.6   389.6  5072.9  390.52  5081.1  389.98  5086.6  390.38  5101.9  391.15
  5108.6  391.85    5131  392.68  5137.3  393.78  5144.1  393.25    5148  393.25
#Mann= 5 ,-1 , 0
  4868.6     .05       0  5014.8     .05       0  5018.8     .05       0
  5031.5     .16       0  5086.6     .05       0
Bank Sta=5014.8,5018.8
XS Rating Curve= 0 ,0
Exp/Cntr=0.3,0.1

Type RM Length L Ch R = 1 ,1909    ,106,106,106
BEGIN DESCRIPTION:
Twin Creek2421909.4
END DESCRIPTION:
XS GIS Cut Line= 3
      2709728.53      6820042.67      2709564.84      6819968.79
      2709480.79      6819928.03
#Sta/Elev= 30
  4822.8  390.36    4835  390.57  4847.5  389.77  4858.2   389.7  4863.6  388.95
  4869.5  388.61  4886.8  388.31  4909.9  387.11    4933  387.08  4938.5  386.53
  4956.2  386.69  4961.6  385.73  4970.6  385.84  4979.2  385.36  4984.8   385.4
  4988.2  384.57  4988.5  384.07    4992  384.07  4992.2  384.57    4999  385.04
  5004.5  385.04  5007.7  385.72  5013.3  386.25  5023.3  385.91  5035.9  387.09
  5044.3  388.17  5052.9  389.52  5058.4  390.73  5075.4  392.67  5095.8  393.73
#Mann= 5 ,-1 , 0
  4822.8     .05       0  4970.6     .12       0  4988.2     .07       0
  4992.2     .12       0  5044.3     .16       0
Bank Sta=4988.2,4992.2
XS Rating Curve= 0 ,0
Exp/Cntr=0.3,0.1

Type RM Length L Ch R = 1 ,1803    ,138,138,138
BEGIN DESCRIPTION:
Twin Creek2421803.48
END DESCRIPTION:
XS GIS Cut Line= 3
      2709817.37      6819884.09      2709625.28       6819886.2
      2709452.66      6819881.17
#Sta/Elev= 30
  4808.7  390.14  4830.1  389.53  4850.1  389.72  4870.1  389.39  4890.1  388.33
  4900.1  388.23  4910.1  387.66  4930.1  386.04  4940.1  386.08  4950.1  384.97
  4960.1  384.15  4974.2  383.74  4983.9  383.74  4988.1  383.01  4988.3  382.51
  4991.8  382.51  4992.1  383.01  4997.9  383.74  5002.9  383.74  5006.4  384.27
  5011.4  383.75  5020.1  384.03  5060.1  386.11  5070.1  386.27  5090.1   390.4
  5097.4  392.41  5100.1  393.15  5110.1  393.95  5140.1  393.36  5173.5  393.26
#Mann= 5 ,-1 , 0
  4808.7    .035       0  4974.2     .12       0  4988.1     .07       0
  4992.1     .12       0  5097.4     .16       0
Bank Sta=4988.1,4992.1
XS Rating Curve= 0 ,0
Exp/Cntr=0.3,0.1

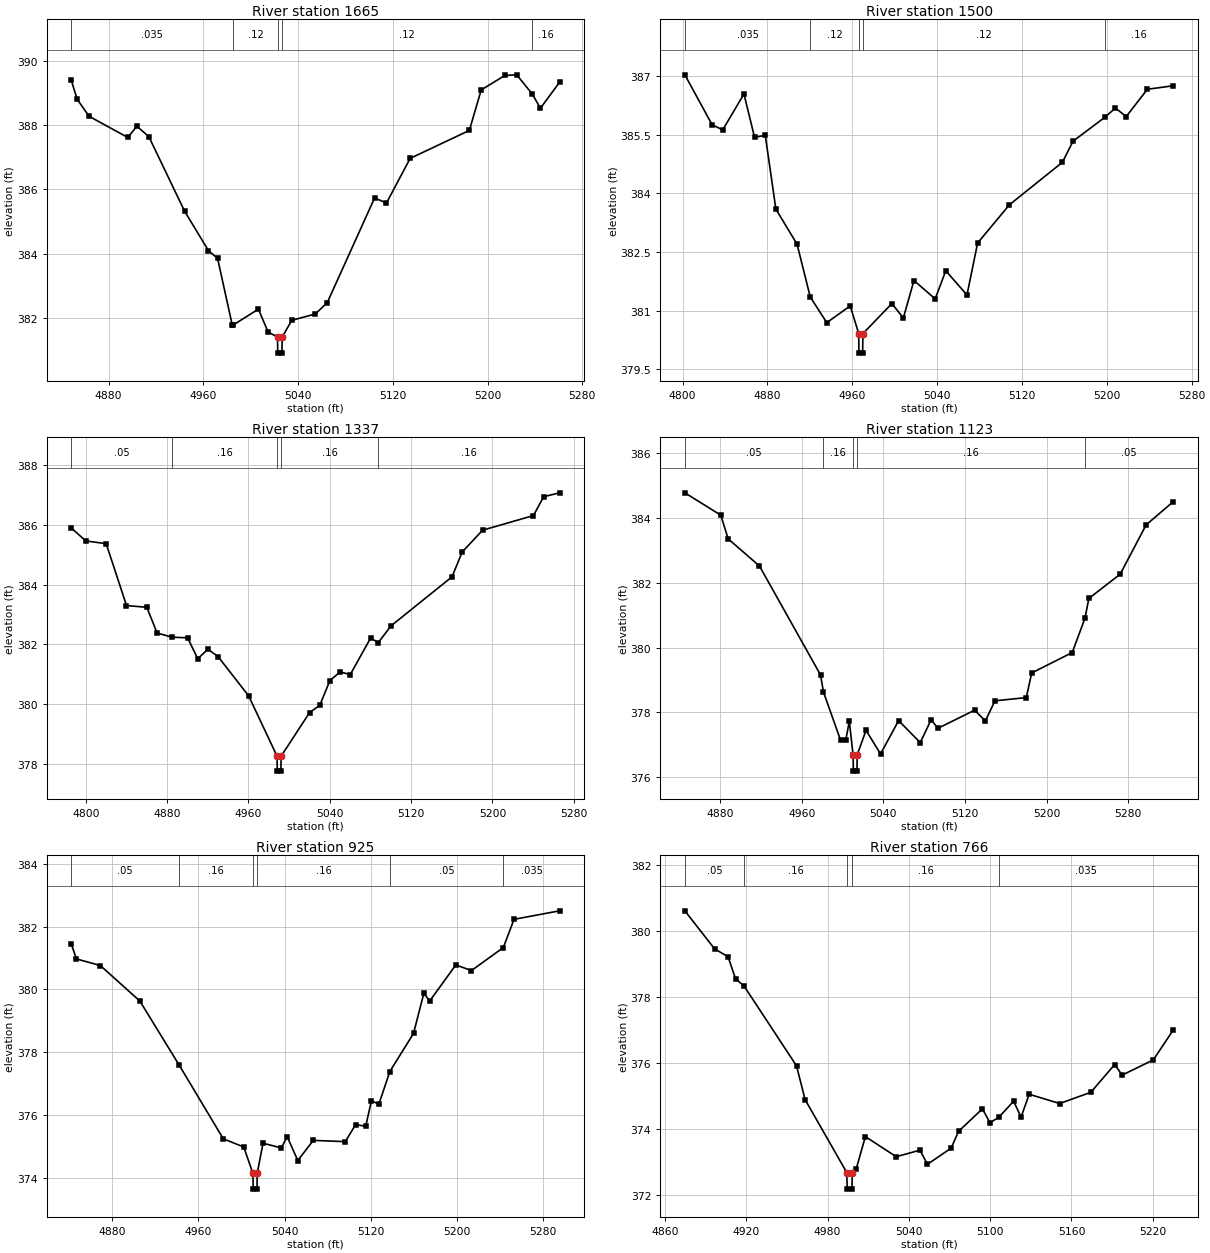
Type RM Length L Ch R = 1 ,1665    ,165,165,165
BEGIN DESCRIPTION:
Twin Creek2421664.95
END DESCRIPTION:
XS GIS Cut Line= 3
      2709821.07      6819781.58      2709667.12      6819762.47
      2709409.77      6819760.03
#Sta/Elev= 30
  4848.3  389.41  4853.4   388.8  4863.5  388.27  4896.2  387.61  4903.8  387.96
  4913.9  387.64  4944.1  385.32  4964.3  384.09    4972  383.85  4984.4  381.77
  4985.4  381.78  5006.5  382.27  5014.6  381.56  5022.6   381.4  5022.8   380.9
  5026.3   380.9  5026.6   381.4  5034.6  381.92  5054.6  382.12  5064.6  382.47
  5104.6  385.73  5114.6  385.57  5134.6  386.96  5184.6  387.83  5194.6  389.09
  5214.6  389.54  5224.6  389.56  5237.8  388.96  5244.6  388.52  5260.8  389.33
#Mann= 5 ,-1 , 0
  4848.3    .035       0  4985.4     .12       0  5022.6     .07       0
  5026.6     .12       0  5237.8     .16       0
Bank Sta=5022.6,5026.6
XS Rating Curve= 0 ,0
Exp/Cntr=0.3,0.1

Type RM Length L Ch R = 1 ,1500    ,163,163,163
BEGIN DESCRIPTION:
Twin Creek2421499.84
END DESCRIPTION:
XS GIS Cut Line= 3
      2709831.64      6819623.57      2709632.57      6819612.53
      2709371.47      6819620.64
#Sta/Elev= 30
  4802.1  387.04  4827.8  385.76  4837.8  385.63  4857.8  386.55  4867.8  385.44
  4877.9  385.49  4887.9   383.6  4907.9   382.7  4920.3  381.35  4935.9  380.69
    4958  381.12    4966  380.41  4966.2  379.91  4969.7  379.91    4970  380.41
  4997.3  381.18  5008.1  380.81  5018.1  381.77  5038.1   381.3  5048.1  382.02
  5068.1   381.4  5078.1  382.73  5108.1  383.71  5158.1   384.8  5168.1  385.34
    5198  385.95  5208.1  386.19  5218.2  385.97  5238.2  386.67  5262.7  386.76
#Mann= 5 ,-1 , 0
  4802.1    .035       0  4920.3     .12       0    4966     .07       0
    4970     .12       0    5198     .16       0
Bank Sta=4966,4970
XS Rating Curve= 0 ,0
Exp/Cntr=0.3,0.1

Type RM Length L Ch R = 1 ,1337    ,214,214,214
BEGIN DESCRIPTION:
Twin Creek2421337.24
END DESCRIPTION:
XS GIS Cut Line= 3
      2709840.54      6819478.74      2709622.83      6819475.93
      2709360.35       6819488.3
#Sta/Elev= 30
  4785.5   385.9    4800  385.46    4820  385.37    4840   383.3    4860  383.24
  4870.1  382.38  4884.9  382.24  4900.1  382.22  4910.1  381.52  4920.1  381.84
  4930.1  381.59  4960.1  380.28  4988.1  378.26  4988.3  377.76  4991.8  377.76
  4992.1  378.26  5020.1  379.72  5030.1  379.96  5040.1  380.79  5050.1  381.08
  5060.1  380.99  5080.1  382.21  5087.7  382.06  5100.2  382.62  5160.2  384.26
  5170.2  385.09  5190.3  385.82  5240.3  386.31  5250.3  386.94    5266  387.07
#Mann= 5 ,-1 , 0
  4785.5     .05       0  4884.9     .16       0  4988.1     .07       0
  4992.1     .16       0  5087.7     .16       0
Bank Sta=4988.1,4992.1
XS Rating Curve= 0 ,0
Exp/Cntr=0.3,0.1

Type RM Length L Ch R = 1 ,1123    ,198,198,198
BEGIN DESCRIPTION:
Twin Creek2421122.91
END DESCRIPTION:
XS GIS Cut Line= 3
       2709903.2      6819392.13      2709767.48      6819318.04
      2709462.76      6819208.03
#Sta/Elev= 30
  4845.6  384.78  4880.8  384.09    4888  383.36  4918.7  382.52  4978.5  379.16
  4981.4  378.63  4998.2  377.14  5003.2  377.14  5006.7  377.73  5010.4  376.69
  5010.7  376.19  5014.2  376.19  5014.4  376.69  5023.1  377.45  5037.3  376.72
    5055  377.75  5076.2  377.07  5086.9  377.78  5093.4  377.51  5129.4  378.07
    5140  377.74  5149.4  378.36  5180.1  378.46  5185.4  379.22  5225.1  379.85
  5237.6  380.91  5241.4  381.52  5272.1  382.27  5297.5  383.79  5324.2  384.51
#Mann= 5 ,-1 , 0
  4845.6     .05       0  4981.4     .16       0  5010.4     .07       0
  5014.4     .16       0  5237.6     .05       0
Bank Sta=5010.4,5014.4
XS Rating Curve= 0 ,0
Exp/Cntr=0.3,0.1

Type RM Length L Ch R = 1 ,925     ,159,159,159
BEGIN DESCRIPTION:
Twin Creek242924.75
END DESCRIPTION:
XS GIS Cut Line= 3
      2709921.18      6819209.68      2709772.61      6819149.13
      2709499.85      6819041.14
#Sta/Elev= 30
  4841.7  381.46  4846.7  380.97  4868.9  380.76  4905.6  379.63    4942   377.6
  4983.1  375.25  5002.1  374.99  5010.6  374.15  5010.9  373.65  5014.4  373.65
  5014.6  374.15    5020  375.11    5037  374.96  5042.4  375.32  5052.3  374.56
  5066.7   375.2  5096.4  375.16    5106   375.7  5115.4  375.65  5120.7  376.46
  5127.6  376.35  5137.8  377.39  5159.8   378.6  5169.4  379.88  5174.8  379.63
  5199.1  380.78  5213.6   380.6  5243.2  381.33  5253.2  382.23  5295.5   382.5
#Mann= 6 ,-1 , 0
  4841.7     .05       0    4942     .16       0  5010.6     .07       0
  5014.6     .16       0  5137.8     .05       0  5243.2    .035       0
Bank Sta=5010.6,5014.6
XS Rating Curve= 0 ,0
Exp/Cntr=0.3,0.1

Type RM Length L Ch R = 1 ,766     ,276,276,276
BEGIN DESCRIPTION:
Twin Creek242765.79
END DESCRIPTION:
XS GIS Cut Line= 3
      2709935.66      6819061.94      2709822.06       6819006.3
       2709609.2       6818909.1
#Sta/Elev= 30
  4874.7   380.6  4896.6  379.45  4906.6  379.21  4912.1  378.54  4918.3  378.33
  4957.1  375.91  4963.4  374.89  4994.2  372.68  4994.5  372.18    4998  372.18
  4998.2  372.68  5001.2   372.8  5007.9  373.77  5030.7  373.16  5048.2  373.36
  5053.7  372.93  5071.2  373.42  5076.7  373.93  5094.3  374.61  5099.8  374.19
  5106.3  374.35  5117.3  374.84  5122.8  374.36  5128.8  375.05  5151.3  374.77
  5174.3  375.11  5191.9  375.95  5197.4  375.63  5220.4  376.09  5235.2     377
#Mann= 5 ,-1 , 0
  4874.7     .05       0  4918.3     .16       0  4994.2     .07       0
  4998.2     .16       0  5106.3    .035       0
Bank Sta=4994.2,4998.2
XS Rating Curve= 0 ,0
Exp/Cntr=0.3,0.1

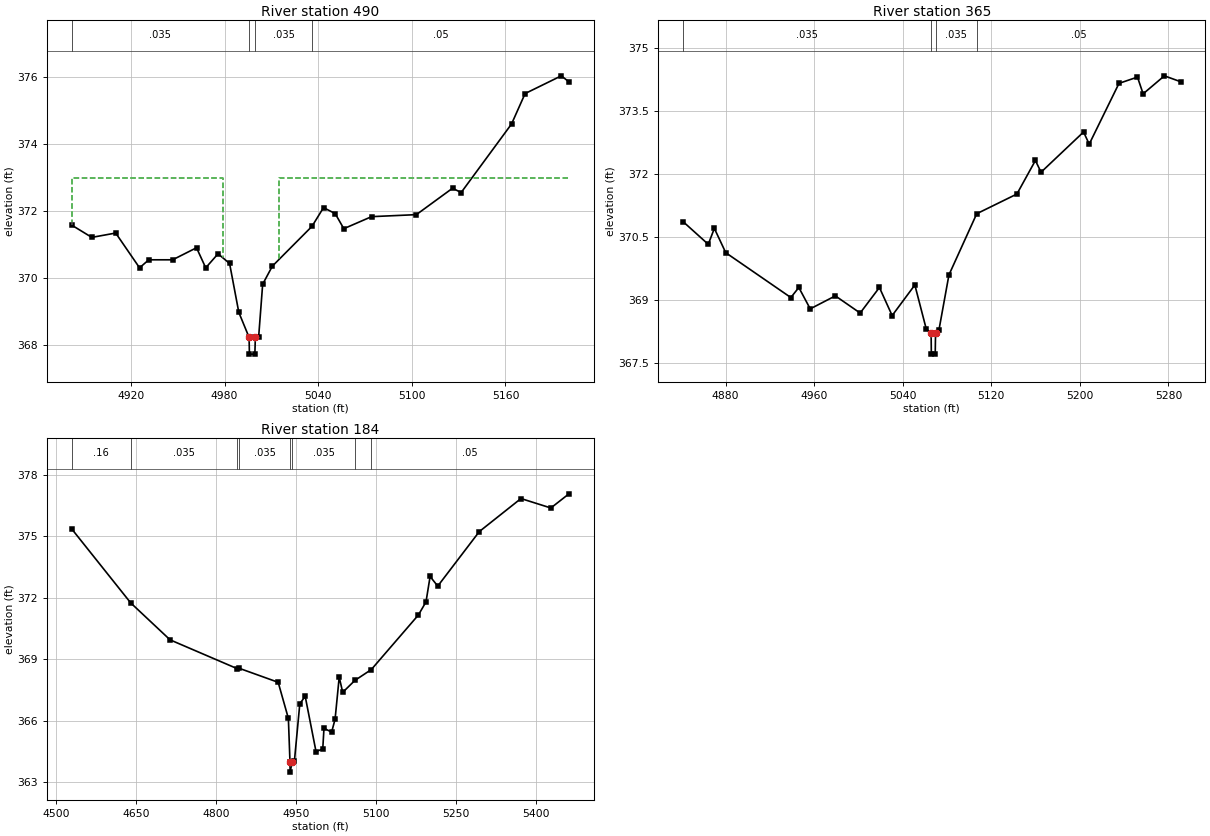
Type RM Length L Ch R = 1 ,490     ,125,125,125
BEGIN DESCRIPTION:
Twin Creek242490.28
END DESCRIPTION:
XS GIS Cut Line= 3
      2709875.44      6818810.79      2709774.02      6818746.79
      2709592.34      6818665.89
#Sta/Elev= 30
  4881.9  371.58  4894.9  371.21  4910.2  371.34  4925.5   370.3  4931.4  370.54
  4946.7  370.54    4962   370.9  4967.9   370.3  4975.8  370.72  4983.2  370.43
  4989.1  368.97  4995.7  368.22  4995.9  367.72  4999.4  367.72  4999.7  368.22
  5001.8  368.22  5004.4  369.81  5010.6  370.35    5036  371.54  5043.4   372.1
  5050.9  371.92  5056.4  371.47  5074.2  371.83  5102.9  371.89  5126.1  372.68
  5131.6  372.55  5163.9   374.6  5172.6  375.51  5195.8  376.04  5200.7  375.86
#Mann= 4 ,-1 , 0
  4881.9    .035       0  4995.7    .035       0  4999.7    .035       0
    5036     .05       0
#XS Ineff= 2 , 0
       0    4979     373    5015       0     373
Permanent Ineff=
       F       F
Bank Sta=4995.7,4999.7
XS Rating Curve= 0 ,0
Exp/Cntr=0.3,0.1

Type RM Length L Ch R = 1 ,365     ,181,181,181
BEGIN DESCRIPTION:
Twin Creek242364.86
END DESCRIPTION:
XS GIS Cut Line= 3
      2709870.73      6818776.04      2709804.23      6818630.59
      2709521.74      6818567.84
#Sta/Elev= 30
  4841.6  370.86  4864.3  370.32  4869.8   370.7  4880.1  370.12  4938.9  369.05
  4946.1  369.29  4956.4  368.78  4979.1  369.09  5001.5  368.68  5018.9  369.29
  5030.4  368.62  5050.9  369.35  5061.2   368.3  5065.6   368.2  5065.8   367.7
  5069.3   367.7  5069.6   368.2  5072.7  368.28  5081.7  369.59  5106.8  371.05
  5143.1  371.52  5159.8  372.32  5164.9  372.04  5203.3     373  5208.4  372.71
  5235.3  374.16    5252  374.31  5257.1  373.91  5276.3  374.34  5290.9   374.2
#Mann= 4 ,-1 , 0
  4841.6    .035       0  5065.6    .035       0  5069.6    .035       0
  5106.8     .05       0
Bank Sta=5065.6,5069.6
XS Rating Curve= 0 ,0
Exp/Cntr=0.3,0.1

Type RM Length L Ch R = 1 ,184     ,0,0,0
BEGIN DESCRIPTION:
Twin Creek242184.055
END DESCRIPTION:
XS GIS Cut Line= 3
      2709905.58      6818923.28      2709831.47      6818458.55
      2709480.01      6818159.91
#Sta/Elev= 30
  4529.4  375.36  4640.3  371.74    4714  369.94  4839.3  368.54  4843.8  368.55
  4916.5  367.87  4935.6  366.11  4938.6  363.99  4938.9  363.49  4942.6  363.99
  4946.9  364.03    4957  366.82  4967.1  367.19  4987.4  364.49    5000  364.62
  5002.3  365.63  5016.6  365.44  5023.1  366.07  5030.8  368.12  5037.4  367.38
  5060.1  367.96  5090.9  368.49  5179.1  371.15  5193.4  371.79  5201.1  373.03
  5215.4  372.56  5293.3  375.22  5371.3  376.83  5427.3  376.37  5461.2  377.06
#Mann= 8 ,-1 , 0
  4529.4     .16       0  4640.3    .035       0  4839.3     .16       0
  4843.8    .035       0  4938.6     .05       0  4942.6    .035       0
  5060.1    .035       0  5090.9     .05       0
Bank Sta=4938.6,4942.6
XS Rating Curve= 0 ,0
Exp/Cntr=0.3,0.1

Chan Stop Cuts=-1
Use User Specified Reach Order=0
Composite Channel Slope=5