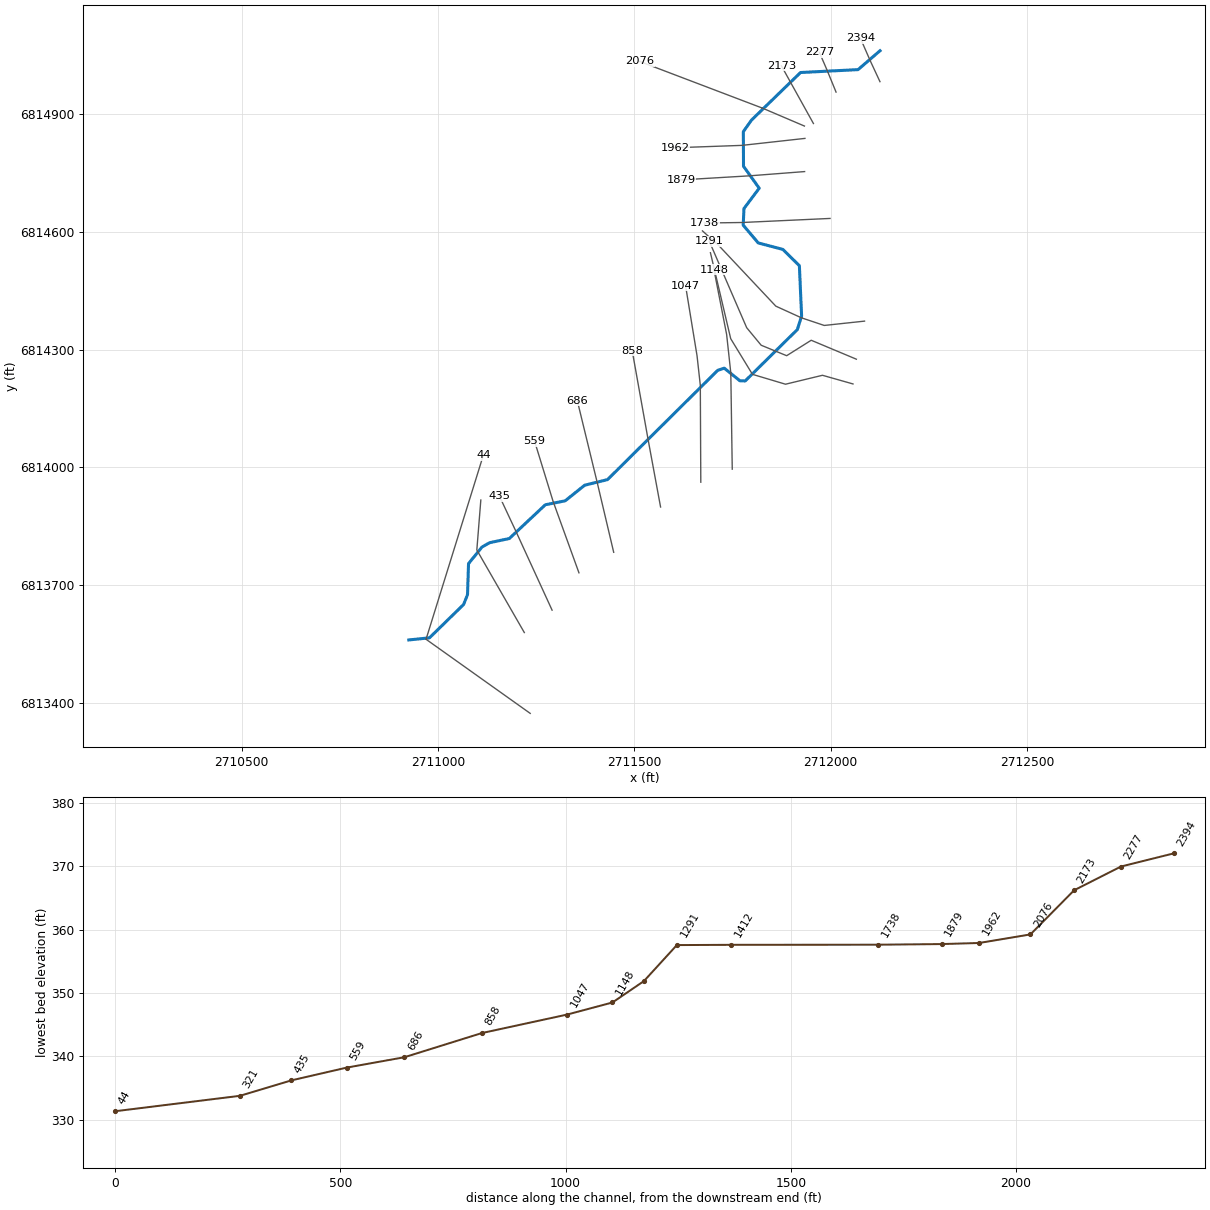
--- Twin Creek244.prj (project) ---

Proj Title=Twin Creek244 Base Level Engineering
Current Plan=p01
Default Exp/Contr=0.3,0.1
English Units
Geom File=g01
Flow File=f01
Plan File=p01
BEGIN DESCRIPTION:
Twin Creek244
END DESCRIPTION:

--- Twin Creek244.p01 (plan) ---

Plan Title=Multiple Run
Short Identifier=Multiple
Geom File=g01
Flow File=f01
Subcritical Flow
K Sum by GR= 0
Std Step Tol= 0.01
Critical Tol= 0.01
Num of Std Step Trials= 20
Max Error Tol= 0.3
Flow Tol Ratio= 0.001
Split Flow NTrial= 30
Split Flow Tol= 0.02
Split Flow Ratio= 0.02
Log Output Level= 0
Friction Slope Method= 1
Unsteady Friction Slope Method= 2
Unsteady Bridges Friction Slope Method= 1
Parabolic Critical Depth
Global Vel Dist=  1 , 1 , 1
Global Log Level= 0
CheckData=True
Encroach Param= -1, 0, 0, 0
BEGIN DESCRIPTION:
Multiple Run
END DESCRIPTION:

--- Twin Creek244.f01 (steady flow) ---

Flow Title=Multiple
Number of Profiles=7
Profile Names=10-year,25-year,50-year,1pct_min,100-year,1pct_plu,500-year
River Rch & RM= Twin Creek244,Reach-1,2394
      96     114     126      70     139     277     169
Boundary for River Rch & Prof#=Twin Creek244,Reach-1,1
Up Type=0
Dn Type=3
Dn Slope=0.005
Boundary for River Rch & Prof#=Twin Creek244,Reach-1,2
Up Type=0
Dn Type=3
Dn Slope=0.005
Boundary for River Rch & Prof#=Twin Creek244,Reach-1,3
Up Type=0
Dn Type=3
Dn Slope=0.005
Boundary for River Rch & Prof#=Twin Creek244,Reach-1,4
Up Type=0
Dn Type=3
Dn Slope=0.005
Boundary for River Rch & Prof#=Twin Creek244,Reach-1,5
Up Type=0
Dn Type=3
Dn Slope=0.005
Boundary for River Rch & Prof#=Twin Creek244,Reach-1,6
Up Type=0
Dn Type=3
Dn Slope=0.005
Boundary for River Rch & Prof#=Twin Creek244,Reach-1,7
Up Type=0
Dn Type=3
Dn Slope=0.005

--- Twin Creek244.g01 (geometry) ---

Geom Title=Existing Conditions

River Reach=Twin Creek244,Reach-1
Reach XY= 30
      2712126.00      6815061.00      2712070.21      6815012.91
      2711923.55      6815005.54      2711798.84      6814884.52
      2711777.97      6814855.11      2711778.36      6814766.90
      2711818.40      6814710.99      2711779.56      6814659.32
      2711777.58      6814616.87      2711815.91      6814571.65
      2711878.55      6814555.25      2711920.65      6814513.70
      2711926.32      6814385.89      2711915.53      6814351.20
      2711782.67      6814220.30      2711769.33      6814220.62
      2711729.33      6814252.84      2711712.67      6814247.35
      2711432.06      6813969.14      2711373.81      6813954.90
      2711324.27      6813915.19      2711273.71      6813905.15
      2711182.02      6813819.19      2711131.85      6813808.55
      2711112.37      6813797.54      2711078.08      6813755.29
      2711075.48      6813676.22      2711065.50      6813651.19
      2710978.54      6813566.30      2710926.00      6813561.00

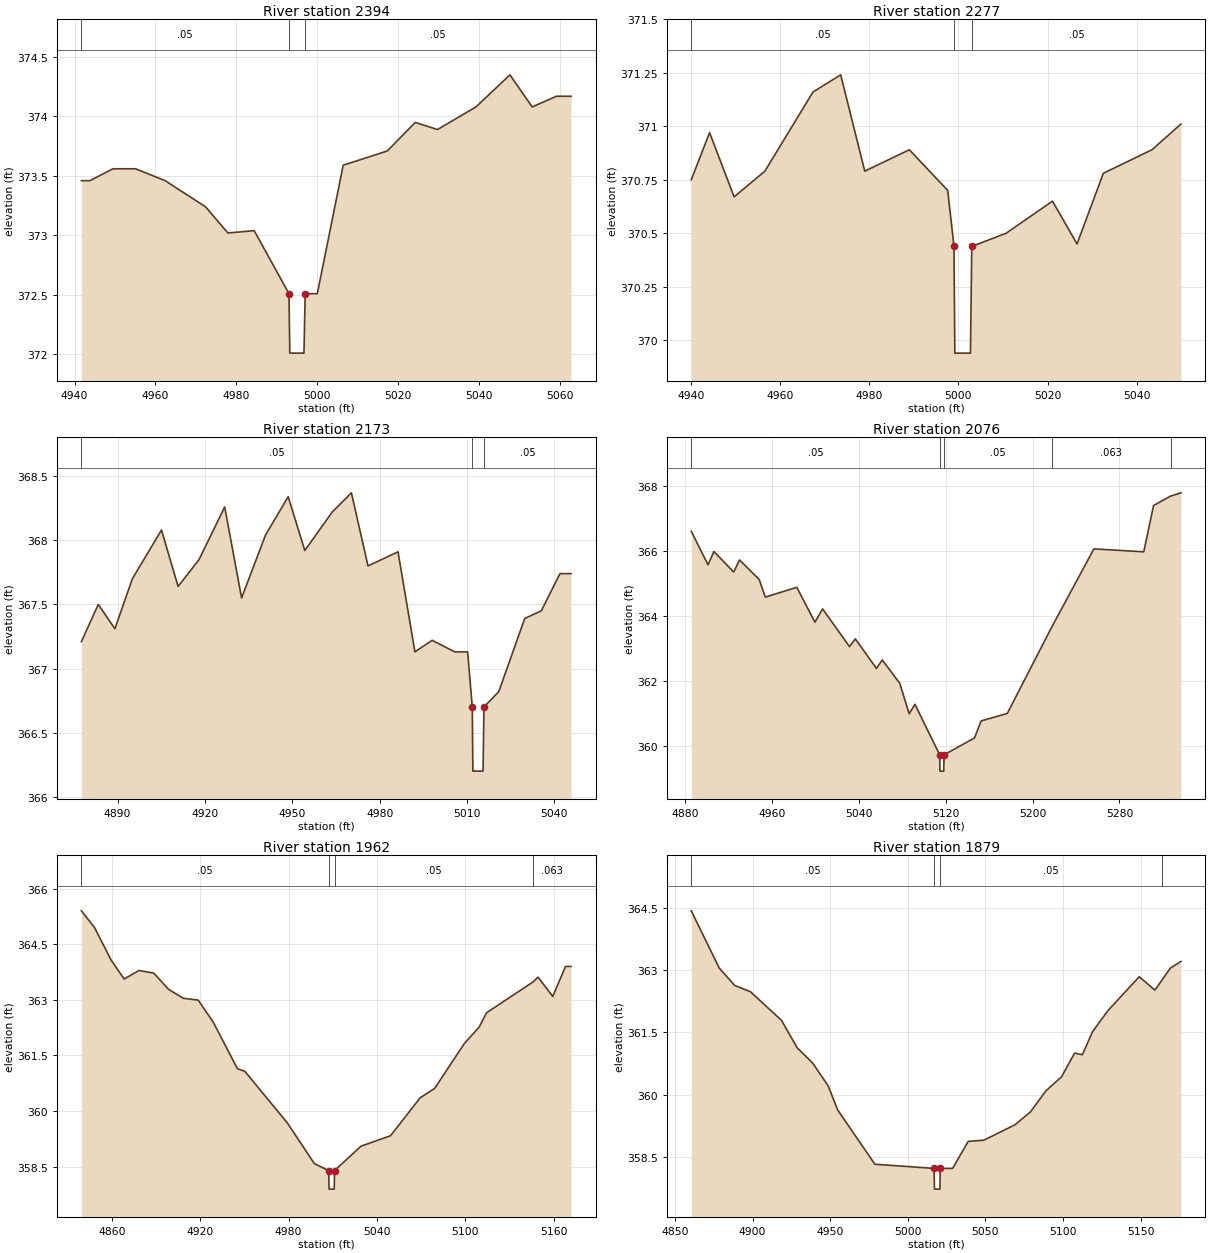
Type RM Length L Ch R = 1,2394,117,117,117
BEGIN DESCRIPTION:
Twin Creek2442360.29
END DESCRIPTION:
XS GIS Cut Line= 3
      2712125.88      6814982.25      2712101.29      6815035.12
      2712076.16      6815092.56
#Sta/Elev= 22
  4941.7  373.46  4943.8  373.46  4949.5  373.56  4955.1  373.56  4962.4  373.46
  4972.4  373.24  4977.9  373.02  4984.4  373.04  4993.0  372.51  4993.2  372.01
  4996.7  372.01  4997.0  372.51  5000.0  372.51  5006.4  373.59  5017.3  373.71
  5024.2  373.95  5029.7  373.89  5039.2  374.08  5047.6  374.35  5053.1  374.08
  5059.1  374.17  5062.7  374.17
#Mann=3,-1,0
  4941.7    0.05       0  4993.0    0.05       0  4997.0    0.05       0
Bank Sta=4993,4997
Exp/Cntr=0.3,0.1

Type RM Length L Ch R = 1,2277,104,104,104
BEGIN DESCRIPTION:
Mapping XS 1bdcb6ed
END DESCRIPTION:
XS GIS Cut Line= 3
      2712014.03      6814955.72      2711990.92      6815012.14
      2711971.55      6815056.96
#Sta/Elev= 20
  4940.1  370.75  4944.2  370.97  4949.7  370.67  4956.6  370.79  4967.4  371.16
  4973.6  371.24  4979.0  370.79  4989.0  370.89  4997.6  370.70  4999.0  370.44
  4999.2  369.94  5002.7  369.94  5003.0  370.44  5003.2  370.44  5010.7  370.50
  5021.1  370.65  5026.6  370.45  5032.5  370.78  5043.4  370.89  5049.9  371.01
#Mann=3,-1,0
  4940.1    0.05       0  4999.0    0.05       0  5003.0    0.05       0
Bank Sta=4999,5003
Exp/Cntr=0.3,0.1

Type RM Length L Ch R = 1,2173,97,97,97
BEGIN DESCRIPTION:
Twin Creek2442172.89
END DESCRIPTION:
XS GIS Cut Line= 3
      2711956.44      6814875.71      2711893.19      6814989.63
      2711874.82      6815022.66
#Sta/Elev= 29
  4877.6  367.21  4883.4  367.50  4889.1  367.31  4895.1  367.70  4905.1  368.08
  4910.8  367.64  4918.0  367.85  4926.8  368.26  4932.6  367.55  4940.8  368.04
  4948.6  368.34  4954.3  367.92  4963.7  368.22  4970.3  368.37  4976.0  367.80
  4986.3  367.91  4992.1  367.13  4998.0  367.22  5005.8  367.13  5010.2  367.13
  5011.8  366.70  5012.0  366.20  5015.5  366.20  5015.8  366.70  5020.9  366.82
  5029.8  367.39  5035.5  367.45  5041.9  367.74  5045.7  367.74
#Mann=3,-1,0
  4877.6    0.05       0  5011.8    0.05       0  5015.8    0.05       0
Bank Sta=5011.8,5015.8
Exp/Cntr=0.3,0.1

Type RM Length L Ch R = 1,2076,114,114,114
BEGIN DESCRIPTION:
Mapping XS 4bd56ede
END DESCRIPTION:
XS GIS Cut Line= 3
      2711933.52      6814869.26      2711826.65      6814914.86
      2711514.06      6815033.69
#Sta/Elev= 30
  4886.0  366.60  4901.4  365.57  4906.8  365.98  4925.0  365.35  4930.4  365.72
  4948.5  365.12  4954.1  364.58  4983.1  364.88  4999.8  363.81  5006.8  364.22
  5031.6  363.06  5036.9  363.30  5056.4  362.39  5061.7  362.65  5077.8  361.94
  5086.5  361.00  5091.8  361.29  5114.6  359.74  5114.8  359.24  5118.3  359.24
  5118.6  359.74  5146.7  360.26  5152.7  360.78  5176.8  361.01  5217.7  363.66
  5256.5  366.06  5302.4  365.97  5311.4  367.39  5327.1  367.68  5336.6  367.78
#Mann=5,-1,0
  4886.0    0.05       0  5114.6    0.05       0  5118.6    0.05       0
  5217.7   0.063       0  5327.1    0.05       0
Bank Sta=5114.6,5118.6
Exp/Cntr=0.3,0.1

Type RM Length L Ch R = 1,1962,83,83,83
BEGIN DESCRIPTION:
Twin Creek2441962.39
END DESCRIPTION:
XS GIS Cut Line= 3
      2711934.82      6814837.80      2711774.41      6814820.05
      2711603.61      6814813.97
#Sta/Elev= 30
  4839.4  365.40  4848.3  364.95  4859.6  364.07  4868.4  363.56  4878.5  363.79
  4888.5  363.72  4898.6  363.28  4908.6  363.04  4918.7  362.99  4928.8  362.40
  4945.3  361.14  4950.3  361.07  4979.1  359.68  4997.5  358.58  5007.2  358.39
  5007.5  357.89  5011.0  357.89  5011.2  358.39  5029.2  359.05  5049.2  359.33
  5069.2  360.35  5079.2  360.61  5099.3  361.82  5109.3  362.26  5114.4  362.65
  5145.9  363.48  5149.3  363.61  5159.3  363.09  5168.0  363.90  5171.7  363.90
#Mann=4,-1,0
  4839.4    0.05       0  5007.2    0.05       0  5011.2    0.05       0
  5145.9   0.063       0
Bank Sta=5007.2,5011.2
Exp/Cntr=0.3,0.1

Type RM Length L Ch R = 1,1879,141,141,141
BEGIN DESCRIPTION:
Twin Creek2441879.25
END DESCRIPTION:
XS GIS Cut Line= 3
      2711933.96      6814753.35      2711794.56      6814742.58
      2711619.19      6814732.13
#Sta/Elev= 30
  4860.5  364.43  4878.5  363.05  4888.5  362.63  4898.6  362.48  4918.6  361.79
  4928.7  361.13  4938.7  360.76  4948.7  360.21  4954.8  359.63  4978.8  358.32
  5016.9  358.22  5017.2  357.72  5020.7  357.72  5020.9  358.22  5028.9  358.22
  5038.9  358.87  5049.0  358.90  5069.0  359.27  5079.0  359.58  5089.0  360.09
  5099.1  360.43  5107.5  361.00  5112.5  360.96  5119.1  361.52  5129.1  362.03
  5149.1  362.84  5159.2  362.52  5163.8  362.76  5169.2  363.05  5176.0  363.21
#Mann=4,-1,0
  4860.5    0.05       0  5016.9    0.05       0  5020.9    0.05       0
  5163.8   0.063       0
Bank Sta=5016.9,5020.9
Exp/Cntr=0.3,0.1

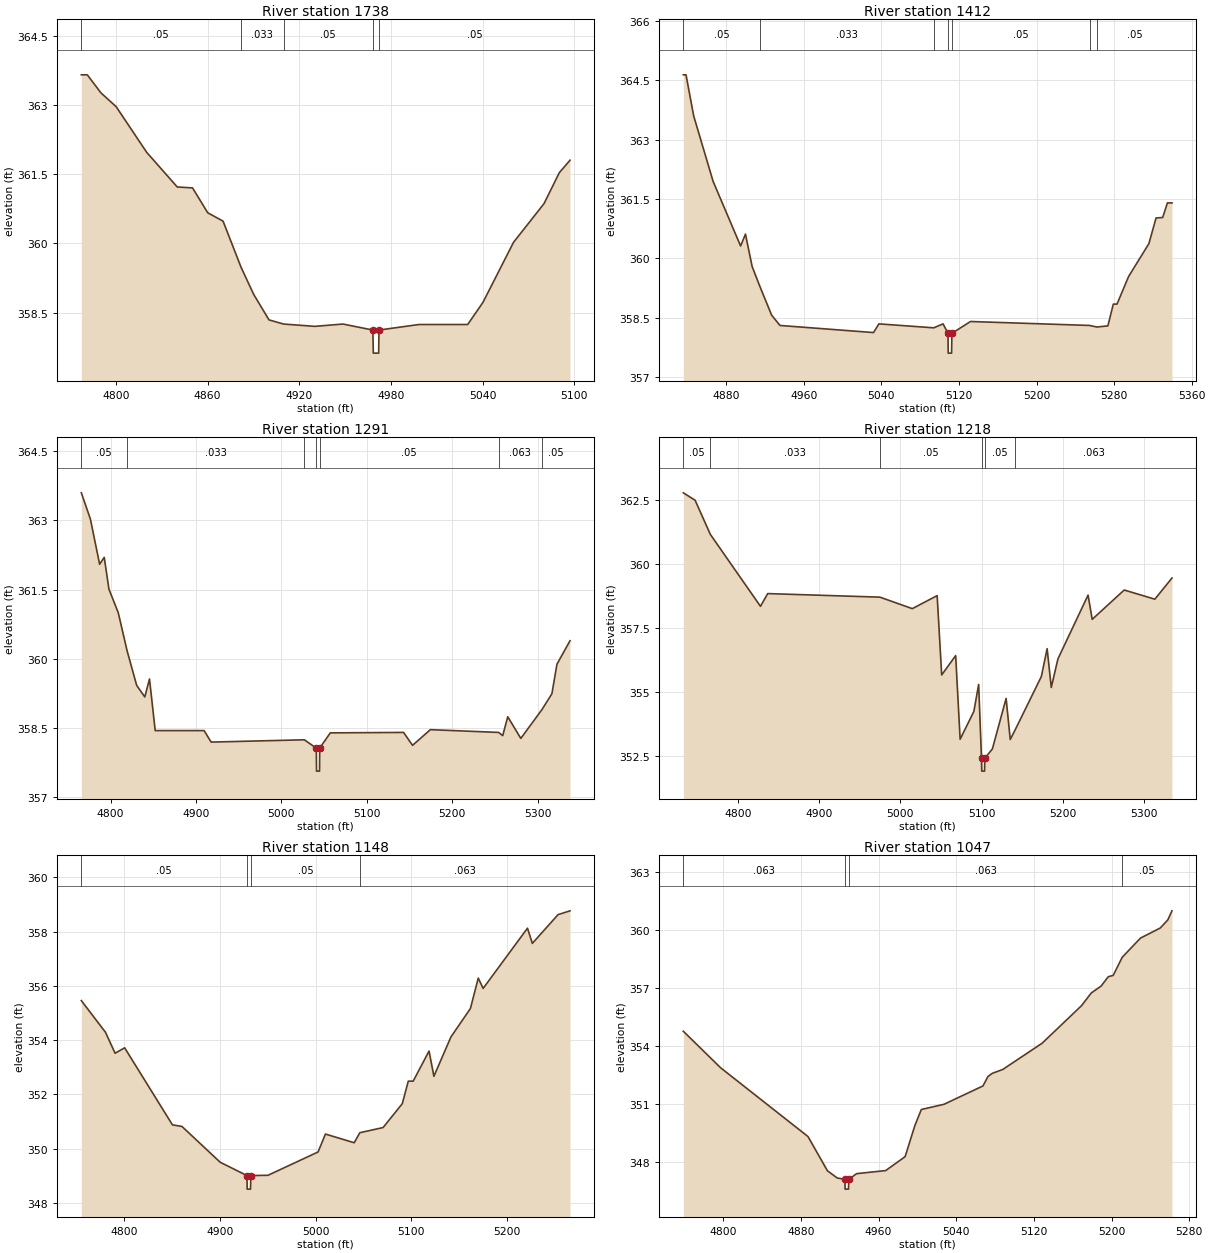
Type RM Length L Ch R = 1,1738,326,326,326
BEGIN DESCRIPTION:
Twin Creek2441737.69
END DESCRIPTION:
XS GIS Cut Line= 3
      2711998.74      6814634.05      2711774.76      6814623.72
      2711678.99      6814622.37
#Sta/Elev= 26
  4777.3  363.65  4781.2  363.65  4790.1  363.26  4800.1  362.96  4820.1  361.97
  4840.1  361.22  4850.1  361.20  4860.1  360.66  4870.1  360.48  4881.9  359.48
  4890.2  358.89  4900.2  358.34  4909.7  358.25  4930.2  358.20  4948.6  358.25
  4968.2  358.12  4968.5  357.62  4972.0  357.62  4972.2  358.12  4998.4  358.24
  5030.3  358.24  5040.3  358.72  5060.3  360.02  5080.3  360.86  5090.3  361.53
  5097.3  361.80
#Mann=5,-1,0
  4777.3    0.05       0  4881.9   0.033       0  4909.7    0.05       0
  4968.2    0.05       0  4972.2    0.05       0
Bank Sta=4968.2,4972.2
Exp/Cntr=0.3,0.1

Type RM Length L Ch R = 1,1412,121,121,121
BEGIN DESCRIPTION:
Twin Creek2441453.15
END DESCRIPTION:
XS GIS Cut Line= 6
      2712086.62      6814372.63      2711983.98      6814361.62
      2711926.06      6814380.99      2711860.64      6814410.75
      2711716.00      6814564.40      2711673.82      6814602.35
#Sta/Elev= 30
  4835.7  364.64  4838.5  364.64  4846.4  363.60  4866.5  361.94  4894.8  360.31
  4899.8  360.61  4906.7  359.79  4914.3  359.31  4926.8  358.56  4935.4  358.30
  5031.9  358.12  5037.4  358.34  5094.0  358.24  5103.6  358.34  5108.7  358.10
  5108.9  357.60  5112.4  357.60  5112.7  358.10  5131.9  358.40  5254.8  358.30
  5262.3  358.26  5273.6  358.29  5279.2  358.84  5283.0  358.84  5295.0  359.54
  5315.9  360.37  5323.3  361.02  5330.1  361.03  5335.0  361.40  5339.7  361.40
#Mann=7,-1,0
  4835.7    0.05       0  4914.3   0.033       0  5094.0    0.05       0
  5108.7   0.033       0  5112.7    0.05       0  5254.8   0.063       0
  5262.3    0.05       0
Bank Sta=5108.7,5112.7
Exp/Cntr=0.3,0.1

Type RM Length L Ch R = 1,1291,73,73,73
BEGIN DESCRIPTION:
Mapping XS e6523f53
END DESCRIPTION:
XS GIS Cut Line= 6
      2712065.80      6814275.69      2711950.77      6814323.92
      2711888.27      6814284.60      2711823.33      6814311.25
      2711786.47      6814355.87      2711691.12      6814576.18
#Sta/Elev= 30
  4765.8  363.60  4776.4  363.03  4787.2  362.05  4792.6  362.20  4798.1  361.51
  4809.0  361.00  4819.4  360.17  4830.6  359.42  4840.1  359.17  4845.6  359.56
  4852.3  358.44  4909.5  358.44  4917.8  358.19  5026.9  358.24  5040.9  358.06
  5041.2  357.56  5044.7  357.56  5044.9  358.06  5057.3  358.39  5143.1  358.40
  5153.6  358.12  5174.5  358.46  5254.4  358.40  5259.2  358.33  5265.1  358.74
  5280.4  358.27  5305.3  358.90  5316.8  359.24  5322.7  359.88  5338.0  360.39
#Mann=7,-1,0
  4765.8    0.05       0  4819.4   0.033       0  5026.9    0.05       0
  5040.9   0.033       0  5044.9    0.05       0  5254.4   0.063       0
  5305.3    0.05       0
Bank Sta=5040.9,5044.9
Exp/Cntr=0.3,0.1

Type RM Length L Ch R = 1,1218,70,70,70
BEGIN DESCRIPTION:
Mapping XS 3c4c42c2
END DESCRIPTION:
XS GIS Cut Line= 6
      2712057.18      6814212.70      2711979.46      6814234.74
      2711885.33      6814212.02      2711801.14      6814237.15
      2711745.77      6814327.88      2711694.14      6814546.76
#Sta/Elev= 30
  4732.9  362.80  4747.4  362.51  4766.2  361.17  4827.9  358.35  4836.8  358.85
  4975.0  358.71  5014.8  358.26  5045.4  358.77  5051.0  355.66  5068.2  356.42
  5073.7  353.14  5090.6  354.23  5096.5  355.29  5100.0  352.39  5100.3  351.89
  5103.8  351.89  5104.0  352.39  5113.4  352.76  5130.3  354.74  5135.4  353.13
  5141.5  353.51  5173.7  355.60  5180.8  356.69  5185.9  355.17  5194.1  356.29
  5231.2  358.79  5236.3  357.84  5275.7  358.99  5313.4  358.63  5334.5  359.46
#Mann=6,-1,0
  4732.9    0.05       0  4766.2   0.033       0  4975.0    0.05       0
  5100.0    0.05       0  5104.0    0.05       0  5141.5   0.063       0
Bank Sta=5100,5104
Exp/Cntr=0.3,0.1

Type RM Length L Ch R = 1,1148,101,101,101
BEGIN DESCRIPTION:
Twin Creek2441173.54
END DESCRIPTION:
XS GIS Cut Line= 4
      2711749.70      6813995.73      2711746.00      6814240.81
      2711735.42      6814338.46      2711703.16      6814503.31
#Sta/Elev= 30
  4754.9  355.46  4780.2  354.29  4790.2  353.52  4800.2  353.72  4850.2  350.88
  4860.2  350.82  4900.2  349.50  4928.2  349.01  4928.4  348.51  4931.9  348.51
  4932.2  349.01  4950.2  349.02  5002.6  349.88  5010.3  350.54  5040.4  350.22
  5046.3  350.59  5070.6  350.78  5090.7  351.66  5097.0  352.49  5102.1  352.49
  5118.7  353.60  5123.8  352.67  5141.6  354.12  5162.0  355.17  5170.2  356.29
  5175.3  355.91  5221.7  358.13  5226.8  357.57  5253.7  358.63  5266.2  358.77
#Mann=4,-1,0
  4754.9    0.05       0  4928.2    0.05       0  4932.2    0.05       0
  5046.3   0.063       0
Bank Sta=4928.2,4932.2
Exp/Cntr=0.3,0.1

Type RM Length L Ch R = 1,1047,189,189,189
BEGIN DESCRIPTION:
Twin Creek2441046.62
END DESCRIPTION:
XS GIS Cut Line= 4
      2711669.60      6813962.61      2711668.35      6814209.34
      2711660.02      6814284.48      2711630.76      6814462.97
#Sta/Elev= 30
  4758.9  354.77  4797.3  352.88  4887.3  349.32  4907.3  347.55  4917.3  347.18
  4925.3  347.10  4925.5  346.60  4929.0  346.60  4929.3  347.10  4937.3  347.40
  4967.3  347.56  4987.3  348.28  4997.3  349.88  5004.0  350.72  5027.4  350.99
  5067.5  351.94  5072.5  352.42  5077.0  352.59  5087.8  352.79  5128.4  354.15
  5168.9  356.09  5179.0  356.75  5189.2  357.11  5196.5  357.59  5201.6  357.66
  5210.9  358.60  5229.7  359.59  5250.0  360.11  5257.8  360.53  5262.1  361.00
#Mann=4,-1,0
  4758.9   0.063       0  4925.3   0.063       0  4929.3   0.063       0
  5210.9    0.05       0
Bank Sta=4925.3,4929.3
Exp/Cntr=0.3,0.1

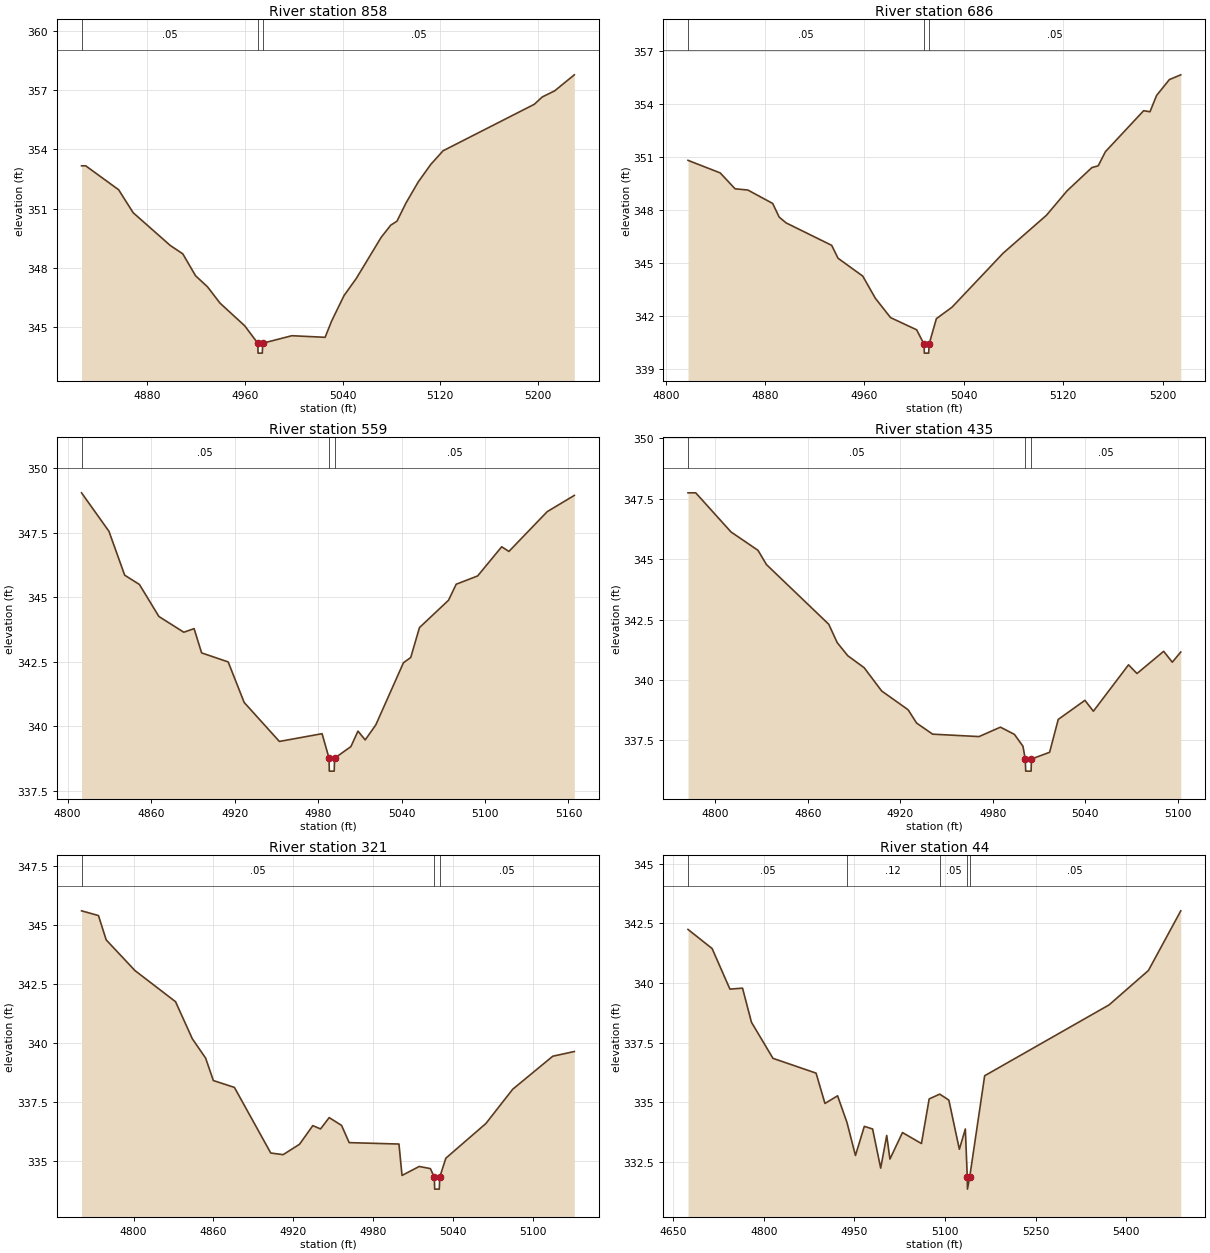
Type RM Length L Ch R = 1,858,172,172,172
BEGIN DESCRIPTION:
Twin Creek244858.47
END DESCRIPTION:
XS GIS Cut Line= 3
      2711567.15      6813899.39      2711535.26      6814071.86
      2711494.96      6814296.89
#Sta/Elev= 30
  4826.0  353.16  4829.4  353.16  4856.4  351.95  4868.3  350.79  4898.8  349.13
  4909.0  348.71  4919.5  347.60  4929.3  347.04  4939.5  346.22  4959.8  345.07
  4970.5  344.19  4970.7  343.69  4974.2  343.69  4974.5  344.19  4998.4  344.57
  5025.7  344.49  5031.0  345.31  5041.2  346.60  5051.3  347.47  5071.6  349.54
  5079.5  350.16  5084.6  350.36  5091.9  351.27  5102.1  352.35  5112.3  353.23
  5122.4  353.92  5197.2  356.27  5203.7  356.64  5213.9  356.95  5230.0  357.76
#Mann=3,-1,0
  4826.0    0.05       0  4970.5    0.05       0  4974.5    0.05       0
Bank Sta=4970.5,4974.5
Exp/Cntr=0.3,0.1

Type RM Length L Ch R = 1,686,127,127,127
BEGIN DESCRIPTION:
Twin Creek244685.88
END DESCRIPTION:
XS GIS Cut Line= 3
      2711447.76      6813784.10      2711405.43      6813963.25
      2711355.11      6814169.93
#Sta/Elev= 30
  4817.9  350.79  4843.8  350.08  4855.8  349.18  4866.1  349.11  4886.1  348.35
  4891.3  347.58  4896.9  347.25  4933.6  345.98  4938.7  345.25  4958.6  344.24
  4968.8  342.98  4981.0  341.89  5002.0  341.20  5008.0  340.38  5008.2  339.88
  5011.7  339.88  5012.0  340.38  5017.9  341.83  5030.5  342.48  5071.7  345.54
  5106.5  347.68  5123.2  349.07  5143.1  350.38  5148.2  350.48  5154.0  351.28
  5184.8  353.60  5189.9  353.54  5195.2  354.46  5205.5  355.36  5214.7  355.63
#Mann=3,-1,0
  4817.9    0.05       0  5008.0    0.05       0  5012.0    0.05       0
Bank Sta=5008,5012
Exp/Cntr=0.3,0.1

Type RM Length L Ch R = 1,559,124,124,124
BEGIN DESCRIPTION:
Twin Creek244558.99
END DESCRIPTION:
XS GIS Cut Line= 3
      2711359.27      6813731.86      2711293.35      6813913.93
      2711246.10      6814067.39
#Sta/Elev= 30
  4810.0  349.04  4829.7  347.55  4841.0  345.85  4851.6  345.49  4865.6  344.25
  4883.5  343.64  4890.9  343.78  4896.3  342.84  4915.4  342.49  4926.9  340.92
  4952.2  339.41  4982.9  339.71  4987.9  338.76  4988.1  338.26  4991.6  338.26
  4991.9  338.76  5003.6  339.21  5008.7  339.81  5013.9  339.47  5021.5  340.05
  5041.4  342.46  5046.6  342.66  5052.9  343.82  5073.8  344.88  5079.3  345.50
  5094.7  345.82  5112.0  346.95  5117.2  346.77  5144.7  348.31  5164.2  348.94
#Mann=3,-1,0
  4810.0    0.05       0  4987.9    0.05       0  4991.9    0.05       0
Bank Sta=4987.9,4991.9
Exp/Cntr=0.3,0.1

Type RM Length L Ch R = 1,435,114,114,114
BEGIN DESCRIPTION:
Twin Creek244435.11
END DESCRIPTION:
XS GIS Cut Line= 3
      2711290.86      6813636.81      2711198.03      6813839.01
      2711156.79      6813927.04
#Sta/Elev= 30
  4782.3  347.75  4787.3  347.75  4810.2  346.13  4827.7  345.37  4833.2  344.78
  4873.6  342.31  4879.1  341.55  4885.9  341.01  4896.6  340.51  4907.9  339.55
  4925.1  338.77  4930.6  338.22  4941.0  337.76  4971.1  337.66  4985.0  338.05
  4994.1  337.75  4999.6  337.26  5001.1  336.73  5001.4  336.23  5004.9  336.23
  5005.1  336.73  5016.9  337.01  5022.5  338.37  5039.8  339.16  5045.3  338.71
  5068.1  340.63  5073.6  340.27  5090.9  341.19  5096.5  340.74  5102.0  341.16
#Mann=3,-1,0
  4782.3    0.05       0  5001.1    0.05       0  5005.1    0.05       0
Bank Sta=5001.1,5005.1
Exp/Cntr=0.3,0.1

Type RM Length L Ch R = 1,321,277,277,277
BEGIN DESCRIPTION:
Twin Creek244321.34
END DESCRIPTION:
XS GIS Cut Line= 3
      2711220.13      6813579.77      2711099.18      6813789.99
      2711109.37      6813917.15
#Sta/Elev= 30
  4760.9  345.59  4773.6  345.39  4779.4  344.36  4801.0  343.06  4831.5  341.74
  4844.1  340.17  4854.1  339.35  4859.9  338.40  4875.7  338.11  4903.0  335.33
  4912.3  335.26  4924.6  335.70  4934.6  336.49  4940.4  336.35  4946.9  336.83
  4956.2  336.50  4961.9  335.77  4999.3  335.71  5001.6  334.38  5014.5  334.76
  5022.9  334.67  5025.9  334.30  5026.1  333.80  5029.6  333.80  5029.9  334.30
  5034.5  335.11  5064.6  336.58  5084.7  338.03  5114.8  339.43  5131.0  339.63
#Mann=3,-1,0
  4760.9    0.05       0  5025.9    0.05       0  5029.9    0.05       0
Bank Sta=5025.9,5029.9
Exp/Cntr=0.3,0.1

Type RM Length L Ch R = 1,44,0,0,0
BEGIN DESCRIPTION:
Twin Creek24444.027
END DESCRIPTION:
XS GIS Cut Line= 3
      2711235.13      6813374.02      2710969.87      6813562.67
      2711115.71      6814031.09
#Sta/Elev= 30
  4674.5  342.25  4714.4  341.45  4743.9  339.75  4764.8  339.79  4779.6  338.36
  4815.2  336.85  4886.6  336.23  4901.3  334.96  4922.2  335.28  4937.8  334.16
  4951.8  332.78  4966.5  334.00  4980.2  333.89  4993.6  332.25  5003.6  333.62
  5008.9  332.63  5029.7  333.74  5061.1  333.28  5073.9  335.15  5091.4  335.35
  5106.5  335.10  5123.9  333.04  5133.8  333.89  5137.0  331.87  5137.3  331.37
  5141.0  331.87  5165.8  336.12  5371.9  339.09  5437.0  340.53  5490.6  343.03
#Mann=5,-1,0
  4674.5    0.05       0  4937.8    0.12       0  5091.4    0.05       0
  5137.0    0.07       0  5141.0    0.05       0
Bank Sta=5137,5141
Exp/Cntr=0.3,0.1

Chan Stop Cuts=-1