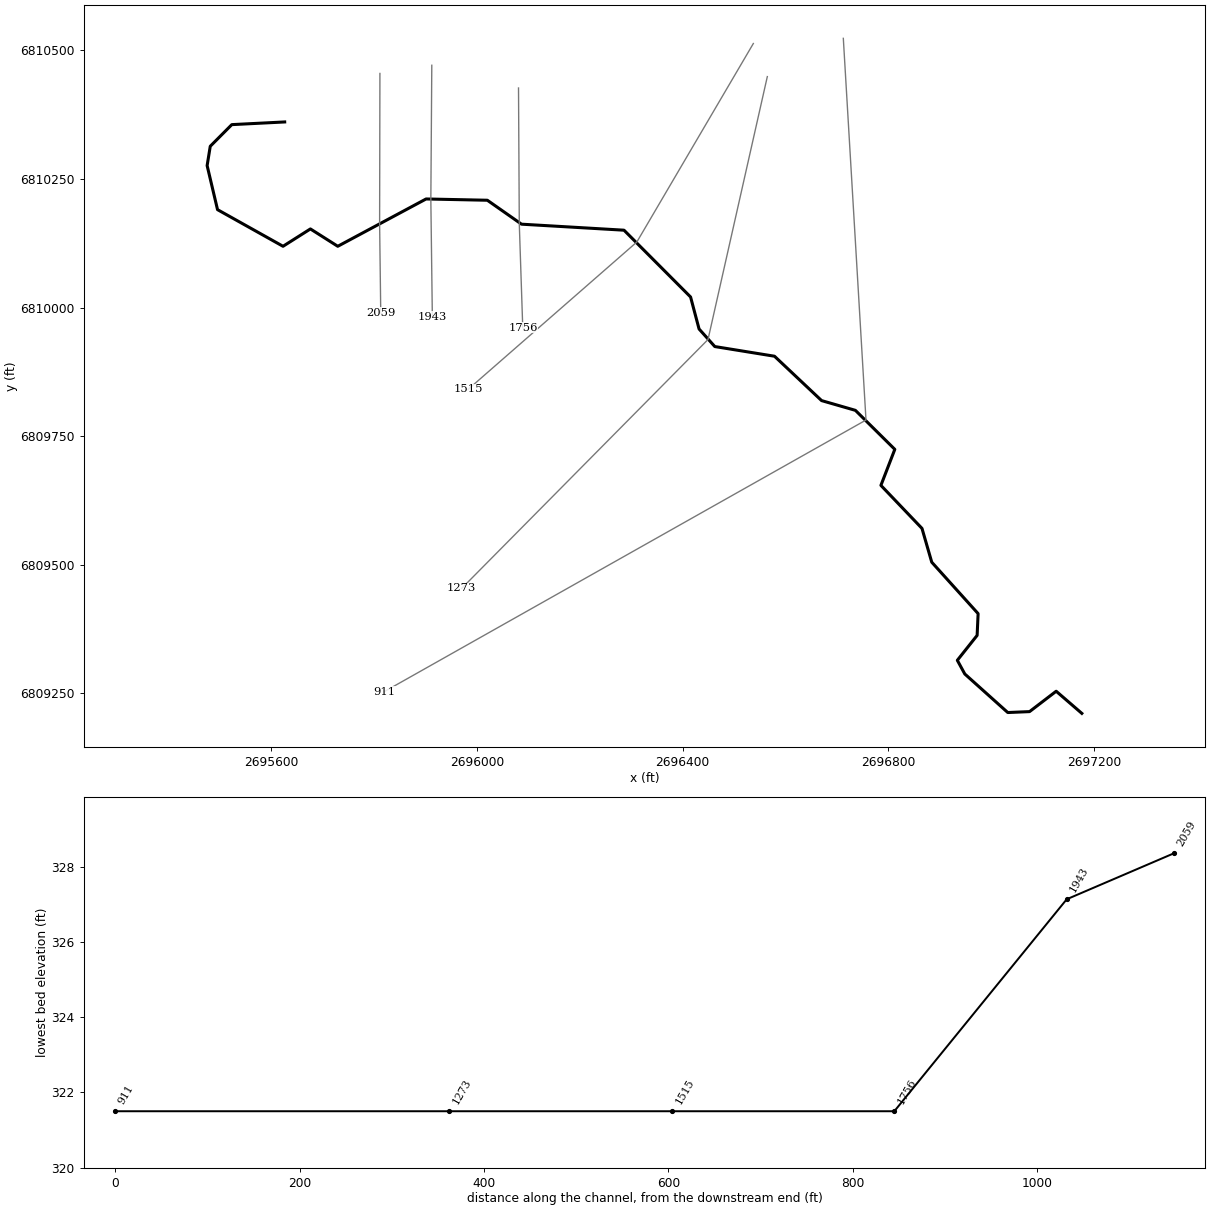
--- Twin Creek246.prj (project) ---

Proj Title=Twin Creek246 Base Level Engineering
Current Plan=p01
Default Exp/Contr=0.3,0.1
English Units
Geom File=g01
Flow File=f01
Plan File=p01
BEGIN DESCRIPTION:
Twin Creek246
END DESCRIPTION:

--- Twin Creek246.p01 (plan) ---

Plan Title=Multiple Run
Short Identifier=Multiple
Geom File=g01
Flow File=f01
Subcritical Flow
K Sum by GR= 0
Std Step Tol= 0.01
Critical Tol= 0.01
Num of Std Step Trials= 20
Max Error Tol= 0.3
Flow Tol Ratio= 0.001
Split Flow NTrial= 30
Split Flow Tol= 0.02
Split Flow Ratio= 0.02
Log Output Level= 0
Friction Slope Method= 1
Unsteady Friction Slope Method= 2
Unsteady Bridges Friction Slope Method= 1
Parabolic Critical Depth
Global Vel Dist=  1 , 1 , 1
Global Log Level= 0
CheckData=True
Encroach Param= -1, 0, 0, 0
BEGIN DESCRIPTION:
Multiple Run
END DESCRIPTION:

--- Twin Creek246.f01 (steady flow) ---

Flow Title=Multiple
Number of Profiles=7
Profile Names=10-year,25-year,50-year,1pct_min,100-year,1pct_plu,500-year
River Rch & RM= Twin Creek246,Reach-1,2059
     228     288     334     193     385     767     508
Boundary for River Rch & Prof#=Twin Creek246,Reach-1,1
Up Type=0
Dn Type=3
Dn Slope=0.005
Boundary for River Rch & Prof#=Twin Creek246,Reach-1,2
Up Type=0
Dn Type=3
Dn Slope=0.005
Boundary for River Rch & Prof#=Twin Creek246,Reach-1,3
Up Type=0
Dn Type=3
Dn Slope=0.005
Boundary for River Rch & Prof#=Twin Creek246,Reach-1,4
Up Type=0
Dn Type=3
Dn Slope=0.005
Boundary for River Rch & Prof#=Twin Creek246,Reach-1,5
Up Type=0
Dn Type=3
Dn Slope=0.005
Boundary for River Rch & Prof#=Twin Creek246,Reach-1,6
Up Type=0
Dn Type=3
Dn Slope=0.005
Boundary for River Rch & Prof#=Twin Creek246,Reach-1,7
Up Type=0
Dn Type=3
Dn Slope=0.005

--- Twin Creek246.g01 (geometry) ---

Geom Title=Existing Conditions

River Reach=Twin Creek246,Reach-1
Reach XY= 30
      2695626.00      6810361.00      2695523.17      6810355.79
      2695481.26      6810313.70      2695475.18      6810276.12
      2695495.42      6810190.45      2695622.77      6810119.23
      2695676.00      6810152.97      2695729.23      6810119.23
      2695900.92      6810211.24      2696020.06      6810208.75
      2696086.51      6810162.22      2696285.80      6810150.52
      2696415.21      6810020.66      2696431.74      6809958.43
      2696462.35      6809924.26      2696578.42      6809905.46
      2696669.96      6809819.18      2696735.72      6809800.22
      2696812.36      6809724.36      2696785.32      6809654.34
      2696865.18      6809570.68      2696884.18      6809504.96
      2696974.33      6809404.95      2696972.41      6809362.65
      2696933.91      6809314.22      2696948.44      6809287.58
      2697032.02      6809212.64      2697074.36      6809214.43
      2697126.12      6809254.05      2697176.00      6809211.00

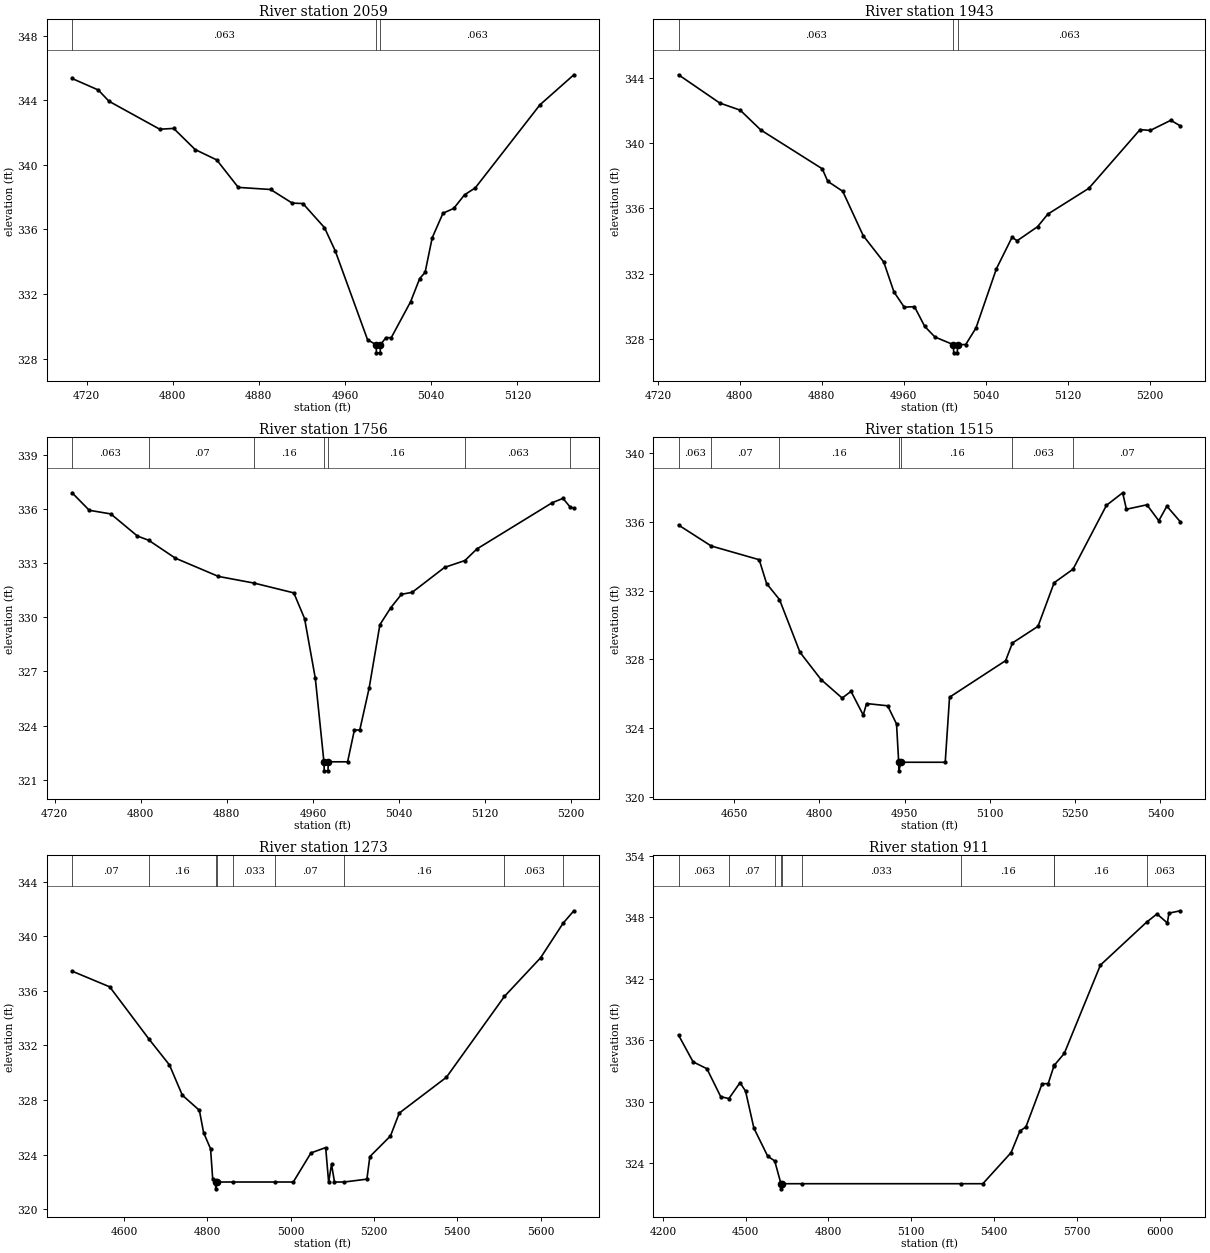
Type RM Length L Ch R = 1,2059,116,116,116
BEGIN DESCRIPTION:
Twin Creek2462222.28
END DESCRIPTION:
XS GIS Cut Line= 3
      2695811.17      6810455.29      2695810.58      6810161.89
      2695812.79      6809989.51
#Sta/Elev= 30
  4706.6  345.34  4730.9  344.63  4740.9  343.93  4788.0  342.20  4800.9  342.25
  4820.9  340.94  4840.9  340.30  4860.9  338.60  4890.9  338.47  4910.9  337.63
  4920.9  337.60  4940.9  336.11  4950.9  334.67  4980.9  329.17  4988.9  328.86
  4989.1  328.36  4992.6  328.36  4992.9  328.86  4997.9  329.30  5002.9  329.30
  5020.9  331.53  5029.3  332.96  5034.3  333.34  5040.9  335.48  5050.9  337.00
  5060.9  337.30  5070.9  338.14  5080.9  338.57  5140.9  343.71  5172.4  345.57
#Mann=3,-1,0
  4706.6   0.063       0  4988.9   0.063       0  4992.9   0.063       0
Bank Sta=4988.9,4992.9
Exp/Cntr=0.3,0.1

Type RM Length L Ch R = 1,1943,187,187,187
BEGIN DESCRIPTION:
Twin Creek2461943.46
END DESCRIPTION:
XS GIS Cut Line= 3
      2695912.04      6810471.24      2695910.18      6810210.14
      2695913.10      6809981.66
#Sta/Elev= 30
  4740.2  344.18  4780.4  342.45  4800.4  342.01  4820.4  340.80  4880.4  338.42
  4885.8  337.65  4900.4  337.04  4920.4  334.32  4940.4  332.71  4950.4  330.87
  4960.4  329.94  4970.4  329.97  4980.4  328.76  4990.4  328.11  5008.4  327.64
  5008.7  327.14  5012.2  327.14  5012.4  327.64  5020.4  327.65  5030.4  328.66
  5050.4  332.30  5065.6  334.22  5070.6  334.01  5090.5  334.87  5100.5  335.64
  5140.5  337.22  5190.5  340.82  5200.5  340.77  5220.5  341.39  5229.8  341.05
#Mann=3,-1,0
  4740.2   0.063       0  5008.4   0.063       0  5012.4   0.063       0
Bank Sta=5008.4,5012.4
Exp/Cntr=0.3,0.1

Type RM Length L Ch R = 1,1756,241,241,241
BEGIN DESCRIPTION:
Twin Creek2461755.53
END DESCRIPTION:
XS GIS Cut Line= 3
      2696080.66      6810427.01      2696082.16      6810163.34
      2696088.90      6809960.92
#Sta/Elev= 30
  4736.2  336.89  4752.2  335.92  4772.2  335.72  4796.8  334.50  4807.4  334.26
  4832.2  333.27  4872.2  332.26  4905.4  331.89  4942.2  331.35  4952.2  329.93
  4962.2  326.62  4970.2  322.00  4970.5  321.50  4974.0  321.50  4974.2  322.00
  4992.2  322.00  4998.5  323.76  5003.5  323.76  5012.2  326.08  5022.2  329.59
  5032.2  330.52  5042.2  331.27  5052.2  331.38  5082.3  332.76  5101.2  333.14
  5112.3  333.78  5182.3  336.34  5192.3  336.58  5199.1  336.09  5202.4  336.03
#Mann=7,-1,0
  4736.2   0.063       0  4807.4    0.07       0  4905.4    0.16       0
  4970.2    0.07       0  4974.2    0.16       0  5101.2   0.063       0
  5199.1    0.07       0
Bank Sta=4970.2,4974.2
Exp/Cntr=0.3,0.1

Type RM Length L Ch R = 1,1515,242,242,242
BEGIN DESCRIPTION:
Twin Creek2461515.36
END DESCRIPTION:
XS GIS Cut Line= 3
      2696537.26      6810513.49      2696310.69      6810127.47
      2695982.64      6809840.90
#Sta/Elev= 30
  4552.0  335.82  4609.5  334.60  4694.0  333.80  4707.0  332.41  4729.7  331.48
  4765.7  328.41  4802.8  326.82  4840.0  325.74  4855.6  326.13  4877.1  324.75
  4882.9  325.42  4920.1  325.29  4935.7  324.23  4939.5  322.00  4939.8  321.50
  4943.5  322.00  5021.4  322.00  5029.0  325.79  5127.7  327.92  5139.7  328.95
  5184.7  329.92  5213.1  332.46  5246.4  333.25  5305.2  336.97  5333.7  337.70
  5340.3  336.74  5376.4  337.00  5397.3  336.07  5411.5  336.92  5435.2  336.01
#Mann=7,-1,0
  4552.0   0.063       0  4609.5    0.07       0  4729.7    0.16       0
  4939.5    0.07       0  4943.5    0.16       0  5139.7   0.063       0
  5246.4    0.07       0
Bank Sta=4939.5,4943.5
Exp/Cntr=0.3,0.1

Type RM Length L Ch R = 1,1273,362,362,362
BEGIN DESCRIPTION:
Twin Creek2461273.43
END DESCRIPTION:
XS GIS Cut Line= 3
      2696564.46      6810449.19      2696449.11      6809937.92
      2695970.14      6809454.00
#Sta/Elev= 30
  4475.1  337.44  4565.5  336.29  4660.4  332.44  4709.0  330.57  4739.8  328.36
  4780.8  327.25  4791.0  325.61  4807.7  324.43  4812.8  322.22  4819.8  322.00
  4820.0  321.50  4823.8  322.00  4862.3  322.00  4963.2  322.00  5006.3  322.00
  5048.8  324.13  5084.1  324.52  5091.2  322.00  5098.2  323.29  5105.3  322.00
  5128.6  322.00  5183.1  322.21  5190.2  323.86  5239.7  325.37  5260.9  327.05
  5374.1  329.67  5513.4  335.59  5600.3  338.42  5654.5  340.96  5680.1  341.86
#Mann=9,-1,0
  4475.1    0.07       0  4660.4    0.16       0  4819.8    0.07       0
  4823.8    0.16       0  4862.3   0.033       0  4963.2    0.07       0
  5128.6    0.16       0  5513.4   0.063       0  5654.5    0.16       0
Bank Sta=4819.8,4823.8
Exp/Cntr=0.3,0.1

Type RM Length L Ch R = 1,911,0,0,0
BEGIN DESCRIPTION:
Twin Creek246910.552
END DESCRIPTION:
XS GIS Cut Line= 3
      2696712.22      6810523.58      2696756.32      6809781.38
      2695819.56      6809253.21
#Sta/Elev= 30
  4256.5  336.50  4309.2  333.89  4359.3  333.22  4409.5  330.49  4439.1  330.31
  4479.5  331.86  4499.5  331.03  4529.6  327.43  4579.6  324.69  4605.2  324.22
  4627.7  322.00  4628.0  321.50  4631.7  322.00  4703.1  322.00  5281.0  322.00
  5359.5  322.00  5462.1  325.04  5493.9  327.14  5515.6  327.54  5574.4  331.75
  5596.5  331.77  5617.3  333.49  5618.4  333.55  5654.7  334.71  5785.7  343.33
  5953.6  347.53  5990.8  348.32  6028.4  347.44  6034.2  348.40  6075.4  348.63
#Mann=10,-1,0
  4256.5   0.063       0  4439.1    0.07       0  4605.2    0.16       0
  4627.7   0.033       0  4631.7    0.16       0  4703.1   0.033       0
  5281.0    0.16       0  5617.3   0.063       0  5618.4    0.16       0
  5953.6   0.063       0
Bank Sta=4627.7,4631.7
Exp/Cntr=0.3,0.1

Chan Stop Cuts=-1