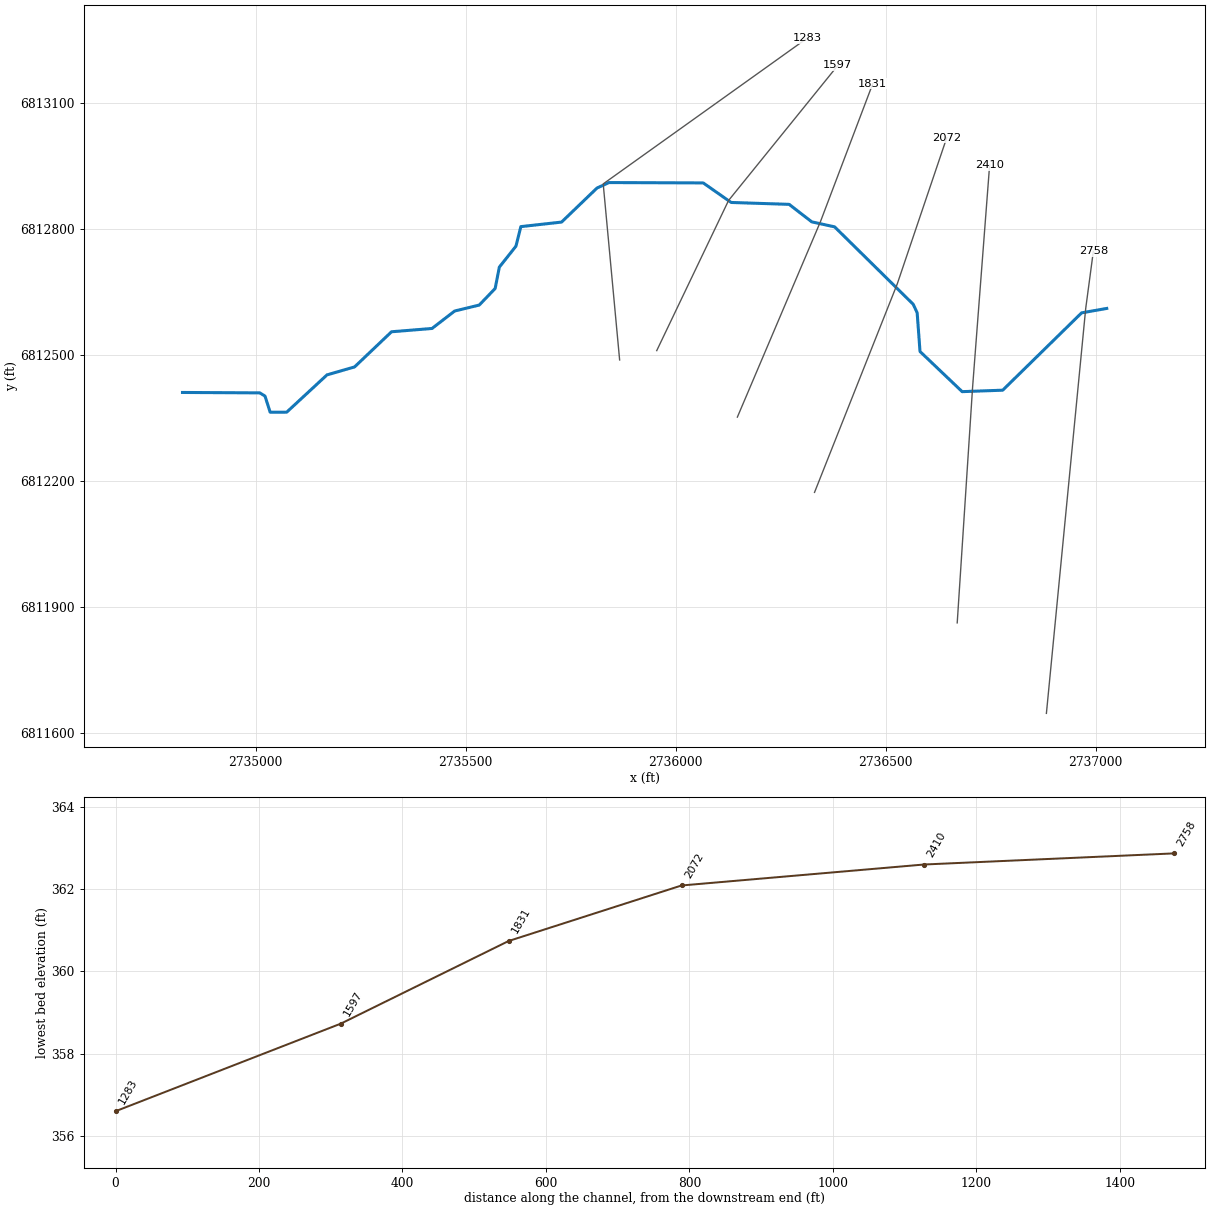
--- Twin Creek249.prj (project) ---

Proj Title=Twin Creek249 Base Level Engineering
Current Plan=p01
Default Exp/Contr=0.3,0.1
English Units
Geom File=g01
Flow File=f01
Plan File=p01
BEGIN DESCRIPTION:
Twin Creek249
END DESCRIPTION:

--- Twin Creek249.p01 (plan) ---

Plan Title=Multiple Run
Short Identifier=Multiple
Geom File=g01
Flow File=f01
Subcritical Flow
K Sum by GR= 0
Std Step Tol= 0.01
Critical Tol= 0.01
Num of Std Step Trials= 20
Max Error Tol= 0.3
Flow Tol Ratio= 0.001
Split Flow NTrial= 30
Split Flow Tol= 0.02
Split Flow Ratio= 0.02
Log Output Level= 0
Friction Slope Method= 1
Unsteady Friction Slope Method= 2
Unsteady Bridges Friction Slope Method= 1
Parabolic Critical Depth
Global Vel Dist=  1 , 1 , 1
Global Log Level= 0
CheckData=True
Encroach Param= -1, 0, 0, 0
BEGIN DESCRIPTION:
Multiple Run
END DESCRIPTION:

--- Twin Creek249.f01 (steady flow) ---

Flow Title=Multiple
Number of Profiles=7
Profile Names=10-year,25-year,50-year,1pct_min,100-year,1pct_plu,500-year
River Rch & RM= Twin Creek249,Reach-1,2758
     147     177     200     112     224     447     280
Boundary for River Rch & Prof#=Twin Creek249,Reach-1,1
Up Type=0
Dn Type=3
Dn Slope=0.005
Boundary for River Rch & Prof#=Twin Creek249,Reach-1,2
Up Type=0
Dn Type=3
Dn Slope=0.005
Boundary for River Rch & Prof#=Twin Creek249,Reach-1,3
Up Type=0
Dn Type=3
Dn Slope=0.005
Boundary for River Rch & Prof#=Twin Creek249,Reach-1,4
Up Type=0
Dn Type=3
Dn Slope=0.005
Boundary for River Rch & Prof#=Twin Creek249,Reach-1,5
Up Type=0
Dn Type=3
Dn Slope=0.005
Boundary for River Rch & Prof#=Twin Creek249,Reach-1,6
Up Type=0
Dn Type=3
Dn Slope=0.005
Boundary for River Rch & Prof#=Twin Creek249,Reach-1,7
Up Type=0
Dn Type=3
Dn Slope=0.005

--- Twin Creek249.g01 (geometry) ---

Geom Title=Existing Conditions

River Reach=Twin Creek249,Reach-1
Reach XY= 30
      2737026.00      6812611.00      2736966.21      6812600.48
      2736778.43      6812416.40      2736681.88      6812412.95
      2736581.52      6812508.56      2736574.83      6812600.52
      2736565.48      6812620.79      2736378.30      6812805.17
      2736323.83      6812817.14      2736270.07      6812858.75
      2736131.94      6812863.27      2736065.50      6812909.78
      2735841.16      6812910.61      2735812.69      6812897.60
      2735728.36      6812816.56      2735631.44      6812805.75
      2735619.74      6812759.20      2735580.19      6812709.27
      2735570.27      6812658.46      2735532.34      6812619.02
      2735473.85      6812604.85      2735420.03      6812563.33
      2735323.58      6812555.46      2735235.67      6812471.80
      2735169.96      6812452.82      2735074.02      6812364.04
      2735034.66      6812363.98      2735022.46      6812402.32
      2735010.07      6812410.01      2734826.00      6812411.00

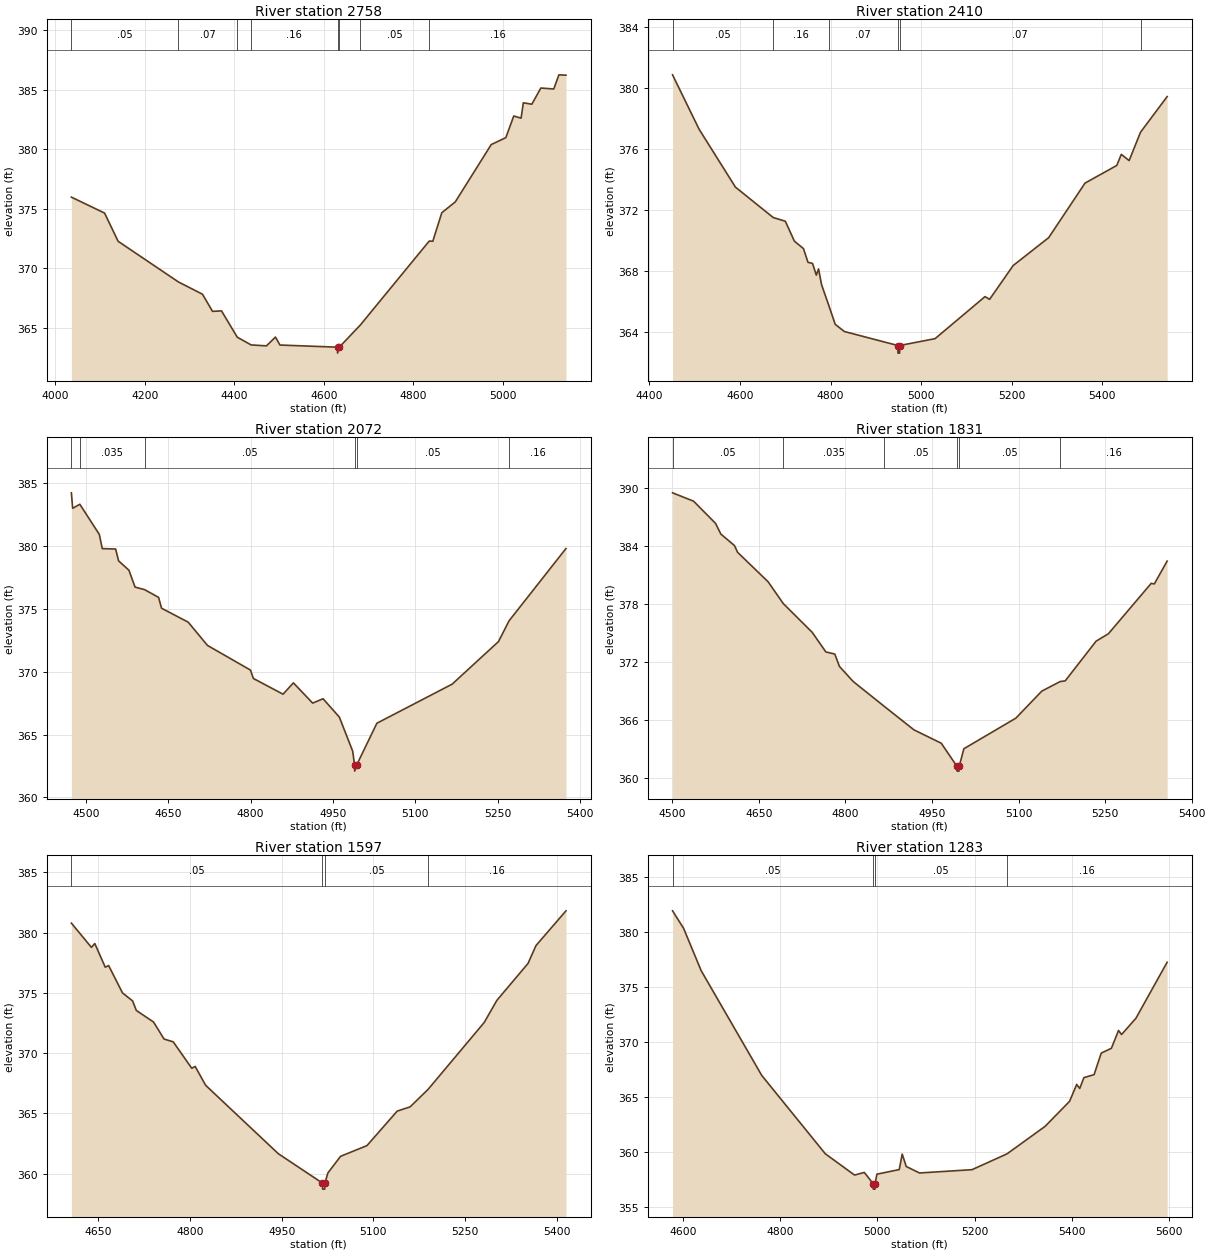
Type RM Length L Ch R = 1,2758,348,348,348
BEGIN DESCRIPTION:
Twin Creek2492757.832
END DESCRIPTION:
XS GIS Cut Line= 3
      2736882.42      6811647.11      2736976.00      6812611.00
      2736994.13      6812746.68
#Sta/Elev= 30
  4035.8  375.98  4110.0  374.64  4140.2  372.27  4275.1  368.85  4328.8  367.82
  4351.2  366.38  4371.3  366.42  4406.5  364.21  4437.4  363.56  4471.7  363.48
  4491.8  364.22  4501.9  363.55  4630.5  363.37  4630.7  362.87  4634.5  363.37
  4681.7  365.24  4835.5  372.29  4843.5  372.27  4863.6  374.67  4893.7  375.58
  4974.1  380.40  5006.7  380.98  5024.4  382.80  5040.8  382.62  5045.8  383.91
  5064.8  383.79  5084.9  385.15  5113.8  385.07  5125.3  386.26  5141.1  386.23
#Mann=8,-1,0
  4035.8    0.05       0  4275.1    0.07       0  4406.5    0.05       0
  4437.4    0.16       0  4630.5    0.07       0  4634.5    0.16       0
  4681.7    0.05       0  4835.5    0.16       0
Bank Sta=4630.5,4634.5
Exp/Cntr=0.3,0.1

Type RM Length L Ch R = 1,2410,338,338,338
BEGIN DESCRIPTION:
Twin Creek2492409.87
END DESCRIPTION:
XS GIS Cut Line= 3
      2736670.11      6811862.52      2736706.80      6812424.49
      2736747.24      6812951.88
#Sta/Elev= 30
  4451.0  380.87  4509.6  377.30  4589.8  373.50  4673.4  371.50  4700.0  371.26
  4720.1  369.95  4740.1  369.46  4750.1  368.56  4760.1  368.49  4768.4  367.72
  4773.4  368.13  4780.2  367.08  4795.8  365.75  4810.2  364.49  4830.3  364.02
  4948.5  363.10  4948.8  362.60  4952.3  362.60  4952.5  363.10  5030.7  363.55
  5141.0  366.31  5151.1  366.13  5203.1  368.35  5281.5  370.18  5361.7  373.76
  5431.9  374.92  5441.9  375.65  5459.2  375.24  5484.3  377.10  5543.1  379.44
#Mann=6,-1,0
  4451.0    0.05       0  4673.4    0.16       0  4795.8    0.07       0
  4948.5    0.07       0  4952.5    0.07       0  5484.3    0.16       0
Bank Sta=4948.5,4952.5
Exp/Cntr=0.3,0.1

Type RM Length L Ch R = 1,2072,241,241,241
BEGIN DESCRIPTION:
Twin Creek2492072.11
END DESCRIPTION:
XS GIS Cut Line= 3
      2736330.47      6812173.16      2736527.49      6812669.62
      2736645.21      6813017.41
#Sta/Elev= 30
  4473.4  384.23  4475.7  383.00  4488.8  383.32  4524.3  380.92  4529.7  379.79
  4554.0  379.76  4559.4  378.82  4578.3  378.07  4589.4  376.73  4606.7  376.53
  4632.3  375.91  4637.7  375.05  4686.3  373.94  4721.4  372.09  4799.7  370.13
  4805.1  369.46  4859.1  368.21  4878.0  369.11  4913.1  367.50  4932.0  367.85
  4961.7  366.39  4986.0  363.68  4989.4  362.59  4989.6  362.09  4993.4  362.59
  5030.1  365.90  5167.3  369.01  5251.8  372.40  5271.0  374.05  5374.7  379.80
#Mann=6,-1,0
  4473.4    0.05       0  4488.8   0.035       0  4606.7    0.05       0
  4989.4    0.05       0  4993.4    0.05       0  5271.0    0.16       0
Bank Sta=4989.4,4993.4
Exp/Cntr=0.3,0.1

Type RM Length L Ch R = 1,1831,234,234,234
BEGIN DESCRIPTION:
Twin Creek2491830.52
END DESCRIPTION:
XS GIS Cut Line= 3
      2736146.82      6812352.32      2736344.61      6812817.69
      2736469.13      6813146.12
#Sta/Elev= 30
  4500.6  389.48  4537.0  388.62  4575.2  386.32  4584.3  385.22  4607.8  384.04
  4613.4  383.33  4666.1  380.30  4692.5  378.04  4742.5  375.08  4766.2  373.05
  4781.7  372.83  4789.8  371.55  4813.5  370.00  4867.6  367.42  4918.9  365.00
  4966.2  363.62  4993.3  361.24  4993.5  360.74  4997.0  360.74  4997.3  361.24
  5005.3  363.05  5095.4  366.21  5140.3  369.00  5172.1  369.99  5180.9  370.06
  5234.4  374.16  5255.8  374.93  5329.9  380.13  5335.3  380.07  5357.5  382.43
#Mann=6,-1,0
  4500.6    0.05       0  4692.5   0.035       0  4867.6    0.05       0
  4993.3    0.05       0  4997.3    0.05       0  5172.1    0.16       0
Bank Sta=4993.3,4997.3
Exp/Cntr=0.3,0.1

Type RM Length L Ch R = 1,1597,314,314,314
BEGIN DESCRIPTION:
Twin Creek2491596.73
END DESCRIPTION:
XS GIS Cut Line= 3
      2735954.88      6812510.59      2736125.81      6812867.93
      2736385.83      6813189.30
#Sta/Elev= 30
  4605.9  380.78  4638.7  378.77  4644.2  379.09  4661.3  377.13  4666.9  377.26
  4689.5  375.00  4706.1  374.33  4712.2  373.54  4740.4  372.58  4757.6  371.17
  4772.6  370.94  4802.9  368.75  4808.5  368.90  4825.6  367.34  4944.5  361.67
  5016.8  359.23  5017.1  358.73  5020.6  358.73  5020.8  359.23  5025.7  360.07
  5046.5  361.45  5089.7  362.34  5139.2  365.20  5160.3  365.55  5189.7  367.00
  5281.5  372.54  5302.3  374.38  5353.3  377.44  5366.3  378.92  5415.4  381.80
#Mann=4,-1,0
  4605.9    0.05       0  5016.8    0.05       0  5020.8    0.05       0
  5189.7    0.16       0
Bank Sta=5016.8,5020.8
Exp/Cntr=0.3,0.1

Type RM Length L Ch R = 1,1283,0,0,0
BEGIN DESCRIPTION:
Twin Creek2491283.473
END DESCRIPTION:
XS GIS Cut Line= 3
      2735866.56      6812488.37      2735827.47      6812907.45
      2736312.40      6813253.94
#Sta/Elev= 30
  4579.1  381.93  4601.8  380.34  4638.0  376.48  4762.5  366.95  4893.1  359.82
  4953.3  357.88  4973.4  358.12  4991.5  357.10  4991.8  356.60  4995.3  356.60
  4995.5  357.10  4999.3  357.96  5045.2  358.38  5051.3  359.79  5059.6  358.66
  5086.9  358.07  5194.8  358.37  5266.8  359.81  5345.0  362.31  5395.4  364.59
  5410.1  366.13  5416.3  365.76  5424.9  366.75  5445.8  367.02  5460.5  368.98
  5481.4  369.42  5496.1  371.04  5502.3  370.67  5531.8  372.15  5596.0  377.25
#Mann=4,-1,0
  4579.1    0.05       0  4991.5    0.05       0  4995.5    0.05       0
  5266.8    0.16       0
Bank Sta=4991.5,4995.5
Exp/Cntr=0.3,0.1

Chan Stop Cuts=-1