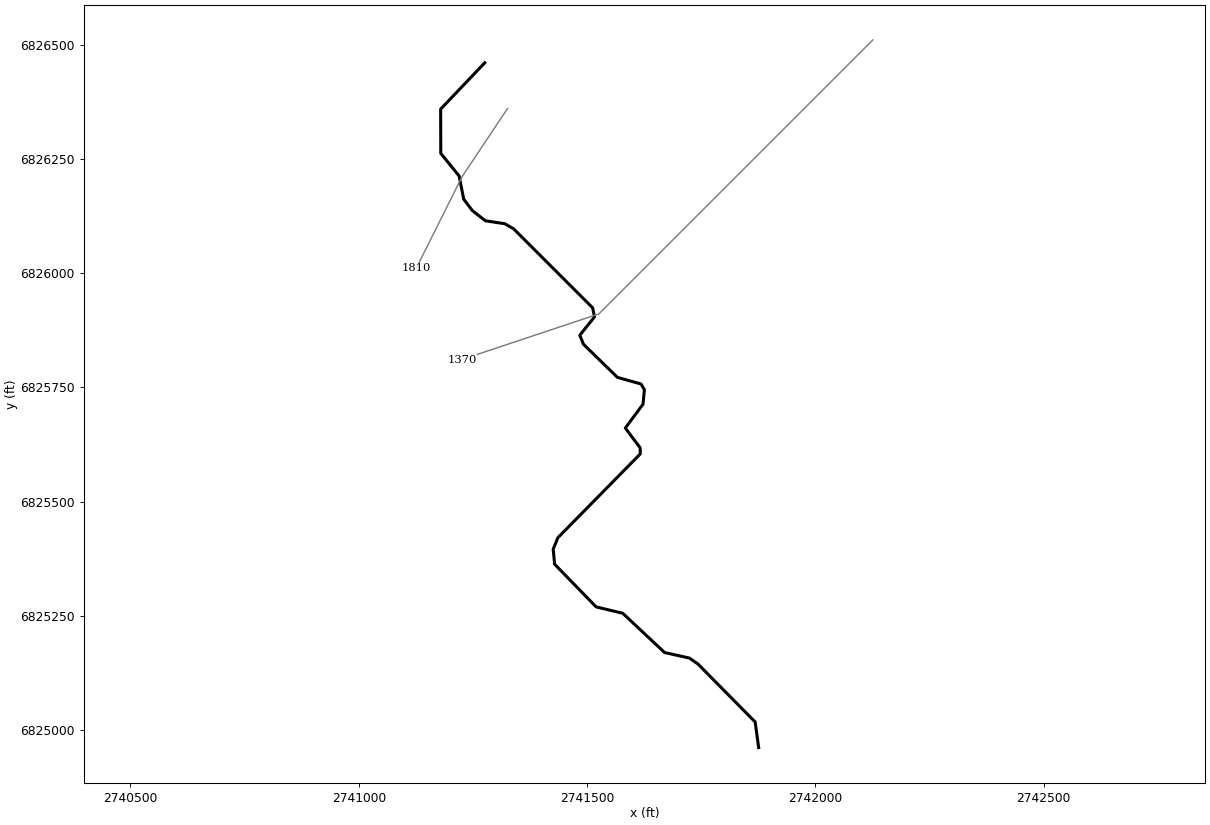
--- Twin Creek251.prj (project) ---

Proj Title=Twin Creek251 Base Level Engineering
Current Plan=p01
Default Exp/Contr=0.3,0.1
English Units
Geom File=g01
Flow File=f01
Plan File=p01
BEGIN DESCRIPTION:
Twin Creek251
END DESCRIPTION:

--- Twin Creek251.p01 (plan) ---

Plan Title=Multiple Run
Short Identifier=Multiple
Geom File=g01
Flow File=f01
Subcritical Flow
K Sum by GR= 0
Std Step Tol= 0.01
Critical Tol= 0.01
Num of Std Step Trials= 20
Max Error Tol= 0.3
Flow Tol Ratio= 0.001
Split Flow NTrial= 30
Split Flow Tol= 0.02
Split Flow Ratio= 0.02
Log Output Level= 0
Friction Slope Method= 1
Unsteady Friction Slope Method= 2
Unsteady Bridges Friction Slope Method= 1
Parabolic Critical Depth
Global Vel Dist=  1 , 1 , 1
Global Log Level= 0
CheckData=True
Encroach Param= -1, 0, 0, 0
BEGIN DESCRIPTION:
Multiple Run
END DESCRIPTION:

--- Twin Creek251.f01 (steady flow) ---

Flow Title=Multiple
Number of Profiles=7
Profile Names=10-year,25-year,50-year,1pct_min,100-year,1pct_plu,500-year
River Rch & RM= Twin Creek251,Reach-1,1810
     190     237     272     156     312     622     408
Boundary for River Rch & Prof#=Twin Creek251,Reach-1,1
Up Type=0
Dn Type=3
Dn Slope=0.005
Boundary for River Rch & Prof#=Twin Creek251,Reach-1,2
Up Type=0
Dn Type=3
Dn Slope=0.005
Boundary for River Rch & Prof#=Twin Creek251,Reach-1,3
Up Type=0
Dn Type=3
Dn Slope=0.005
Boundary for River Rch & Prof#=Twin Creek251,Reach-1,4
Up Type=0
Dn Type=3
Dn Slope=0.005
Boundary for River Rch & Prof#=Twin Creek251,Reach-1,5
Up Type=0
Dn Type=3
Dn Slope=0.005
Boundary for River Rch & Prof#=Twin Creek251,Reach-1,6
Up Type=0
Dn Type=3
Dn Slope=0.005
Boundary for River Rch & Prof#=Twin Creek251,Reach-1,7
Up Type=0
Dn Type=3
Dn Slope=0.005

--- Twin Creek251.g01 (geometry) ---

Geom Title=Existing Conditions

River Reach=Twin Creek251,Reach-1
Reach XY= 30
      2741276.00      6826461.00      2741179.40      6826359.52
      2741179.67      6826262.58      2741219.84      6826213.15
      2741229.86      6826162.42      2741248.85      6826137.16
      2741277.43      6826114.89      2741319.91      6826108.45
      2741339.20      6826097.36      2741512.35      6825924.33
      2741516.38      6825904.33      2741484.16      6825864.32
      2741492.38      6825844.30      2741566.62      6825771.89
      2741618.24      6825757.45      2741625.71      6825744.96
      2741622.59      6825713.01      2741583.85      6825660.94
      2741616.40      6825617.66      2741616.70      6825604.33
      2741436.17      6825420.68      2741425.89      6825395.64
      2741429.09      6825362.64      2741519.93      6825269.15
      2741578.28      6825255.13      2741669.96      6825169.18
      2741724.35      6825157.03      2741742.67      6825144.35
      2741868.24      6825017.21      2741876.00      6824961.00

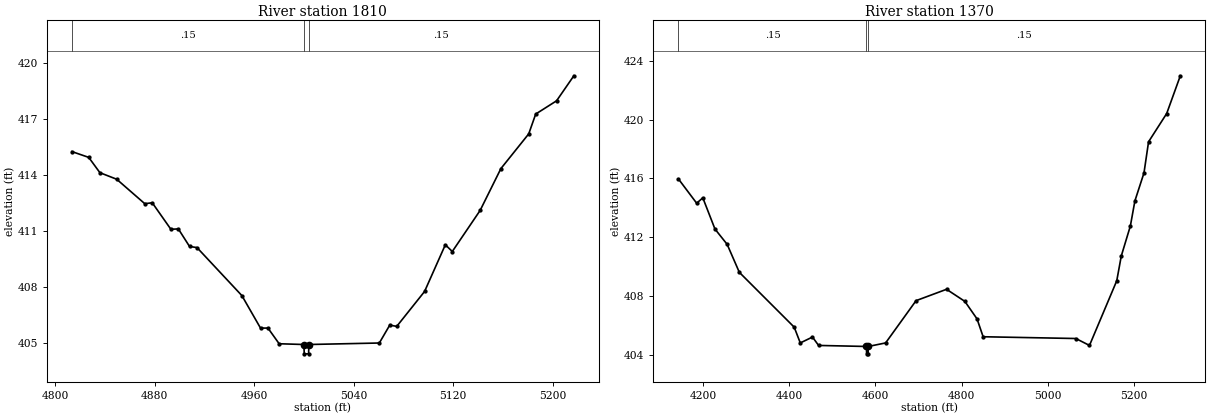
Type RM Length L Ch R = 1,1810,440,440,440
BEGIN DESCRIPTION:
Twin Creek251 2.0
END DESCRIPTION:
XS GIS Cut Line= 3
      2741325.98      6826360.97      2741226.00      6826211.00
      2741126.02      6826011.04
#Sta/Elev= 30
  4813.3  415.24  4826.8  414.93  4835.8  414.11  4849.3  413.76  4871.9  412.45
  4877.9  412.50  4892.9  411.08  4898.9  411.10  4907.9  410.16  4913.9  410.10
  4950.0  407.53  4965.0  405.79  4971.0  405.79  4980.0  404.95  4999.9  404.91
  5000.2  404.41  5003.7  404.41  5003.9  404.91  5060.6  404.99  5069.0  405.95
  5074.6  405.88  5097.0  407.75  5113.7  410.25  5119.3  409.89  5141.7  412.09
  5158.4  414.33  5180.8  416.19  5186.4  417.25  5203.2  417.96  5217.1  419.30
#Mann=3,-1,0
  4813.3    0.15       0  4999.9    0.05       0  5003.9    0.15       0
Bank Sta=4999.9,5003.9
Exp/Cntr=0.3,0.1

Type RM Length L Ch R = 1,1370,0,0,0
BEGIN DESCRIPTION:
Twin Creek251 1.0
END DESCRIPTION:
XS GIS Cut Line= 3
      2742126.00      6826511.00      2741526.00      6825911.00
      2741226.05      6825811.02
#Sta/Elev= 30
  4143.0  415.97  4185.4  414.32  4199.6  414.69  4227.8  412.57  4256.1  411.53
  4284.4  409.63  4411.7  405.91  4425.8  404.84  4454.1  405.24  4468.3  404.67
  4579.4  404.60  4579.7  404.10  4583.2  404.10  4583.4  404.60  4623.8  404.84
  4694.5  407.71  4765.2  408.48  4807.7  407.66  4836.0  406.47  4850.1  405.26
  5065.3  405.14  5096.9  404.67  5160.2  409.06  5170.7  410.74  5191.8  412.78
  5202.3  414.48  5223.4  416.38  5234.0  418.49  5276.1  420.41  5307.7  422.97
#Mann=3,-1,0
  4143.0    0.15       0  4579.4    0.05       0  4583.4    0.15       0
Bank Sta=4579.4,4583.4
Exp/Cntr=0.3,0.1

Chan Stop Cuts=-1