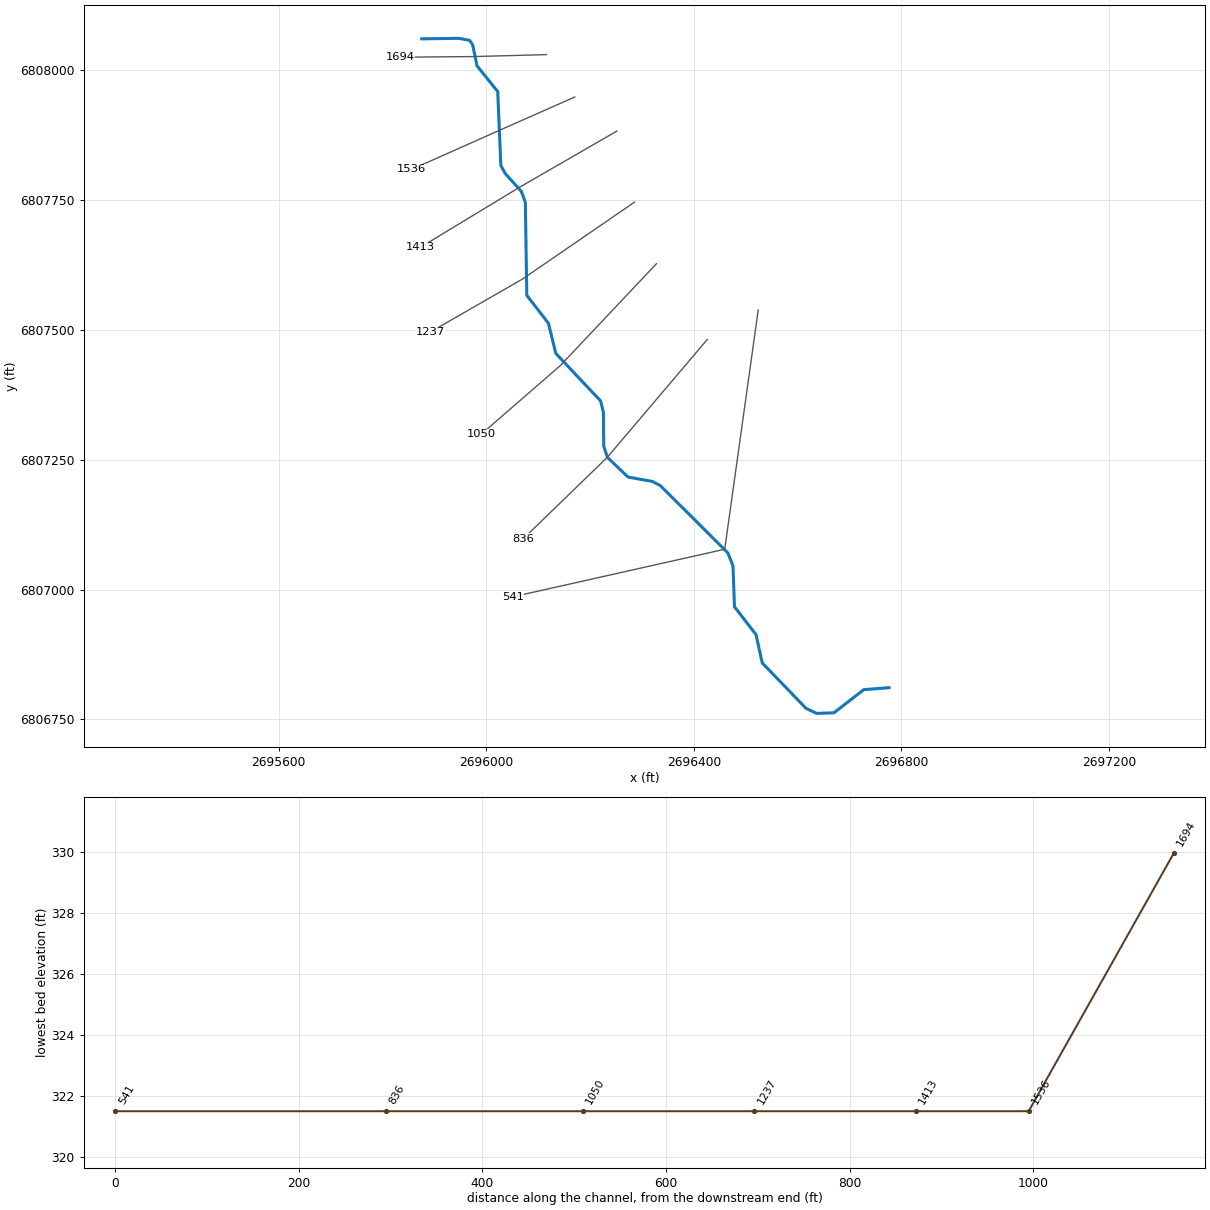
--- Twin Creek253.prj (project) ---

Proj Title=Twin Creek253 Base Level Engineering
Current Plan=p01
Default Exp/Contr=0.3,0.1
English Units
Geom File=g01
Flow File=f01
Plan File=p01
BEGIN DESCRIPTION:
Twin Creek253
END DESCRIPTION:

--- Twin Creek253.p01 (plan) ---

Plan Title=Multiple Run
Short Identifier=Multiple
Geom File=g01
Flow File=f01
Subcritical Flow
K Sum by GR= 0
Std Step Tol= 0.01
Critical Tol= 0.01
Num of Std Step Trials= 20
Max Error Tol= 0.3
Flow Tol Ratio= 0.001
Split Flow NTrial= 30
Split Flow Tol= 0.02
Split Flow Ratio= 0.02
Log Output Level= 0
Friction Slope Method= 1
Unsteady Friction Slope Method= 2
Unsteady Bridges Friction Slope Method= 1
Parabolic Critical Depth
Global Vel Dist=  1 , 1 , 1
Global Log Level= 0
CheckData=True
Encroach Param= -1, 0, 0, 0
BEGIN DESCRIPTION:
Multiple Run
END DESCRIPTION:

--- Twin Creek253.f01 (steady flow) ---

Flow Title=Multiple
Number of Profiles=7
Profile Names=10-year,25-year,50-year,1pct_min,100-year,1pct_plu,500-year
River Rch & RM= Twin Creek253,Reach-1,1694
      89     104     114      63     126     251     151
Boundary for River Rch & Prof#=Twin Creek253,Reach-1,1
Up Type=0
Dn Type=3
Dn Slope=0.005
Boundary for River Rch & Prof#=Twin Creek253,Reach-1,2
Up Type=0
Dn Type=3
Dn Slope=0.005
Boundary for River Rch & Prof#=Twin Creek253,Reach-1,3
Up Type=0
Dn Type=3
Dn Slope=0.005
Boundary for River Rch & Prof#=Twin Creek253,Reach-1,4
Up Type=0
Dn Type=3
Dn Slope=0.005
Boundary for River Rch & Prof#=Twin Creek253,Reach-1,5
Up Type=0
Dn Type=3
Dn Slope=0.005
Boundary for River Rch & Prof#=Twin Creek253,Reach-1,6
Up Type=0
Dn Type=3
Dn Slope=0.005
Boundary for River Rch & Prof#=Twin Creek253,Reach-1,7
Up Type=0
Dn Type=3
Dn Slope=0.005

--- Twin Creek253.g01 (geometry) ---

Geom Title=Existing Conditions

River Reach=Twin Creek253,Reach-1
Reach XY= 30
      2695876.00      6808061.00      2695946.81      6808061.95
      2695967.92      6808058.19      2695974.08      6808049.40
      2695982.26      6808009.19      2696022.26      6807959.48
      2696028.27      6807816.94      2696036.86      6807801.36
      2696067.86      6807767.06      2696075.48      6807745.78
      2696078.24      6807566.93      2696119.86      6807513.17
      2696134.16      6807454.95      2696220.46      6807363.42
      2696225.86      6807340.94      2696226.47      6807276.09
      2696233.75      6807254.55      2696273.43      6807216.74
      2696319.91      6807208.45      2696335.66      6807200.21
      2696465.48      6807070.79      2696475.48      6807045.78
      2696478.33      6806966.97      2696519.86      6806913.17
      2696531.82      6806858.68      2696616.29      6806771.17
      2696636.60      6806761.56      2696669.90      6806762.60
      2696727.49      6806807.31      2696776.00      6806811.00

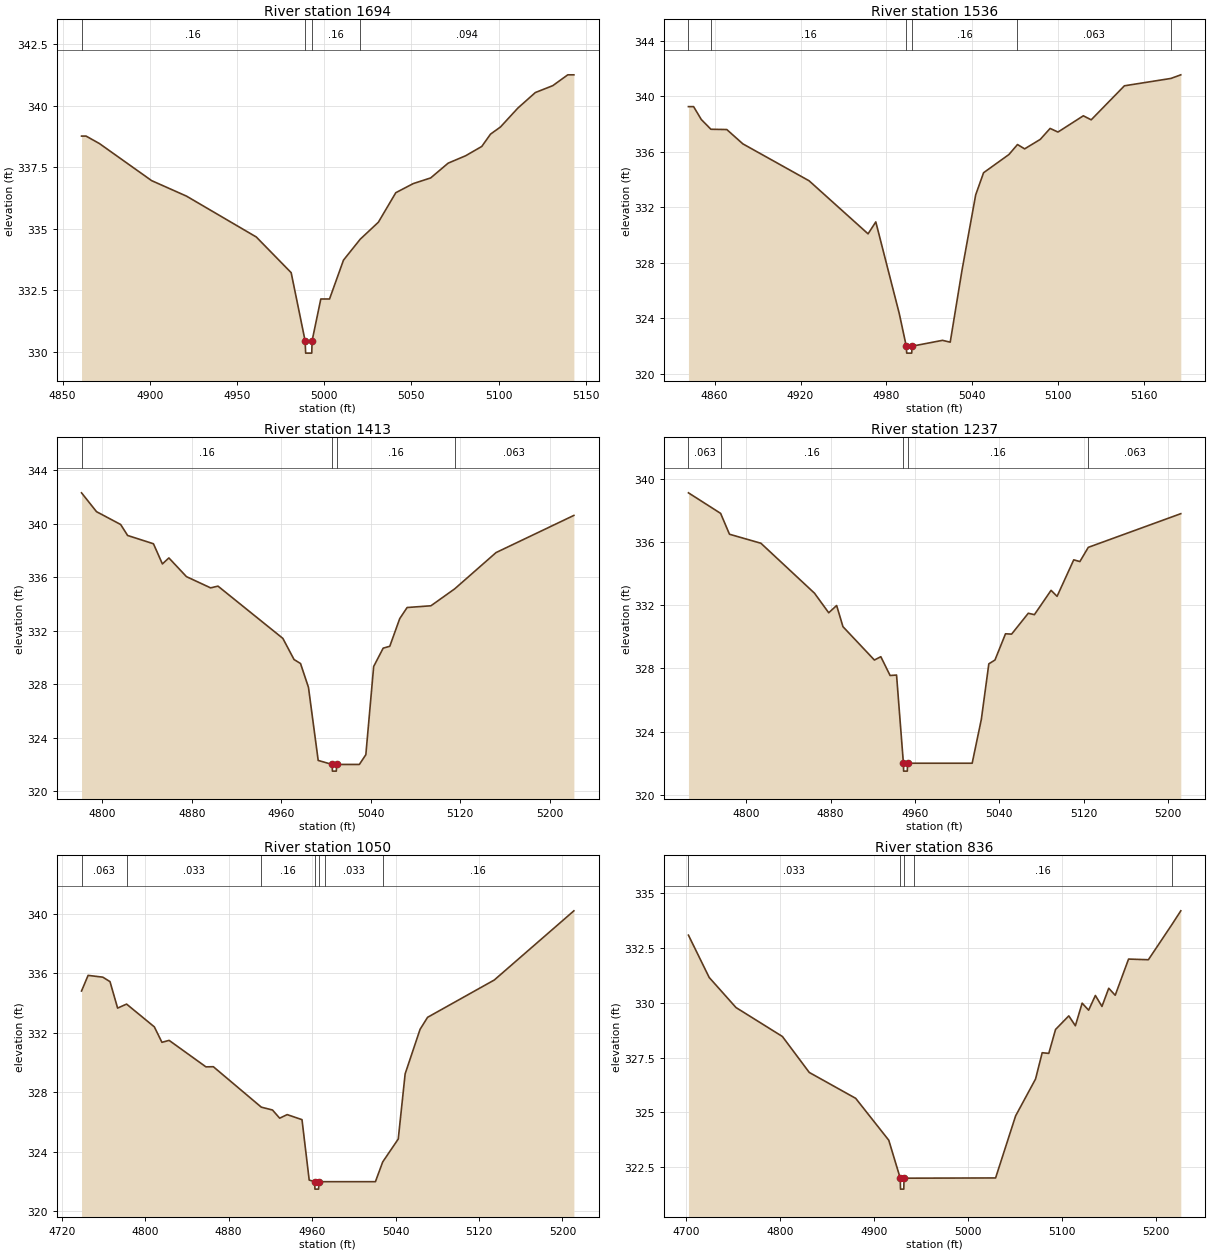
Type RM Length L Ch R = 1,1694,158,158,158
BEGIN DESCRIPTION:
Twin Creek2531693.936
END DESCRIPTION:
XS GIS Cut Line= 3
      2696116.18      6808030.59      2695977.13      6808026.86
      2695833.93      6808025.56
#Sta/Elev= 29
  4860.9  338.76  4863.5  338.76  4871.1  338.46  4901.1  336.95  4921.1  336.32
  4961.1  334.66  4981.1  333.21  4989.1  330.44  4989.4  329.94  4992.9  329.94
  4993.1  330.44  4998.1  332.14  5003.1  332.14  5011.1  333.72  5020.7  334.57
  5031.1  335.26  5041.1  336.46  5051.1  336.83  5061.1  337.06  5071.1  337.66
  5081.1  337.96  5090.4  338.34  5095.4  338.84  5101.1  339.13  5111.1  339.90
  5121.1  340.53  5131.1  340.81  5139.7  341.25  5143.2  341.25
#Mann=4,-1,0
  4860.9    0.16       0  4989.1    0.07       0  4993.1    0.16       0
  5020.7   0.094       0
Bank Sta=4989.1,4993.1
Exp/Cntr=0.3,0.1

Type RM Length L Ch R = 1,1536,123,123,123
BEGIN DESCRIPTION:
Twin Creek2531536.36
END DESCRIPTION:
XS GIS Cut Line= 3
      2696170.76      6807948.94      2696022.27      6807883.28
      2695856.31      6807809.43
#Sta/Elev= 30
  4841.7  339.25  4845.3  339.25  4850.7  338.32  4857.4  337.62  4868.5  337.60
  4879.7  336.57  4926.0  333.91  4967.2  330.09  4972.6  330.95  4989.0  324.35
  4993.9  322.00  4994.2  321.50  4997.7  321.50  4997.9  322.00  5019.2  322.42
  5024.6  322.29  5032.8  327.45  5042.4  332.90  5047.9  334.49  5065.6  335.80
  5071.6  336.52  5076.6  336.21  5087.5  336.89  5094.4  337.68  5099.9  337.42
  5117.6  338.59  5123.1  338.30  5146.3  340.75  5178.8  341.28  5185.7  341.54
#Mann=6,-1,0
  4841.7   0.063       0  4857.4    0.16       0  4993.9    0.07       0
  4997.9    0.16       0  5071.6   0.063       0  5178.8    0.16       0
Bank Sta=4993.9,4997.9
Exp/Cntr=0.3,0.1

Type RM Length L Ch R = 1,1413,176,176,176
BEGIN DESCRIPTION:
Twin Creek2531412.76
END DESCRIPTION:
XS GIS Cut Line= 3
      2696251.70      6807883.24      2696064.40      6807775.12
      2695872.86      6807659.11
#Sta/Elev= 30
  4781.4  342.32  4794.8  340.91  4816.4  339.95  4822.6  339.13  4845.7  338.51
  4853.7  337.00  4859.5  337.45  4875.2  336.05  4896.8  335.21  4903.4  335.34
  4961.4  331.43  4971.4  329.85  4977.2  329.55  4984.3  327.77  4993.0  322.30
  5005.5  322.00  5005.7  321.50  5009.2  321.50  5009.5  322.00  5029.8  322.00
  5035.6  322.73  5042.6  329.33  5051.1  330.70  5057.0  330.84  5065.9  332.91
  5072.5  333.74  5093.8  333.87  5115.1  335.14  5152.0  337.85  5221.6  340.63
#Mann=4,-1,0
  4781.4    0.16       0  5005.5    0.07       0  5009.5    0.16       0
  5115.1   0.063       0
Bank Sta=5005.5,5009.5
Exp/Cntr=0.3,0.1

Type RM Length L Ch R = 1,1237,187,187,187
BEGIN DESCRIPTION:
Twin Creek2531237.37
END DESCRIPTION:
XS GIS Cut Line= 3
      2696285.62      6807746.32      2696070.57      6807598.62
      2695892.07      6807495.95
#Sta/Elev= 30
  4745.2  339.11  4775.7  337.81  4784.1  336.49  4813.9  335.92  4864.7  332.76
  4878.2  331.52  4885.7  331.98  4891.7  330.64  4921.5  328.53  4927.6  328.74
  4936.4  327.55  4942.5  327.58  4949.0  322.00  4949.2  321.50  4952.7  321.50
  4953.0  322.00  5014.2  322.00  5022.9  324.78  5030.0  328.29  5035.8  328.53
  5045.8  330.19  5051.6  330.17  5067.4  331.49  5073.2  331.40  5089.0  332.94
  5094.7  332.56  5110.5  334.87  5116.3  334.76  5124.3  335.66  5212.0  337.79
#Mann=5,-1,0
  4745.2   0.063       0  4775.7    0.16       0  4949.0    0.07       0
  4953.0    0.16       0  5124.3   0.063       0
Bank Sta=4949,4953
Exp/Cntr=0.3,0.1

Type RM Length L Ch R = 1,1050,214,214,214
BEGIN DESCRIPTION:
Twin Creek2531050.37
END DESCRIPTION:
XS GIS Cut Line= 3
      2696327.97      6807627.76      2696142.69      6807431.40
      2695990.04      6807298.91
#Sta/Elev= 30
  4738.9  334.82  4745.2  335.87  4759.3  335.75  4766.2  335.45  4773.5  333.67
  4782.1  333.94  4808.7  332.41  4816.0  331.37  4822.9  331.50  4858.2  329.72
  4865.3  329.73  4911.3  327.01  4922.0  326.82  4928.9  326.27  4936.1  326.51
  4950.3  326.17  4957.2  322.11  4962.5  322.00  4962.7  321.50  4966.2  321.50
  4966.5  322.00  4972.0  322.00  5020.7  322.00  5027.7  323.33  5042.6  324.87
  5049.2  329.25  5063.5  332.24  5070.7  333.05  5134.7  335.56  5211.0  340.21
#Mann=7,-1,0
  4738.9   0.063       0  4782.1   0.033       0  4911.3    0.16       0
  4962.5   0.033       0  4966.5    0.16       0  4972.0   0.033       0
  5027.7    0.16       0
Bank Sta=4962.5,4966.5
Exp/Cntr=0.3,0.1

Type RM Length L Ch R = 1,836,295,295,295
BEGIN DESCRIPTION:
Twin Creek253836.24
END DESCRIPTION:
XS GIS Cut Line= 3
      2696426.08      6807481.89      2696232.69      6807254.18
      2696070.92      6807097.43
#Sta/Elev= 30
  4702.4  333.08  4724.5  331.15  4753.0  329.78  4802.4  328.46  4831.0  326.82
  4880.4  325.64  4915.6  323.73  4927.8  322.00  4928.1  321.50  4931.6  321.50
  4931.8  322.00  4942.3  322.00  5029.3  322.01  5050.6  324.84  5071.8  326.52
  5078.9  327.72  5085.9  327.69  5093.1  328.78  5107.2  329.40  5114.2  328.95
  5121.4  329.98  5128.3  329.66  5135.5  330.33  5142.5  329.83  5149.7  330.66
  5156.6  330.34  5170.8  331.99  5191.9  331.96  5217.2  333.58  5226.4  334.19
#Mann=5,-1,0
  4702.4   0.033       0  4927.8    0.07       0  4931.8   0.033       0
  4942.3    0.16       0  5217.2   0.063       0
Bank Sta=4927.8,4931.8
Exp/Cntr=0.3,0.1

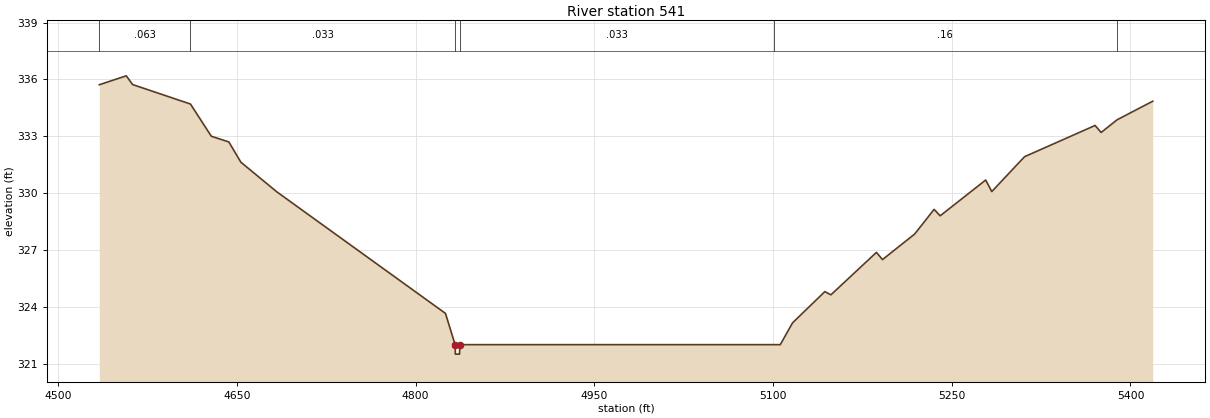
Type RM Length L Ch R = 1,541,0,0,0
BEGIN DESCRIPTION:
Twin Creek253540.882
END DESCRIPTION:
XS GIS Cut Line= 3
      2696524.09      6807538.66      2696459.54      6807077.75
      2696051.02      6806986.00
#Sta/Elev= 30
  4534.6  335.72  4557.2  336.19  4562.5  335.73  4611.1  334.70  4628.6  333.00
  4643.3  332.70  4653.4  331.63  4683.7  330.06  4825.1  323.65  4833.2  322.00
  4833.4  321.50  4836.9  321.50  4837.2  322.00  5100.5  322.00  5106.1  322.00
  5116.4  323.15  5143.5  324.80  5148.6  324.63  5186.8  326.87  5191.9  326.49
  5218.9  327.84  5235.2  329.14  5240.3  328.80  5278.5  330.69  5283.6  330.08
  5311.1  331.92  5370.3  333.57  5375.4  333.20  5388.8  333.87  5418.7  334.85
#Mann=6,-1,0
  4534.6   0.063       0  4611.1   0.033       0  4833.2   0.033       0
  4837.2   0.033       0  5100.5    0.16       0  5388.8   0.063       0
Bank Sta=4833.2,4837.2
Exp/Cntr=0.3,0.1

Chan Stop Cuts=-1