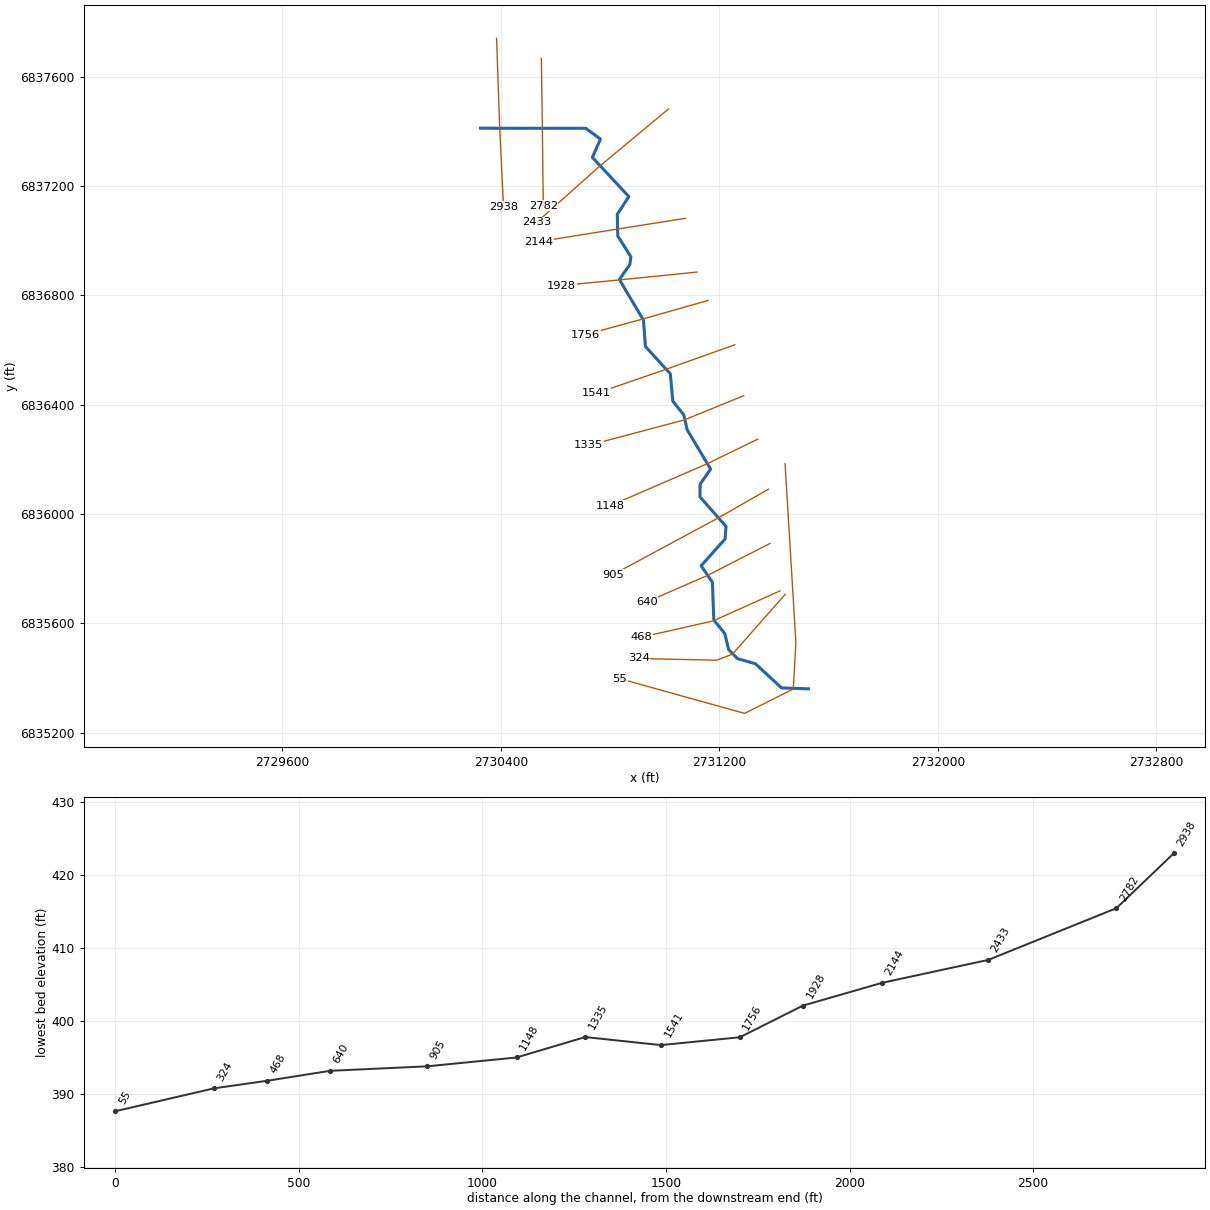
--- Twin Creek261.prj (project) ---

Proj Title=Twin Creek261 Base Level Engineering
Current Plan=p01
Default Exp/Contr=0.3,0.1
English Units
Geom File=g01
Flow File=f01
Plan File=p01
BEGIN DESCRIPTION:
Twin Creek261
END DESCRIPTION:

--- Twin Creek261.p01 (plan) ---

Plan Title=Multiple Run
Short Identifier=Multiple
Geom File=g01
Flow File=f01
Subcritical Flow
K Sum by GR= 0
Std Step Tol= 0.01
Critical Tol= 0.01
Num of Std Step Trials= 20
Max Error Tol= 0.3
Flow Tol Ratio= 0.001
Split Flow NTrial= 30
Split Flow Tol= 0.02
Split Flow Ratio= 0.02
Log Output Level= 0
Friction Slope Method= 1
Unsteady Friction Slope Method= 2
Unsteady Bridges Friction Slope Method= 1
Parabolic Critical Depth
Global Vel Dist=  1 , 1 , 1
Global Log Level= 0
CheckData=True
Encroach Param= -1, 0, 0, 0
BEGIN DESCRIPTION:
Multiple Run
END DESCRIPTION:

--- Twin Creek261.f01 (steady flow) ---

Flow Title=Multiple
Number of Profiles=7
Profile Names=10-year,25-year,50-year,1pct_min,100-year,1pct_plu,500-year
River Rch & RM= Twin Creek261,Reach-1,2938
     294     377     441     256     512    1021     688
Boundary for River Rch & Prof#=Twin Creek261,Reach-1,1
Up Type=0
Dn Type=3
Dn Slope=0.005
Boundary for River Rch & Prof#=Twin Creek261,Reach-1,2
Up Type=0
Dn Type=3
Dn Slope=0.005
Boundary for River Rch & Prof#=Twin Creek261,Reach-1,3
Up Type=0
Dn Type=3
Dn Slope=0.005
Boundary for River Rch & Prof#=Twin Creek261,Reach-1,4
Up Type=0
Dn Type=3
Dn Slope=0.005
Boundary for River Rch & Prof#=Twin Creek261,Reach-1,5
Up Type=0
Dn Type=3
Dn Slope=0.005
Boundary for River Rch & Prof#=Twin Creek261,Reach-1,6
Up Type=0
Dn Type=3
Dn Slope=0.005
Boundary for River Rch & Prof#=Twin Creek261,Reach-1,7
Up Type=0
Dn Type=3
Dn Slope=0.005

--- Twin Creek261.g01 (geometry) ---

Geom Title=Existing Conditions

River Reach=Twin Creek261,Reach-1
Reach XY= 30
      2730326.00      6837411.00      2730711.11      6837410.62
      2730764.91      6837371.38      2730735.31      6837304.34
      2730868.68      6837161.10      2730826.52      6837095.78
      2730828.20      6837016.97      2730876.21      6836940.79
      2730872.39      6836912.64      2730834.07      6836857.69
      2730922.17      6836709.41      2730929.62      6836612.50
      2731020.46      6836513.42      2731029.83      6836412.59
      2731069.88      6836363.18      2731082.08      6836308.80
      2731167.93      6836164.31      2731129.58      6836109.35
      2731129.17      6836062.65      2731224.41      6835954.95
      2731220.91      6835908.71      2731133.33      6835811.10
      2731174.60      6835750.56      2731179.76      6835612.56
      2731219.85      6835563.15      2731234.02      6835504.66
      2731266.00      6835471.65      2731332.02      6835452.82
      2731427.41      6835364.39      2731526.00      6835361.00

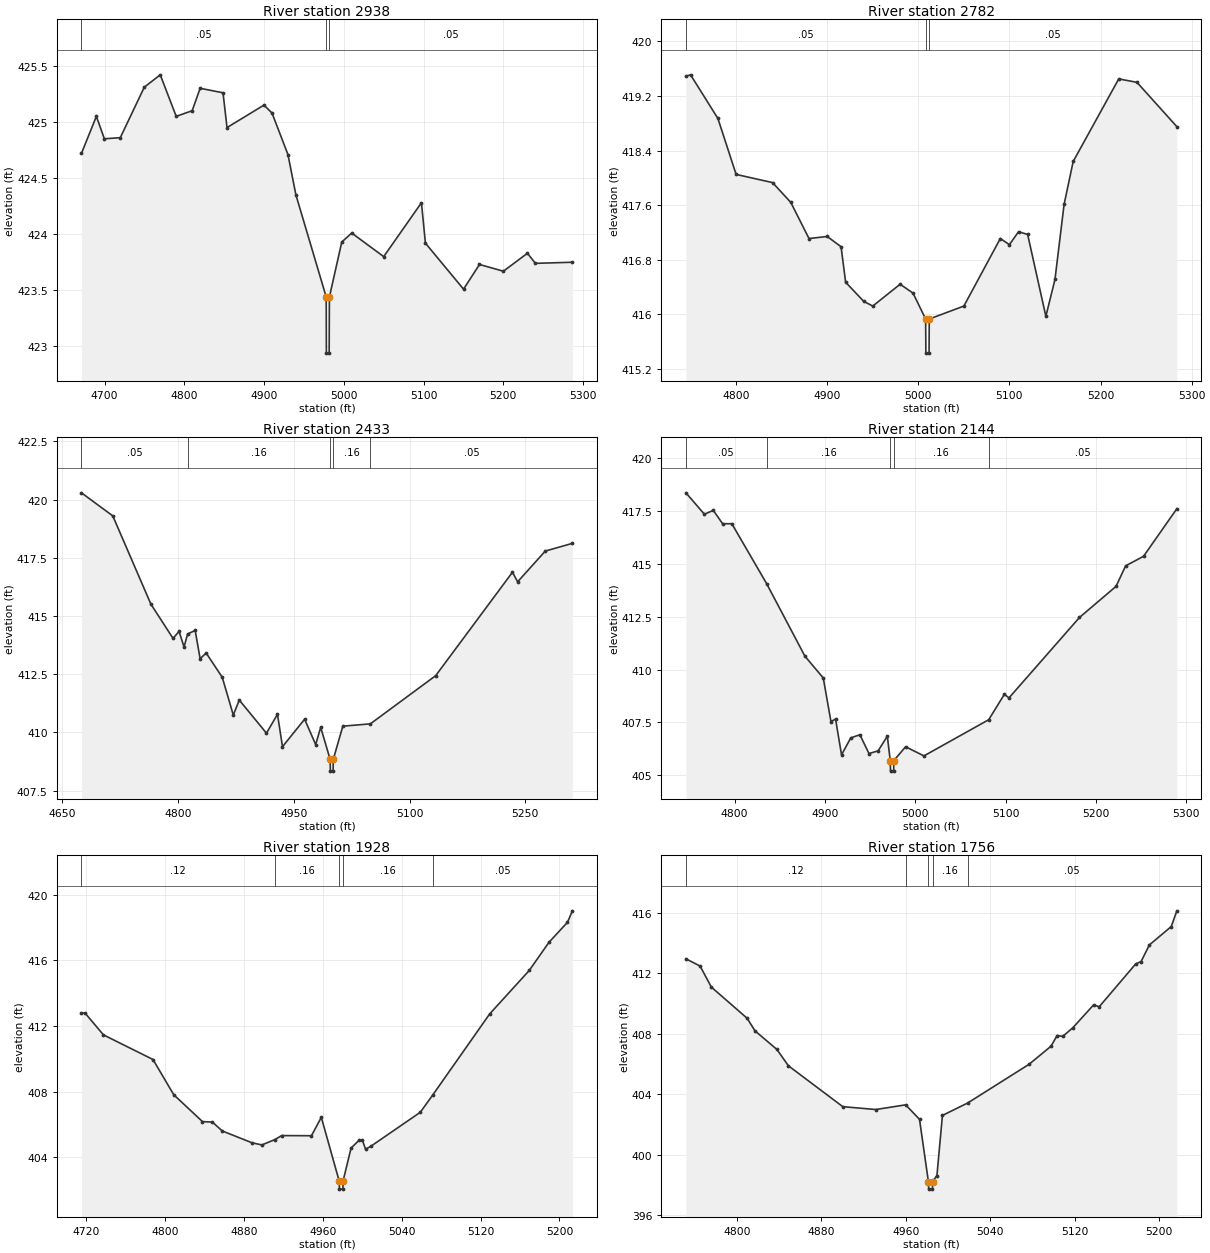
Type RM Length L Ch R = 1,2938,156,156,156
BEGIN DESCRIPTION:
Twin Creek2612938.14
END DESCRIPTION:
XS GIS Cut Line= 3
      2730384.70      6837739.71      2730396.13      6837411.01
      2730410.14      6837124.65
#Sta/Elev= 30
  4671.1  424.72  4689.8  425.05  4699.8  424.85  4719.8  424.86  4749.9  425.31
  4769.9  425.42  4789.9  425.05  4809.9  425.10  4819.9  425.30  4848.6  425.26
  4853.6  424.95  4899.9  425.15  4910.0  425.08  4930.0  424.71  4940.0  424.35
  4978.0  423.44  4978.2  422.94  4981.7  422.94  4982.0  423.44  4997.5  423.93
  5010.0  424.01  5050.1  423.80  5097.4  424.28  5102.4  423.92  5150.2  423.51
  5170.2  423.73  5200.2  423.67  5230.3  423.83  5240.3  423.74  5286.7  423.75
#Mann=3,-1,0
  4671.1    0.05       0  4978.0    0.05       0  4982.0    0.05       0
Bank Sta=4978,4982
Exp/Cntr=0.3,0.1

Type RM Length L Ch R = 1,2782,349,349,349
BEGIN DESCRIPTION:
Twin Creek2612782.04
END DESCRIPTION:
XS GIS Cut Line= 3
      2730548.50      6837666.10      2730552.16      6837416.80
      2730555.66      6837127.25
#Sta/Elev= 30
  4744.9  419.49  4750.0  419.51  4780.0  418.87  4800.0  418.05  4840.0  417.93
  4860.0  417.64  4880.0  417.11  4900.0  417.14  4915.2  416.99  4920.2  416.47
  4940.0  416.19  4950.0  416.12  4980.0  416.44  4994.2  416.31  5008.0  415.93
  5008.3  415.43  5011.8  415.43  5012.0  415.93  5050.0  416.12  5090.0  417.11
  5100.0  417.02  5110.0  417.21  5120.0  417.17  5140.0  415.97  5150.0  416.51
  5160.0  417.61  5170.0  418.24  5220.0  419.45  5240.0  419.40  5283.8  418.75
#Mann=3,-1,0
  4744.9    0.05       0  5008.0    0.05       0  5012.0    0.05       0
Bank Sta=5008,5012
Exp/Cntr=0.3,0.1

Type RM Length L Ch R = 1,2433,289,289,289
BEGIN DESCRIPTION:
Twin Creek2612432.5
END DESCRIPTION:
XS GIS Cut Line= 3
      2731013.44      6837480.89      2730760.54      6837271.03
      2730530.76      6837066.28
#Sta/Elev= 30
  4674.7  420.29  4715.3  419.30  4764.7  415.51  4793.4  414.04  4801.2  414.34
  4807.7  413.67  4812.3  414.23  4822.1  414.38  4828.5  413.17  4836.4  413.41
  4857.2  412.37  4871.5  410.75  4879.3  411.39  4914.5  409.97  4928.8  410.78
  4935.3  409.39  4964.0  410.57  4978.3  409.48  4984.8  410.22  4997.1  408.84
  4997.4  408.34  5000.9  408.34  5001.1  408.84  5013.5  410.27  5049.2  410.37
  5133.9  412.44  5233.4  416.88  5240.1  416.47  5276.0  417.79  5311.1  418.12
#Mann=5,-1,0
  4674.7    0.05       0  4812.3    0.16       0  4997.1    0.07       0
  5001.1    0.16       0  5049.2    0.05       0
Bank Sta=4997.1,5001.1
Exp/Cntr=0.3,0.1

Type RM Length L Ch R = 1,2144,216,216,216
BEGIN DESCRIPTION:
Twin Creek2612144.2
END DESCRIPTION:
XS GIS Cut Line= 3
      2731076.15      6837081.47      2730823.60      6837041.76
      2730539.57      6836996.31
#Sta/Elev= 30
  4746.2  418.35  4766.6  417.34  4776.5  417.52  4786.8  416.89  4797.0  416.89
  4835.5  414.06  4877.9  410.63  4898.2  409.60  4906.7  407.54  4911.8  407.66
  4918.4  405.97  4928.6  406.77  4938.7  406.92  4948.8  406.03  4958.9  406.16
  4969.1  406.85  4972.3  405.70  4972.6  405.20  4976.1  405.20  4976.3  405.70
  4989.3  406.35  5009.6  405.92  5081.3  407.63  5098.6  408.83  5103.7  408.66
  5181.7  412.46  5222.2  413.93  5232.8  414.90  5252.6  415.35  5289.5  417.60
#Mann=5,-1,0
  4746.2    0.05       0  4835.5    0.16       0  4972.3    0.07       0
  4976.3    0.16       0  5081.3    0.05       0
Bank Sta=4972.3,4976.3
Exp/Cntr=0.3,0.1

Type RM Length L Ch R = 1,1928,172,172,172
BEGIN DESCRIPTION:
Twin Creek2611927.7
END DESCRIPTION:
XS GIS Cut Line= 3
      2731118.19      6836885.03      2730834.57      6836856.28
      2730622.43      6836835.87
#Sta/Elev= 30
  4715.0  412.79  4718.6  412.79  4737.3  411.46  4787.6  409.96  4808.6  407.82
  4837.8  406.18  4847.9  406.15  4857.9  405.61  4888.1  404.89  4898.1  404.76
  4911.4  405.09  4918.2  405.33  4948.4  405.32  4958.4  406.44  4976.5  402.57
  4976.8  402.07  4980.3  402.07  4980.5  402.57  4988.6  404.57  4996.8  405.05
  5000.1  405.05  5003.3  404.50  5008.7  404.68  5058.9  406.75  5071.6  407.81
  5129.2  412.73  5169.4  415.38  5189.5  417.10  5208.2  418.31  5213.2  419.01
#Mann=5,-1,0
  4715.0    0.12       0  4911.4    0.16       0  4976.5    0.07       0
  4980.5    0.16       0  5071.6    0.05       0
Bank Sta=4976.5,4980.5
Exp/Cntr=0.3,0.1

Type RM Length L Ch R = 1,1756,215,215,215
BEGIN DESCRIPTION:
Twin Creek2611756.31
END DESCRIPTION:
XS GIS Cut Line= 3
      2731158.93      6836781.22      2730919.57      6836713.24
      2730710.89      6836656.41
#Sta/Elev= 30
  4751.8  412.95  4765.2  412.47  4775.9  411.08  4809.8  409.02  4817.2  408.19
  4838.0  406.96  4848.9  405.88  4900.4  403.18  4931.6  402.99  4960.0  403.30
  4973.1  402.34  4981.5  398.23  4981.8  397.73  4985.3  397.73  4985.5  398.23
  4989.6  398.63  4994.8  402.60  5018.7  403.42  5076.9  405.98  5097.6  407.17
  5103.5  407.88  5108.7  407.82  5118.3  408.39  5138.1  409.91  5143.3  409.78
  5177.9  412.61  5183.0  412.77  5190.9  413.87  5211.6  415.08  5216.9  416.12
#Mann=5,-1,0
  4751.8    0.12       0  4960.0    0.16       0  4981.5    0.07       0
  4985.5    0.16       0  5018.7    0.05       0
Bank Sta=4981.5,4985.5
Exp/Cntr=0.3,0.1

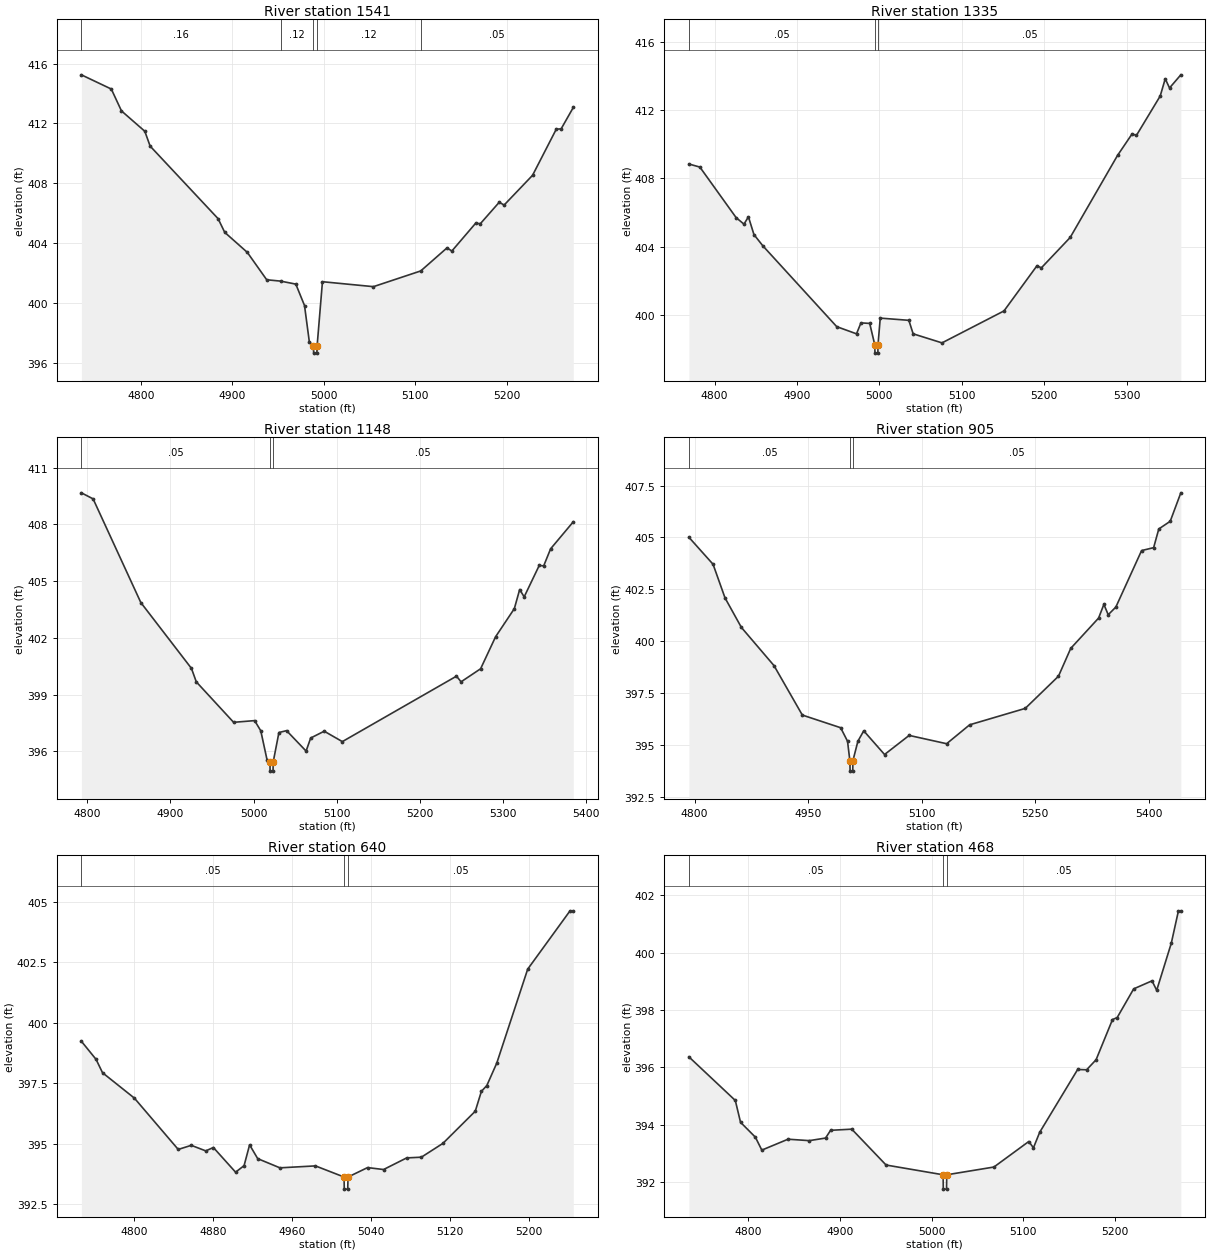
Type RM Length L Ch R = 1,1541,206,206,206
BEGIN DESCRIPTION:
Twin Creek2611540.74
END DESCRIPTION:
XS GIS Cut Line= 3
      2731256.81      6836619.02      2731006.16      6836529.98
      2730749.56      6836441.26
#Sta/Elev= 30
  4735.0  415.25  4767.7  414.30  4778.8  412.84  4804.3  411.48  4810.1  410.49
  4884.4  405.64  4891.6  404.73  4916.3  403.39  4937.5  401.56  4952.7  401.47
  4969.3  401.27  4978.8  399.84  4984.1  397.40  4988.6  397.16  4988.8  396.66
  4992.3  396.66  4992.6  397.16  4998.4  401.43  5054.1  401.10  5105.8  402.15
  5134.5  403.69  5139.8  403.48  5165.7  405.33  5171.0  405.31  5191.6  406.74
  5196.9  406.55  5228.0  408.54  5253.9  411.62  5259.2  411.64  5272.5  413.07
#Mann=5,-1,0
  4735.0    0.16       0  4952.7    0.12       0  4988.6    0.07       0
  4992.6    0.12       0  5105.8    0.05       0
Bank Sta=4988.6,4992.6
Exp/Cntr=0.3,0.1

Type RM Length L Ch R = 1,1335,187,187,187
BEGIN DESCRIPTION:
Twin Creek2611334.77
END DESCRIPTION:
XS GIS Cut Line= 3
      2731289.10      6836432.74      2731072.23      6836344.50
      2730721.82      6836251.41
#Sta/Elev= 30
  4768.9  408.83  4782.2  408.65  4826.2  405.69  4835.7  405.31  4841.1  405.74
  4847.8  404.70  4858.6  404.04  4948.2  399.31  4972.2  398.89  4977.6  399.53
  4988.2  399.50  4994.3  398.26  4994.6  397.76  4998.1  397.76  4998.3  398.26
  5001.0  399.81  5035.7  399.68  5040.9  398.89  5075.9  398.36  5151.1  400.23
  5191.2  402.88  5196.4  402.75  5231.4  404.53  5288.8  409.33  5306.6  410.60
  5311.7  410.50  5340.6  412.81  5346.7  413.82  5351.9  413.28  5365.6  414.05
#Mann=3,-1,0
  4768.9    0.05       0  4994.3    0.05       0  4998.3    0.05       0
Bank Sta=4994.3,4998.3
Exp/Cntr=0.3,0.1

Type RM Length L Ch R = 1,1148,243,243,243
BEGIN DESCRIPTION:
Twin Creek2611147.77
END DESCRIPTION:
XS GIS Cut Line= 3
      2731340.31      6836273.76      2731152.88      6836182.75
      2730800.95      6836030.76
#Sta/Elev= 30
  4792.9  409.67  4807.0  409.35  4864.4  403.87  4925.3  400.39  4931.1  399.68
  4976.0  397.54  5001.3  397.63  5008.7  397.09  5016.2  395.56  5019.7  395.46
  5019.9  394.96  5023.4  394.96  5023.7  395.46  5030.5  397.00  5039.7  397.10
  5063.2  396.02  5068.7  396.71  5085.0  397.07  5106.8  396.52  5244.1  399.98
  5249.6  399.68  5273.1  400.37  5291.1  402.06  5313.7  403.55  5320.1  404.56
  5325.5  404.17  5343.6  405.83  5349.0  405.81  5357.3  406.71  5384.6  408.14
#Mann=3,-1,0
  4792.9    0.05       0  5019.7    0.05       0  5023.7    0.05       0
Bank Sta=5019.7,5023.7
Exp/Cntr=0.3,0.1

Type RM Length L Ch R = 1,905,265,265,265
BEGIN DESCRIPTION:
Twin Creek261904.58
END DESCRIPTION:
XS GIS Cut Line= 3
      2731379.87      6836091.13      2731200.07      6835988.17
      2730810.41      6835778.45
#Sta/Elev= 30
  4792.4  405.01  4824.3  403.71  4840.1  402.09  4861.7  400.67  4904.8  398.83
  4942.2  396.45  4992.8  395.84  5001.9  395.19  5005.0  394.25  5005.3  393.75
  5008.8  393.75  5009.0  394.25  5015.6  395.19  5023.3  395.69  5050.8  394.55
  5083.3  395.47  5132.8  395.07  5163.2  395.98  5236.6  396.77  5280.5  398.32
  5296.7  399.66  5333.5  401.12  5340.5  401.78  5346.2  401.28  5356.3  401.65
  5390.3  404.37  5406.2  404.51  5413.0  405.41  5428.1  405.78  5442.1  407.15
#Mann=3,-1,0
  4792.4    0.05       0  5005.0    0.05       0  5009.0    0.05       0
Bank Sta=5005,5009
Exp/Cntr=0.3,0.1

Type RM Length L Ch R = 1,640,172,172,172
BEGIN DESCRIPTION:
Twin Creek261639.76
END DESCRIPTION:
XS GIS Cut Line= 3
      2731385.07      6835892.36      2731158.54      6835776.60
      2730934.95      6835679.14
#Sta/Elev= 30
  4746.5  399.24  4761.4  398.49  4767.9  397.94  4800.2  396.89  4844.6  394.77
  4857.8  394.94  4872.5  394.71  4880.2  394.85  4902.7  393.83  4911.3  394.10
  4916.9  394.96  4925.1  394.39  4947.6  394.01  4983.6  394.09  5012.6  393.63
  5012.8  393.13  5016.3  393.13  5016.6  393.63  5036.4  394.02  5052.6  393.94
  5076.0  394.42  5090.9  394.45  5112.7  395.02  5145.5  396.35  5151.7  397.17
  5157.2  397.41  5167.3  398.34  5198.6  402.22  5241.5  404.63  5244.8  404.63
#Mann=3,-1,0
  4746.5    0.05       0  5012.6    0.05       0  5016.6    0.05       0
Bank Sta=5012.6,5016.6
Exp/Cntr=0.3,0.1

Type RM Length L Ch R = 1,468,144,144,144
BEGIN DESCRIPTION:
Twin Creek261468.17
END DESCRIPTION:
XS GIS Cut Line= 3
      2731422.14      6835719.16      2731177.90      6835609.51
      2730915.88      6835550.09
#Sta/Elev= 30
  4735.3  396.37  4785.9  394.85  4791.6  394.09  4807.8  393.57  4814.8  393.12
  4843.4  393.50  4866.6  393.45  4884.3  393.54  4889.8  393.81  4912.9  393.85
  4950.3  392.60  5012.5  392.26  5012.7  391.76  5016.2  391.76  5016.5  392.26
  5067.9  392.53  5105.9  393.42  5111.0  393.20  5117.8  393.74  5159.2  395.93
  5169.0  395.92  5179.3  396.27  5197.2  397.67  5202.3  397.74  5220.3  398.74
  5240.3  399.02  5245.4  398.69  5261.3  400.33  5269.1  401.46  5271.7  401.46
#Mann=3,-1,0
  4735.3    0.05       0  5012.5    0.05       0  5016.5    0.05       0
Bank Sta=5012.5,5016.5
Exp/Cntr=0.3,0.1

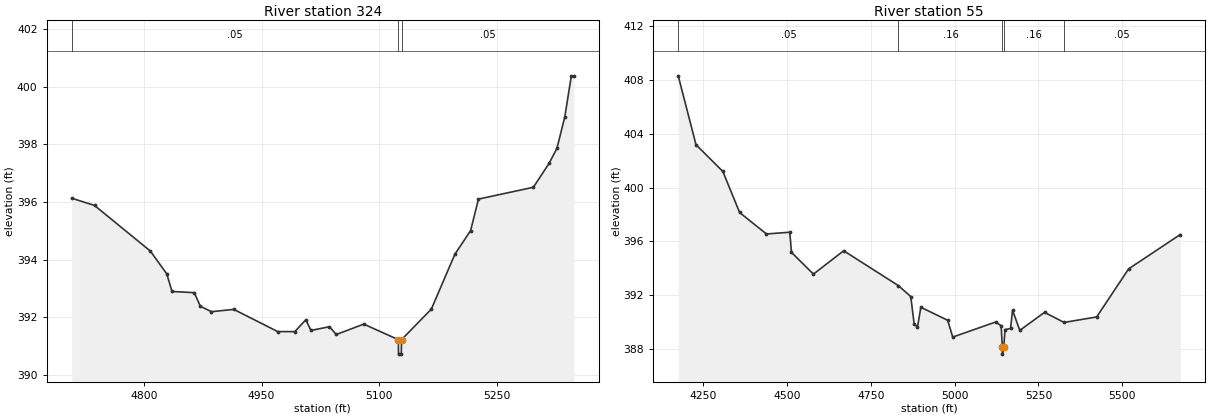
Type RM Length L Ch R = 1,324,269,269,269
BEGIN DESCRIPTION:
Twin Creek261323.53
END DESCRIPTION:
XS GIS Cut Line= 4
      2731441.17      6835706.60      2731247.98      6835487.77
      2731190.10      6835465.63      2730904.55      6835471.90
#Sta/Elev= 30
  4708.3  396.13  4737.3  395.88  4808.4  394.30  4829.3  393.51  4836.0  392.90
  4864.4  392.86  4872.0  392.39  4886.2  392.20  4914.6  392.28  4970.7  391.51
  4992.4  391.51  5006.4  391.92  5013.0  391.55  5036.5  391.68  5045.2  391.41
  5080.3  391.77  5124.3  391.23  5124.5  390.73  5128.0  390.73  5128.3  391.23
  5166.3  392.29  5196.3  394.19  5216.3  395.01  5226.3  396.10  5296.3  396.51
  5316.3  397.34  5326.3  397.86  5336.3  398.95  5344.6  400.37  5347.8  400.37
#Mann=3,-1,0
  4708.3    0.05       0  5124.3    0.05       0  5128.3    0.05       0
Bank Sta=5124.3,5128.3
Exp/Cntr=0.3,0.1

Type RM Length L Ch R = 1,55,0,0,0
BEGIN DESCRIPTION:
Twin Creek26155.319
END DESCRIPTION:
XS GIS Cut Line= 5
      2731440.57      6836183.88      2731480.20      6835530.21
      2731470.69      6835360.24      2731292.35      6835271.22
      2730835.37      6835398.13
#Sta/Elev= 30
  4174.9  408.32  4227.9  403.19  4308.0  401.20  4358.1  398.14  4438.3  396.54
  4507.9  396.67  4512.9  395.17  4578.5  393.55  4668.7  395.29  4832.2  392.69
  4869.0  391.88  4879.1  389.84  4889.1  389.61  4899.1  391.08  4979.2  390.11
  4994.3  388.86  5122.0  389.98  5138.8  389.71  5142.4  388.09  5142.6  387.59
  5146.4  388.09  5150.5  389.42  5166.8  389.50  5172.9  390.85  5194.5  389.36
  5268.2  390.70  5326.7  389.95  5423.9  390.36  5519.3  393.94  5673.6  396.50
#Mann=5,-1,0
  4174.9    0.05       0  4832.2    0.16       0  5142.4    0.07       0
  5146.4    0.16       0  5326.7    0.05       0
Bank Sta=5142.4,5146.4
Exp/Cntr=0.3,0.1

Chan Stop Cuts=-1