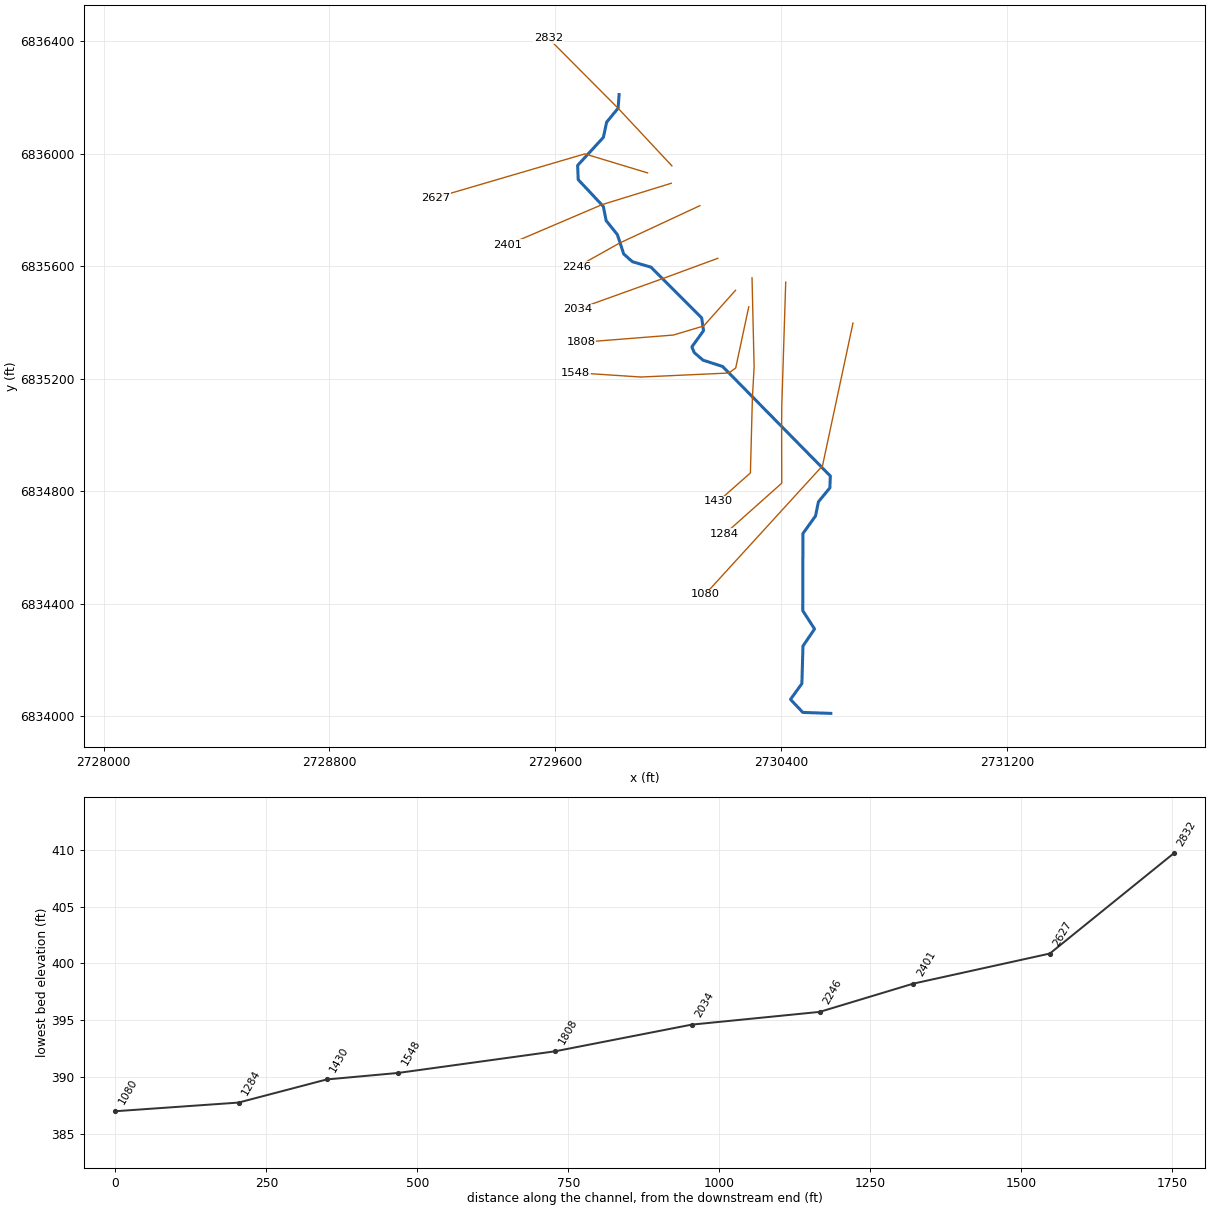
--- Twin Creek263.prj (project) ---

Proj Title=Twin Creek263 Base Level Engineering
Current Plan=p01
Default Exp/Contr=0.3,0.1
English Units
Geom File=g01
Flow File=f01
Plan File=p01
Y Axis Title=Elevation
X Axis Title(PF)=Main Channel Distance
X Axis Title(XS)=Station
BEGIN DESCRIPTION:
Twin Creek263
END DESCRIPTION:
DSS Export Rating Curves= 0
DSS Export Rating Curve Sorted= 0
DSS Export Volume Flow Curves= 0
DXF OffsetX= 0
DXF OffsetY= 0
DXF ScaleX= 1
DXF ScaleY= 10

--- Twin Creek263.p01 (plan) ---

Plan Title=Multiple Run
Short Identifier=Multiple
Geom File=g01
Flow File=f01
Subcritical Flow
K Sum by GR= 0
Std Step Tol= 0.01
Critical Tol= 0.01
Num of Std Step Trials= 20
Max Error Tol= 0.3
Flow Tol Ratio= 0.001
Split Flow NTrial= 30
Split Flow Tol= 0.02
Split Flow Ratio= 0.02
Log Output Level= 0
Friction Slope Method= 1
Unsteady Friction Slope Method= 2
Unsteady Bridges Friction Slope Method= 1
Parabolic Critical Depth
Global Vel Dist=  1 , 1 , 1
Global Log Level= 0
CheckData=True
Encroach Param= -1, 0, 0, 0
BEGIN DESCRIPTION:
Multiple Run
END DESCRIPTION:

--- Twin Creek263.f01 (steady flow) ---

Flow Title=Multiple
Number of Profiles=7
Profile Names=10-year,25-year,50-year,1pct_min,100-year,1pct_plu,500-year
River Rch & RM= Twin Creek263,Reach-1,2832
     393     513     609     359     716    1428     988
Boundary for River Rch & Prof#=Twin Creek263,Reach-1,1
Up Type=0
Dn Type=3
Dn Slope=0.005
Boundary for River Rch & Prof#=Twin Creek263,Reach-1,2
Up Type=0
Dn Type=3
Dn Slope=0.005
Boundary for River Rch & Prof#=Twin Creek263,Reach-1,3
Up Type=0
Dn Type=3
Dn Slope=0.005
Boundary for River Rch & Prof#=Twin Creek263,Reach-1,4
Up Type=0
Dn Type=3
Dn Slope=0.005
Boundary for River Rch & Prof#=Twin Creek263,Reach-1,5
Up Type=0
Dn Type=3
Dn Slope=0.005
Boundary for River Rch & Prof#=Twin Creek263,Reach-1,6
Up Type=0
Dn Type=3
Dn Slope=0.005
Boundary for River Rch & Prof#=Twin Creek263,Reach-1,7
Up Type=0
Dn Type=3
Dn Slope=0.005

--- Twin Creek263.g01 (geometry) ---

Geom Title=Existing Conditions
Program Version=4.10

River Reach=Twin Creek263   ,Reach-1
Reach XY= 30
        2729826.        6836211.       2729822.4      6836162.49
      2729781.97      6836113.24      2729770.17       6836058.7
      2729679.11      6835959.35      2729681.08      6835908.72
      2729770.15      6835813.29      2729780.19      6835762.73
      2729819.89      6835713.16      2729842.49      6835643.95
      2729873.46      6835616.75       2729939.2      6835597.36
       2730118.5      6835417.05      2730125.11      6835371.63
      2730083.84      6835314.05      2730092.15      6835293.92
      2730123.15      6835266.85      2730192.65      6835244.35
      2730574.39      6834854.97      2730572.69      6834812.74
      2730532.16       6834763.2      2730521.81      6834712.74
       2730477.2       6834650.5      2730476.66      6834376.16
      2730518.44        6834311.      2730477.39      6834250.56
      2730473.52      6834116.85      2730433.19      6834060.66
      2730476.84      6834014.37        2730576.        6834011.

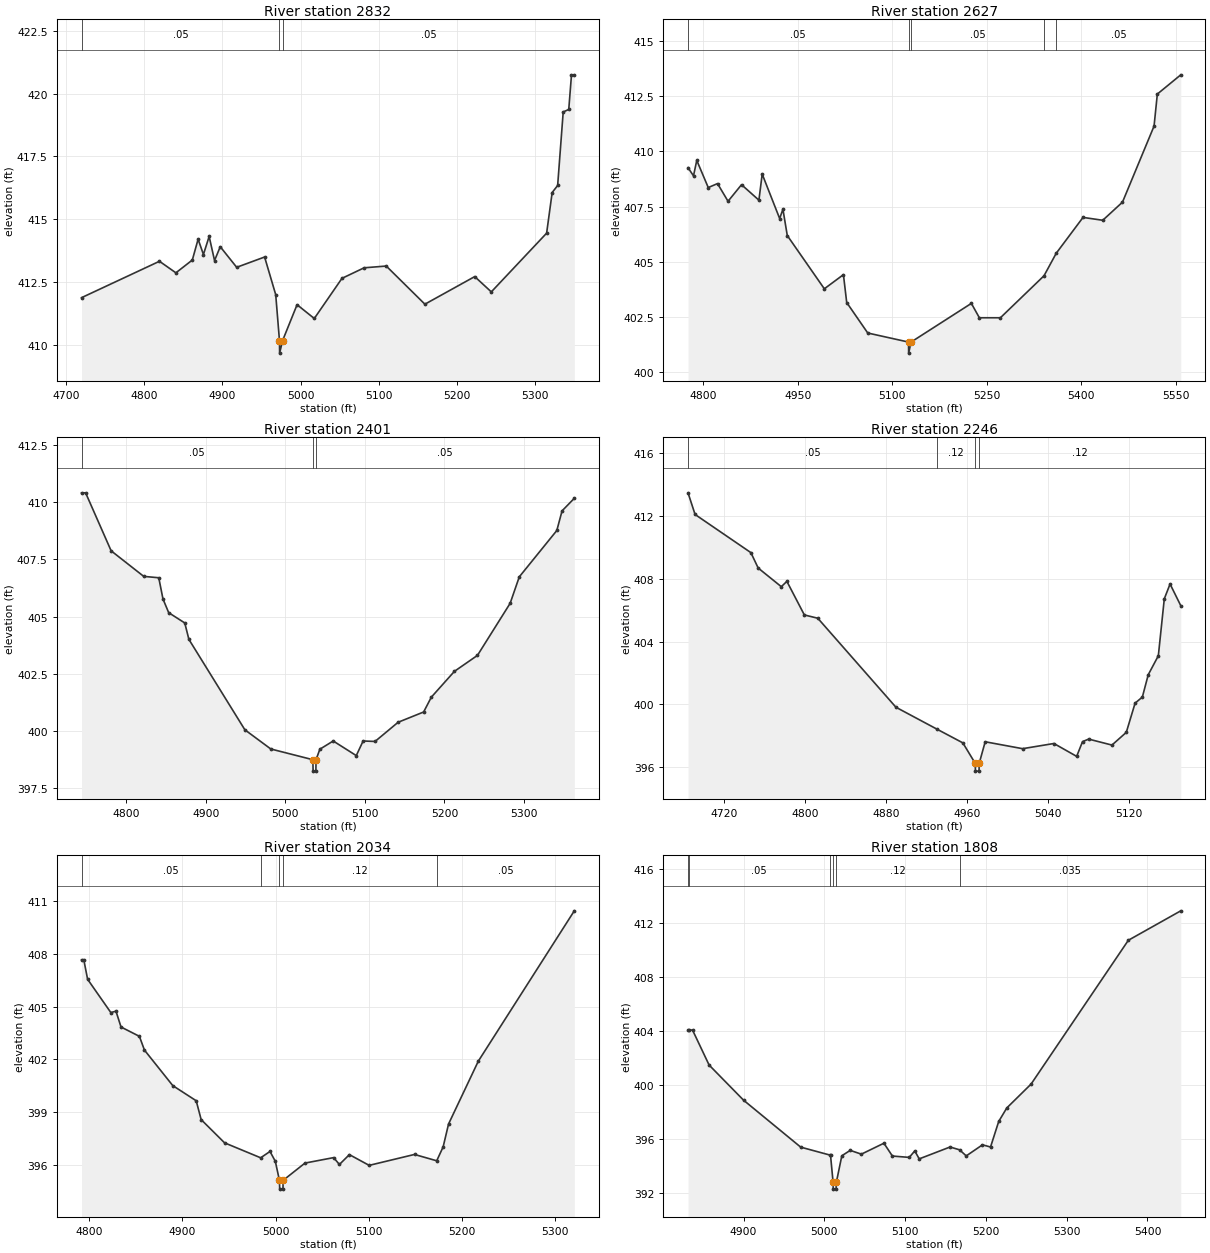
Type RM Length L Ch R = 1 ,2832    ,205,205,205
BEGIN DESCRIPTION:
Twin Creek2632831.534
END DESCRIPTION:
XS GIS Cut Line= 3
      2730013.07      6835957.58       2729822.4      6836162.49
      2729575.97      6836411.03
#Sta/Elev= 30
  4720.1  411.87  4819.7  413.32  4840.7  412.86  4861.7  413.37  4869.1   414.2
  4875.9  413.59  4883.2  414.31  4890.1  413.35  4897.4   413.9  4918.4  413.08
  4954.1  413.49  4968.3  411.99  4973.1  410.16  4973.3  409.66  4977.1  410.16
  4995.6  411.59  5017.6  411.04    5053  412.64  5081.3  413.06  5109.6  413.13
    5159  411.61  5222.7  412.71  5243.9   412.1  5314.6  414.44  5321.7  416.06
  5328.7  416.34  5335.8  419.27  5342.9  419.37  5346.4  420.75    5350  420.75
#Mann= 3 ,-1 , 0
  4720.1     .05       0  4973.1     .05       0  4977.1     .05       0
Bank Sta=4973.1,4977.1
XS Rating Curve= 0 ,0
Exp/Cntr=0.3,0.1

Type RM Length L Ch R = 1 ,2627    ,226,226,226
BEGIN DESCRIPTION:
Twin Creek2632627.25
END DESCRIPTION:
XS GIS Cut Line= 3
      2729926.71      6835932.67      2729704.72      6836000.19
      2729177.22      6835844.94
#Sta/Elev= 30
    4776  409.26  4784.7  408.89  4789.9  409.59  4808.1  408.36  4822.8  408.54
  4839.5  407.74  4860.9  408.49  4888.5  407.79  4893.7  408.97  4921.4  406.96
  4926.6  407.38  4933.5  406.19  4992.3  403.78  5022.6  404.42  5027.8  403.16
  5061.2  401.78  5125.9  401.37  5126.1  400.87  5129.9  401.37  5225.6  403.12
  5238.3  402.47  5271.7  402.47  5340.9  404.37  5360.3  405.39  5402.8  407.01
  5434.1  406.88  5465.4   407.7  5515.5  411.14  5520.7  412.59  5557.9  413.46
#Mann= 5 ,-1 , 0
    4776     .05       0  5125.9     .05       0  5129.9     .05       0
  5340.9     .16       0  5360.3     .05       0
Bank Sta=5125.9,5129.9
XS Rating Curve= 0 ,0
Exp/Cntr=0.3,0.1

Type RM Length L Ch R = 1 ,2401    ,155,155,155
BEGIN DESCRIPTION:
Twin Creek2632401.11
END DESCRIPTION:
XS GIS Cut Line= 3
      2730010.74      6835895.69      2729765.67      6835819.79
      2729431.83      6835676.87
#Sta/Elev= 30
  4743.6  410.42  4748.7  410.42  4780.8  407.88  4821.8  406.76  4840.7   406.7
    4846  405.77  4853.2  405.17  4873.4  404.72  4878.6     404    4949  400.04
  4981.6   399.2  5034.5  398.73  5034.8  398.23  5038.3  398.23  5038.5  398.73
  5043.3  399.19  5060.1  399.55  5089.1  398.91  5097.7  399.55  5112.7  399.53
  5141.7  400.37  5173.8  400.82  5183.5  401.47  5212.5   402.6  5241.5   403.3
  5282.6  405.58  5294.1  406.74  5341.3  408.77  5347.9  409.63  5363.3  410.18
#Mann= 3 ,-1 , 0
  4743.6     .05       0  5034.5     .05       0  5038.5     .05       0
Bank Sta=5034.5,5038.5
XS Rating Curve= 0 ,0
Exp/Cntr=0.3,0.1

Type RM Length L Ch R = 1 ,2246    ,212,212,212
BEGIN DESCRIPTION:
Twin Creek2632245.85
END DESCRIPTION:
XS GIS Cut Line= 3
      2730112.32      6835816.14       2729827.5      6835683.05
      2729676.66      6835598.09
#Sta/Elev= 30
  4684.1  413.48  4691.1   412.1  4746.3  409.67  4753.5  408.69  4776.4   407.5
  4781.9  407.84  4799.2   405.7  4812.5  405.49  4889.8  399.82  4930.8  398.41
    4956  397.55  4968.2  396.25  4968.5  395.75    4972  395.75  4972.2  396.25
  4978.1  397.62  5015.1  397.18  5046.1  397.51  5068.6  396.69  5074.4  397.63
  5080.5  397.79  5103.5  397.41  5117.7  398.22  5126.4  400.08  5133.6  400.47
  5139.4  401.89  5149.4   403.1  5155.3  406.73    5161  407.67  5171.6  406.29
#Mann= 4 ,-1 , 0
  4684.1     .05       0  4930.8     .12       0  4968.2     .07       0
  4972.2     .12       0
Bank Sta=4968.2,4972.2
XS Rating Curve= 0 ,0
Exp/Cntr=0.3,0.1

Type RM Length L Ch R = 1 ,2034    ,226,226,226
BEGIN DESCRIPTION:
Twin Creek2632033.92
END DESCRIPTION:
XS GIS Cut Line= 3
      2730175.49      6835628.86      2729980.34      6835556.75
      2729679.18      6835448.14
#Sta/Elev= 30
  4792.1  407.66  4794.5  407.66  4798.6  406.55  4823.5  404.66    4829  404.74
  4834.4  403.84  4854.1  403.31  4859.5  402.53  4889.9  400.51    4915  399.65
  4920.3  398.58  4945.4  397.26  4984.1  396.41  4994.1  396.77  4999.8  396.21
  5004.2  395.13  5004.5  394.63    5008  394.63  5008.2  395.13  5031.6  396.11
  5062.3  396.42  5068.5  396.03  5079.2  396.59  5100.4  395.98    5149   396.6
  5172.8  396.24  5179.7  397.03  5185.5  398.33  5217.4   401.9  5320.3  410.44
#Mann= 5 ,-1 , 0
  4792.1     .05       0  4984.1     .12       0  5004.2     .07       0
  5008.2     .12       0  5172.8     .05       0
Bank Sta=5004.2,5008.2
XS Rating Curve= 0 ,0
Exp/Cntr=0.3,0.1

Type RM Length L Ch R = 1 ,1808    ,260,260,260
BEGIN DESCRIPTION:
Mapping XS 183cd38d
END DESCRIPTION:
XS GIS Cut Line= 4
      2730238.47      6835515.32      2730125.65      6835388.34
      2730018.04      6835356.08      2729691.26      6835330.16
#Sta/Elev= 30
  4831.2  404.07  4832.4  404.07  4836.8  404.07  4857.3  401.48  4899.9  398.88
  4970.7   395.4  5006.4  394.82  5007.6  394.81  5010.8  392.79    5011  392.29
  5014.5  392.29  5014.8  392.79  5021.6  394.76    5032  395.16  5045.8  394.88
  5073.7  395.69  5084.2  394.74  5105.1  394.64  5111.9  395.12  5117.4  394.53
  5155.6  395.41  5167.4   395.2  5175.6  394.75  5195.7  395.57  5205.7  395.41
  5215.8   397.3  5225.8   398.3  5255.9  400.07  5376.3  410.72  5441.2   412.9
#Mann= 6 ,-1 , 0
  4831.2    .035       0  4832.4     .05       0  5006.4     .12       0
  5010.8     .05       0  5014.8     .12       0  5167.4    .035       0
Bank Sta=5010.8,5014.8
XS Rating Curve= 0 ,0
Exp/Cntr=0.3,0.1

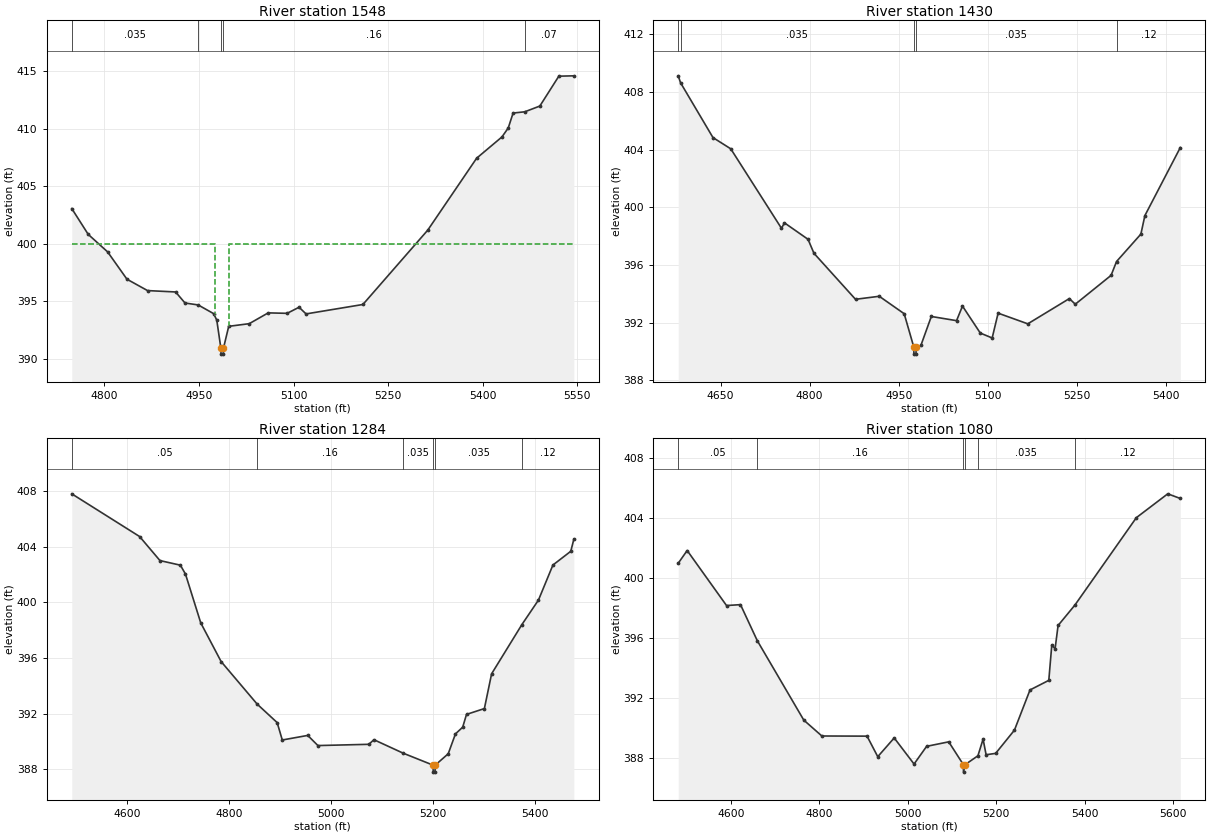
Type RM Length L Ch R = 1 ,1548    ,118,118,118
BEGIN DESCRIPTION:
Twin Creek2631547.57
END DESCRIPTION:
XS GIS Cut Line= 5
      2730285.37      6835456.54      2730239.06      6835238.99
       2730214.5      6835221.09      2729903.34      6835206.86
      2729672.25      6835222.21
#Sta/Elev= 30
  4748.5  403.06  4774.6  400.81  4805.3  399.29    4836  396.91  4868.6  395.92
  4913.1   395.8    4928  394.84  4948.9  394.67  4973.5  393.91  4978.4  393.34
  4984.9  390.89  4985.2  390.39  4988.7  390.39  4988.9  390.89  4997.3  392.81
  5029.8  393.04  5059.9  393.98  5089.9  393.94  5108.8  394.47  5119.9  393.89
    5210  394.71  5312.8  401.18  5390.3  407.44  5430.4  409.29  5440.4  410.07
  5448.1  411.37  5466.6  411.48  5490.5  411.98  5520.6  414.58  5544.4  414.61
#Mann= 5 ,-1 , 0
  4748.5    .035       0  4948.9     .16       0  4984.9     .07       0
  4988.9     .16       0  5466.6     .07       0
#XS Ineff= 2 , 0
       0    4975     400    4997       0     400
Permanent Ineff=
       F       F
Bank Sta=4984.9,4988.9
XS Rating Curve= 0 ,0
Exp/Cntr=0.3,0.1

Type RM Length L Ch R = 1 ,1430    ,146,146,146
BEGIN DESCRIPTION:
Twin Creek2631429.88
END DESCRIPTION:
XS GIS Cut Line= 5
      2730296.91       6835559.5      2730304.35      6835242.77
      2730298.16      6835130.93      2730291.17       6834865.8
      2730177.67      6834765.23
#Sta/Elev= 30
  4578.7  409.11  4582.6  408.63  4637.2  404.83  4667.2  404.05  4752.6  398.54
  4757.6  398.92  4797.3  397.78  4807.3  396.81  4877.3  393.62  4917.3  393.83
  4959.3  392.62  4975.4  390.32  4975.7  389.82  4979.2  389.82  4979.4  390.32
  4987.4  390.42    5005  392.43  5047.5  392.14  5057.5  393.15  5087.5  391.28
  5107.5  390.94  5117.5  392.66  5167.5  391.92  5237.5  393.67  5247.5  393.28
  5307.8  395.28    5317  396.24    5358  398.14  5364.7  399.42  5424.4  404.14
#Mann= 5 ,-1 , 0
  4578.7     .05       0  4582.6    .035       0  4975.4    .035       0
  4979.4    .035       0    5317     .12       0
Bank Sta=4975.4,4979.4
XS Rating Curve= 0 ,0
Exp/Cntr=0.3,0.1

Type RM Length L Ch R = 1 ,1284    ,204,204,204
BEGIN DESCRIPTION:
Twin Creek2631283.98
END DESCRIPTION:
XS GIS Cut Line= 5
      2730416.28      6835544.16      2730402.36       6835104.8
      2730401.75      6835037.25      2730402.22      6834829.45
      2730200.14      6834648.78
#Sta/Elev= 30
  4490.9   407.8  4624.1  404.73  4664.1     403  4704.2  402.67  4714.2  402.03
  4744.2  398.52  4784.2  395.74    4855  392.68  4894.3  391.35  4904.3   390.1
  4954.3  390.43  4974.3   389.7  5074.3  389.79  5084.3  390.12  5141.9  389.15
  5200.6  388.29  5200.8  387.79  5204.3  387.79  5204.6  388.29  5230.2  389.11
  5244.4  390.54  5258.6  391.02  5266.1  391.94  5301.2  392.36  5315.4  394.86
  5374.9   398.4  5407.4  400.16  5435.8  402.68  5470.9  403.67  5476.9  404.54
#Mann= 6 ,-1 , 0
  4490.9     .05       0    4855     .16       0  5141.9    .035       0
  5200.6     .07       0  5204.6    .035       0  5374.9     .12       0
Bank Sta=5200.6,5204.6
XS Rating Curve= 0 ,0
Exp/Cntr=0.3,0.1

Type RM Length L Ch R = 1 ,1080    ,0,0,0
BEGIN DESCRIPTION:
Twin Creek2631079.649
END DESCRIPTION:
XS GIS Cut Line= 3
      2730654.59       6835398.7       2730546.6      6834891.16
      2730131.75      6834435.12
#Sta/Elev= 30
  4481.1  400.96  4501.3  401.81  4590.3  398.14  4621.9   398.2  4659.8   395.8
    4765   390.5  4805.9  389.44  4908.1  389.43  4932.3  388.06  4969.5  389.31
  5014.4  387.57  5042.8  388.75  5092.8  389.05  5125.9  387.53  5126.2  387.03
  5129.9  387.53  5158.8  388.12  5170.5  389.23  5177.3  388.19  5198.9  388.28
  5241.4  389.83  5276.6  392.51  5319.1  393.15  5325.9  395.52  5333.3  395.25
  5340.1  396.81  5378.1  398.17  5517.1     404  5588.1  405.59  5616.5  405.28
#Mann= 6 ,-1 , 0
  4481.1     .05       0  4659.8     .16       0  5125.9     .07       0
  5129.9     .16       0  5158.8    .035       0  5378.1     .12       0
Bank Sta=5125.9,5129.9
XS Rating Curve= 0 ,0
Exp/Cntr=0.3,0.1

Chan Stop Cuts=-1
Use User Specified Reach Order=0
Composite Channel Slope=5