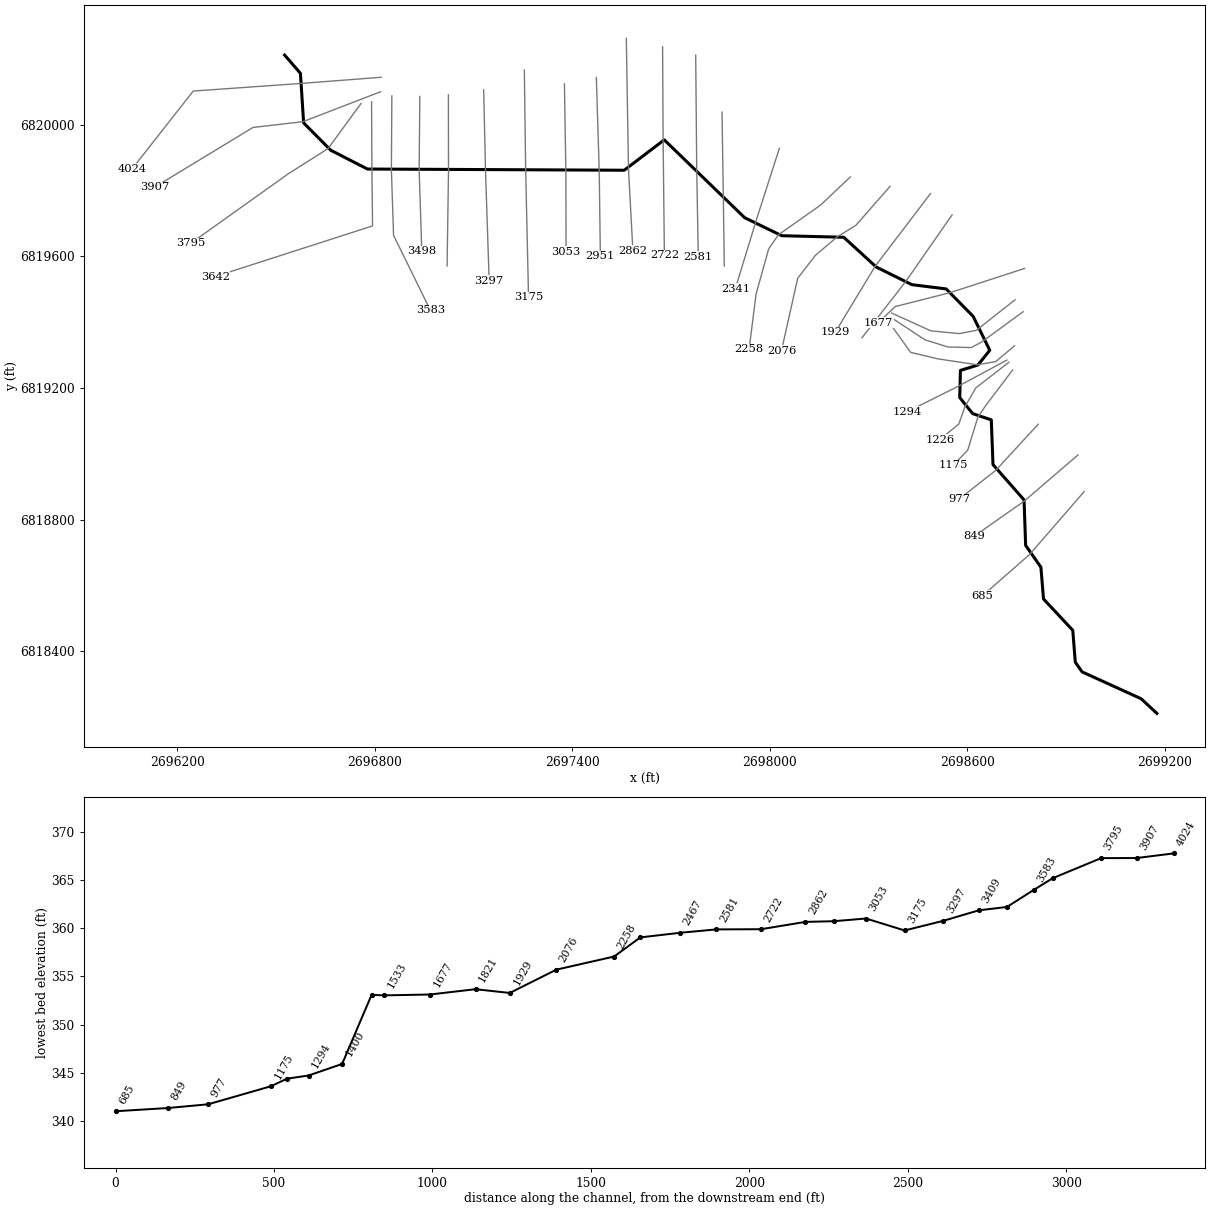
--- Twin Creek264.prj (project) ---

Proj Title=Twin Creek264 Base Level Engineering
Current Plan=p01
Default Exp/Contr=0.3,0.1
English Units
Geom File=g01
Flow File=f01
Plan File=p01
Y Axis Title=Elevation
X Axis Title(PF)=Main Channel Distance
X Axis Title(XS)=Station
BEGIN DESCRIPTION:
Twin Creek264
END DESCRIPTION:
DSS Export Rating Curves= 0
DSS Export Rating Curve Sorted= 0
DSS Export Volume Flow Curves= 0
DXF OffsetX= 0
DXF OffsetY= 0
DXF ScaleX= 1
DXF ScaleY= 10

--- Twin Creek264.p01 (plan) ---

Plan Title=Multiple Run
Program Version=4.10
Short Identifier=Multiple
Geom File=g01
Flow File=f01
Subcritical Flow
K Sum by GR= 0
Std Step Tol= 0.01
Critical Tol= 0.01
Num of Std Step Trials= 20
Max Error Tol= 0.3
Flow Tol Ratio= 0.001
Split Flow NTrial= 30
Split Flow Tol= 0.02
Split Flow Ratio= 0.02
Log Output Level= 0
Friction Slope Method= 1
Unsteady Friction Slope Method= 2
Unsteady Bridges Friction Slope Method= 1
Parabolic Critical Depth
Global Vel Dist= 1 , 1 , 1
Global Log Level= 0
CheckData=True
Encroach Param=-1 ,0,0, 0
BEGIN DESCRIPTION:
Multiple Run
END DESCRIPTION:
Computation Interval=1HOUR
Output Interval=1HOUR
Run HTab= 0
Run UNet= 0
Run PostProcess= 0
Run WQNet= 0
UNET Theta= 1
UNET Theta Warmup= 1
UNET ZTol= 0.02
UNET ZSATol= 0.05
UNET MxIter= 20
UNET MaxInSteps= 0
UNET DtIC= 0
UNET DtMin= 0
UNET MaxCRTS= 20
UNET WFStab= 2
UNET SFStab= 1
UNET WFX= 1
UNET SFX= 1
UNET DSS MLevel= 4
UNET DZMax Abort= 100
UNET Convert EG Bridges= 0
UNET Use Existing IB Tables=-1
UNET Froude Reduction=False
UNET Froude Limit= 1
UNET Froude Power= 10
UNET Time Slicing=0,0, 5
UNET Junction Losses=0
Instantaneous Interval=1HOUR
Write IC File= 0
Write IC File at Sim End=0
Echo Input=False
Echo Parameters=False
Echo Output=False
Write Detailed= 0
WQ AD Non Conservative
WQ ULTIMATE=-1
WQ Max Comp Step=1HOUR
WQ Output Interval=15MIN
WQ Output Selected Increments= 0
WQ Output face flow=0
WQ Output face velocity=0
WQ Output face area=0
WQ Output face dispersion=0
WQ Output cell volume=0
WQ Output cell surface area=0
WQ Output cell continuity=0
WQ Output cumulative cell continuity=0
WQ Output face conc=0
WQ Output face dconc_dx=0
WQ Output face courant=0
WQ Output face peclet=0
WQ Output face adv mass=0
WQ Output face disp mass=0
WQ Output cell mass=0
WQ Output cell source sink temp=0
WQ Output cell source sink nsm=0
WQ Output MaxMinRange=-1
WQ Daily Max Min Mean=-1
WQ Daily Range=0
WQ Daily Time=0
WQ Create Restart=0
WQ Fixed Restart=0
WQ System Summary=0
WQ Use Fixed Temperature=0
Sorting and Armoring Iterations= 10
XS Update Threshold= 0.02
Hydraulics Update Threshold= 0.02
Energy Slope Method= 1
Volume Change Method= 0
XS Weighting Method= 0
Number of US Weighted Cross Sections= 1
Number of DS Weighted Cross Sections= 1
Upstream XS Weight=0.25
Main XS Weight=0.5
Downstream XS Weight=0.25
Number of DS XS's Weighted with US Boundary= 1
Upstream Boundary Weight= 1
Weight of XSs Associated with US Boundary= 0
Number of US XS's Weighted with DS Boundary= 1
Downstream Boundary Weight= 0.5
Weight of XSs Associated with DS Boundary= 0.5
Sediment Output Level= 4
Mass or Volume Output= 0
Output Increment Type= 1
Profile and TS Output Increment= 10
XS Output Flag= 0
XS Output Increment= 10
Disregard all LS=0
Disregard all Conn=0
Disregard all Breaches=0
Disregard all Pumps=0

--- Twin Creek264.f01 (steady flow) ---

Flow Title=Multiple
Number of Profiles=7
Profile Names=10-year,25-year,50-year,1pct_min,100-year,1pct_plu,500-year
River Rch & RM= Twin Creek264,Reach-1,4024
     232     291     336     193     385     768     504
Boundary for River Rch & Prof#=Twin Creek264,Reach-1,1
Up Type=0
Dn Type=3
Dn Slope=0.005
Boundary for River Rch & Prof#=Twin Creek264,Reach-1,2
Up Type=0
Dn Type=3
Dn Slope=0.005
Boundary for River Rch & Prof#=Twin Creek264,Reach-1,3
Up Type=0
Dn Type=3
Dn Slope=0.005
Boundary for River Rch & Prof#=Twin Creek264,Reach-1,4
Up Type=0
Dn Type=3
Dn Slope=0.005
Boundary for River Rch & Prof#=Twin Creek264,Reach-1,5
Up Type=0
Dn Type=3
Dn Slope=0.005
Boundary for River Rch & Prof#=Twin Creek264,Reach-1,6
Up Type=0
Dn Type=3
Dn Slope=0.005
Boundary for River Rch & Prof#=Twin Creek264,Reach-1,7
Up Type=0
Dn Type=3
Dn Slope=0.005

--- Twin Creek264.g01 (geometry) ---

Geom Title=Existing Conditions

River Reach=Twin Creek264,Reach-1
Reach XY= 30
      2696526.00      6820211.00      2696573.99      6820155.62
      2696583.81      6820004.79      2696666.29      6819921.75
      2696777.55      6819864.75      2697557.78      6819861.10
      2697679.34      6819953.40      2697923.70      6819716.83
      2698036.50      6819662.20      2698224.53      6819657.45
      2698323.71      6819566.85      2698431.56      6819513.45
      2698535.81      6819500.49      2698617.89      6819417.07
      2698668.22      6819314.06      2698632.34      6819269.30
      2698579.19      6819252.95      2698577.00      6819170.59
      2698616.24      6819121.76      2698672.89      6819102.68
      2698678.08      6818966.87      2698772.44      6818859.53
      2698777.23      6818721.51      2698823.64      6818655.02
      2698831.54      6818558.58      2698920.46      6818463.42
      2698928.08      6818366.71      2698948.72      6818337.10
      2699128.36      6818255.33      2699176.00      6818211.00

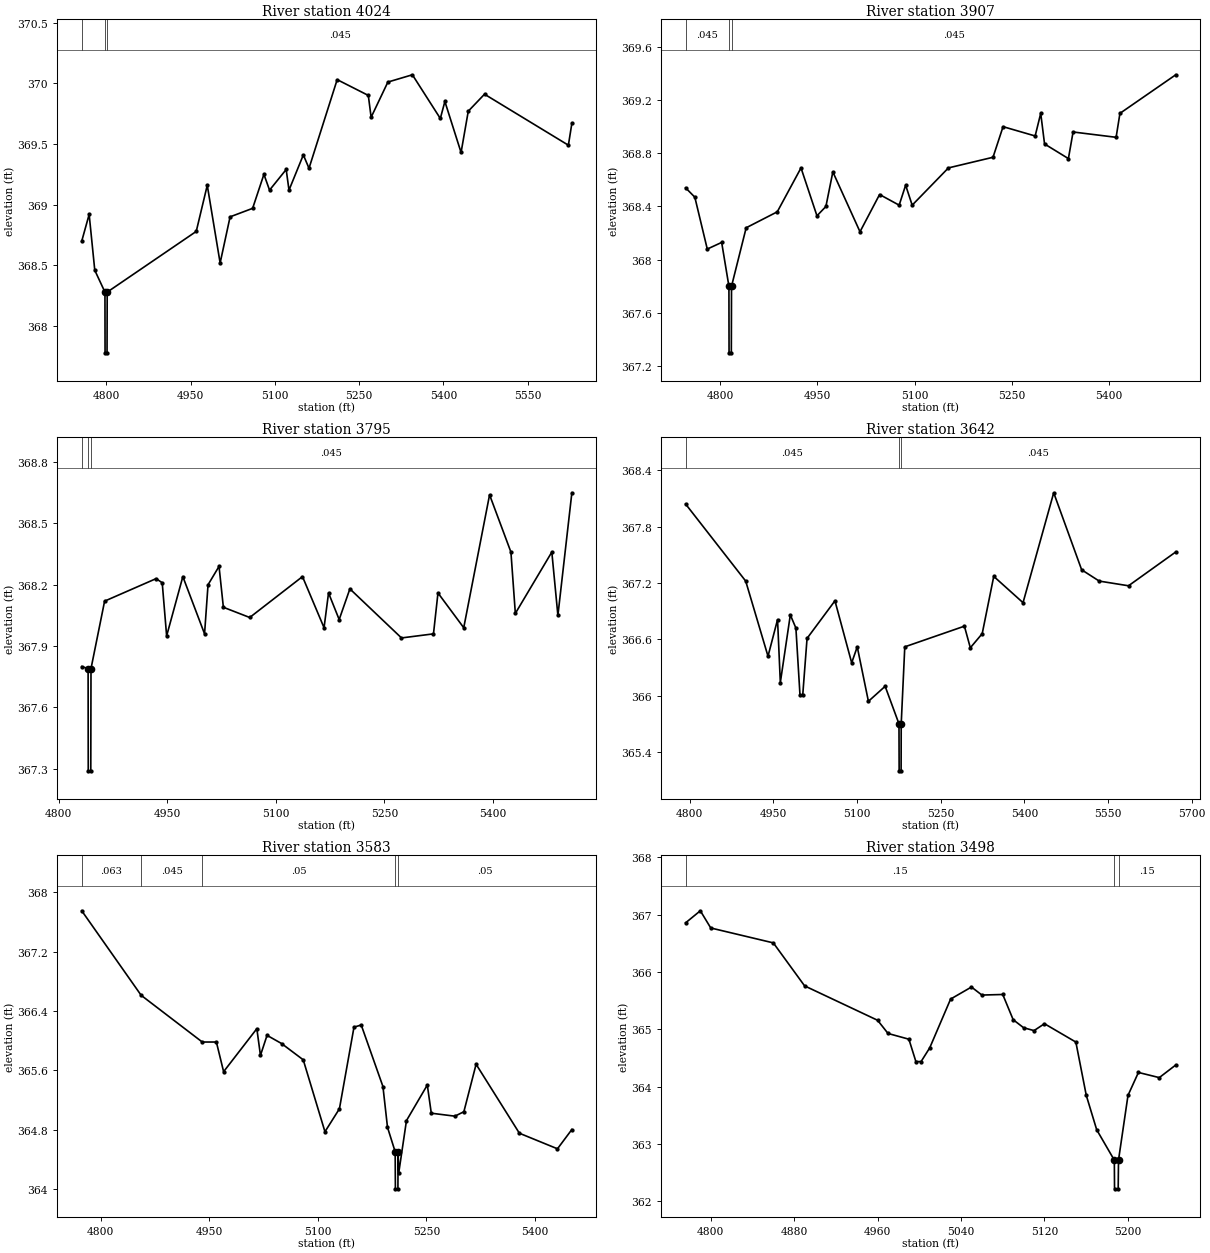
Type RM Length L Ch R = 1,4024,117,117,117
BEGIN DESCRIPTION:
Twin Creek2644023.74
END DESCRIPTION:
XS GIS Cut Line= 4
      2696819.15      6820143.51      2696576.37      6820124.79
      2696248.40      6820101.62      2696063.31      6819866.01
#Sta/Elev= 30
  4756.5  368.70  4769.7  368.92  4779.7  368.46  4797.8  368.28  4798.0  367.78
  4801.5  367.78  4801.8  368.28  4960.2  368.78  4979.8  369.16  5002.7  368.52
  5020.4  368.90  5060.5  368.97  5080.6  369.25  5090.6  369.12  5120.2  369.29
  5125.2  369.12  5150.7  369.41  5160.8  369.30  5210.9  370.03  5266.3  369.90
  5271.3  369.72  5301.1  370.01  5344.7  370.07  5394.4  369.71  5402.5  369.85
  5431.3  369.43  5444.1  369.77  5473.0  369.91  5622.2  369.49  5628.4  369.67
#Mann=3,-1,0
  4756.5   0.045       0  4797.8   0.045       0  4801.8   0.045       0
Bank Sta=4797.8,4801.8
Exp/Cntr=0.3,0.1

Type RM Length L Ch R = 1,3907,112,112,112
BEGIN DESCRIPTION:
Twin Creek2643909.55
END DESCRIPTION:
XS GIS Cut Line= 4
      2696817.90      6820099.67      2696581.46      6820008.54
      2696429.82      6819991.03      2696130.61      6819809.34
#Sta/Elev= 30
  4746.6  368.54  4760.8  368.47  4780.0  368.08  4802.2  368.13  4813.4  367.80
  4813.6  367.30  4817.1  367.30  4817.4  367.80  4840.0  368.24  4888.0  368.36
  4924.6  368.69  4949.2  368.33  4963.0  368.40  4973.7  368.66  5015.6  368.21
  5045.8  368.49  5076.0  368.41  5086.0  368.56  5096.1  368.41  5152.0  368.69
  5220.8  368.77  5236.3  369.00  5285.8  368.93  5294.4  369.10  5300.3  368.87
  5337.1  368.76  5344.3  368.96  5410.7  368.92  5416.6  369.10  5502.7  369.39
#Mann=3,-1,0
  4746.6   0.045       0  4813.4   0.045       0  4817.4   0.045       0
Bank Sta=4813.4,4817.4
Exp/Cntr=0.3,0.1

Type RM Length L Ch R = 1,3795,153,153,153
BEGIN DESCRIPTION:
Twin Creek2643794.73
END DESCRIPTION:
XS GIS Cut Line= 4
      2696758.10      6820063.71      2696657.85      6819926.76
      2696536.45      6819849.78      2696240.26      6819638.66
#Sta/Elev= 30
  4831.9  367.80  4840.7  367.79  4840.9  367.29  4844.4  367.29  4844.7  367.79
  4863.5  368.12  4934.6  368.23  4943.1  368.21  4949.2  367.95  4971.6  368.24
  5001.6  367.96  5006.4  368.20  5021.6  368.29  5027.6  368.09  5064.0  368.04
  5136.9  368.24  5166.7  367.99  5172.9  368.16  5187.6  368.03  5202.4  368.18
  5273.7  367.94  5317.9  367.96  5324.1  368.16  5359.7  367.99  5395.4  368.64
  5424.9  368.36  5431.0  368.06  5481.4  368.36  5489.8  368.05  5509.1  368.65
#Mann=3,-1,0
  4831.9   0.045       0  4840.7   0.045       0  4844.7   0.045       0
Bank Sta=4840.7,4844.7
Exp/Cntr=0.3,0.1

Type RM Length L Ch R = 1,3642,59,59,59
BEGIN DESCRIPTION:
Twin Creek2643660.99
END DESCRIPTION:
XS GIS Cut Line= 4
      2696790.13      6820068.70      2696791.21      6819861.51
      2696793.18      6819691.98      2696315.39      6819538.10
#Sta/Elev= 30
  4792.8  368.04  4900.5  367.22  4940.5  366.42  4957.6  366.81  4962.6  366.14
  4980.5  366.86  4990.5  366.72  4997.8  366.01  5002.8  366.01  5010.5  366.61
  5060.5  367.01  5090.5  366.35  5100.5  366.52  5120.5  365.94  5150.5  366.10
  5175.3  365.70  5175.6  365.20  5179.1  365.20  5179.3  365.70  5185.7  366.52
  5292.6  366.74  5303.2  366.51  5324.5  366.66  5345.2  367.27  5397.7  366.99
  5452.7  368.16  5502.8  367.34  5534.3  367.22  5586.8  367.17  5671.5  367.53
#Mann=3,-1,0
  4792.8   0.045       0  5175.3   0.045       0  5179.3   0.045       0
Bank Sta=5175.3,5179.3
Exp/Cntr=0.3,0.1

Type RM Length L Ch R = 1,3583,85,85,85
BEGIN DESCRIPTION:
Twin Creek2643582.69
END DESCRIPTION:
XS GIS Cut Line= 4
      2696851.78      6820086.97      2696850.38      6819862.90
      2696856.95      6819663.36      2696968.65      6819435.92
#Sta/Elev= 30
  4773.8  367.75  4855.9  366.61  4940.3  365.98  4959.8  365.98  4969.8  365.58
  5015.7  366.16  5020.7  365.80  5029.8  366.07  5049.8  365.96  5079.8  365.74
  5109.8  364.77  5129.8  365.08  5149.9  366.18  5159.9  366.21  5189.9  365.38
  5196.2  364.83  5206.8  364.50  5207.1  364.00  5210.6  364.00  5210.8  364.50
  5211.8  364.22  5222.4  364.92  5251.2  365.40  5256.7  365.02  5289.3  364.98
  5301.7  365.04  5318.6  365.68  5378.4  364.75  5431.0  364.54  5450.9  364.80
#Mann=5,-1,0
  4773.8   0.063       0  4855.9   0.045       0  4940.3    0.05       0
  5206.8    0.05       0  5210.8    0.05       0
Bank Sta=5206.8,5210.8
Exp/Cntr=0.3,0.1

Type RM Length L Ch R = 1,3498,89,89,89
BEGIN DESCRIPTION:
Twin Creek2643498.34
END DESCRIPTION:
XS GIS Cut Line= 3
      2696936.76      6820085.07      2696934.72      6819862.63
      2696942.71      6819615.21
#Sta/Elev= 30
  4775.9  366.86  4790.0  367.07  4800.0  366.77  4860.0  366.51  4890.0  365.76
  4960.0  365.16  4970.0  364.93  4990.0  364.83  4996.7  364.44  5001.7  364.44
  5010.0  364.68  5030.0  365.53  5050.0  365.74  5060.0  365.60  5080.0  365.61
  5090.0  365.17  5100.0  365.03  5110.0  364.98  5120.0  365.10  5150.1  364.78
  5160.1  363.85  5170.1  363.25  5187.0  362.72  5187.2  362.22  5190.7  362.22
  5191.0  362.72  5200.1  363.85  5210.1  364.25  5230.1  364.16  5245.9  364.38
#Mann=3,-1,0
  4775.9    0.15       0  5187.0    0.05       0  5191.0    0.15       0
Bank Sta=5187,5191
Exp/Cntr=0.3,0.1

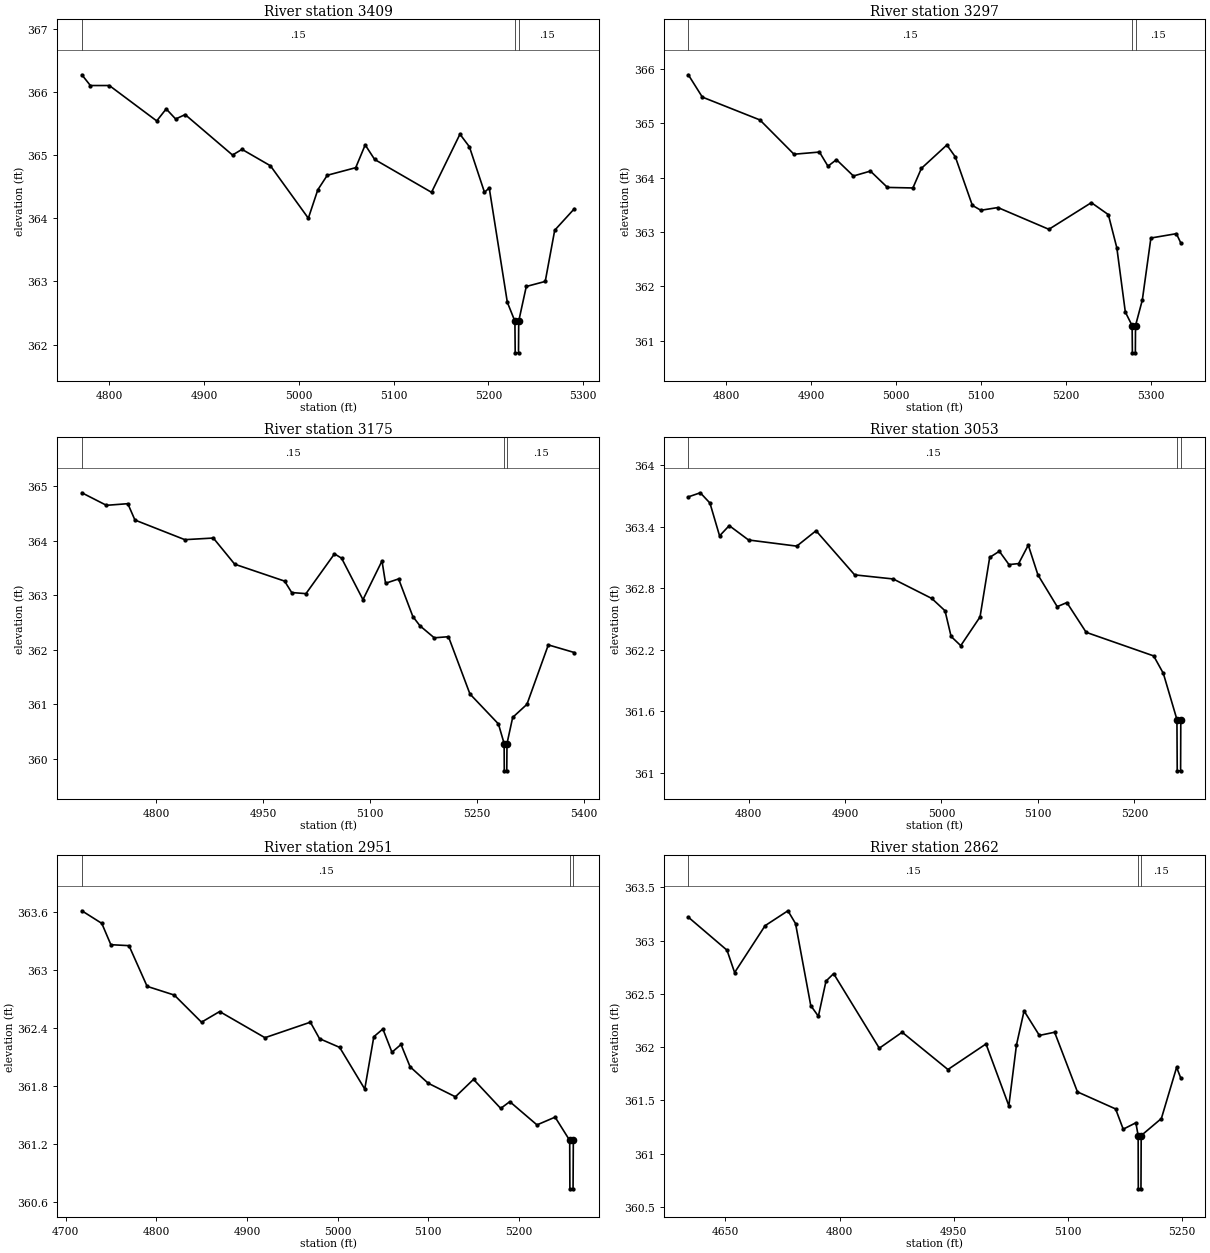
Type RM Length L Ch R = 1,3409,112,112,112
BEGIN DESCRIPTION:
Twin Creek2643409.18
END DESCRIPTION:
XS GIS Cut Line= 3
      2697023.54      6820089.99      2697023.92      6819859.22
      2697019.60      6819570.32
#Sta/Elev= 30
  4771.0  366.27  4780.0  366.10  4800.0  366.10  4850.0  365.54  4860.0  365.73
  4870.0  365.57  4880.0  365.64  4930.0  365.00  4940.0  365.09  4970.0  364.83
  5010.0  364.00  5020.0  364.45  5030.0  364.68  5060.0  364.80  5070.0  365.16
  5080.0  364.93  5140.0  364.41  5170.0  365.33  5180.0  365.13  5195.9  364.41
  5200.9  364.48  5220.0  362.67  5228.0  362.37  5228.3  361.87  5231.8  361.87
  5232.0  362.37  5240.0  362.92  5260.0  363.00  5270.0  363.81  5290.7  364.15
#Mann=3,-1,0
  4771.0    0.15       0  5228.0    0.05       0  5232.0    0.15       0
Bank Sta=5228,5232
Exp/Cntr=0.3,0.1

Type RM Length L Ch R = 1,3297,122,122,122
BEGIN DESCRIPTION:
Twin Creek2643296.78
END DESCRIPTION:
XS GIS Cut Line= 3
      2697130.69      6820105.33      2697136.34      6819860.44
      2697147.38      6819525.77
#Sta/Elev= 30
  4755.6  365.89  4772.1  365.48  4839.9  365.06  4880.0  364.43  4910.0  364.47
  4920.0  364.21  4930.0  364.33  4950.0  364.03  4970.0  364.12  4990.0  363.82
  5020.0  363.81  5030.0  364.17  5060.0  364.60  5070.0  364.38  5090.0  363.49
  5100.0  363.40  5120.1  363.45  5180.1  363.05  5230.1  363.54  5250.1  363.32
  5260.1  362.71  5270.1  361.53  5278.1  361.28  5278.4  360.78  5281.9  360.78
  5282.1  361.28  5290.1  361.75  5300.2  362.89  5330.2  362.97  5335.4  362.80
#Mann=3,-1,0
  4755.6    0.15       0  5278.1    0.05       0  5282.1    0.15       0
Bank Sta=5278.1,5282.1
Exp/Cntr=0.3,0.1

Type RM Length L Ch R = 1,3175,122,122,122
BEGIN DESCRIPTION:
Twin Creek2643174.88
END DESCRIPTION:
XS GIS Cut Line= 3
      2697254.28      6820165.47      2697258.24      6819864.91
      2697267.05      6819474.49
#Sta/Elev= 30
  4695.5  364.88  4730.0  364.65  4760.0  364.68  4770.0  364.38  4840.0  364.02
  4880.0  364.05  4910.0  363.57  4980.0  363.26  4990.0  363.05  5010.0  363.03
  5050.0  363.76  5060.0  363.68  5090.0  362.92  5116.7  363.63  5121.7  363.22
  5140.0  363.30  5160.0  362.61  5170.0  362.44  5190.0  362.22  5210.0  362.24
  5240.1  361.19  5280.1  360.64  5288.1  360.28  5288.3  359.78  5291.8  359.78
  5292.1  360.28  5300.1  360.76  5320.1  361.00  5350.1  362.09  5386.6  361.95
#Mann=3,-1,0
  4695.5    0.15       0  5288.1    0.05       0  5292.1    0.15       0
Bank Sta=5288.1,5292.1
Exp/Cntr=0.3,0.1

Type RM Length L Ch R = 1,3053,102,102,102
BEGIN DESCRIPTION:
Twin Creek2643052.78
END DESCRIPTION:
XS GIS Cut Line= 3
      2697376.08      6820123.36      2697380.42      6819857.27
      2697381.11      6819612.90
#Sta/Elev= 30
  4737.6  363.69  4750.0  363.73  4760.0  363.63  4770.0  363.31  4780.0  363.41
  4800.0  363.27  4850.0  363.21  4870.0  363.36  4910.0  362.93  4950.0  362.89
  4990.0  362.70  5003.7  362.58  5010.0  362.33  5020.0  362.24  5040.0  362.52
  5050.0  363.10  5060.0  363.16  5070.0  363.03  5080.0  363.04  5090.0  363.22
  5100.0  362.93  5120.0  362.62  5130.0  362.66  5150.0  362.37  5220.0  362.14
  5230.0  361.97  5244.1  361.52  5244.4  361.02  5247.9  361.02  5248.1  361.52
#Mann=3,-1,0
  4737.6    0.15       0  5244.1    0.05       0  5248.1    0.15       0
Bank Sta=5244.1,5248.1
Exp/Cntr=0.3,0.1

Type RM Length L Ch R = 1,2951,89,89,89
BEGIN DESCRIPTION:
Twin Creek2642951.36
END DESCRIPTION:
XS GIS Cut Line= 3
      2697473.02      6820142.95      2697481.76      6819861.28
      2697485.23      6819599.81
#Sta/Elev= 30
  4717.8  363.61  4739.8  363.48  4749.8  363.26  4769.8  363.25  4789.8  362.83
  4819.8  362.74  4849.8  362.46  4869.8  362.57  4919.8  362.30  4969.9  362.46
  4980.0  362.29  5002.2  362.20  5029.9  361.77  5039.9  362.31  5049.9  362.39
  5059.9  362.15  5069.9  362.23  5079.9  362.00  5099.9  361.83  5129.9  361.69
  5149.9  361.87  5179.9  361.57  5189.9  361.64  5219.9  361.40  5239.9  361.48
  5256.0  361.24  5256.2  360.74  5259.7  360.74  5260.0  361.24  5261.1  361.24
#Mann=3,-1,0
  4717.8    0.15       0  5256.0    0.05       0  5260.0    0.15       0
Bank Sta=5256,5260
Exp/Cntr=0.3,0.1

Type RM Length L Ch R = 1,2862,140,140,140
BEGIN DESCRIPTION:
Twin Creek2642862.16
END DESCRIPTION:
XS GIS Cut Line= 3
      2697564.06      6820261.81      2697570.75      6819863.63
      2697584.09      6819615.52
#Sta/Elev= 30
  4601.4  363.22  4652.2  362.91  4662.2  362.70  4702.2  363.14  4732.2  363.28
  4742.2  363.16  4762.2  362.39  4772.2  362.29  4782.2  362.62  4792.2  362.69
  4852.2  361.99  4882.2  362.14  4942.3  361.79  4992.3  362.03  5022.3  361.45
  5032.3  362.02  5042.3  362.34  5062.4  362.11  5082.4  362.14  5112.4  361.58
  5162.5  361.42  5172.5  361.23  5189.1  361.29  5192.1  361.17  5192.3  360.67
  5195.8  360.67  5196.1  361.17  5222.6  361.33  5242.6  361.81  5248.1  361.71
#Mann=3,-1,0
  4601.4    0.15       0  5192.1    0.05       0  5196.1    0.15       0
Bank Sta=5192.1,5196.1
Exp/Cntr=0.3,0.1

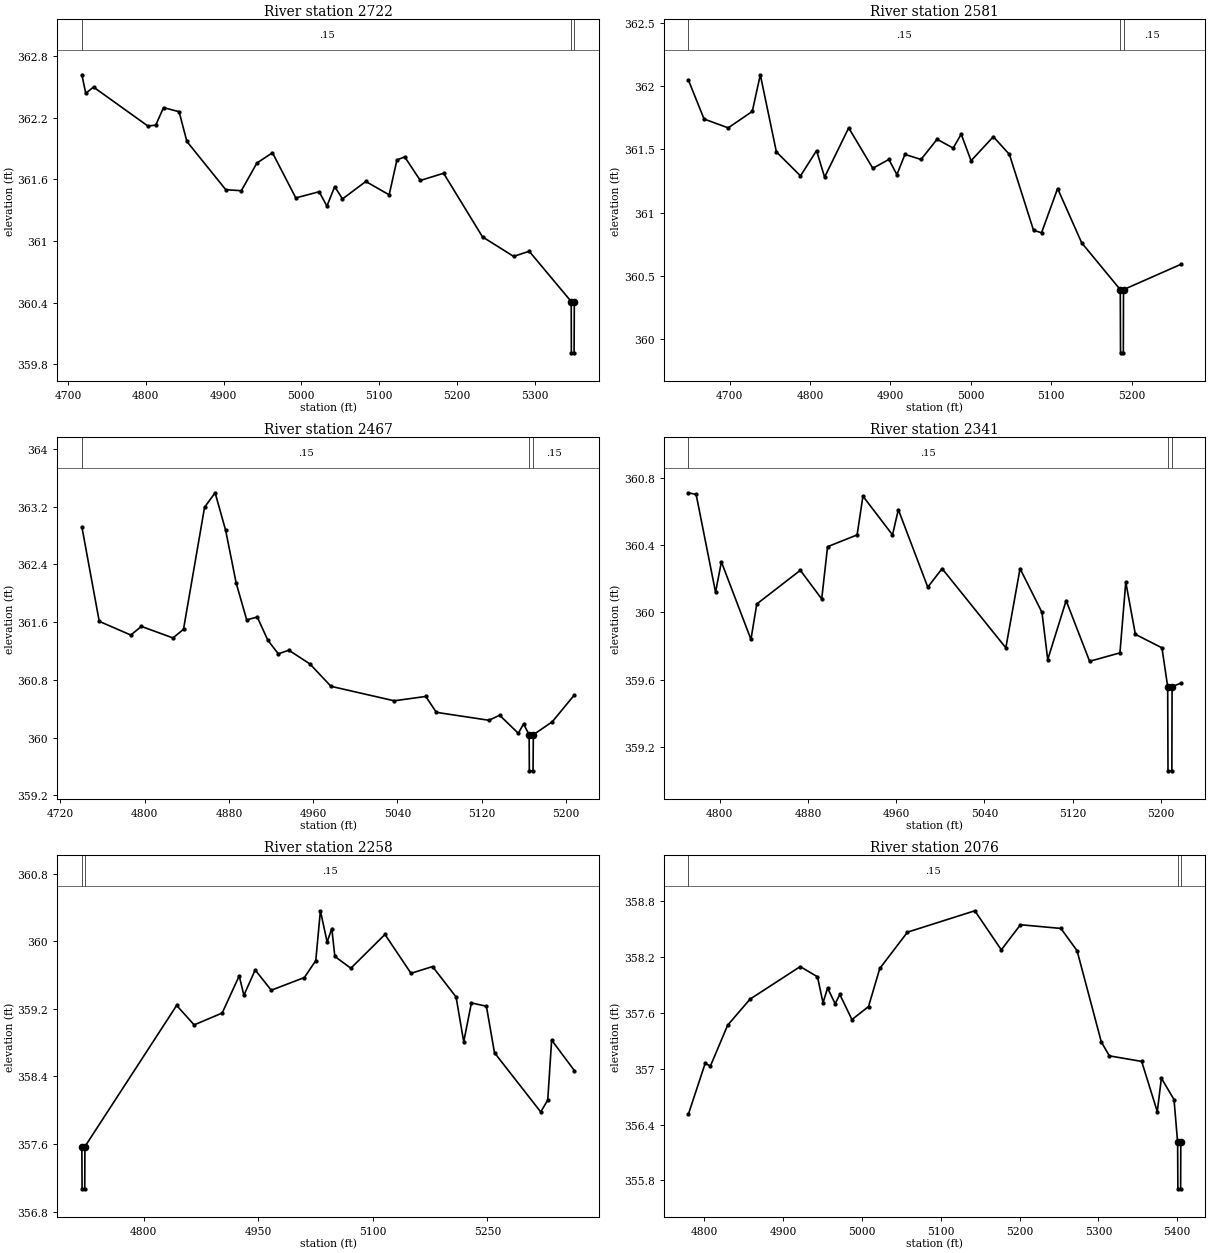
Type RM Length L Ch R = 1,2722,141,141,141
BEGIN DESCRIPTION:
Twin Creek2642721.79
END DESCRIPTION:
XS GIS Cut Line= 3
      2697674.36      6820236.00      2697675.90      6819953.27
      2697679.76      6819603.02
#Sta/Elev= 30
  4717.9  362.62  4722.9  362.44  4732.9  362.50  4802.9  362.12  4812.9  362.13
  4822.9  362.30  4842.9  362.26  4852.9  361.97  4902.9  361.50  4922.9  361.49
  4942.9  361.76  4962.9  361.86  4992.9  361.42  5022.9  361.48  5032.9  361.34
  5042.9  361.53  5052.9  361.41  5082.9  361.58  5112.9  361.45  5122.9  361.79
  5132.9  361.82  5152.9  361.59  5182.9  361.66  5232.9  361.04  5272.9  360.85
  5292.9  360.90  5346.9  360.41  5347.1  359.91  5350.6  359.91  5350.9  360.41
#Mann=3,-1,0
  4717.9    0.15       0  5346.9    0.05       0  5350.9    0.15       0
Bank Sta=5346.9,5350.9
Exp/Cntr=0.3,0.1

Type RM Length L Ch R = 1,2581,114,114,114
BEGIN DESCRIPTION:
Twin Creek2642581.25
END DESCRIPTION:
XS GIS Cut Line= 3
      2697774.89      6820210.58      2697778.07      6819858.70
      2697782.79      6819597.74
#Sta/Elev= 30
  4648.4  362.05  4668.0  361.74  4698.0  361.67  4728.0  361.80  4738.0  362.09
  4758.0  361.48  4788.0  361.29  4808.0  361.49  4818.0  361.28  4848.0  361.67
  4878.0  361.35  4898.0  361.42  4908.0  361.30  4918.0  361.46  4938.0  361.42
  4958.0  361.58  4978.0  361.51  4988.0  361.62  5000.3  361.41  5028.0  361.60
  5048.0  361.46  5078.0  360.86  5088.0  360.84  5108.0  361.19  5138.0  360.76
  5186.0  360.39  5186.3  359.89  5189.8  359.89  5190.0  360.39  5261.3  360.59
#Mann=3,-1,0
  4648.4    0.15       0  5186.0    0.05       0  5190.0    0.15       0
Bank Sta=5186,5190
Exp/Cntr=0.3,0.1

Type RM Length L Ch R = 1,2467,126,126,126
BEGIN DESCRIPTION:
Twin Creek2642466.77
END DESCRIPTION:
XS GIS Cut Line= 3
      2697854.84      6820037.51      2697858.91      6819777.18
      2697861.67      6819570.06
#Sta/Elev= 30
  4740.4  362.92  4756.9  361.61  4786.9  361.42  4796.9  361.54  4826.9  361.38
  4836.9  361.50  4856.9  363.19  4866.9  363.39  4876.9  362.87  4886.9  362.14
  4896.9  361.63  4906.9  361.67  4916.9  361.35  4926.9  361.16  4936.9  361.21
  4956.9  361.02  4976.9  360.71  5036.9  360.51  5066.9  360.57  5076.9  360.35
  5126.9  360.24  5137.0  360.31  5154.7  360.06  5159.7  360.19  5165.0  360.04
  5165.2  359.54  5168.7  359.54  5169.0  360.04  5187.0  360.22  5207.9  360.59
#Mann=3,-1,0
  4740.4    0.15       0  5165.0    0.05       0  5169.0    0.15       0
Bank Sta=5165,5169
Exp/Cntr=0.3,0.1

Type RM Length L Ch R = 1,2341,83,83,83
BEGIN DESCRIPTION:
Mapping XS 8d527a1d
END DESCRIPTION:
XS GIS Cut Line= 3
      2698029.12      6819927.78      2697958.70      6819708.60
      2697895.38      6819501.58
#Sta/Elev= 30
  4771.4  360.71  4778.5  360.70  4796.1  360.12  4801.4  360.30  4828.2  359.84
  4833.5  360.05  4873.0  360.25  4892.4  360.08  4897.7  360.39  4924.5  360.46
  4929.8  360.69  4956.6  360.46  4961.9  360.61  4988.6  360.15  5001.6  360.26
  5059.4  359.79  5072.3  360.26  5092.2  360.00  5097.4  359.72  5114.1  360.07
  5135.4  359.71  5162.9  359.76  5168.2  360.18  5176.9  359.87  5201.0  359.79
  5206.2  359.56  5206.5  359.06  5210.0  359.06  5210.2  359.56  5218.1  359.58
#Mann=3,-1,0
  4771.4    0.15       0  5206.2    0.05       0  5210.2    0.15       0
Bank Sta=5206.2,5210.2
Exp/Cntr=0.3,0.1

Type RM Length L Ch R = 1,2258,182,182,182
BEGIN DESCRIPTION:
Mapping XS a7eaa66a
END DESCRIPTION:
XS GIS Cut Line= 6
      2698244.79      6819840.87      2698154.25      6819755.21
      2698025.83      6819664.65      2697996.48      6819621.78
      2697958.22      6819484.55      2697937.17      6819317.36
#Sta/Elev= 30
  4719.2  357.57  4719.5  357.07  4723.0  357.07  4723.2  357.57  4843.3  359.24
  4866.2  359.01  4902.9  359.15  4925.2  359.59  4931.3  359.36  4946.1  359.66
  4967.1  359.42  5010.5  359.57  5025.4  359.77  5031.5  360.36  5040.3  359.99
  5046.4  360.15  5050.4  359.82  5071.3  359.68  5116.0  360.08  5150.1  359.62
  5178.3  359.70  5209.1  359.34  5219.1  358.81  5229.2  359.27  5248.8  359.23
  5259.4  358.68  5319.9  357.98  5329.1  358.12  5334.2  358.83  5363.9  358.47
#Mann=2,-1,0
  4719.2    0.05       0  4723.2    0.15       0
Bank Sta=4719.2,4723.2
Exp/Cntr=0.3,0.1

Type RM Length L Ch R = 1,2076,147,147,147
BEGIN DESCRIPTION:
Twin Creek2642076.42
END DESCRIPTION:
XS GIS Cut Line= 6
      2698365.23      6819811.94      2698261.12      6819693.30
      2698205.30      6819659.14      2698138.23      6819602.22
      2698084.67      6819532.61      2698035.47      6819312.62
#Sta/Elev= 30
  4780.0  356.51  4801.4  357.06  4808.0  357.03  4829.9  357.47  4858.3  357.75
  4921.9  358.10  4943.8  357.99  4950.8  357.71  4956.6  357.87  4966.2  357.70
  4972.1  357.80  4987.5  357.53  5008.5  357.67  5022.8  358.08  5057.9  358.47
  5143.3  358.70  5176.9  358.28  5201.2  358.55  5252.5  358.51  5273.0  358.27
  5303.7  357.29  5313.9  357.14  5354.9  357.08  5374.7  356.54  5379.9  356.90
  5395.9  356.67  5400.5  356.21  5400.8  355.71  5404.3  355.71  5404.5  356.21
#Mann=3,-1,0
  4780.0    0.15       0  5400.5    0.05       0  5404.5    0.15       0
Bank Sta=5400.5,5404.5
Exp/Cntr=0.3,0.1

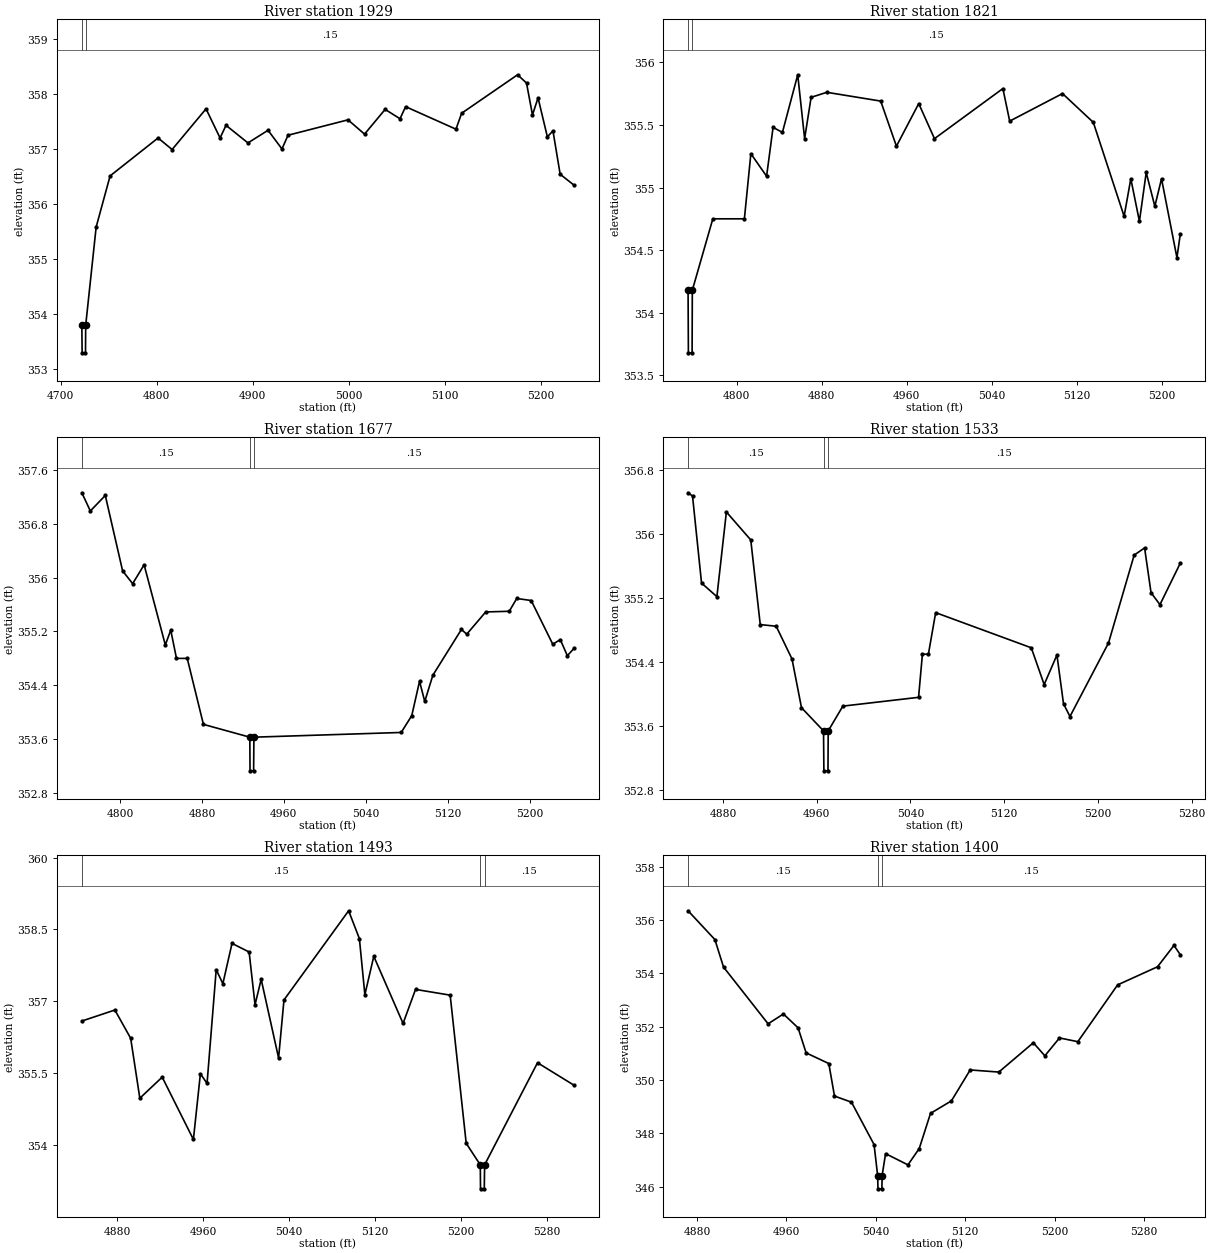
Type RM Length L Ch R = 1,1929,108,108,108
BEGIN DESCRIPTION:
Twin Creek2641910.69
END DESCRIPTION:
XS GIS Cut Line= 3
      2698488.23      6819790.19      2698319.95      6819569.16
      2698198.78      6819368.62
#Sta/Elev= 30
  4722.2  353.79  4722.5  353.29  4726.0  353.29  4726.2  353.79  4737.1  355.58
  4751.6  356.51  4801.5  357.20  4816.1  356.99  4851.4  357.73  4866.0  357.20
  4872.2  357.43  4895.0  357.11  4915.9  357.34  4930.4  357.00  4936.7  357.25
  4999.1  357.53  5016.3  357.27  5037.7  357.72  5053.2  357.55  5059.0  357.77
  5111.4  357.36  5117.3  357.65  5175.5  358.35  5184.8  358.20  5191.0  357.62
  5196.8  357.93  5206.5  357.22  5212.3  357.33  5219.8  356.54  5234.3  356.34
#Mann=2,-1,0
  4722.2    0.05       0  4726.2    0.15       0
Bank Sta=4722.2,4726.2
Exp/Cntr=0.3,0.1

Type RM Length L Ch R = 1,1821,144,144,144
BEGIN DESCRIPTION:
Twin Creek2641821.45
END DESCRIPTION:
XS GIS Cut Line= 3
      2698553.92      6819725.69      2698412.59      6819522.54
      2698280.07      6819352.19
#Sta/Elev= 30
  4754.4  354.18  4754.7  353.68  4758.2  353.68  4758.4  354.18  4777.7  354.75
  4807.4  354.75  4813.5  355.27  4828.3  355.09  4834.4  355.48  4843.2  355.44
  4857.6  355.90  4864.1  355.39  4870.2  355.72  4885.0  355.76  4935.7  355.69
  4950.5  355.33  4971.5  355.67  4986.3  355.39  5050.7  355.79  5057.1  355.53
  5106.8  355.75  5135.8  355.52  5164.8  354.77  5171.1  355.07  5179.2  354.73
  5185.6  355.12  5193.7  354.85  5200.0  355.07  5214.5  354.44  5217.7  354.63
#Mann=2,-1,0
  4754.4    0.05       0  4758.4    0.15       0
Bank Sta=4754.4,4758.4
Exp/Cntr=0.3,0.1

Type RM Length L Ch R = 1,1677,144,144,144
BEGIN DESCRIPTION:
Twin Creek2641676.86
END DESCRIPTION:
XS GIS Cut Line= 4
      2698773.86      6819562.71      2698547.84      6819489.21
      2698381.02      6819446.88      2698329.69      6819398.09
#Sta/Elev= 30
  4762.8  357.26  4771.1  356.99  4785.7  357.22  4802.6  356.10  4812.4  355.91
  4823.6  356.19  4844.3  355.00  4849.6  355.22  4855.2  354.80  4865.7  354.80
  4881.5  353.82  4926.8  353.63  4927.0  353.13  4930.5  353.13  4930.8  353.63
  5074.6  353.70  5084.9  353.95  5092.5  354.46  5097.6  354.16  5105.5  354.55
  5133.4  355.23  5138.6  355.16  5157.1  355.49  5180.1  355.50  5187.4  355.69
  5201.5  355.66  5222.6  355.01  5229.9  355.08  5236.8  354.84  5243.4  354.95
#Mann=3,-1,0
  4762.8    0.15       0  4926.8    0.05       0  4930.8    0.15       0
Bank Sta=4926.8,4930.8
Exp/Cntr=0.3,0.1

Type RM Length L Ch R = 1,1533,40,40,40
BEGIN DESCRIPTION:
Twin Creek2641532.55
END DESCRIPTION:
XS GIS Cut Line= 5
      2698745.03      6819467.51      2698627.17      6819374.61
      2698575.21      6819364.78      2698489.02      6819373.23
      2698370.17      6819427.25
#Sta/Elev= 30
  4850.2  356.52  4854.0  356.48  4861.7  355.39  4874.8  355.22  4882.9  356.28
  4903.7  355.93  4911.8  354.87  4925.4  354.85  4938.9  354.44  4947.0  353.83
  4965.8  353.54  4966.1  353.04  4969.6  353.04  4969.8  353.54  4982.3  353.85
  5046.9  353.96  5050.2  354.50  5055.3  354.50  5061.5  355.02  5143.1  354.58
  5154.1  354.12  5165.0  354.49  5170.6  353.88  5176.1  353.72  5209.0  354.64
  5230.9  355.74  5239.8  355.83  5245.3  355.27  5252.9  355.12  5270.3  355.64
#Mann=3,-1,0
  4850.2    0.15       0  4965.8    0.05       0  4969.8    0.15       0
Bank Sta=4965.8,4969.8
Exp/Cntr=0.3,0.1

Type RM Length L Ch R = 1,1493,93,93,93
BEGIN DESCRIPTION:
Twin Creek2641493.31
END DESCRIPTION:
XS GIS Cut Line= 6
      2698769.72      6819431.25      2698644.13      6819339.49
      2698612.18      6819322.32      2698540.84      6819324.18
      2698471.26      6819345.99      2698369.79      6819412.83
#Sta/Elev= 30
  4847.4  356.59  4878.1  356.82  4892.8  356.23  4901.3  354.98  4922.1  355.42
  4951.1  354.12  4957.6  355.49  4963.8  355.29  4972.3  357.66  4978.5  357.37
  4987.0  358.21  5002.9  358.03  5008.4  356.93  5014.1  357.46  5030.3  355.82
  5035.3  357.03  5095.4  358.89  5105.4  358.31  5110.5  357.14  5118.8  357.94
  5146.0  356.54  5157.6  357.25  5189.8  357.13  5204.7  354.04  5217.8  353.59
  5218.0  353.09  5221.5  353.09  5221.8  353.59  5271.0  355.72  5305.0  355.25
#Mann=3,-1,0
  4847.4    0.15       0  5217.8    0.05       0  5221.8    0.15       0
Bank Sta=5217.8,5221.8
Exp/Cntr=0.3,0.1

Type RM Length L Ch R = 1,1400,106,106,106
BEGIN DESCRIPTION:
Twin Creek2641400.43
END DESCRIPTION:
XS GIS Cut Line= 6
      2698743.58      6819327.85      2698686.63      6819279.84
      2698630.99      6819269.93      2698510.79      6819288.00
      2698428.02      6819307.79      2698368.10      6819391.26
#Sta/Elev= 30
  4872.1  356.35  4896.1  355.27  4903.8  354.24  4943.7  352.11  4957.4  352.48
  4970.5  351.96  4977.7  351.02  4998.0  350.62  5003.1  349.40  5018.3  349.17
  5038.5  347.58  5041.7  346.42  5042.0  345.92  5045.5  345.92  5045.7  346.42
  5048.8  347.24  5068.8  346.82  5078.9  347.43  5089.0  348.75  5107.7  349.22
  5124.5  350.38  5150.1  350.30  5181.0  351.40  5191.3  350.91  5204.4  351.58
  5220.8  351.44  5256.4  353.57  5292.1  354.25  5306.8  355.05  5312.5  354.70
#Mann=3,-1,0
  4872.1    0.15       0  5041.7    0.05       0  5045.7    0.15       0
Bank Sta=5041.7,5045.7
Exp/Cntr=0.3,0.1

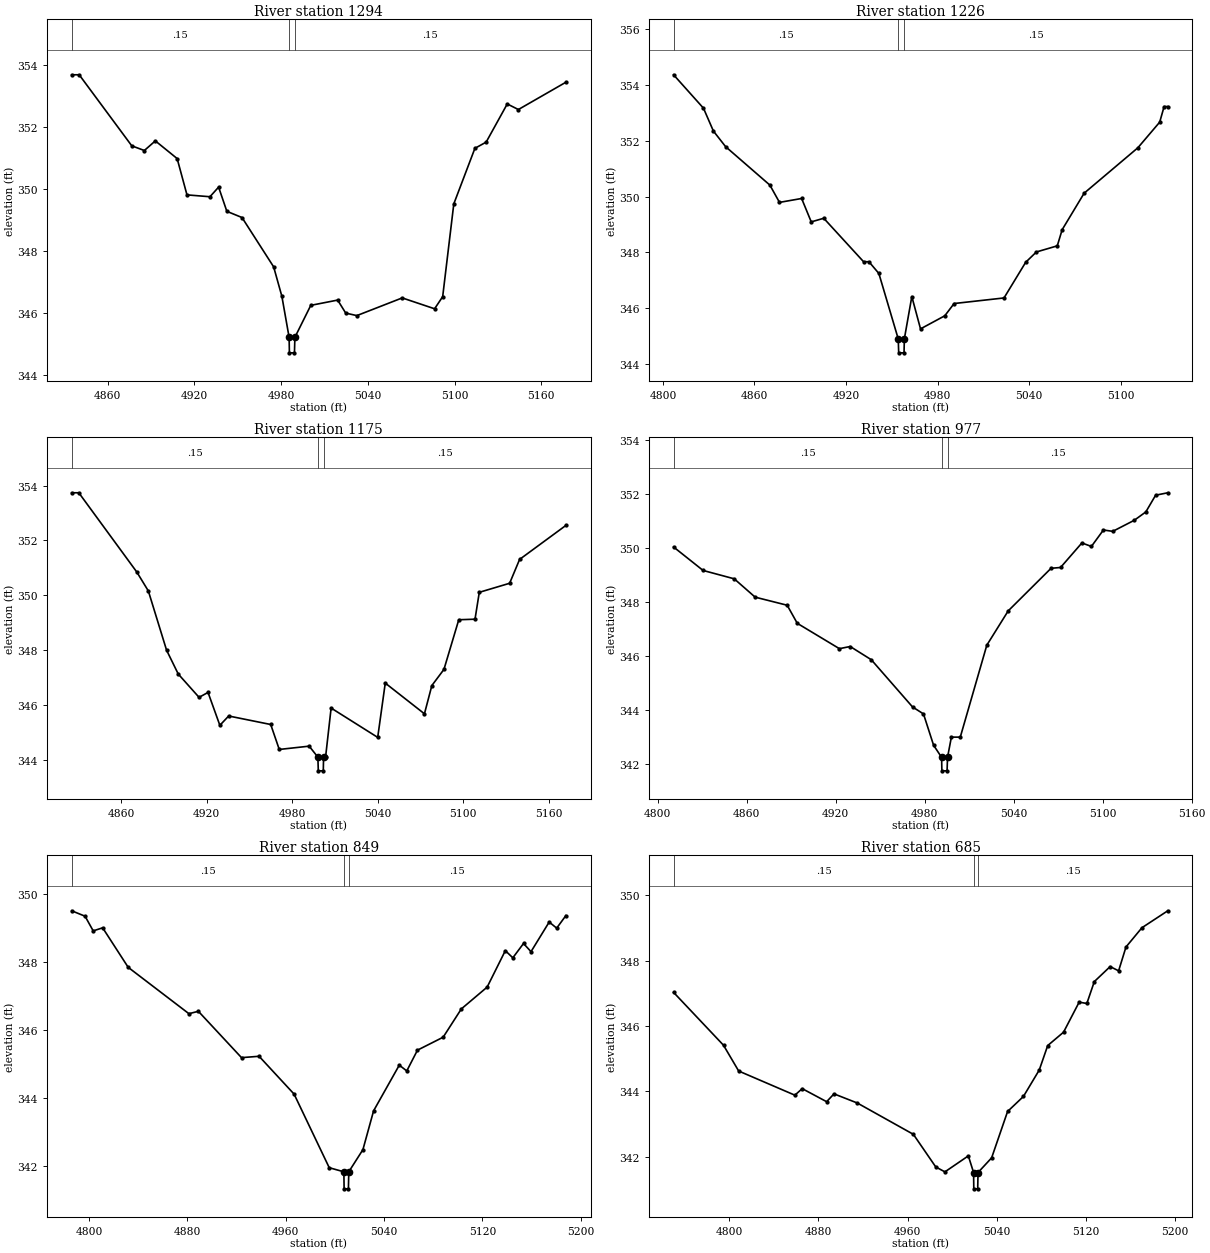
Type RM Length L Ch R = 1,1294,68,68,68
BEGIN DESCRIPTION:
Twin Creek2641294.02
END DESCRIPTION:
XS GIS Cut Line= 3
      2698720.26      6819284.35      2698574.31      6819205.75
      2698416.60      6819126.87
#Sta/Elev= 30
  4835.0  353.68  4840.2  353.68  4876.6  351.39  4885.3  351.24  4892.9  351.55
  4908.0  350.98  4914.8  349.81  4930.7  349.75  4936.7  350.06  4942.4  349.28
  4952.9  349.08  4974.8  347.49  4980.5  346.54  4985.5  345.22  4985.7  344.72
  4989.2  344.72  4989.5  345.22  5000.5  346.25  5019.1  346.42  5024.7  346.00
  5032.4  345.92  5063.8  346.49  5086.2  346.14  5091.8  346.53  5099.5  349.52
  5114.1  351.31  5121.9  351.51  5136.5  352.74  5144.2  352.56  5177.1  353.44
#Mann=3,-1,0
  4835.0    0.15       0  4985.5    0.05       0  4989.5    0.15       0
Bank Sta=4985.5,4989.5
Exp/Cntr=0.3,0.1

Type RM Length L Ch R = 1,1226,51,51,51
BEGIN DESCRIPTION:
Twin Creek2641225.99
END DESCRIPTION:
XS GIS Cut Line= 5
      2698726.63      6819277.90      2698625.54      6819199.45
      2698592.30      6819141.56      2698574.35      6819090.07
      2698516.62      6819042.89
#Sta/Elev= 30
  4807.0  354.37  4826.6  353.17  4833.1  352.35  4841.1  351.79  4870.1  350.41
  4876.4  349.79  4890.9  349.93  4897.2  349.09  4905.4  349.22  4931.5  347.66
  4935.0  347.66  4941.5  347.24  4954.2  344.89  4954.5  344.39  4958.0  344.39
  4958.2  344.89  4963.1  346.41  4968.8  345.25  4984.7  345.72  4990.8  346.16
  5023.5  346.36  5037.7  347.64  5044.7  348.01  5058.4  348.23  5061.6  348.81
  5076.0  350.12  5111.2  351.75  5125.5  352.67  5128.4  353.23  5130.8  353.23
#Mann=3,-1,0
  4807.0    0.15       0  4954.2    0.05       0  4958.2    0.15       0
Bank Sta=4954.2,4958.2
Exp/Cntr=0.3,0.1

Type RM Length L Ch R = 1,1175,198,198,198
BEGIN DESCRIPTION:
Twin Creek2641174.8
END DESCRIPTION:
XS GIS Cut Line= 5
      2698737.50      6819253.93      2698656.13      6819146.46
      2698631.95      6819110.41      2698601.13      6819010.14
      2698556.48      6818964.57
#Sta/Elev= 30
  4825.3  353.74  4830.3  353.74  4871.0  350.85  4879.1  350.16  4891.9  348.00
  4900.1  347.13  4914.7  346.28  4921.0  346.46  4929.3  345.26  4935.5  345.60
  4965.0  345.29  4971.0  344.38  4992.0  344.50  4998.1  344.10  4998.4  343.60
  5001.9  343.60  5002.1  344.10  5003.5  344.10  5007.4  345.89  5040.1  344.82
  5045.4  346.80  5072.9  345.68  5078.1  346.71  5086.6  347.30  5097.0  349.11
  5108.4  349.13  5111.4  350.11  5132.7  350.44  5139.7  351.31  5172.2  352.55
#Mann=3,-1,0
  4825.3    0.15       0  4998.1    0.05       0  5002.1    0.15       0
Bank Sta=4998.1,5002.1
Exp/Cntr=0.3,0.1

Type RM Length L Ch R = 1,977,128,128,128
BEGIN DESCRIPTION:
Twin Creek264977.47
END DESCRIPTION:
XS GIS Cut Line= 3
      2698815.48      6819089.54      2698686.32      6818949.16
      2698574.36      6818861.11
#Sta/Elev= 30
  4810.7  350.03  4830.6  349.16  4851.6  348.85  4865.7  348.17  4887.3  347.87
  4894.1  347.20  4922.5  346.26  4929.8  346.34  4944.0  345.85  4971.8  344.10
  4979.2  343.84  4986.0  342.68  4991.4  342.23  4991.6  341.73  4995.1  341.73
  4995.4  342.23  4998.0  342.98  5004.0  342.98  5021.9  346.39  5036.3  347.66
  5065.2  349.24  5071.6  349.27  5086.0  350.18  5092.4  350.05  5100.5  350.66
  5106.8  350.61  5121.3  351.02  5129.1  351.33  5135.7  351.95  5143.9  352.04
#Mann=3,-1,0
  4810.7    0.15       0  4991.4    0.05       0  4995.4    0.15       0
Bank Sta=4991.4,4995.4
Exp/Cntr=0.3,0.1

Type RM Length L Ch R = 1,849,164,164,164
BEGIN DESCRIPTION:
Twin Creek264849.33
END DESCRIPTION:
XS GIS Cut Line= 3
      2698936.06      6818995.89      2698772.95      6818855.86
      2698619.66      6818748.36
#Sta/Elev= 30
  4785.8  349.50  4796.7  349.34  4803.3  348.91  4811.0  349.00  4831.8  347.84
  4881.2  346.48  4888.9  346.55  4924.0  345.19  4938.3  345.23  4966.8  344.12
  4995.4  341.96  5007.3  341.84  5007.5  341.34  5011.0  341.34  5011.3  341.84
  5022.8  342.49  5031.5  343.63  5052.4  344.97  5058.5  344.80  5067.2  345.41
  5088.1  345.79  5102.9  346.62  5123.9  347.26  5138.7  348.33  5144.8  348.12
  5153.5  348.54  5159.6  348.30  5174.4  349.17  5180.5  348.99  5188.0  349.36
#Mann=3,-1,0
  4785.8    0.15       0  5007.3    0.05       0  5011.3    0.15       0
Bank Sta=5007.3,5011.3
Exp/Cntr=0.3,0.1

Type RM Length L Ch R = 1,685,175,175,175
BEGIN DESCRIPTION:
Twin Creek264684.6
END DESCRIPTION:
XS GIS Cut Line= 3
      2698955.13      6818884.87      2698789.46      6818693.88
      2698646.20      6818568.35
#Sta/Elev= 30
  4750.1  347.03  4794.9  345.41  4808.5  344.62  4858.9  343.88  4865.5  344.08
  4887.4  343.68  4894.0  343.92  4914.9  343.64  4965.2  342.68  4985.3  341.68
  4993.5  341.53  5014.5  342.02  5019.2  341.51  5019.4  341.01  5022.9  341.01
  5023.2  341.51  5035.4  341.96  5049.7  343.38  5063.9  343.84  5078.1  344.65
  5085.7  345.40  5099.9  345.81  5113.9  346.73  5120.8  346.69  5127.5  347.36
  5141.7  347.82  5149.3  347.69  5155.9  348.42  5170.2  349.01  5193.4  349.53
#Mann=3,-1,0
  4750.1    0.15       0  5019.2    0.05       0  5023.2    0.15       0
Bank Sta=5019.2,5023.2
Exp/Cntr=0.3,0.1