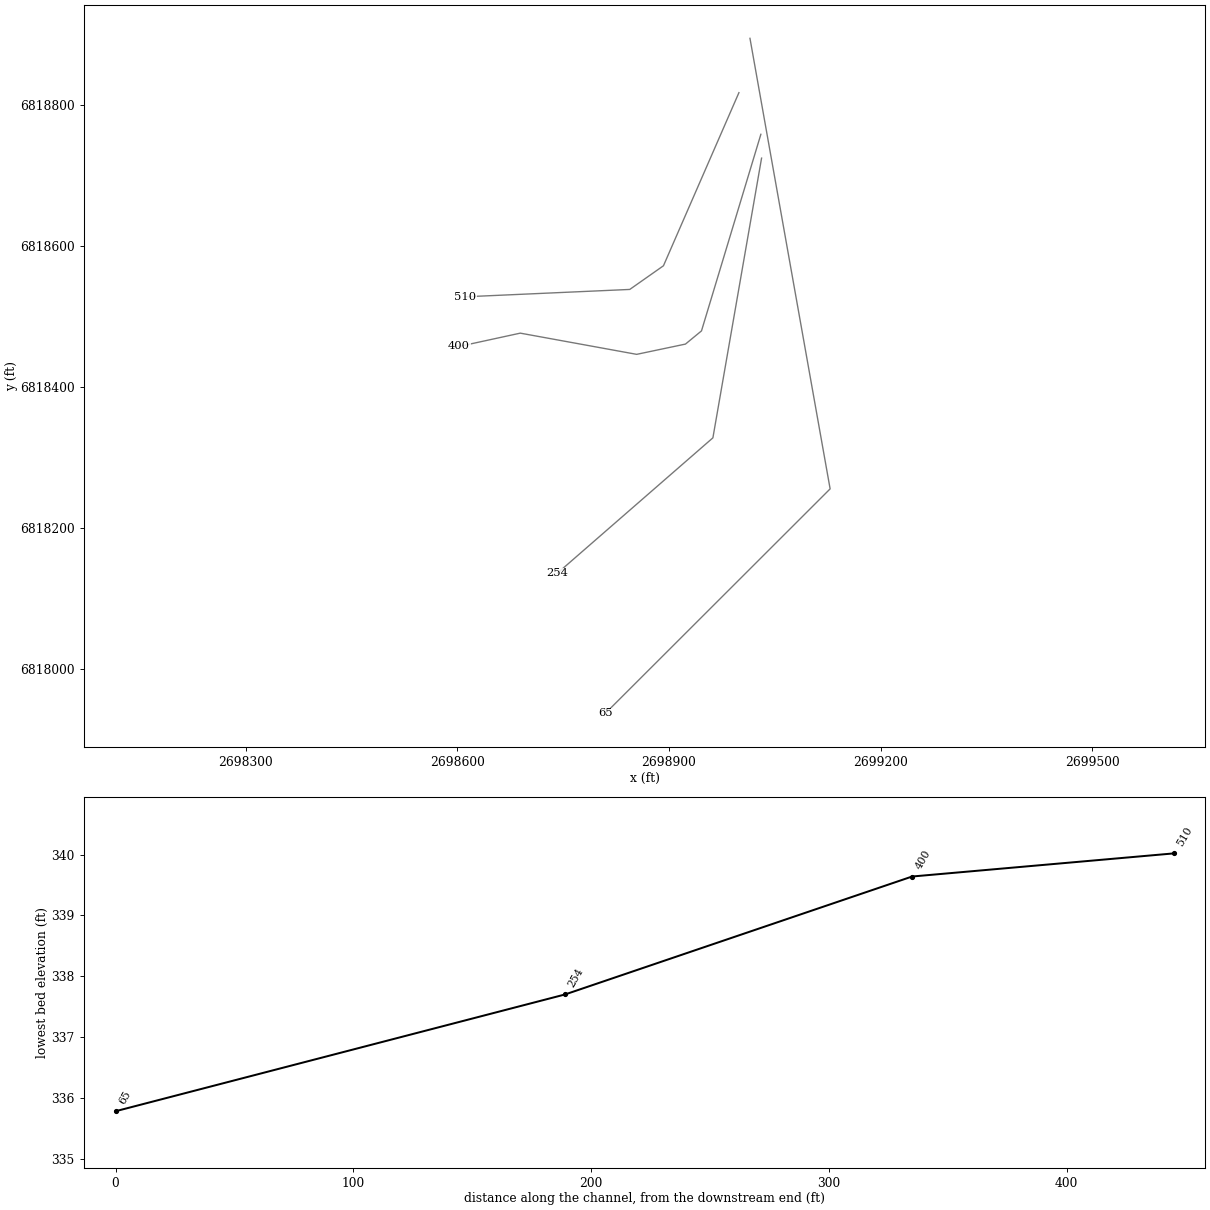
HEC-RAS study Twin Creek264.prj: Twin Creek264 Base Level Engineering

--- Twin Creek264.g01 (geometry) --- (continued)

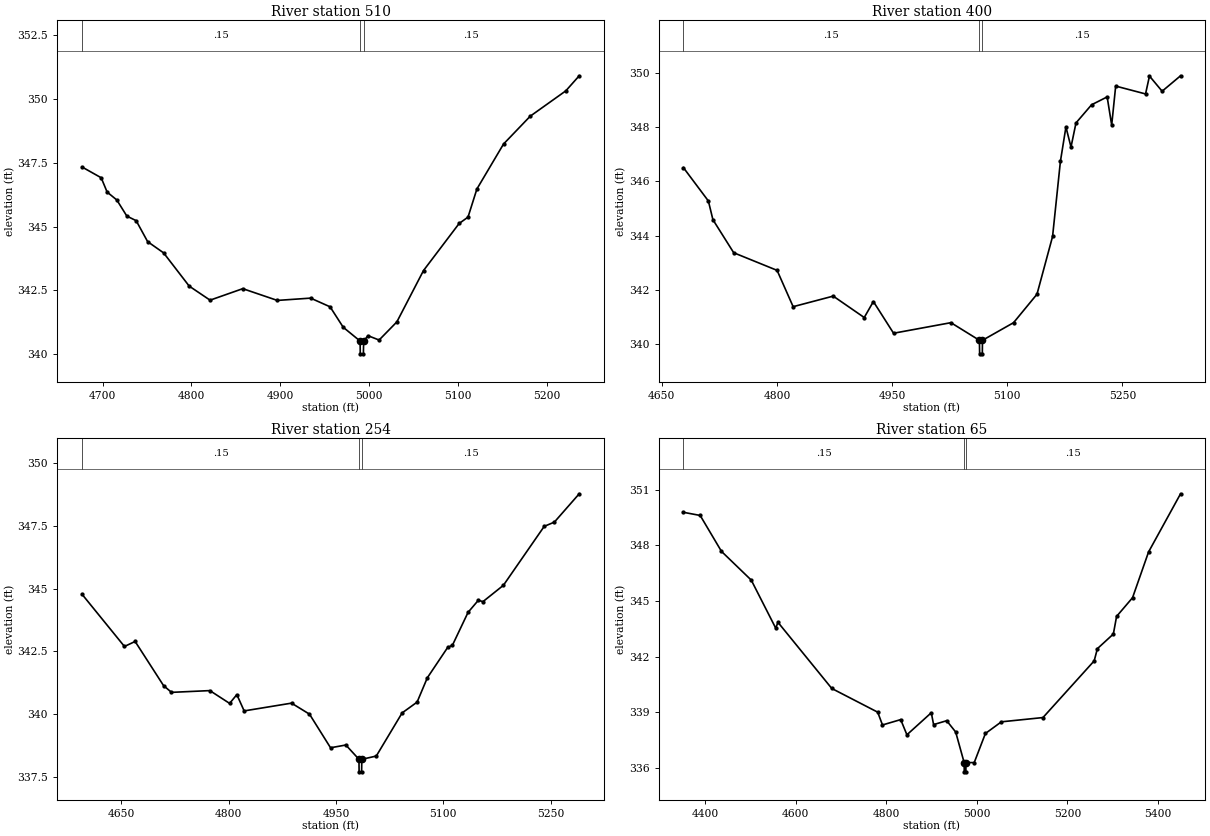
Type RM Length L Ch R = 1,510,110,110,110
BEGIN DESCRIPTION:
Twin Creek264510
END DESCRIPTION:
XS GIS Cut Line= 4
      2698999.11      6818816.82      2698892.17      6818571.51
      2698844.42      6818537.96      2698610.92      6818527.51
#Sta/Elev= 30
  4677.0  347.33  4698.5  346.91  4705.2  346.35  4716.1  346.04  4727.4  345.41
  4737.9  345.23  4750.8  344.41  4768.8  343.97  4797.6  342.67  4821.1  342.12
  4857.9  342.57  4896.8  342.11  4934.3  342.20  4956.2  341.86  4971.0  341.06
  4990.0  340.52  4990.2  340.02  4993.7  340.02  4994.0  340.52  4998.9  340.73
  5011.4  340.56  5031.4  341.27  5061.4  343.28  5101.5  345.12  5111.5  345.37
  5121.5  346.47  5151.5  348.23  5181.6  349.32  5221.6  350.31  5236.7  350.90
#Mann=3,-1,0
  4677.0    0.15       0  4990.0    0.05       0  4994.0    0.15       0
Bank Sta=4990,4994
Exp/Cntr=0.3,0.1

Type RM Length L Ch R = 1,400,146,146,146
BEGIN DESCRIPTION:
Twin Creek264400.28
END DESCRIPTION:
XS GIS Cut Line= 6
      2699030.21      6818757.79      2698946.07      6818479.21
      2698923.34      6818460.51      2698854.21      6818445.97
      2698689.26      6818476.02      2698602.54      6818457.18
#Sta/Elev= 30
  4678.2  346.51  4710.7  345.28  4716.6  344.59  4743.7  343.37  4800.2  342.72
  4821.1  341.38  4873.3  341.77  4913.7  340.98  4925.6  341.57  4951.9  340.40
  5026.6  340.79  5063.7  340.14  5064.0  339.64  5067.5  339.64  5067.7  340.14
  5108.2  340.79  5138.7  341.84  5159.0  343.97  5169.2  346.74  5176.4  348.01
  5183.0  347.27  5189.5  348.16  5209.8  348.83  5230.1  349.12  5236.0  348.08
  5241.2  349.52  5280.1  349.23  5285.2  349.89  5301.7  349.33  5325.7  349.90
#Mann=3,-1,0
  4678.2    0.15       0  5063.7    0.05       0  5067.7    0.15       0
Bank Sta=5063.7,5067.7
Exp/Cntr=0.3,0.1

Type RM Length L Ch R = 1,254,189,189,189
BEGIN DESCRIPTION:
Twin Creek264253.52
END DESCRIPTION:
XS GIS Cut Line= 3
      2699031.21      6818724.03      2698962.23      6818327.65
      2698741.85      6818135.84
#Sta/Elev= 30
  4595.3  344.78  4654.5  342.70  4669.4  342.90  4709.1  341.14  4720.2  340.87
  4773.8  340.94  4801.4  340.43  4811.5  340.78  4821.7  340.13  4887.9  340.44
  4913.0  340.00  4942.4  338.66  4963.8  338.77  4982.1  338.20  4982.3  337.70
  4985.8  337.70  4986.1  338.20  5006.3  338.33  5042.4  340.05  5063.3  340.48
  5077.6  341.45  5106.0  342.66  5112.7  342.75  5134.5  344.06  5148.8  344.54
  5155.4  344.49  5183.9  345.14  5240.9  347.49  5255.1  347.66  5289.8  348.79
#Mann=3,-1,0
  4595.3    0.15       0  4982.1    0.05       0  4986.1    0.15       0
Bank Sta=4982.1,4986.1
Exp/Cntr=0.3,0.1

Type RM Length L Ch R = 1,65,0,0,0
BEGIN DESCRIPTION:
Twin Creek26465.285
END DESCRIPTION:
XS GIS Cut Line= 3
      2699014.77      6818893.80      2699128.36      6818255.33
      2698809.83      6817937.18
#Sta/Elev= 30
  4351.5  349.79  4388.5  349.62  4435.6  347.68  4501.4  346.13  4555.4  343.54
  4560.5  343.85  4679.4  340.28  4780.9  339.00  4791.4  338.31  4831.7  338.60
  4845.4  337.78  4899.3  338.97  4904.4  338.33  4933.3  338.54  4953.2  337.93
  4971.9  336.28  4972.2  335.78  4975.7  335.78  4975.9  336.28  4994.2  336.28
  5018.9  337.85  5054.2  338.48  5146.1  338.71  5259.3  341.77  5266.4  342.43
  5301.7  343.22  5308.8  344.17  5344.1  345.18  5379.5  347.65  5450.2  350.79
#Mann=3,-1,0
  4351.5    0.15       0  4971.9    0.05       0  4975.9    0.15       0
Bank Sta=4971.9,4975.9
Exp/Cntr=0.3,0.1

Chan Stop Cuts=-1