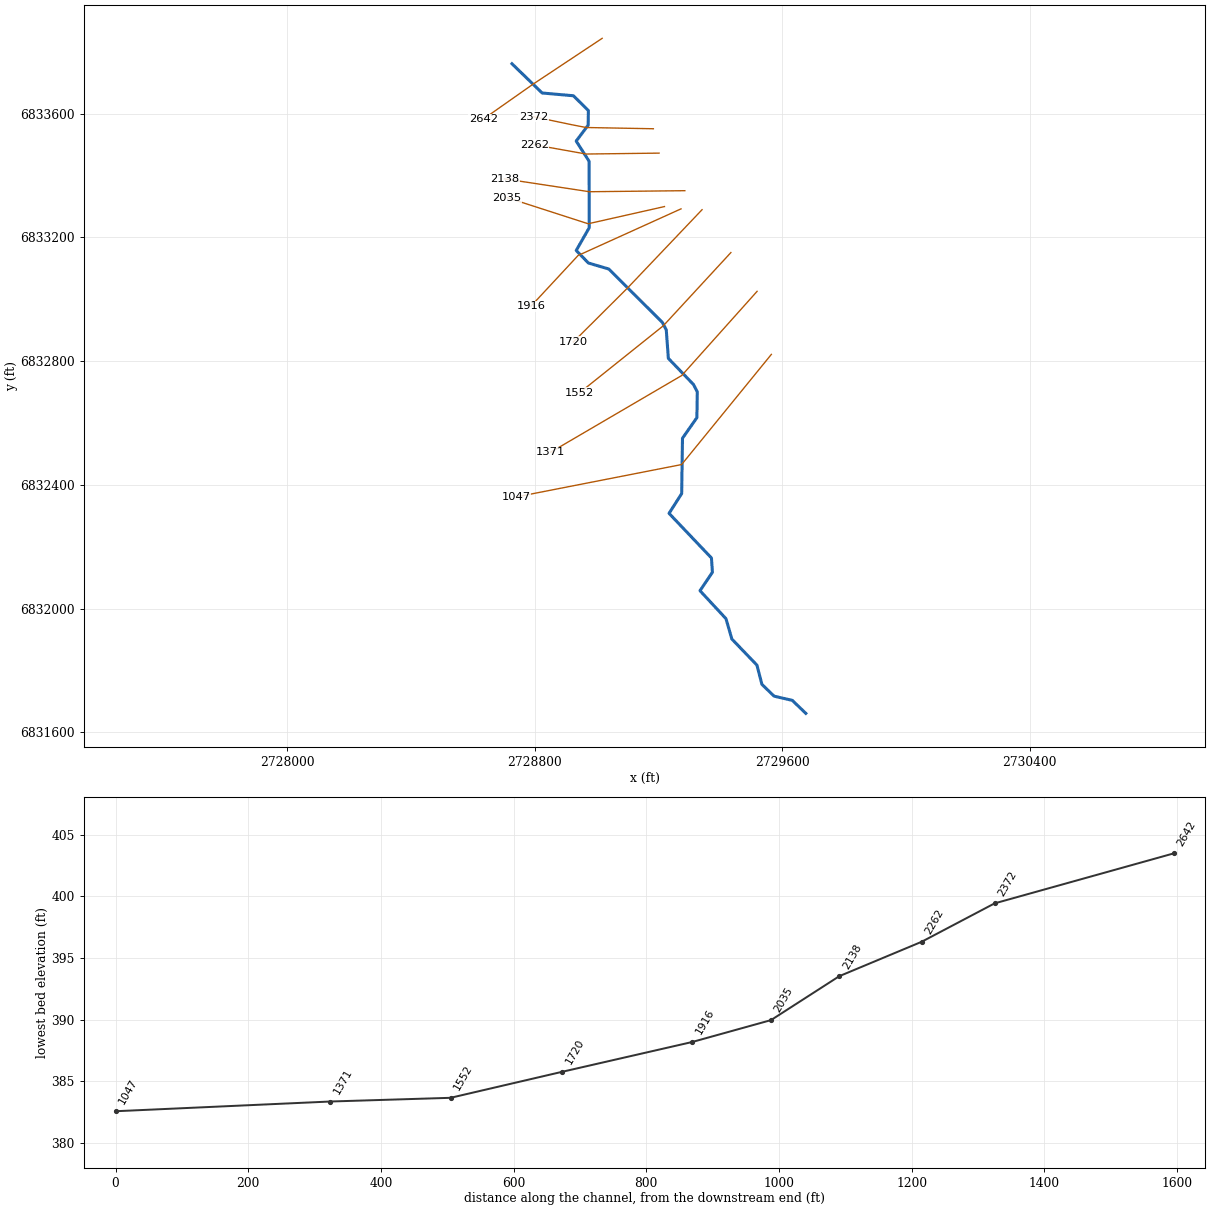
--- Twin Creek265.prj (project) ---

Proj Title=Twin Creek265 Base Level Engineering
Current Plan=p01
Default Exp/Contr=0.3,0.1
English Units
Geom File=g01
Flow File=f01
Plan File=p01
BEGIN DESCRIPTION:
Twin Creek265
END DESCRIPTION:

--- Twin Creek265.p01 (plan) ---

Plan Title=Multiple Run
Short Identifier=Multiple
Geom File=g01
Flow File=f01
Subcritical Flow
K Sum by GR= 0
Std Step Tol= 0.01
Critical Tol= 0.01
Num of Std Step Trials= 20
Max Error Tol= 0.3
Flow Tol Ratio= 0.001
Split Flow NTrial= 30
Split Flow Tol= 0.02
Split Flow Ratio= 0.02
Log Output Level= 0
Friction Slope Method= 1
Unsteady Friction Slope Method= 2
Unsteady Bridges Friction Slope Method= 1
Parabolic Critical Depth
Global Vel Dist=  1 , 1 , 1
Global Log Level= 0
CheckData=True
Encroach Param= -1, 0, 0, 0
BEGIN DESCRIPTION:
Multiple Run
END DESCRIPTION:

--- Twin Creek265.f01 (steady flow) ---

Flow Title=Multiple
Number of Profiles=7
Profile Names=10-year,25-year,50-year,1pct_min,100-year,1pct_plu,500-year
River Rch & RM= Twin Creek265,Reach-1,2642
     376     491     581     342     683    1362     940
Boundary for River Rch & Prof#=Twin Creek265,Reach-1,1
Up Type=0
Dn Type=3
Dn Slope=0.005
Boundary for River Rch & Prof#=Twin Creek265,Reach-1,2
Up Type=0
Dn Type=3
Dn Slope=0.005
Boundary for River Rch & Prof#=Twin Creek265,Reach-1,3
Up Type=0
Dn Type=3
Dn Slope=0.005
Boundary for River Rch & Prof#=Twin Creek265,Reach-1,4
Up Type=0
Dn Type=3
Dn Slope=0.005
Boundary for River Rch & Prof#=Twin Creek265,Reach-1,5
Up Type=0
Dn Type=3
Dn Slope=0.005
Boundary for River Rch & Prof#=Twin Creek265,Reach-1,6
Up Type=0
Dn Type=3
Dn Slope=0.005
Boundary for River Rch & Prof#=Twin Creek265,Reach-1,7
Up Type=0
Dn Type=3
Dn Slope=0.005

--- Twin Creek265.g01 (geometry) ---

Geom Title=Existing Conditions

River Reach=Twin Creek265,Reach-1
Reach XY= 30
      2728726.00      6833761.00      2728823.55      6833666.46
      2728924.78      6833657.48      2728972.94      6833609.60
      2728972.44      6833562.68      2728933.59      6833511.01
      2728975.34      6833445.84      2728975.81      6833230.98
      2728933.69      6833157.33      2728973.15      6833116.85
      2729039.18      6833097.37      2729212.60      6832924.30
      2729224.83      6832900.52      2729231.54      6832808.58
      2729312.63      6832724.29      2729325.06      6832700.52
      2729323.84      6832616.98      2729277.22      6832550.50
      2729274.61      6832371.43      2729233.79      6832307.58
      2729370.88      6832163.29      2729374.01      6832117.05
      2729333.83      6832057.60      2729417.80      6831967.05
      2729436.80      6831901.33      2729517.82      6831817.02
      2729534.03      6831754.66      2729573.39      6831716.61
      2729632.11      6831703.05      2729676.00      6831661.00

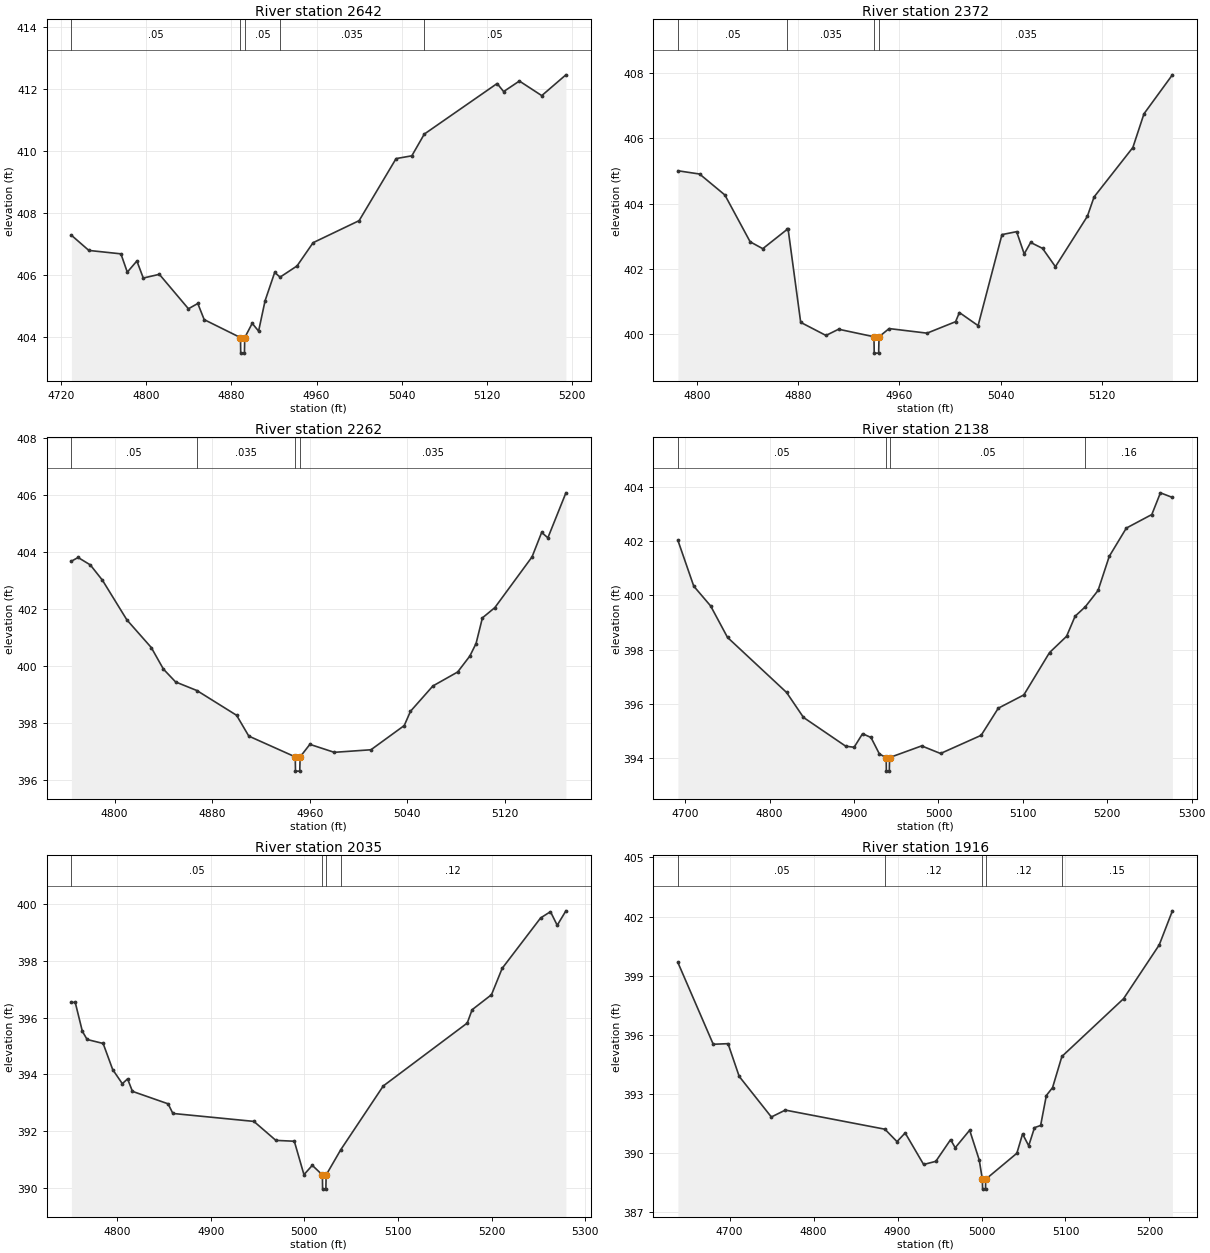
Type RM Length L Ch R = 1,2642,270,270,270
BEGIN DESCRIPTION:
Twin Creek2652641.588
END DESCRIPTION:
XS GIS Cut Line= 3
      2729017.59      6833843.14      2728792.43      6833693.77
      2728633.54      6833582.12
#Sta/Elev= 30
  4729.8  407.29  4746.2  406.80  4776.3  406.69  4782.3  406.10  4791.3  406.46
  4797.3  405.91  4812.4  406.03  4839.7  404.92  4848.5  405.09  4854.5  404.57
  4888.6  403.99  4888.8  403.49  4892.3  403.49  4892.6  403.99  4899.6  404.45
  4905.6  404.20  4911.7  405.18  4920.7  406.09  4925.8  405.94  4941.7  406.30
  4956.8  407.05  5000.0  407.76  5034.7  409.76  5049.5  409.85  5061.2  410.55
  5129.6  412.18  5135.7  411.92  5150.5  412.26  5171.5  411.79  5194.2  412.46
#Mann=5,-1,0
  4729.8    0.05       0  4888.6   0.035       0  4892.6    0.05       0
  4925.8   0.035       0  5061.2    0.05       0
Bank Sta=4888.6,4892.6
Exp/Cntr=0.3,0.1

Type RM Length L Ch R = 1,2372,110,110,110
BEGIN DESCRIPTION:
Twin Creek2652371.83
END DESCRIPTION:
XS GIS Cut Line= 4
      2729183.15      6833550.87      2728965.91      6833554.87
      2728923.85      6833562.97      2728795.34      6833589.84
#Sta/Elev= 30
  4784.6  405.00  4801.8  404.90  4821.8  404.26  4841.8  402.83  4851.8  402.62
  4871.1  403.21  4871.8  403.23  4881.8  400.37  4901.8  399.97  4911.8  400.16
  4939.8  399.93  4940.0  399.43  4943.5  399.43  4943.8  399.93  4951.8  400.18
  4981.8  400.04  5004.4  400.39  5007.4  400.67  5022.2  400.27  5041.1  403.05
  5052.7  403.14  5058.7  402.46  5063.8  402.81  5073.2  402.63  5083.4  402.07
  5108.7  403.61  5114.0  404.20  5144.7  405.71  5153.5  406.74  5176.0  407.93
#Mann=4,-1,0
  4784.6    0.05       0  4871.1   0.035       0  4939.8   0.035       0
  4943.8   0.035       0
Bank Sta=4939.8,4943.8
Exp/Cntr=0.3,0.1

Type RM Length L Ch R = 1,2262,124,124,124
BEGIN DESCRIPTION:
Twin Creek2652261.86
END DESCRIPTION:
XS GIS Cut Line= 3
      2729201.54      6833472.07      2728965.72      6833469.14
      2728798.60      6833498.99
#Sta/Elev= 30
  4764.5  403.68  4770.0  403.81  4780.0  403.55  4790.0  403.01  4810.0  401.62
  4830.0  400.65  4840.0  399.89  4850.0  399.44  4867.4  399.14  4900.0  398.27
  4910.0  397.54  4948.1  396.81  4948.3  396.31  4951.8  396.31  4952.1  396.81
  4960.1  397.25  4980.1  396.97  5010.2  397.06  5037.5  397.91  5042.6  398.41
  5061.0  399.30  5081.3  399.79  5091.3  400.35  5096.4  400.79  5101.6  401.69
  5111.8  402.05  5142.3  403.83  5150.2  404.69  5155.3  404.50  5170.1  406.08
#Mann=4,-1,0
  4764.5    0.05       0  4867.4   0.035       0  4948.1   0.035       0
  4952.1   0.035       0
Bank Sta=4948.1,4952.1
Exp/Cntr=0.3,0.1

Type RM Length L Ch R = 1,2138,103,103,103
BEGIN DESCRIPTION:
Twin Creek2652137.85
END DESCRIPTION:
XS GIS Cut Line= 3
      2729284.75      6833350.64      2728976.29      6833347.30
      2728702.01      6833388.92
#Sta/Elev= 30
  4691.3  402.03  4710.1  400.34  4730.1  399.61  4750.1  398.45  4820.1  396.42
  4840.1  395.50  4890.1  394.44  4900.1  394.40  4910.1  394.90  4920.1  394.76
  4930.1  394.15  4938.1  394.02  4938.3  393.52  4941.8  393.52  4942.1  394.02
  4980.1  394.45  5002.5  394.17  5050.6  394.84  5070.9  395.84  5101.2  396.33
  5131.6  397.89  5151.8  398.49  5161.9  399.23  5174.0  399.58  5189.1  400.18
  5202.4  401.44  5222.6  402.48  5252.8  402.98  5263.0  403.78  5277.2  403.61
#Mann=4,-1,0
  4691.3    0.05       0  4938.1    0.05       0  4942.1    0.05       0
  5174.0    0.16       0
Bank Sta=4938.1,4942.1
Exp/Cntr=0.3,0.1

Type RM Length L Ch R = 1,2035,119,119,119
BEGIN DESCRIPTION:
Twin Creek2652035.14
END DESCRIPTION:
XS GIS Cut Line= 3
      2729219.04      6833299.31      2728972.36      6833243.73
      2728710.31      6833328.24
#Sta/Elev= 30
  4751.2  396.54  4755.3  396.54  4762.9  395.52  4768.0  395.23  4785.1  395.09
  4795.3  394.17  4805.6  393.67  4811.2  393.84  4816.4  393.40  4854.5  392.96
  4859.6  392.62  4946.1  392.34  4969.6  391.67  4989.3  391.64  4999.6  390.46
  5008.5  390.79  5019.3  390.45  5019.5  389.95  5023.0  389.95  5023.3  390.45
  5038.9  391.34  5084.3  393.59  5174.0  395.81  5179.2  396.28  5199.9  396.81
  5211.3  397.74  5252.4  399.52  5262.9  399.74  5270.1  399.26  5279.4  399.77
#Mann=4,-1,0
  4751.2    0.05       0  5019.3    0.05       0  5023.3    0.05       0
  5038.9    0.12       0
Bank Sta=5019.3,5023.3
Exp/Cntr=0.3,0.1

Type RM Length L Ch R = 1,1916,196,196,196
BEGIN DESCRIPTION:
Twin Creek2651916.13
END DESCRIPTION:
XS GIS Cut Line= 3
      2729272.48      6833291.91      2728939.86      6833141.22
      2728787.57      6832977.45
#Sta/Elev= 30
  4638.5  399.67  4680.6  395.52  4698.2  395.55  4711.5  393.89  4749.8  391.83
  4766.4  392.18  4885.0  391.21  4899.4  390.58  4909.1  391.02  4931.1  389.42
  4945.6  389.58  4963.2  390.68  4968.7  390.27  4985.9  391.16  4997.3  389.65
  5001.0  388.67  5001.3  388.17  5004.8  388.17  5005.0  388.67  5042.1  389.99
  5048.9  390.97  5056.2  390.37  5063.1  391.29  5070.4  391.40  5077.2  392.92
  5084.6  393.32  5095.7  394.90  5169.1  397.83  5211.6  400.56  5227.3  402.29
#Mann=5,-1,0
  4638.5    0.05       0  4885.0    0.12       0  5001.0    0.07       0
  5005.0    0.12       0  5095.7    0.15       0
Bank Sta=5001,5005
Exp/Cntr=0.3,0.1

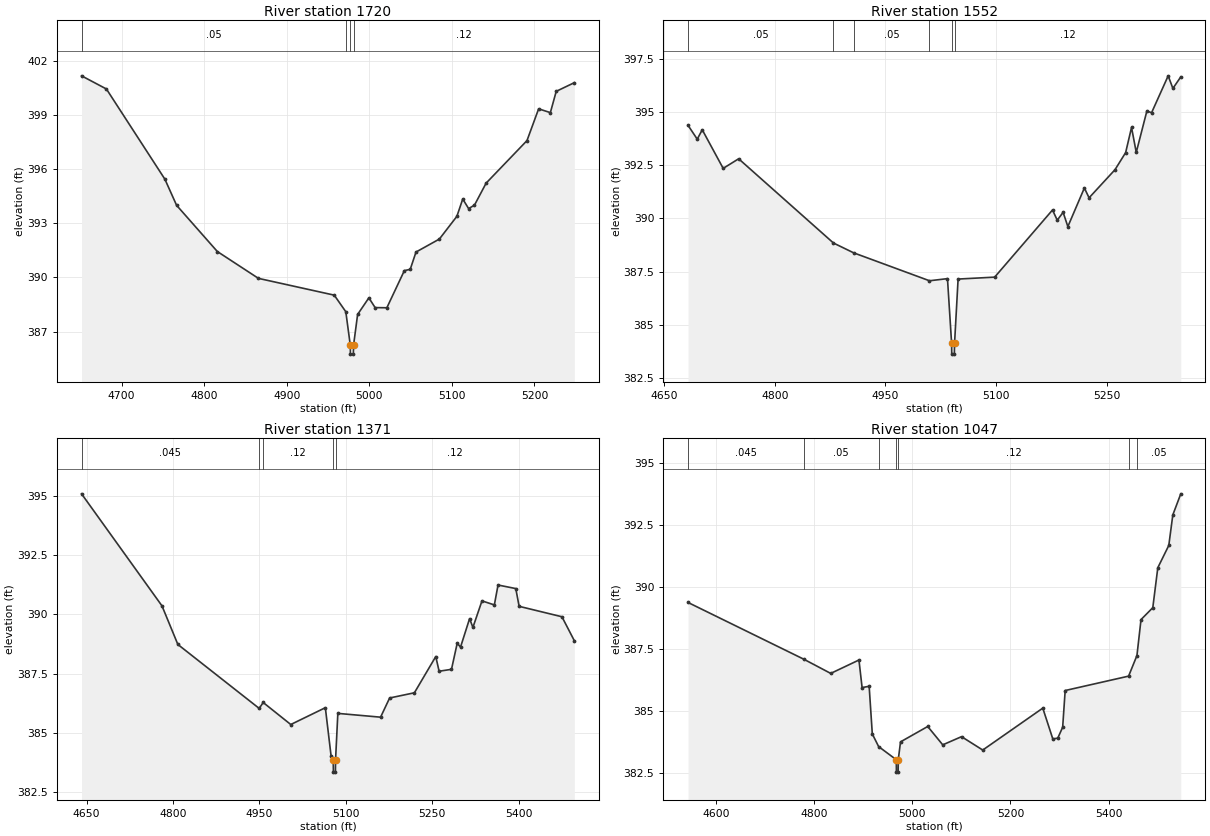
Type RM Length L Ch R = 1,1720,168,168,168
BEGIN DESCRIPTION:
Twin Creek2651720.1
END DESCRIPTION:
XS GIS Cut Line= 3
      2729340.49      6833289.18      2729100.27      6833036.75
      2728924.36      6832861.60
#Sta/Elev= 30
  4651.6  401.18  4681.7  400.45  4752.5  395.45  4766.7  394.00  4816.0  391.44
  4865.8  389.95  4957.6  389.02  4971.6  388.10  4977.0  386.25  4977.2  385.75
  4980.7  385.75  4981.0  386.25  4985.9  387.95  4999.5  388.87  5007.1  388.33
  5021.3  388.32  5042.5  390.38  5049.6  390.45  5056.6  391.41  5084.9  392.13
  5106.1  393.39  5113.2  394.35  5120.3  393.82  5127.4  394.01  5141.5  395.23
  5191.0  397.59  5205.1  399.35  5219.3  399.14  5226.4  400.32  5248.3  400.80
#Mann=4,-1,0
  4651.6    0.05       0  4971.6    0.12       0  4977.0    0.07       0
  4981.0    0.12       0
Bank Sta=4977,4981
Exp/Cntr=0.3,0.1

Type RM Length L Ch R = 1,1552,181,181,181
BEGIN DESCRIPTION:
Twin Creek2651552.04
END DESCRIPTION:
XS GIS Cut Line= 3
      2729433.72      6833150.64      2729215.20      6832913.89
      2728944.76      6832697.57
#Sta/Elev= 30
  4682.2  394.37  4694.7  393.72  4701.5  394.16  4729.9  392.35  4750.9  392.80
  4879.5  388.85  4906.9  388.39  5009.8  387.08  5034.2  387.18  5039.8  384.14
  5040.0  383.64  5043.5  383.64  5043.8  384.14  5048.6  387.16  5098.2  387.25
  5176.7  390.40  5183.1  389.92  5191.1  390.29  5197.5  389.62  5219.9  391.43
  5226.3  390.97  5261.5  392.29  5275.9  393.09  5283.9  394.27  5290.3  393.10
  5304.7  395.04  5311.1  394.96  5333.6  396.69  5340.0  396.10  5350.7  396.64
#Mann=6,-1,0
  4682.2    0.05       0  4879.5   0.045       0  4906.9    0.05       0
  5009.8    0.12       0  5039.8    0.05       0  5043.8    0.12       0
Bank Sta=5039.8,5043.8
Exp/Cntr=0.3,0.1

Type RM Length L Ch R = 1,1371,324,324,324
BEGIN DESCRIPTION:
Twin Creek2651371.48
END DESCRIPTION:
XS GIS Cut Line= 3
      2729518.38      6833025.24      2729274.93      6832753.23
      2728851.69      6832505.60
#Sta/Elev= 30
  4641.3  395.09  4780.9  390.36  4808.5  388.73  4949.7  386.03  4956.6  386.28
  5004.5  385.35  5064.5  386.06  5074.4  384.04  5078.2  383.84  5078.5  383.34
  5082.0  383.34  5082.2  383.84  5086.2  385.82  5160.4  385.66  5176.1  386.47
  5219.1  386.69  5256.2  388.22  5262.0  387.60  5283.5  387.68  5293.4  388.78
  5299.2  388.62  5314.9  389.82  5320.7  389.45  5336.4  390.57  5357.9  390.40
  5364.3  391.24  5395.1  391.09  5400.9  390.34  5475.2  389.90  5496.7  388.89
#Mann=5,-1,0
  4641.3   0.045       0  4949.7    0.05       0  4956.6    0.12       0
  5078.2    0.07       0  5082.2    0.12       0
Bank Sta=5078.2,5082.2
Exp/Cntr=0.3,0.1

Type RM Length L Ch R = 1,1047,0,0,0
BEGIN DESCRIPTION:
Twin Creek2651048.14
END DESCRIPTION:
XS GIS Cut Line= 3
      2729564.54      6832821.48      2729274.34      6832465.31
      2728740.11      6832360.71
#Sta/Elev= 30
  4543.1  389.39  4779.2  387.10  4833.8  386.53  4891.3  387.07  4897.7  385.96
  4912.1  386.01  4918.5  384.09  4931.4  383.58  4967.4  383.05  4967.6  382.55
  4971.1  382.55  4971.4  383.05  4976.0  383.77  5031.4  384.39  5062.0  383.65
  5100.3  383.98  5143.5  383.44  5265.8  385.13  5286.2  383.89  5296.3  383.92
  5306.3  384.36  5311.4  385.84  5440.6  386.42  5457.6  387.25  5465.9  388.70
  5489.9  389.18  5500.1  390.79  5522.5  391.69  5530.7  392.92  5546.9  393.77
#Mann=7,-1,0
  4543.1   0.045       0  4779.2    0.05       0  4931.4    0.12       0
  4967.4    0.07       0  4971.4    0.12       0  5440.6    0.16       0
  5457.6    0.05       0
Bank Sta=4967.4,4971.4
Exp/Cntr=0.3,0.1

Chan Stop Cuts=-1