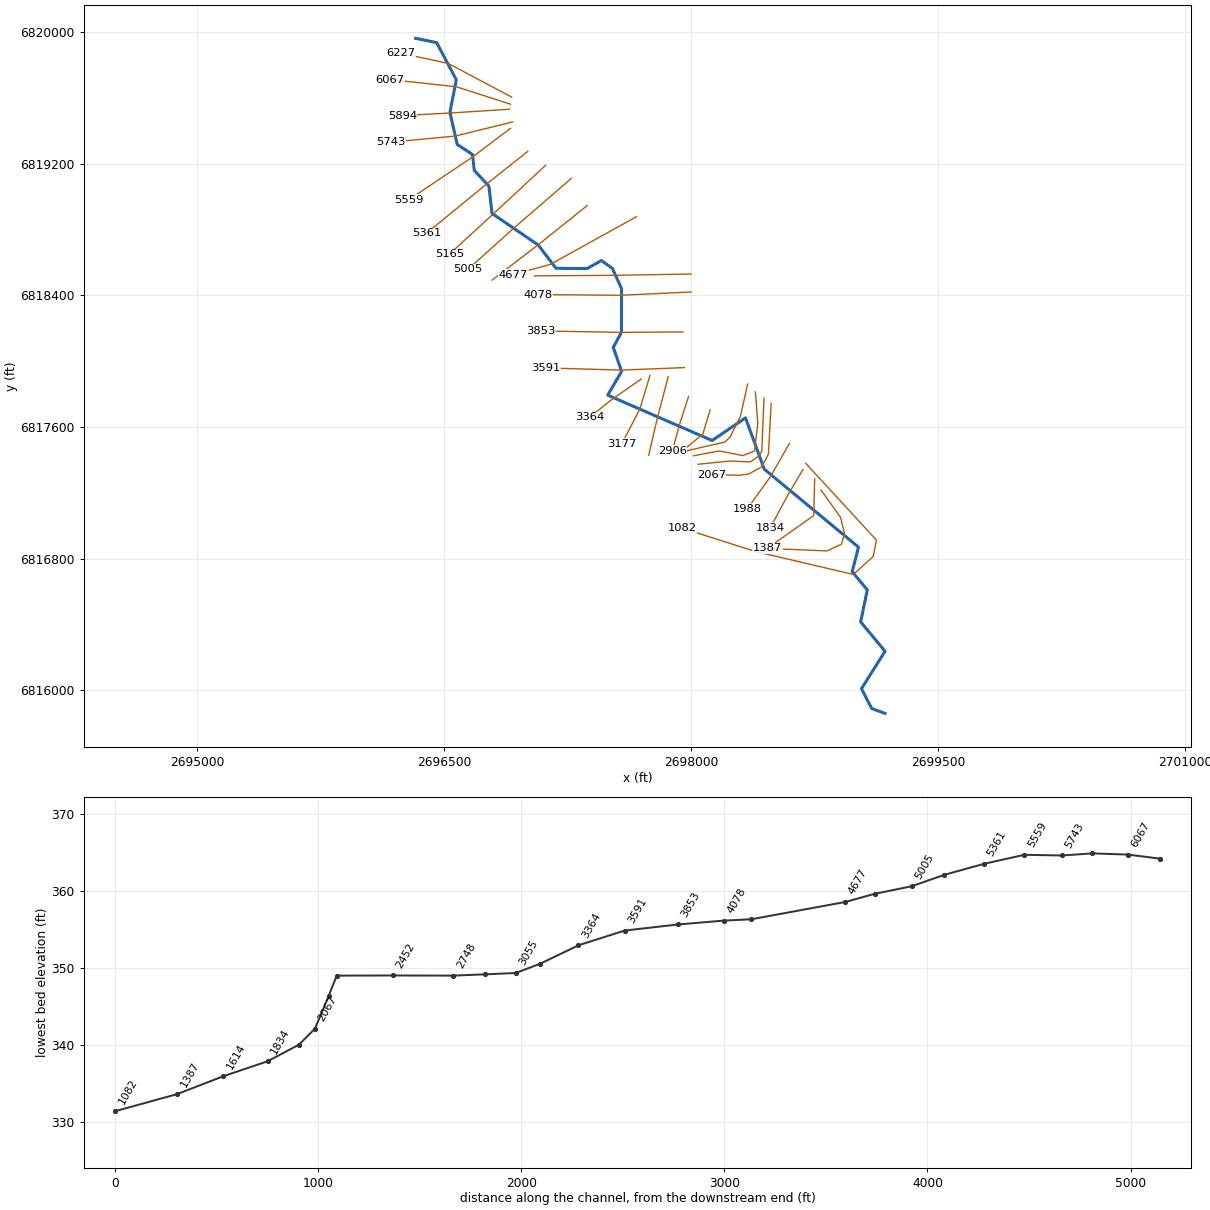
--- Twin Creek266.prj (project) ---

Proj Title=Twin Creek266 Base Level Engineering
Current Plan=p01
Default Exp/Contr=0.3,0.1
English Units
Geom File=g01
Flow File=f01
Plan File=p01
BEGIN DESCRIPTION:
Twin Creek266
END DESCRIPTION:

--- Twin Creek266.p01 (plan) ---

Plan Title=Multiple Run
Short Identifier=Multiple
Geom File=g01
Flow File=f01
Subcritical Flow
K Sum by GR= 0
Std Step Tol= 0.01
Critical Tol= 0.01
Num of Std Step Trials= 20
Max Error Tol= 0.3
Flow Tol Ratio= 0.001
Split Flow NTrial= 30
Split Flow Tol= 0.02
Split Flow Ratio= 0.02
Log Output Level= 0
Friction Slope Method= 1
Unsteady Friction Slope Method= 2
Unsteady Bridges Friction Slope Method= 1
Parabolic Critical Depth
Global Vel Dist=  1 , 1 , 1
Global Log Level= 0
CheckData=True
Encroach Param= -1, 0, 0, 0
BEGIN DESCRIPTION:
Multiple Run
END DESCRIPTION:

--- Twin Creek266.f01 (steady flow) ---

Flow Title=Multiple
Number of Profiles=7
Profile Names=10-year,25-year,50-year,1pct_min,100-year,1pct_plu,500-year
River Rch & RM= Twin Creek266,Reach-1,6227
     200     248     284     162     323     644     415
Boundary for River Rch & Prof#=Twin Creek266,Reach-1,1
Up Type=0
Dn Type=3
Dn Slope=0.005
Boundary for River Rch & Prof#=Twin Creek266,Reach-1,2
Up Type=0
Dn Type=3
Dn Slope=0.005
Boundary for River Rch & Prof#=Twin Creek266,Reach-1,3
Up Type=0
Dn Type=3
Dn Slope=0.005
Boundary for River Rch & Prof#=Twin Creek266,Reach-1,4
Up Type=0
Dn Type=3
Dn Slope=0.005
Boundary for River Rch & Prof#=Twin Creek266,Reach-1,5
Up Type=0
Dn Type=3
Dn Slope=0.005
Boundary for River Rch & Prof#=Twin Creek266,Reach-1,6
Up Type=0
Dn Type=3
Dn Slope=0.005
Boundary for River Rch & Prof#=Twin Creek266,Reach-1,7
Up Type=0
Dn Type=3
Dn Slope=0.005

--- Twin Creek266.g01 (geometry) ---

Geom Title=Existing Conditions

River Reach=Twin Creek266,Reach-1
Reach XY= 30
      2696326.00      6819961.00      2696453.23      6819934.96
      2696572.26      6819709.44      2696533.56      6819511.00
      2696578.13      6819316.28      2696670.71      6819255.51
      2696681.56      6819158.64      2696770.52      6819063.44
      2696789.23      6818897.33      2697070.38      6818705.38
      2697177.45      6818564.53      2697366.35      6818562.40
      2697453.33      6818611.52      2697520.27      6818563.62
      2697575.94      6818440.98      2697575.46      6818176.21
      2697525.62      6818083.81      2697576.58      6817938.21
      2697492.01      6817793.88      2698126.09      6817518.29
      2698328.83      6817655.94      2698442.64      6817344.32
      2699014.90      6816871.06      2698976.95      6816721.48
      2699068.67      6816611.10      2699028.16      6816416.45
      2699176.49      6816238.23      2699033.29      6816011.08
      2699095.49      6815890.53      2699176.00      6815861.00

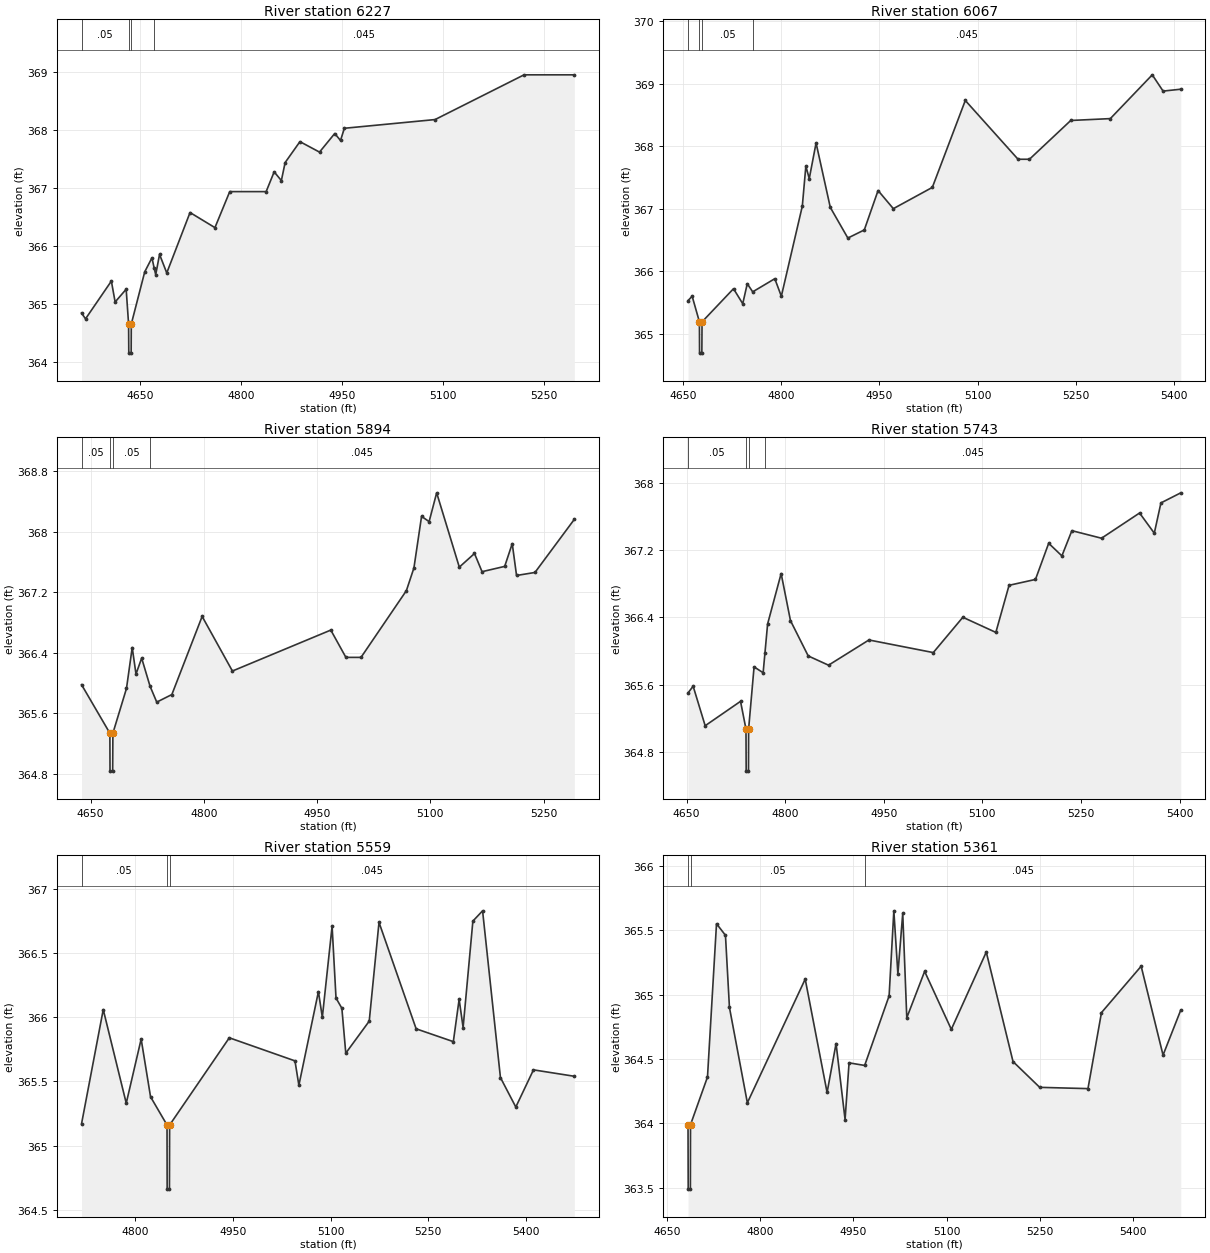
Type RM Length L Ch R = 1,6227,160,160,160
BEGIN DESCRIPTION:
Twin Creek2666226.691
END DESCRIPTION:
XS GIS Cut Line= 3
      2696908.38      6819604.35      2696521.84      6819809.28
      2696233.59      6819870.60
#Sta/Elev= 30
  4562.5  364.85  4568.4  364.75  4606.8  365.40  4612.4  365.04  4628.8  365.26
  4632.4  364.66  4632.7  364.16  4636.2  364.16  4636.4  364.66  4656.4  365.56
  4667.1  365.80  4670.3  365.63  4672.7  365.51  4678.4  365.86  4689.1  365.54
  4723.7  366.58  4760.7  366.32  4782.7  366.94  4836.8  366.94  4848.7  367.28
  4859.4  367.13  4865.0  367.44  4887.0  367.80  4916.1  367.62  4938.7  367.94
  4947.3  367.82  4953.0  368.03  5087.8  368.18  5220.0  368.95  5294.7  368.95
#Mann=4,-1,0
  4562.5    0.05       0  4632.4   0.045       0  4636.4    0.05       0
  4670.3   0.045       0
Bank Sta=4632.4,4636.4
Exp/Cntr=0.3,0.1

Type RM Length L Ch R = 1,6067,173,173,173
BEGIN DESCRIPTION:
Twin Creek2666067.75
END DESCRIPTION:
XS GIS Cut Line= 3
      2696902.04      6819560.90      2696573.80      6819666.56
      2696169.14      6819710.90
#Sta/Elev= 30
  4658.0  365.53  4664.3  365.60  4675.4  365.19  4675.6  364.69  4679.1  364.69
  4679.4  365.19  4727.4  365.72  4741.5  365.48  4748.4  365.80  4756.7  365.67
  4790.4  365.88  4800.4  365.60  4832.4  367.04  4837.8  367.68  4843.0  367.48
  4853.4  368.05  4875.1  367.02  4901.9  366.53  4927.0  366.66  4948.0  367.29
  4971.3  367.00  5030.8  367.34  5081.1  368.73  5161.6  367.79  5179.0  367.79
  5242.0  368.41  5302.4  368.44  5366.4  369.14  5382.9  368.88  5409.9  368.91
#Mann=4,-1,0
  4658.0    0.05       0  4675.4   0.045       0  4679.4    0.05       0
  4756.7   0.045       0
Bank Sta=4675.4,4679.4
Exp/Cntr=0.3,0.1

Type RM Length L Ch R = 1,5894,151,151,151
BEGIN DESCRIPTION:
Twin Creek2665894.16
END DESCRIPTION:
XS GIS Cut Line= 3
      2696895.39      6819530.45      2696531.07      6819507.14
      2696243.93      6819492.02
#Sta/Elev= 30
  4638.1  365.98  4675.6  365.34  4675.8  364.84  4679.3  364.84  4679.6  365.34
  4697.6  365.93  4705.2  366.47  4710.2  366.12  4717.7  366.33  4728.8  365.96
  4737.7  365.75  4757.7  365.85  4797.8  366.88  4837.9  366.16  4968.2  366.70
  4988.2  366.34  5008.2  366.34  5068.3  367.22  5078.3  367.52  5088.4  368.20
  5098.4  368.13  5108.4  368.51  5138.4  367.53  5158.5  367.71  5168.5  367.47
  5198.5  367.54  5208.5  367.84  5214.2  367.42  5238.6  367.46  5290.7  368.16
#Mann=4,-1,0
  4638.1    0.05       0  4675.6   0.045       0  4679.6    0.05       0
  4728.8   0.045       0
Bank Sta=4675.6,4679.6
Exp/Cntr=0.3,0.1

Type RM Length L Ch R = 1,5743,184,184,184
BEGIN DESCRIPTION:
Twin Creek2665740.84
END DESCRIPTION:
XS GIS Cut Line= 3
      2696913.59      6819452.92      2696566.17      6819367.49
      2696175.91      6819330.30
#Sta/Elev= 30
  4652.1  365.50  4659.9  365.58  4678.2  365.11  4732.0  365.40  4740.3  365.07
  4740.6  364.57  4744.1  364.57  4744.3  365.07  4752.6  365.81  4766.4  365.74
  4769.1  365.97  4773.2  366.32  4793.8  366.92  4808.0  366.36  4835.0  365.94
  4865.9  365.83  4927.4  366.13  5025.3  365.98  5070.3  366.40  5120.5  366.22
  5140.6  366.78  5180.8  366.85  5200.9  367.28  5221.0  367.13  5236.2  367.43
  5281.3  367.34  5339.2  367.64  5361.6  367.40  5371.7  367.76  5401.9  367.88
#Mann=4,-1,0
  4652.1    0.05       0  4740.3   0.045       0  4744.3    0.05       0
  4769.1   0.045       0
Bank Sta=4740.3,4744.3
Exp/Cntr=0.3,0.1

Type RM Length L Ch R = 1,5559,198,198,198
BEGIN DESCRIPTION:
Twin Creek2665558.88
END DESCRIPTION:
XS GIS Cut Line= 3
      2696900.52      6819413.79      2696670.46      6819239.95
      2696281.86      6818979.08
#Sta/Elev= 30
  4717.8  365.17  4751.1  366.06  4786.4  365.33  4809.3  365.83  4823.7  365.38
  4849.0  365.16  4849.2  364.66  4852.7  364.66  4853.0  365.16  4944.6  365.84
  5045.4  365.66  5051.4  365.47  5081.4  366.20  5087.4  366.00  5102.4  366.71
  5108.4  366.15  5117.4  366.07  5123.4  365.72  5159.4  365.97  5174.4  366.74
  5231.4  365.91  5288.5  365.81  5297.4  366.14  5303.5  365.92  5318.5  366.75
  5333.4  366.83  5360.8  365.53  5384.4  365.30  5411.5  365.59  5474.2  365.54
#Mann=3,-1,0
  4717.8    0.05       0  4849.0   0.045       0  4853.0   0.045       0
Bank Sta=4849,4853
Exp/Cntr=0.3,0.1

Type RM Length L Ch R = 1,5361,196,196,196
BEGIN DESCRIPTION:
Twin Creek2665361.3
END DESCRIPTION:
XS GIS Cut Line= 3
      2697006.71      6819274.54      2696755.73      6819075.61
      2696390.52      6818776.68
#Sta/Elev= 30
  4684.0  363.99  4684.3  363.49  4687.8  363.49  4688.0  363.99  4715.3  364.36
  4729.8  365.55  4744.2  365.46  4750.6  364.90  4779.4  364.16  4872.4  365.12
  4907.6  364.24  4922.0  364.62  4936.5  364.03  4942.9  364.47  4968.0  364.45
  5007.3  364.99  5014.9  365.65  5021.4  365.16  5029.2  365.63  5035.7  364.82
  5064.4  365.18  5107.3  364.73  5163.5  365.33  5206.5  364.48  5249.4  364.28
  5327.0  364.27  5348.7  364.86  5412.5  365.22  5447.7  364.53  5476.2  364.88
#Mann=3,-1,0
  4684.0   0.045       0  4688.0    0.05       0  4968.0   0.045       0
Bank Sta=4684,4688
Exp/Cntr=0.3,0.1

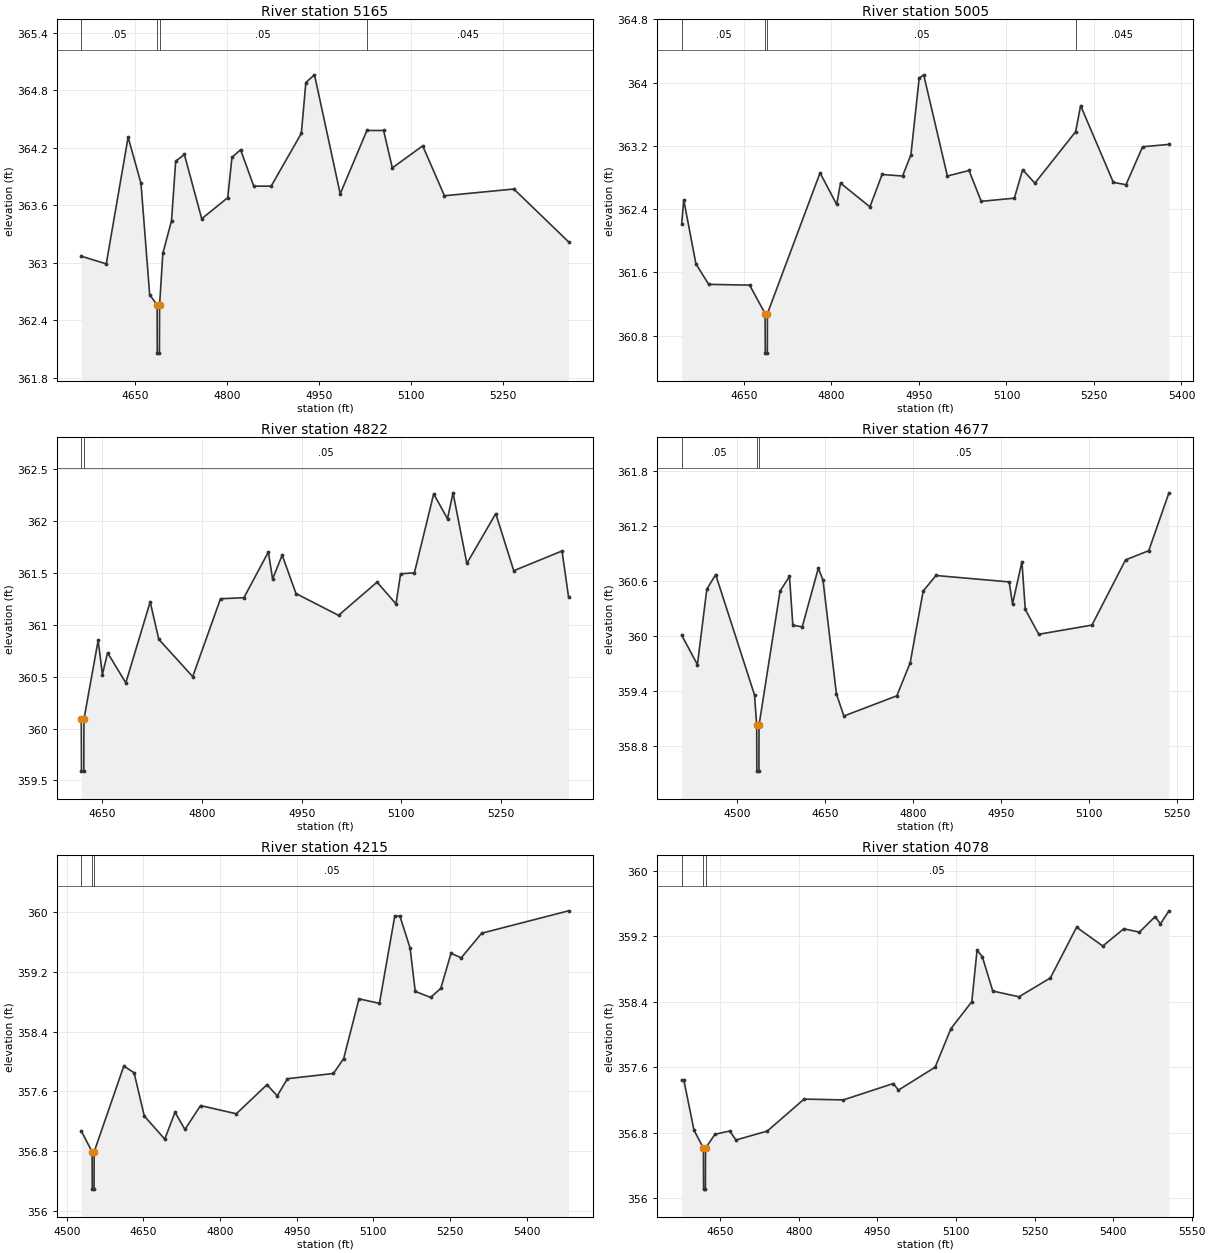
Type RM Length L Ch R = 1,5165,160,160,160
BEGIN DESCRIPTION:
Twin Creek2665164.43
END DESCRIPTION:
XS GIS Cut Line= 3
      2697115.01      6819190.00      2696788.64      6818886.73
      2696530.30      6818650.18
#Sta/Elev= 30
  4562.0  363.07  4602.8  362.99  4638.5  364.31  4659.5  363.83  4673.7  362.67
  4685.9  362.56  4686.1  362.06  4689.6  362.06  4689.9  362.56  4695.2  363.10
  4709.4  363.44  4716.2  364.06  4730.4  364.13  4758.7  363.46  4801.2  363.68
  4808.1  364.10  4822.2  364.18  4843.7  363.80  4872.1  363.80  4921.4  364.35
  4928.8  364.88  4942.9  364.96  4984.9  363.72  5028.5  364.38  5055.8  364.38
  5070.0  363.99  5119.6  364.22  5155.1  363.70  5268.5  363.77  5357.8  363.22
#Mann=4,-1,0
  4562.0    0.05       0  4685.9    0.05       0  4689.9    0.05       0
  5028.5   0.045       0
Bank Sta=4685.9,4689.9
Exp/Cntr=0.3,0.1

Type RM Length L Ch R = 1,5005,183,183,183
BEGIN DESCRIPTION:
Twin Creek2665004.77
END DESCRIPTION:
XS GIS Cut Line= 3
      2697271.21      6819110.44      2696922.68      6818809.21
      2696644.16      6818558.65
#Sta/Elev= 30
  4543.2  362.21  4546.7  362.52  4567.6  361.71  4589.5  361.45  4659.7  361.44
  4686.2  361.08  4686.5  360.58  4690.0  360.58  4690.2  361.08  4780.4  362.86
  4808.9  362.46  4815.5  362.73  4865.9  362.43  4886.8  362.84  4921.9  362.82
  4936.2  363.09  4950.4  364.06  4958.1  364.10  4998.7  362.82  5035.8  362.89
  5056.7  362.50  5113.5  362.54  5127.7  362.90  5148.7  362.73  5218.5  363.38
  5227.1  363.71  5283.2  362.74  5304.9  362.71  5333.3  363.19  5378.5  363.22
#Mann=4,-1,0
  4543.2    0.05       0  4686.2    0.05       0  4690.2    0.05       0
  5218.5   0.045       0
Bank Sta=4686.2,4690.2
Exp/Cntr=0.3,0.1

Type RM Length L Ch R = 1,4822,145,145,145
BEGIN DESCRIPTION:
Twin Creek2664821.61
END DESCRIPTION:
XS GIS Cut Line= 3
      2697366.93      6818944.97      2697068.32      6818705.98
      2696790.00      6818492.55
#Sta/Elev= 30
  4618.3  360.09  4618.6  359.59  4622.1  359.59  4622.3  360.09  4643.7  360.85
  4650.1  360.52  4657.9  360.73  4685.3  360.44  4722.0  361.22  4734.9  360.86
  4786.0  360.50  4827.8  361.25  4863.0  361.26  4899.8  361.70  4906.2  361.44
  4920.6  361.67  4941.4  361.30  5005.4  361.09  5063.4  361.41  5091.9  361.20
  5098.8  361.49  5119.6  361.50  5148.6  362.26  5169.4  362.02  5177.7  362.27
  5198.5  361.59  5242.0  362.07  5269.1  361.52  5341.7  361.71  5351.5  361.27
#Mann=2,-1,0
  4618.3    0.05       0  4622.3    0.05       0
Bank Sta=4618.3,4622.3
Exp/Cntr=0.3,0.1

Type RM Length L Ch R = 1,4677,462,462,462
BEGIN DESCRIPTION:
Twin Creek2664676.68
END DESCRIPTION:
XS GIS Cut Line= 3
      2697666.69      6818877.73      2697143.73      6818588.18
      2696919.56      6818526.39
#Sta/Elev= 30
  4405.4  360.01  4432.2  359.69  4448.2  360.51  4463.3  360.67  4529.5  359.36
  4533.2  359.03  4533.5  358.53  4537.0  358.53  4537.2  359.03  4573.0  360.49
  4589.1  360.65  4594.8  360.12  4610.8  360.10  4638.3  360.74  4646.2  360.61
  4669.1  359.37  4681.8  359.13  4772.0  359.35  4794.8  359.71  4816.9  360.49
  4838.7  360.66  4963.5  360.59  4969.2  360.35  4985.2  360.81  4990.9  360.29
  5013.9  360.02  5104.5  360.12  5161.8  360.83  5201.3  360.93  5235.7  361.56
#Mann=3,-1,0
  4405.4    0.05       0  4533.2    0.05       0  4537.2    0.05       0
Bank Sta=4533.2,4537.2
Exp/Cntr=0.3,0.1

Type RM Length L Ch R = 1,4215,137,137,137
BEGIN DESCRIPTION:
Twin Creek2664214.83
END DESCRIPTION:
XS GIS Cut Line= 3
      2697999.24      6818529.55      2697526.69      6818521.46
      2697046.11      6818518.45
#Sta/Elev= 30
  4528.5  357.07  4549.7  356.79  4550.0  356.29  4553.5  356.29  4553.7  356.79
  4611.7  357.94  4631.8  357.85  4651.8  357.27  4691.8  356.96  4711.8  357.32
  4731.3  357.09  4761.8  357.41  4831.8  357.30  4891.8  357.69  4911.8  357.54
  4931.8  357.77  5021.8  357.84  5041.8  358.04  5071.8  358.84  5111.8  358.78
  5141.8  359.95  5151.8  359.95  5171.8  359.52  5181.8  358.94  5211.8  358.86
  5231.8  358.98  5251.8  359.45  5271.8  359.39  5311.8  359.72  5481.7  360.02
#Mann=3,-1,0
  4528.5    0.05       0  4549.7    0.05       0  4553.7    0.05       0
Bank Sta=4549.7,4553.7
Exp/Cntr=0.3,0.1

Type RM Length L Ch R = 1,4078,225,225,225
BEGIN DESCRIPTION:
Twin Creek2664078.24
END DESCRIPTION:
XS GIS Cut Line= 3
      2697999.46      6818420.45      2697571.31      6818400.37
      2697069.74      6818404.65
#Sta/Elev= 30
  4576.4  357.44  4580.6  357.44  4599.9  356.83  4617.9  356.61  4618.2  356.11
  4621.7  356.11  4621.9  356.61  4639.9  356.78  4668.2  356.82  4680.0  356.71
  4740.0  356.82  4810.1  357.21  4885.1  357.20  4980.3  357.40  4990.3  357.32
  5060.3  357.60  5090.3  358.07  5130.3  358.40  5140.3  359.03  5150.3  358.95
  5170.3  358.53  5220.3  358.46  5280.3  358.69  5330.3  359.31  5380.3  359.08
  5420.3  359.29  5450.3  359.25  5480.3  359.44  5490.3  359.35  5506.6  359.51
#Mann=3,-1,0
  4576.4    0.05       0  4617.9    0.05       0  4621.9    0.05       0
Bank Sta=4617.9,4621.9
Exp/Cntr=0.3,0.1

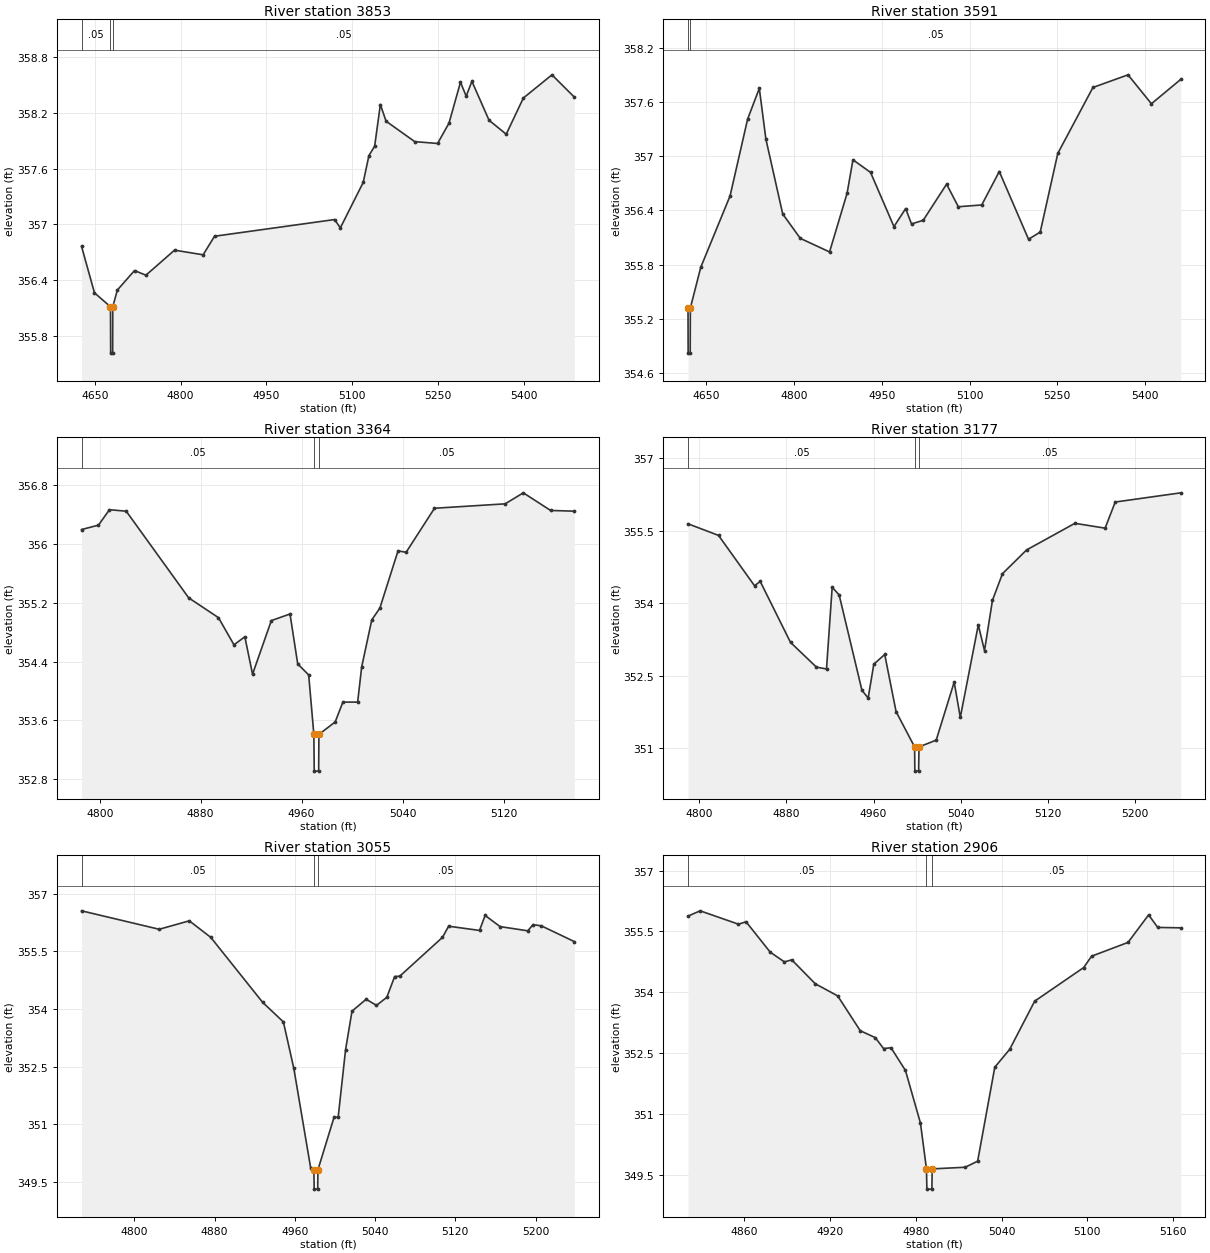
Type RM Length L Ch R = 1,3853,262,262,262
BEGIN DESCRIPTION:
Twin Creek2663852.86
END DESCRIPTION:
XS GIS Cut Line= 3
      2697948.61      6818177.73      2697572.21      6818175.24
      2697086.90      6818183.82
#Sta/Elev= 30
  4626.7  356.76  4649.3  356.26  4677.3  356.11  4677.6  355.61  4681.1  355.61
  4681.3  356.11  4689.3  356.29  4719.3  356.50  4739.3  356.45  4789.3  356.72
  4839.3  356.67  4859.3  356.87  5069.3  357.05  5079.3  356.96  5119.3  357.45
  5129.3  357.74  5139.3  357.84  5149.3  358.29  5159.3  358.11  5209.4  357.89
  5249.4  357.87  5269.4  358.09  5289.4  358.53  5299.4  358.38  5309.4  358.54
  5339.4  358.12  5369.4  357.97  5399.4  358.36  5449.4  358.61  5488.5  358.37
#Mann=3,-1,0
  4626.7    0.05       0  4677.3    0.05       0  4681.3    0.05       0
Bank Sta=4677.3,4681.3
Exp/Cntr=0.3,0.1

Type RM Length L Ch R = 1,3591,227,227,227
BEGIN DESCRIPTION:
Twin Creek2663590.96
END DESCRIPTION:
XS GIS Cut Line= 3
      2697957.82      6817961.16      2697573.69      6817945.82
      2697115.82      6817959.34
#Sta/Elev= 30
  4618.6  355.32  4618.8  354.82  4622.3  354.82  4622.6  355.32  4640.4  355.77
  4690.5  356.56  4720.5  357.41  4740.5  357.75  4751.7  357.19  4780.5  356.36
  4810.6  356.09  4860.6  355.94  4890.6  356.59  4900.6  356.96  4930.7  356.82
  4970.7  356.22  4990.7  356.42  5000.7  356.25  5020.7  356.29  5060.7  356.69
  5080.8  356.44  5120.8  356.46  5150.8  356.83  5200.8  356.08  5220.8  356.16
  5250.8  357.03  5310.9  357.76  5370.9  357.90  5410.9  357.58  5461.1  357.85
#Mann=2,-1,0
  4618.6    0.05       0  4622.6    0.05       0
Bank Sta=4618.6,4622.6
Exp/Cntr=0.3,0.1

Type RM Length L Ch R = 1,3364,187,187,187
BEGIN DESCRIPTION:
Twin Creek2663363.55
END DESCRIPTION:
XS GIS Cut Line= 3
      2697695.06      6817891.52      2697515.62      6817766.29
      2697381.30      6817659.36
#Sta/Elev= 30
  4785.6  356.20  4799.0  356.26  4807.7  356.47  4821.0  356.45  4870.5  355.27
  4894.1  355.00  4906.4  354.63  4915.0  354.74  4921.1  354.23  4936.0  354.96
  4950.8  355.05  4956.9  354.37  4965.6  354.22  4969.7  353.41  4970.0  352.91
  4973.5  352.91  4973.7  353.41  4986.6  353.58  4992.7  353.85  5004.4  353.85
  5007.6  354.33  5015.6  354.97  5022.0  355.13  5036.4  355.91  5042.8  355.89
  5065.3  356.49  5121.3  356.55  5135.7  356.70  5157.3  356.46  5176.1  356.45
#Mann=3,-1,0
  4785.6    0.05       0  4969.7    0.05       0  4973.7    0.05       0
Bank Sta=4969.7,4973.7
Exp/Cntr=0.3,0.1

Type RM Length L Ch R = 1,3177,122,122,122
BEGIN DESCRIPTION:
Twin Creek2663177.49
END DESCRIPTION:
XS GIS Cut Line= 3
      2697748.85      6817913.69      2697687.29      6817709.71
      2697577.38      6817497.67
#Sta/Elev= 30
  4789.8  355.64  4817.8  355.40  4850.8  354.36  4856.0  354.45  4883.8  353.19
  4907.5  352.68  4916.8  352.64  4922.0  354.33  4928.4  354.17  4949.3  352.20
  4955.0  352.04  4960.2  352.74  4970.2  352.94  4980.6  351.76  4997.6  351.03
  4997.8  350.53  5001.3  350.53  5001.6  351.03  5017.4  351.17  5033.9  352.37
  5039.5  351.64  5056.0  353.55  5061.7  353.02  5069.0  354.06  5078.2  354.61
  5100.3  355.10  5144.6  355.65  5172.3  355.55  5181.6  356.09  5241.7  356.28
#Mann=3,-1,0
  4789.8    0.05       0  4997.6    0.05       0  5001.6    0.05       0
Bank Sta=4997.6,5001.6
Exp/Cntr=0.3,0.1

Type RM Length L Ch R = 1,3055,149,149,149
BEGIN DESCRIPTION:
Twin Creek2663054.52
END DESCRIPTION:
XS GIS Cut Line= 3
      2697859.41      6817905.61      2697794.41      6817658.26
      2697740.90      6817428.97
#Sta/Elev= 30
  4747.4  356.55  4824.8  356.07  4854.8  356.29  4876.2  355.86  4927.9  354.17
  4948.6  353.66  4959.0  352.45  4975.8  349.86  4979.0  349.81  4979.3  349.31
  4982.8  349.31  4983.0  349.81  4999.1  351.18  5003.2  351.18  5010.6  352.94
  5017.0  353.94  5031.1  354.25  5041.4  354.09  5051.7  354.30  5059.5  354.84
  5064.6  354.85  5107.2  355.86  5113.3  356.15  5144.1  356.04  5149.7  356.43
  5164.6  356.14  5192.2  356.03  5197.4  356.19  5205.7  356.16  5238.6  355.75
#Mann=3,-1,0
  4747.4    0.05       0  4979.0    0.05       0  4983.0    0.05       0
Bank Sta=4979,4983
Exp/Cntr=0.3,0.1

Type RM Length L Ch R = 1,2906,158,158,158
BEGIN DESCRIPTION:
Twin Creek2662906.26
END DESCRIPTION:
XS GIS Cut Line= 3
      2697983.09      6817785.72      2697927.44      6817613.02
      2697884.83      6817455.43
#Sta/Elev= 30
  4820.7  355.88  4829.2  356.01  4856.0  355.68  4861.3  355.74  4878.2  354.99
  4888.1  354.75  4893.3  354.80  4909.7  354.21  4925.4  353.91  4941.2  353.05
  4951.7  352.88  4957.5  352.61  4962.7  352.63  4972.8  352.07  4983.3  350.77
  4987.5  349.64  4987.8  349.14  4991.3  349.14  4991.5  349.64  5014.6  349.68
  5023.3  349.83  5035.3  352.15  5045.7  352.59  5063.2  353.78  5097.5  354.61
  5103.0  354.89  5128.5  355.23  5142.9  355.91  5149.3  355.60  5165.4  355.59
#Mann=3,-1,0
  4820.7    0.05       0  4987.5    0.05       0  4991.5    0.05       0
Bank Sta=4987.5,4991.5
Exp/Cntr=0.3,0.1

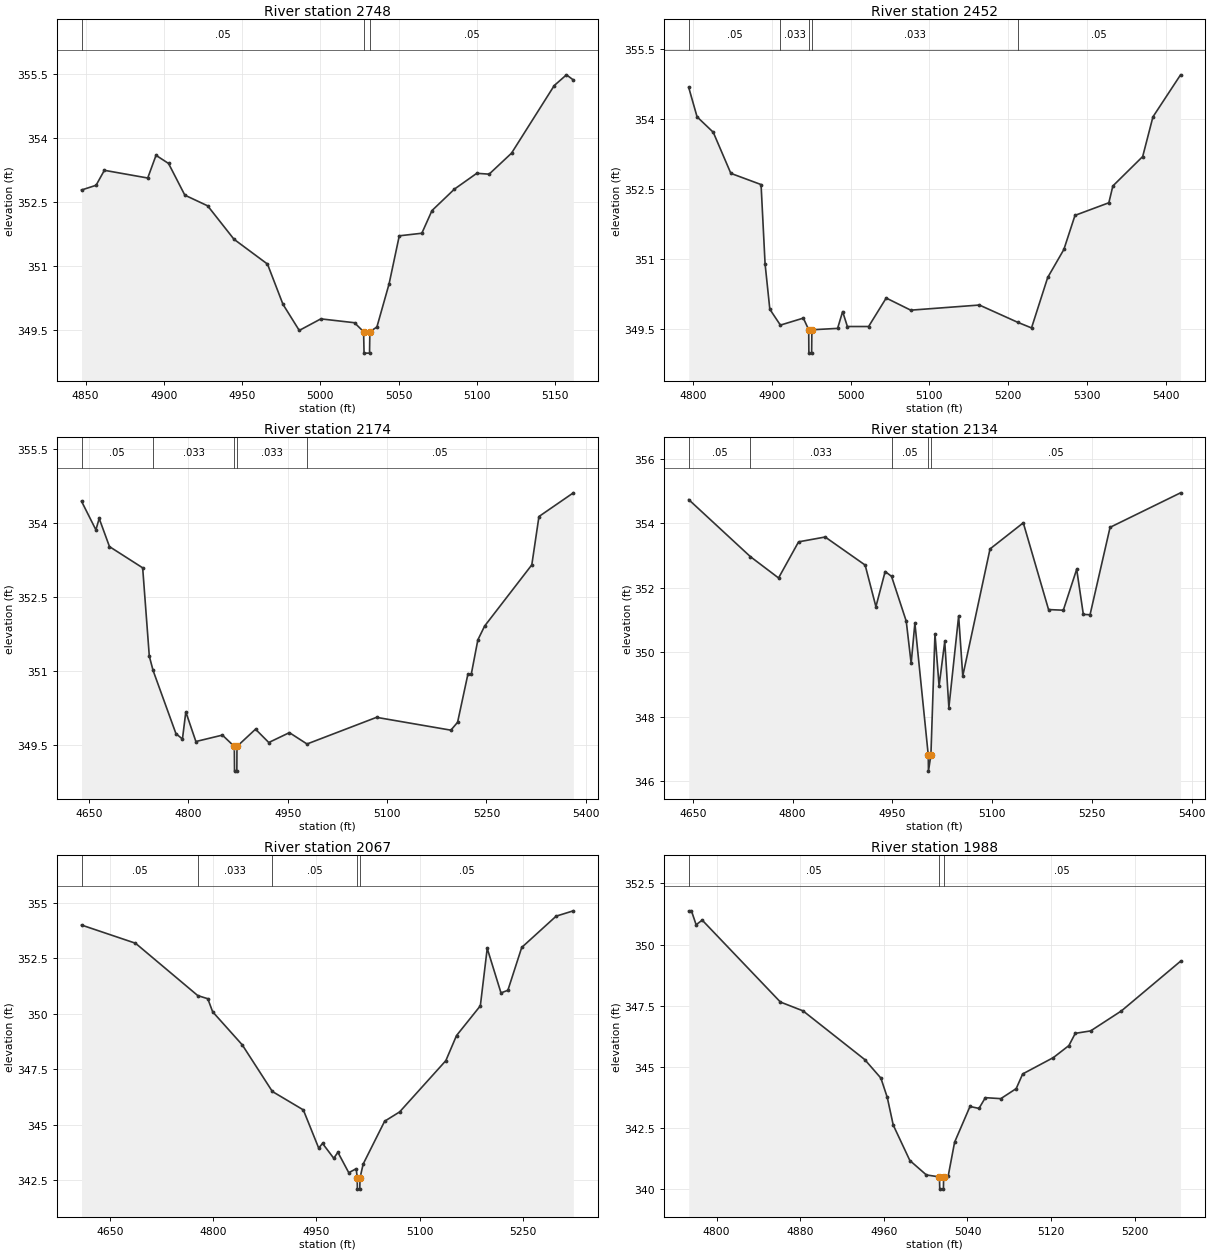
Type RM Length L Ch R = 1,2748,296,296,296
BEGIN DESCRIPTION:
Twin Creek2662748.15
END DESCRIPTION:
XS GIS Cut Line= 3
      2698113.92      6817704.22      2698069.81      6817557.78
      2697945.68      6817454.83
#Sta/Elev= 30
  4847.4  352.78  4856.7  352.89  4862.0  353.24  4889.7  353.06  4895.0  353.59
  4903.0  353.40  4913.4  352.66  4928.0  352.41  4944.8  351.63  4966.2  351.05
  4976.1  350.11  4986.5  349.50  5000.3  349.77  5021.8  349.68  5027.6  349.47
  5027.9  348.97  5031.4  348.97  5031.6  349.47  5036.1  349.58  5043.9  350.59
  5050.4  351.71  5064.8  351.77  5071.3  352.30  5085.6  352.80  5099.9  353.17
  5107.8  353.15  5122.1  353.64  5149.4  355.22  5157.2  355.47  5161.6  355.35
#Mann=3,-1,0
  4847.4    0.05       0  5027.6    0.05       0  5031.6    0.05       0
Bank Sta=5027.6,5031.6
Exp/Cntr=0.3,0.1

Type RM Length L Ch R = 1,2452,278,278,278
BEGIN DESCRIPTION:
Twin Creek2662451.64
END DESCRIPTION:
XS GIS Cut Line= 5
      2698341.93      6817861.36      2698297.84      6817664.21
      2698235.60      6817539.43      2698203.21      6817508.82
      2697971.84      6817455.80
#Sta/Elev= 30
  4794.9  354.68  4805.5  354.05  4826.0  353.72  4848.3  352.84  4886.6  352.60
  4891.7  350.90  4897.7  349.93  4911.1  349.59  4940.2  349.74  4947.0  349.49
  4947.2  348.99  4950.7  348.99  4951.0  349.49  4983.6  349.52  4990.0  349.88
  4996.0  349.56  5022.9  349.56  5045.2  350.17  5076.3  349.91  5163.3  350.02
  5211.9  349.65  5229.4  349.53  5249.9  350.61  5270.4  351.21  5284.5  351.94
  5327.4  352.21  5332.5  352.57  5370.3  353.20  5383.3  354.05  5418.3  354.95
#Mann=5,-1,0
  4794.9    0.05       0  4911.1   0.033       0  4947.0   0.033       0
  4951.0   0.033       0  5211.9    0.05       0
Bank Sta=4947,4951
Exp/Cntr=0.3,0.1

Type RM Length L Ch R = 1,2174,40,40,40
BEGIN DESCRIPTION:
Twin Creek2662174.33
END DESCRIPTION:
XS GIS Cut Line= 6
      2698388.99      6817813.05      2698403.56      6817622.89
      2698383.83      6817454.47      2698312.42      6817426.89
      2698170.66      6817454.87      2698014.34      6817425.67
#Sta/Elev= 30
  4638.9  354.44  4660.6  353.86  4665.6  354.09  4681.1  353.52  4731.2  353.09
  4741.2  351.30  4746.9  351.01  4781.4  349.73  4791.2  349.62  4796.3  350.17
  4811.5  349.57  4851.5  349.70  4869.5  349.47  4869.8  348.97  4873.3  348.97
  4873.5  349.47  4901.5  349.82  4921.5  349.55  4952.6  349.75  4979.2  349.52
  5084.1  350.06  5196.3  349.80  5206.4  349.96  5221.9  350.93  5227.0  350.93
  5237.0  351.63  5247.2  351.91  5318.4  353.15  5329.2  354.13  5381.1  354.61
#Mann=5,-1,0
  4638.9    0.05       0  4746.9   0.033       0  4869.5    0.05       0
  4873.5   0.033       0  4979.2    0.05       0
Bank Sta=4869.5,4873.5
Exp/Cntr=0.3,0.1

Type RM Length L Ch R = 1,2134,67,67,67
BEGIN DESCRIPTION:
Twin Creek2662134.02
END DESCRIPTION:
XS GIS Cut Line= 6
      2698441.27      6817776.10      2698427.95      6817453.73
      2698413.84      6817427.44      2698358.86      6817388.10
      2698235.24      6817393.98      2698040.60      6817374.05
#Sta/Elev= 30
  4643.8  354.73  4736.6  352.96  4778.9  352.30  4809.0  353.42  4849.0  353.57
  4909.1  352.70  4925.3  351.41  4939.2  352.50  4948.8  352.35  4970.9  350.96
  4978.3  349.65  4983.9  350.90  5004.0  346.81  5004.3  346.31  5008.0  346.81
  5014.1  350.57  5020.3  348.95  5028.8  350.33  5035.0  348.28  5049.7  351.12
  5055.9  349.26  5096.9  353.20  5146.9  354.01  5184.9  351.32  5207.1  351.30
  5227.2  352.57  5237.2  351.17  5247.3  351.16  5277.4  353.87  5383.4  354.94
#Mann=5,-1,0
  4643.8    0.05       0  4736.6   0.033       0  4948.8    0.05       0
  5004.0    0.05       0  5008.0    0.05       0
Bank Sta=5004,5008
Exp/Cntr=0.3,0.1

Type RM Length L Ch R = 1,2067,79,79,79
BEGIN DESCRIPTION:
Twin Creek2662067.46
END DESCRIPTION:
XS GIS Cut Line= 6
      2698484.62      6817744.22      2698468.05      6817435.58
      2698427.15      6817358.47      2698348.74      6817315.14
      2698290.13      6817306.90      2698120.98      6817311.75
#Sta/Elev= 30
  4608.9  353.99  4687.3  353.17  4777.8  350.81  4792.3  350.67  4799.4  350.08
  4842.4  348.59  4886.1  346.49  4931.1  345.66  4953.4  343.94  4959.0  344.15
  4975.3  343.48  4981.3  343.75  4997.1  342.83  5007.9  343.01  5009.4  342.59
  5009.6  342.09  5013.1  342.09  5013.4  342.59  5018.0  343.22  5049.2  345.15
  5071.0  345.57  5138.1  347.88  5153.6  349.01  5188.2  350.35  5198.2  352.94
  5218.2  350.93  5228.2  351.05  5248.3  352.98  5298.3  354.39  5323.3  354.63
#Mann=5,-1,0
  4608.9    0.05       0  4777.8   0.033       0  4886.1    0.05       0
  5009.4    0.05       0  5013.4    0.05       0
Bank Sta=5009.4,5013.4
Exp/Cntr=0.3,0.1

Type RM Length L Ch R = 1,1988,154,154,154
BEGIN DESCRIPTION:
Twin Creek2661987.51
END DESCRIPTION:
XS GIS Cut Line= 3
      2698595.45      6817500.52      2698478.77      6817296.59
      2698341.48      6817105.32
#Sta/Elev= 30
  4773.4  351.38  4776.0  351.38  4780.5  350.81  4786.3  351.00  4861.1  347.65
  4882.7  347.29  4941.7  345.30  4957.2  344.54  4963.3  343.75  4969.0  342.62
  4984.9  341.17  5000.7  340.58  5013.2  340.50  5013.5  340.00  5017.0  340.00
  5017.2  340.50  5021.5  340.52  5027.7  341.92  5042.4  343.38  5051.0  343.30
  5057.1  343.74  5071.9  343.70  5086.6  344.11  5092.8  344.71  5122.2  345.38
  5137.0  345.87  5143.1  346.37  5157.8  346.47  5187.3  347.29  5243.8  349.32
#Mann=3,-1,0
  4773.4    0.05       0  5013.2    0.05       0  5017.2    0.05       0
Bank Sta=5013.2,5017.2
Exp/Cntr=0.3,0.1

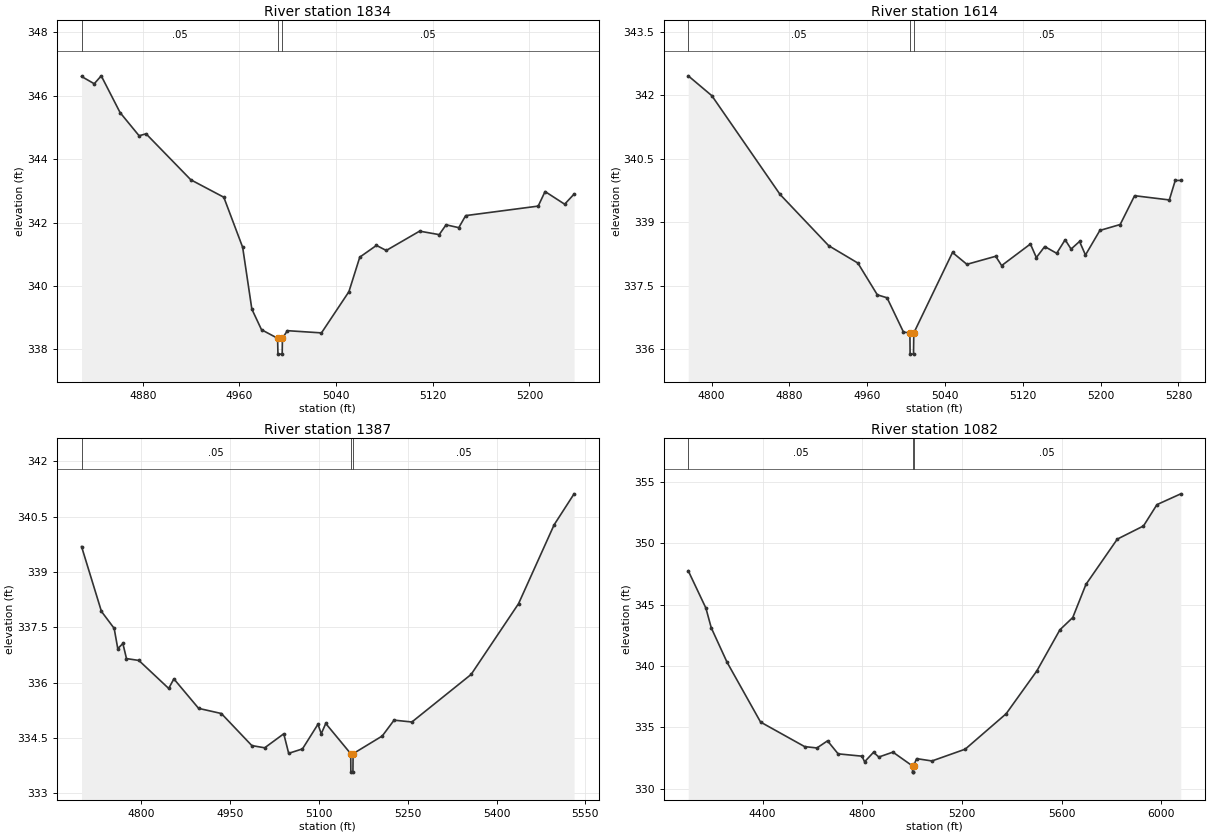
Type RM Length L Ch R = 1,1834,220,220,220
BEGIN DESCRIPTION:
Twin Creek2661834.48
END DESCRIPTION:
XS GIS Cut Line= 3
      2698678.05      6817342.22      2698589.52      6817193.02
      2698478.40      6816987.07
#Sta/Elev= 30
  4829.4  346.61  4839.9  346.38  4845.7  346.63  4861.3  345.47  4877.0  344.74
  4882.8  344.80  4919.8  343.35  4947.1  342.80  4962.7  341.22  4970.3  339.27
  4978.3  338.62  4991.6  338.35  4991.9  337.85  4995.4  337.85  4995.6  338.35
  4999.7  338.59  5027.9  338.52  5050.6  339.82  5059.6  340.91  5073.4  341.28
  5081.5  341.12  5109.1  341.73  5125.3  341.62  5131.0  341.93  5141.5  341.84
  5147.2  342.22  5207.2  342.52  5212.9  342.98  5229.1  342.58  5236.9  342.90
#Mann=3,-1,0
  4829.4    0.05       0  4991.6    0.05       0  4995.6    0.05       0
Bank Sta=4991.6,4995.6
Exp/Cntr=0.3,0.1

Type RM Length L Ch R = 1,1614,227,227,227
BEGIN DESCRIPTION:
Twin Creek2661613.95
END DESCRIPTION:
XS GIS Cut Line= 3
      2698749.15      6817285.32      2698743.14      6817062.27
      2698511.63      6816899.05
#Sta/Elev= 30
  4776.0  342.46  4800.3  341.99  4870.4  339.66  4920.4  338.45  4950.4  338.04
  4970.4  337.29  4980.4  337.22  4997.3  336.41  5003.9  336.39  5004.1  335.89
  5007.6  335.89  5007.9  336.39  5047.7  338.29  5062.5  338.01  5092.1  338.20
  5098.2  337.98  5127.8  338.49  5133.9  338.17  5142.5  338.43  5154.8  338.27
  5163.5  338.59  5169.6  338.37  5178.3  338.55  5184.4  338.23  5199.2  338.81
  5220.1  338.95  5234.9  339.63  5270.6  339.53  5276.7  339.99  5282.4  339.99
#Mann=3,-1,0
  4776.0    0.05       0  5003.9    0.05       0  5007.9    0.05       0
Bank Sta=5003.9,5007.9
Exp/Cntr=0.3,0.1

Type RM Length L Ch R = 1,1387,305,305,305
BEGIN DESCRIPTION:
Twin Creek2661387.01
END DESCRIPTION:
XS GIS Cut Line= 6
      2698787.27      6817218.33      2698905.69      6817052.13
      2698929.95      6816953.97      2698911.58      6816888.61
      2698824.30      6816847.68      2698462.30      6816862.91
#Sta/Elev= 30
  4699.1  339.69  4732.7  337.93  4754.2  337.47  4760.3  336.92  4768.9  337.06
  4775.0  336.65  4795.9  336.60  4846.3  335.84  4855.0  336.10  4896.8  335.30
  4935.2  335.16  4986.7  334.29  5008.4  334.23  5040.6  334.61  5048.9  334.08
  5072.2  334.20  5098.4  334.87  5103.9  334.61  5111.5  334.89  5153.7  334.07
  5153.9  333.57  5157.4  333.57  5157.7  334.07  5206.9  334.55  5226.9  334.98
  5257.0  334.93  5357.0  336.22  5437.1  338.14  5497.2  340.28  5530.9  341.12
#Mann=3,-1,0
  4699.1    0.05       0  5153.7    0.05       0  5157.7    0.05       0
Bank Sta=5153.7,5157.7
Exp/Cntr=0.3,0.1

Type RM Length L Ch R = 1,1082,0,0,0
BEGIN DESCRIPTION:
Twin Creek2661081.715
END DESCRIPTION:
XS GIS Cut Line= 6
      2698694.68      6817379.90      2699124.17      6816913.33
      2699104.37      6816813.30      2698983.80      6816704.83
      2698387.00      6816844.78      2697943.27      6816986.16
#Sta/Elev= 30
  4101.7  347.77  4172.5  344.73  4194.1  343.12  4257.6  340.31  4392.0  335.44
  4568.9  333.44  4618.3  333.33  4660.8  333.91  4703.3  332.85  4799.0  332.66
  4809.6  332.20  4845.5  332.98  4866.5  332.59  4923.3  332.99  5002.0  331.86
  5002.3  331.36  5005.8  331.36  5006.0  331.86  5018.3  332.46  5079.9  332.27
  5213.4  333.23  5377.8  336.12  5501.0  339.61  5593.5  342.96  5645.1  343.96
  5698.0  346.66  5823.9  350.35  5928.9  351.42  5983.0  353.16  6078.7  354.04
#Mann=3,-1,0
  4101.7    0.05       0  5002.0    0.05       0  5006.0    0.05       0
Bank Sta=5002,5006
Exp/Cntr=0.3,0.1

Chan Stop Cuts=-1