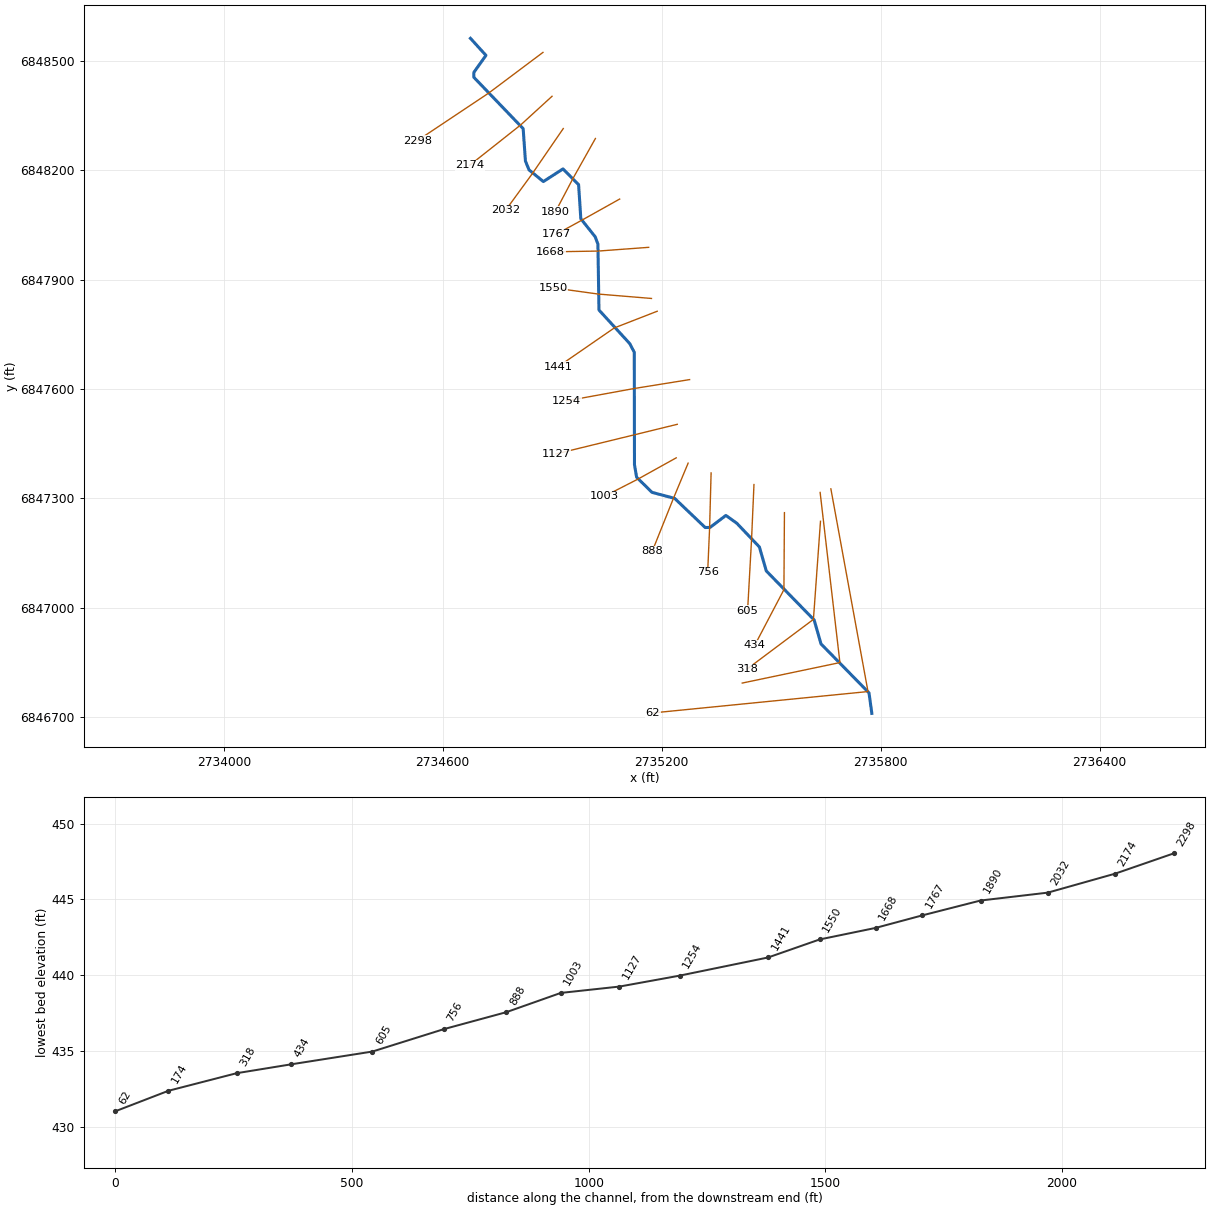
--- Twin Creek268.prj (project) ---

Proj Title=Twin Creek268 Base Level Engineering
Current Plan=p01
Default Exp/Contr=0.3,0.1
English Units
Geom File=g01
Flow File=f01
Plan File=p01
BEGIN DESCRIPTION:
Twin Creek268
END DESCRIPTION:

--- Twin Creek268.p01 (plan) ---

Plan Title=Multiple Run
Short Identifier=Multiple
Geom File=g01
Flow File=f01
Subcritical Flow
K Sum by GR= 0
Std Step Tol= 0.01
Critical Tol= 0.01
Num of Std Step Trials= 20
Max Error Tol= 0.3
Flow Tol Ratio= 0.001
Split Flow NTrial= 30
Split Flow Tol= 0.02
Split Flow Ratio= 0.02
Log Output Level= 0
Friction Slope Method= 1
Unsteady Friction Slope Method= 2
Unsteady Bridges Friction Slope Method= 1
Parabolic Critical Depth
Global Vel Dist=  1 , 1 , 1
Global Log Level= 0
CheckData=True
Encroach Param= -1, 0, 0, 0
BEGIN DESCRIPTION:
Multiple Run
END DESCRIPTION:

--- Twin Creek268.f01 (steady flow) ---

Flow Title=Multiple
Number of Profiles=7
Profile Names=10-year,25-year,50-year,1pct_min,100-year,1pct_plu,500-year
River Rch & RM= Twin Creek268,Reach-1,2298
     224     280     323     185     370     738     483
Boundary for River Rch & Prof#=Twin Creek268,Reach-1,1
Up Type=0
Dn Type=3
Dn Slope=0.005
Boundary for River Rch & Prof#=Twin Creek268,Reach-1,2
Up Type=0
Dn Type=3
Dn Slope=0.005
Boundary for River Rch & Prof#=Twin Creek268,Reach-1,3
Up Type=0
Dn Type=3
Dn Slope=0.005
Boundary for River Rch & Prof#=Twin Creek268,Reach-1,4
Up Type=0
Dn Type=3
Dn Slope=0.005
Boundary for River Rch & Prof#=Twin Creek268,Reach-1,5
Up Type=0
Dn Type=3
Dn Slope=0.005
Boundary for River Rch & Prof#=Twin Creek268,Reach-1,6
Up Type=0
Dn Type=3
Dn Slope=0.005
Boundary for River Rch & Prof#=Twin Creek268,Reach-1,7
Up Type=0
Dn Type=3
Dn Slope=0.005

--- Twin Creek268.g01 (geometry) ---

Geom Title=Existing Conditions

River Reach=Twin Creek268,Reach-1
Reach XY= 30
      2734676.00      6848561.00      2734718.48      6848514.33
      2734685.36      6848467.67      2734685.19      6848454.33
      2734820.47      6848313.42      2734826.67      6848224.63
      2734836.52      6848200.51      2734875.77      6848168.47
      2734929.61      6848203.11      2734972.39      6848159.97
      2734978.47      6848066.58      2735017.86      6848017.06
      2735025.32      6847997.08      2735028.18      6847816.45
      2735112.60      6847724.31      2735124.94      6847700.56
      2735125.51      6847392.56      2735131.36      6847358.30
      2735173.42      6847316.74      2735235.66      6847300.17
      2735319.34      6847220.32      2735332.67      6847220.62
      2735376.01      6847253.44      2735406.07      6847231.93
      2735467.84      6847167.08      2735486.78      6847101.32
      2735617.84      6846967.05      2735636.78      6846901.32
      2735768.24      6846767.21      2735776.00      6846711.00

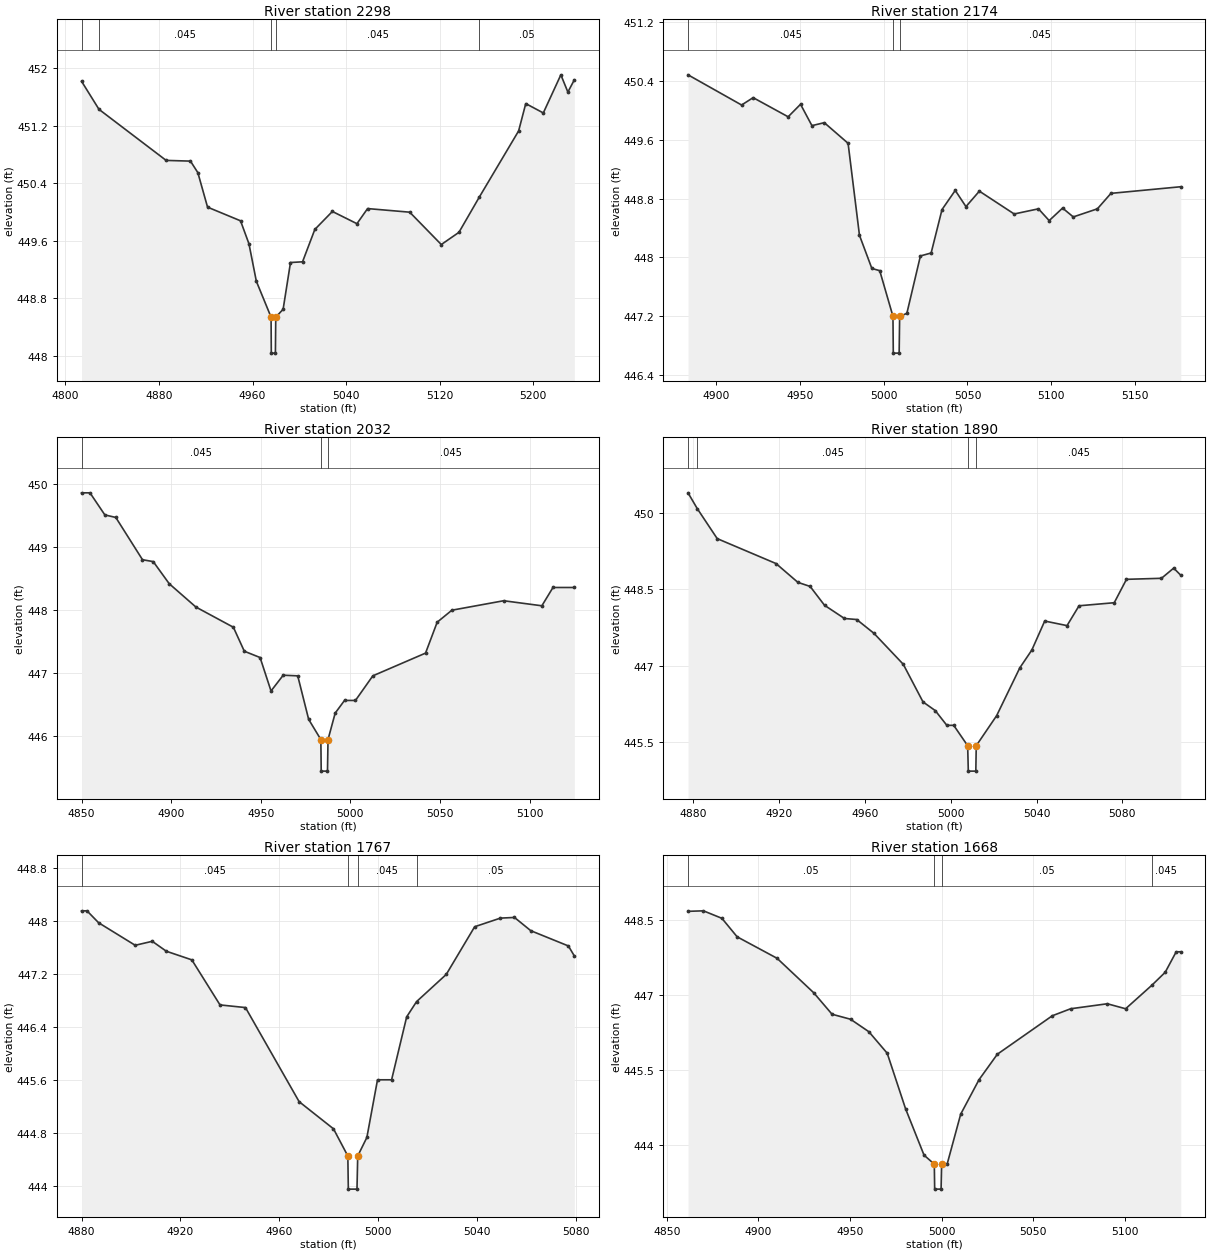
Type RM Length L Ch R = 1,2298,124,124,124
BEGIN DESCRIPTION:
Twin Creek2682297.745
END DESCRIPTION:
XS GIS Cut Line= 3
      2734874.72      6848522.47      2734726.00      6848411.00
      2734530.19      6848280.46
#Sta/Elev= 30
  4813.8  451.82  4828.7  451.43  4886.1  450.72  4906.9  450.71  4913.2  450.55
  4921.5  450.07  4949.7  449.88  4956.9  449.56  4963.2  449.04  4975.8  448.54
  4976.0  448.04  4979.5  448.04  4979.8  448.54  4986.1  448.65  4992.4  449.30
  5002.7  449.31  5013.2  449.76  5028.2  450.01  5049.2  449.84  5058.3  450.05
  5094.3  450.00  5121.3  449.55  5136.4  449.72  5153.8  450.21  5187.4  451.13
  5193.5  451.51  5208.5  451.38  5223.5  451.91  5229.5  451.67  5235.0  451.84
#Mann=5,-1,0
  4813.8    0.05       0  4828.7   0.045       0  4975.8   0.045       0
  4979.8   0.045       0  5153.8    0.05       0
Bank Sta=4975.8,4979.8
Exp/Cntr=0.3,0.1

Type RM Length L Ch R = 1,2174,142,142,142
BEGIN DESCRIPTION:
Mapping XS 9762d288
END DESCRIPTION:
XS GIS Cut Line= 3
      2734899.63      6848402.25      2734814.09      6848324.03
      2734674.21      6848213.33
#Sta/Elev= 30
  4883.1  450.48  4915.1  450.07  4922.0  450.17  4942.9  449.91  4950.3  450.08
  4957.1  449.79  4964.5  449.83  4978.7  449.55  4985.5  448.30  4992.9  447.85
  4997.6  447.82  5005.5  447.20  5005.7  446.70  5009.2  446.70  5009.5  447.20
  5013.8  447.24  5021.9  448.02  5028.3  448.06  5034.8  448.65  5042.7  448.91
  5049.1  448.69  5057.1  448.90  5077.9  448.59  5092.4  448.66  5098.8  448.50
  5106.8  448.67  5113.2  448.55  5127.6  448.66  5135.7  448.87  5177.4  448.96
#Mann=3,-1,0
  4883.1   0.045       0  5005.5   0.045       0  5009.5   0.045       0
Bank Sta=5005.5,5009.5
Exp/Cntr=0.3,0.1

Type RM Length L Ch R = 1,2032,142,142,142
BEGIN DESCRIPTION:
Mapping XS 094fb81f
END DESCRIPTION:
XS GIS Cut Line= 3
      2734930.36      6848313.79      2734845.18      6848189.68
      2734771.88      6848089.20
#Sta/Elev= 30
  4850.0  449.86  4854.7  449.86  4863.0  449.51  4869.1  449.47  4884.0  448.80
  4890.0  448.77  4898.9  448.42  4913.8  448.05  4934.7  447.73  4940.8  447.35
  4949.6  447.25  4955.7  446.72  4962.5  446.97  4970.6  446.96  4976.7  446.27
  4983.5  445.95  4983.7  445.45  4987.2  445.45  4987.5  445.95  4991.5  446.37
  4996.7  446.57  5002.8  446.57  5012.5  446.96  5041.9  447.32  5048.4  447.81
  5056.6  448.00  5085.5  448.15  5106.8  448.07  5113.0  448.36  5124.9  448.36
#Mann=3,-1,0
  4850.0   0.045       0  4983.5   0.045       0  4987.5   0.045       0
Bank Sta=4983.5,4987.5
Exp/Cntr=0.3,0.1

Type RM Length L Ch R = 1,1890,123,123,123
BEGIN DESCRIPTION:
Mapping XS 8792fe77
END DESCRIPTION:
XS GIS Cut Line= 3
      2735018.42      6848286.47      2734957.80      6848178.49
      2734908.49      6848084.92
#Sta/Elev= 30
  4877.6  450.40  4881.9  450.09  4891.2  449.50  4918.6  449.01  4928.8  448.64
  4934.5  448.56  4941.2  448.19  4950.5  447.93  4956.2  447.91  4964.2  447.64
  4977.9  447.03  4987.1  446.29  4992.8  446.12  4998.2  445.83  5001.4  445.83
  5007.9  445.43  5008.2  444.93  5011.7  444.93  5011.9  445.43  5021.4  446.02
  5032.2  446.96  5037.8  447.31  5043.8  447.88  5054.2  447.79  5059.8  448.18
  5076.2  448.24  5081.9  448.70  5098.2  448.72  5103.9  448.92  5107.2  448.78
#Mann=4,-1,0
  4877.6    0.05       0  4881.9   0.045       0  5007.9   0.045       0
  5011.9   0.045       0
Bank Sta=5007.9,5011.9
Exp/Cntr=0.3,0.1

Type RM Length L Ch R = 1,1767,99,99,99
BEGIN DESCRIPTION:
Mapping XS 1e9f1336
END DESCRIPTION:
XS GIS Cut Line= 3
      2735084.91      6848120.55      2734979.80      6848061.77
      2734910.58      6848023.97
#Sta/Elev= 27
  4880.0  448.15  4882.2  448.15  4886.9  447.97  4901.7  447.63  4908.6  447.69
  4914.3  447.54  4924.6  447.41  4936.0  446.73  4946.3  446.69  4968.0  445.27
  4981.9  444.86  4987.7  444.45  4987.9  443.95  4991.4  443.95  4991.7  444.45
  4995.4  444.73  4999.7  445.60  5005.4  445.60  5011.5  446.55  5015.5  446.78
  5027.5  447.19  5039.0  447.91  5049.4  448.04  5055.1  448.05  5061.7  447.85
  5076.9  447.62  5079.3  447.47
#Mann=4,-1,0
  4880.0   0.045       0  4987.7   0.045       0  4991.7   0.045       0
  5015.5    0.05       0
Bank Sta=4987.7,4991.7
Exp/Cntr=0.3,0.1

Type RM Length L Ch R = 1,1668,118,118,118
BEGIN DESCRIPTION:
Mapping XS b18f7049
END DESCRIPTION:
XS GIS Cut Line= 3
      2735164.42      6847988.21      2735025.84      6847978.00
      2734895.92      6847975.80
#Sta/Elev= 28
  4861.6  448.68  4870.0  448.69  4880.1  448.54  4888.4  448.17  4910.2  447.74
  4930.2  447.05  4940.2  446.62  4950.3  446.52  4960.3  446.27  4970.3  445.84
  4980.3  444.73  4990.4  443.80  4996.0  443.62  4996.2  443.12  4999.7  443.12
  5000.0  443.62  5003.0  443.62  5010.4  444.62  5020.4  445.31  5030.4  445.82
  5060.4  446.59  5070.4  446.73  5090.4  446.83  5100.4  446.73  5114.7  447.20
  5122.0  447.46  5128.0  447.87  5130.5  447.87
#Mann=4,-1,0
  4861.6    0.05       0  4996.0    0.05       0  5000.0    0.05       0
  5114.7   0.045       0
Bank Sta=4996,5000
Exp/Cntr=0.3,0.1

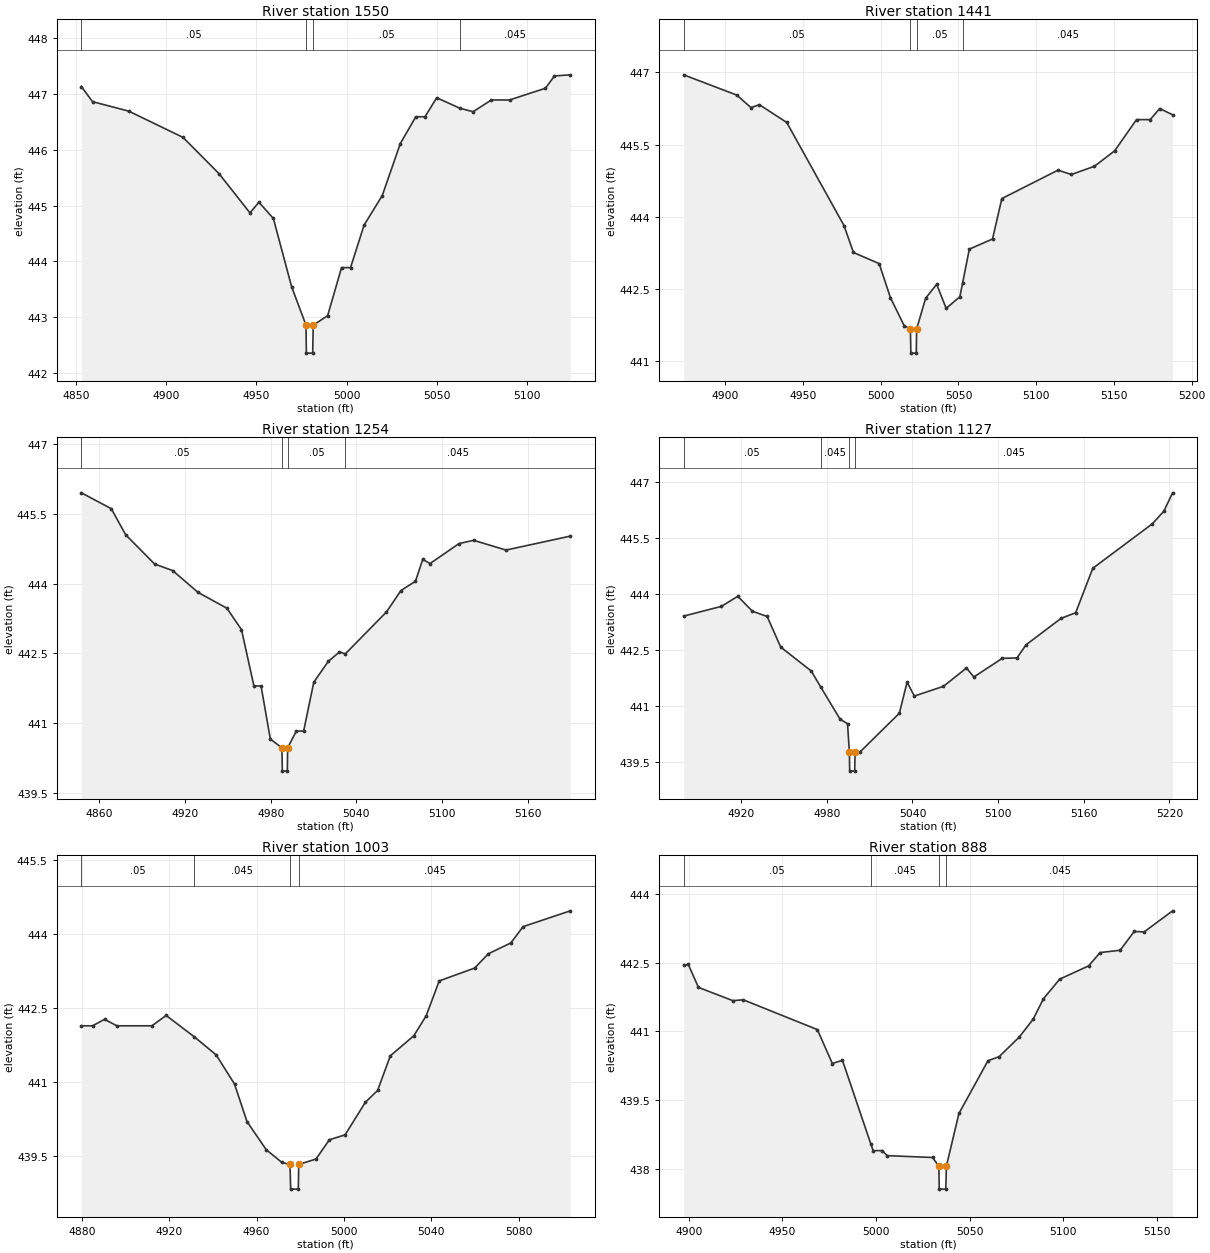
Type RM Length L Ch R = 1,1550,109,109,109
BEGIN DESCRIPTION:
Mapping XS 9d21dacb
END DESCRIPTION:
XS GIS Cut Line= 3
      2735172.16      6847848.11      2735025.69      6847860.24
      2734902.63      6847877.25
#Sta/Elev= 29
  4852.9  447.13  4859.1  446.86  4879.2  446.69  4909.3  446.22  4929.3  445.57
  4946.4  444.87  4951.4  445.06  4959.4  444.77  4969.5  443.55  4977.5  442.86
  4977.7  442.36  4981.2  442.36  4981.5  442.86  4989.5  443.03  4997.2  443.89
  5002.2  443.89  5009.7  444.65  5019.8  445.18  5029.8  446.11  5038.4  446.59
  5043.5  446.59  5050.0  446.93  5063.0  446.74  5070.2  446.68  5080.3  446.89
  5090.4  446.89  5110.3  447.10  5115.3  447.32  5124.1  447.34
#Mann=4,-1,0
  4852.9    0.05       0  4977.5    0.05       0  4981.5    0.05       0
  5063.0   0.045       0
Bank Sta=4977.5,4981.5
Exp/Cntr=0.3,0.1

Type RM Length L Ch R = 1,1441,187,187,187
BEGIN DESCRIPTION:
Mapping XS 7fd258ac
END DESCRIPTION:
XS GIS Cut Line= 3
      2735187.82      6847813.08      2735070.26      6847767.36
      2734915.30      6847660.46
#Sta/Elev= 30
  4873.3  446.95  4907.4  446.53  4916.6  446.27  4922.0  446.33  4939.6  445.96
  4976.4  443.82  4982.5  443.26  4999.0  443.03  5006.3  442.32  5015.1  441.74
  5019.1  441.67  5019.4  441.17  5022.9  441.17  5023.1  441.67  5028.9  442.31
  5036.0  442.60  5042.1  442.10  5050.9  442.34  5052.7  442.63  5057.0  443.33
  5071.9  443.54  5077.9  444.38  5114.0  444.97  5122.6  444.88  5137.4  445.05
  5150.4  445.37  5164.5  446.02  5173.3  446.02  5179.4  446.25  5187.7  446.12
#Mann=4,-1,0
  4873.3    0.05       0  5019.1    0.05       0  5023.1    0.05       0
  5052.7   0.045       0
Bank Sta=5019.1,5023.1
Exp/Cntr=0.3,0.1

Type RM Length L Ch R = 1,1254,127,127,127
BEGIN DESCRIPTION:
Mapping XS fe6a2528
END DESCRIPTION:
XS GIS Cut Line= 3
      2735276.64      6847625.74      2735125.00      6847601.37
      2734939.36      6847567.43
#Sta/Elev= 30
  4847.5  445.95  4868.4  445.61  4878.5  445.05  4898.8  444.42  4911.4  444.28
  4929.2  443.81  4949.4  443.47  4959.6  443.01  4968.3  441.80  4973.3  441.80
  4979.8  440.66  4987.9  440.47  4988.2  439.97  4991.7  439.97  4991.9  440.47
  4998.0  440.83  5003.1  440.83  5010.2  441.88  5020.4  442.33  5028.2  442.53
  5032.3  442.49  5061.1  443.39  5071.2  443.85  5081.4  444.05  5086.5  444.52
  5091.6  444.43  5111.9  444.86  5122.1  444.93  5144.8  444.72  5189.8  445.02
#Mann=4,-1,0
  4847.5    0.05       0  4987.9    0.05       0  4991.9    0.05       0
  5032.3   0.045       0
Bank Sta=4987.9,4991.9
Exp/Cntr=0.3,0.1

Type RM Length L Ch R = 1,1127,124,124,124
BEGIN DESCRIPTION:
Mapping XS dfc0b9df
END DESCRIPTION:
XS GIS Cut Line= 3
      2735242.80      6847503.20      2735125.22      6847474.43
      2734910.08      6847421.94
#Sta/Elev= 30
  4879.7  443.40  4906.1  443.66  4917.6  443.93  4927.9  443.53  4938.2  443.39
  4947.7  442.57  4969.1  441.93  4975.6  441.51  4989.3  440.64  4994.5  440.52
  4995.8  439.75  4996.0  439.25  4999.5  439.25  4999.8  439.75  5002.9  439.75
  5030.8  440.80  5036.2  441.63  5041.3  441.26  5061.7  441.52  5077.8  442.01
  5083.0  441.77  5102.9  442.27  5113.2  442.28  5119.5  442.63  5144.1  443.34
  5154.3  443.49  5166.3  444.68  5208.0  445.87  5216.1  446.21  5222.2  446.70
#Mann=4,-1,0
  4879.7    0.05       0  4975.6   0.045       0  4995.8   0.045       0
  4999.8   0.045       0
Bank Sta=4995.8,4999.8
Exp/Cntr=0.3,0.1

Type RM Length L Ch R = 1,1003,115,115,115
BEGIN DESCRIPTION:
Mapping XS 66ac0006
END DESCRIPTION:
XS GIS Cut Line= 3
      2735239.93      6847411.30      2735134.39      6847352.69
      2735042.62      6847305.75
#Sta/Elev= 30
  4879.8  442.14  4884.9  442.14  4890.4  442.27  4896.1  442.14  4912.1  442.14
  4918.6  442.35  4931.4  441.92  4941.5  441.55  4949.9  440.96  4955.6  440.20
  4964.4  439.63  4971.6  439.37  4975.3  439.33  4975.6  438.83  4979.1  438.83
  4979.3  439.33  4987.2  439.44  4993.3  439.83  5000.5  439.93  5009.8  440.59
  5015.4  440.83  5021.2  441.53  5032.0  441.94  5037.6  442.34  5043.6  443.05
  5059.8  443.31  5066.1  443.60  5076.4  443.82  5082.0  444.15  5103.6  444.47
#Mann=4,-1,0
  4879.8    0.05       0  4931.4   0.045       0  4975.3   0.045       0
  4979.3   0.045       0
Bank Sta=4975.3,4979.3
Exp/Cntr=0.3,0.1

Type RM Length L Ch R = 1,888,132,132,132
BEGIN DESCRIPTION:
Mapping XS 08a04a2b
END DESCRIPTION:
XS GIS Cut Line= 3
      2735272.59      6847396.85      2735232.55      6847300.98
      2735174.12      6847155.04
#Sta/Elev= 30
  4897.3  442.44  4899.8  442.46  4905.2  441.96  4923.6  441.67  4929.1  441.69
  4968.7  441.04  4976.7  440.30  4982.1  440.37  4997.3  438.54  4998.5  438.40
  5003.3  438.40  5006.0  438.29  5030.2  438.25  5033.6  438.06  5033.8  437.56
  5037.3  437.56  5037.6  438.06  5044.3  439.21  5059.8  440.36  5065.8  440.45
  5076.6  440.88  5084.0  441.27  5089.4  441.71  5098.1  442.14  5113.6  442.43
  5119.7  442.72  5130.4  442.77  5137.9  443.18  5143.2  443.17  5158.4  443.63
#Mann=4,-1,0
  4897.3    0.05       0  4997.3   0.045       0  5033.6   0.045       0
  5037.6   0.045       0
Bank Sta=5033.6,5037.6
Exp/Cntr=0.3,0.1

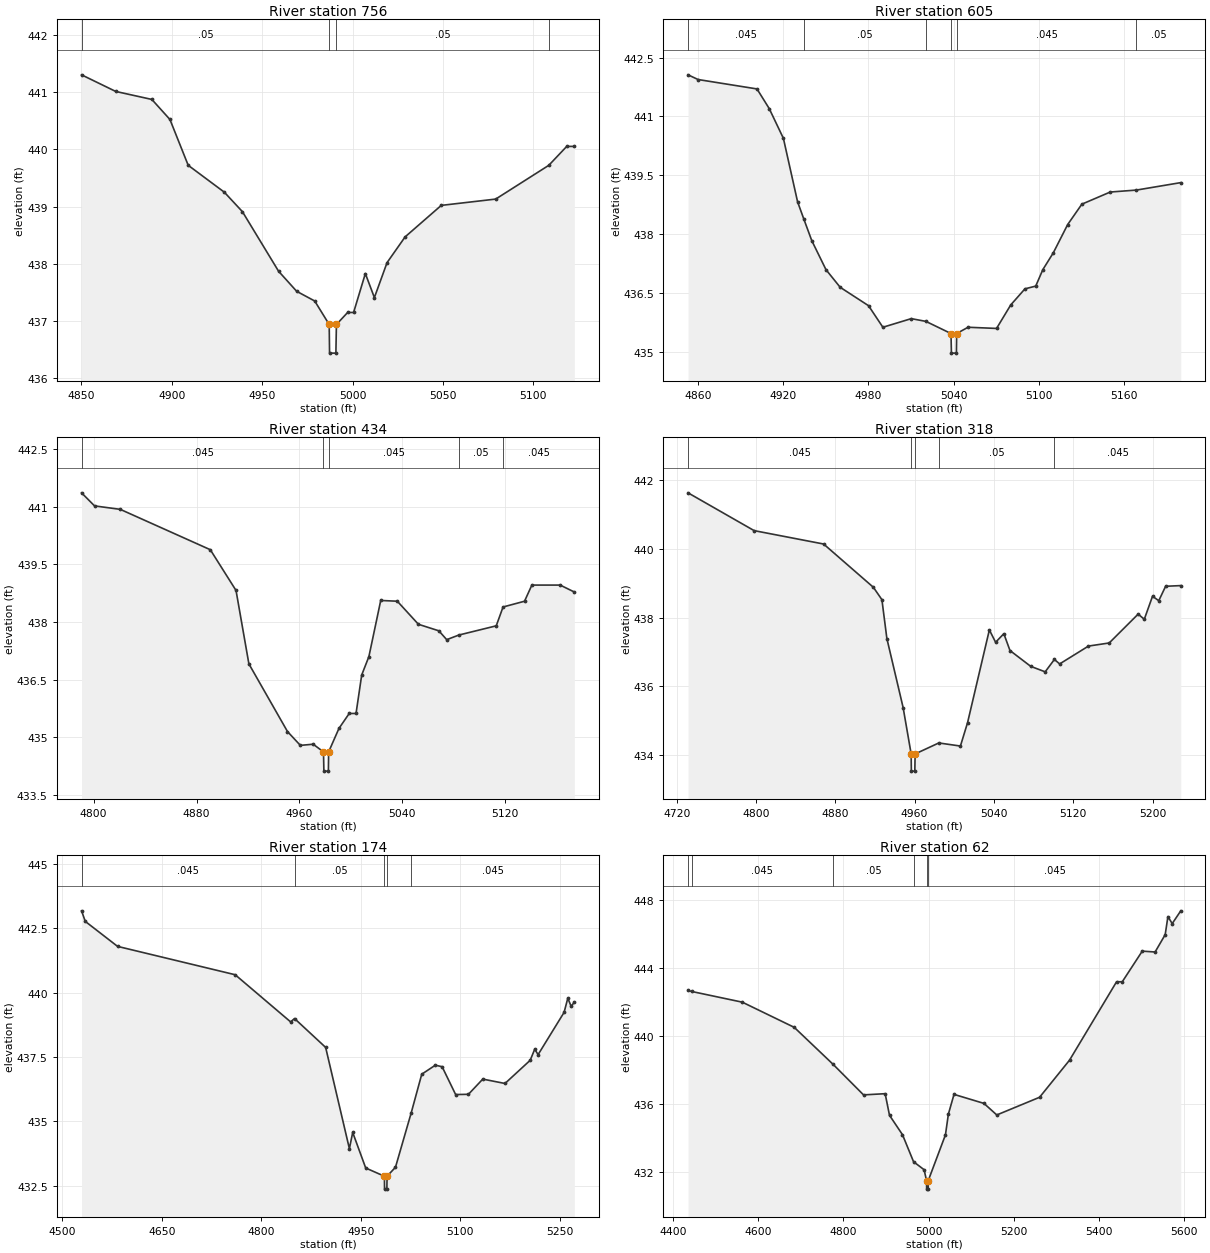
Type RM Length L Ch R = 1,756,151,151,151
BEGIN DESCRIPTION:
Mapping XS e76d64c4
END DESCRIPTION:
XS GIS Cut Line= 3
      2735335.50      6847369.93      2735331.42      6847219.50
      2735326.08      6847097.50
#Sta/Elev= 25
  4850.1  441.30  4869.0  441.01  4889.0  440.87  4899.0  440.52  4909.1  439.72
  4929.1  439.25  4939.1  438.91  4959.1  437.87  4969.1  437.52  4979.1  437.35
  4987.1  436.94  4987.3  436.44  4990.8  436.44  4991.1  436.94  4997.3  437.15
  5000.6  437.15  5007.1  437.83  5012.1  437.41  5019.1  438.02  5029.1  438.47
  5049.1  439.02  5079.2  439.13  5108.6  439.72  5118.5  440.05  5122.7  440.05
#Mann=4,-1,0
  4850.1    0.05       0  4987.1    0.05       0  4991.1    0.05       0
  5108.6   0.045       0
Bank Sta=4987.1,4991.1
Exp/Cntr=0.3,0.1

Type RM Length L Ch R = 1,605,171,171,171
BEGIN DESCRIPTION:
Mapping XS dcc36f00
END DESCRIPTION:
XS GIS Cut Line= 3
      2735452.98      6847338.13      2735446.42      6847188.65
      2735435.48      6846991.37
#Sta/Elev= 30
  4852.9  442.06  4860.0  441.94  4901.5  441.70  4910.1  441.20  4920.1  440.44
  4930.1  438.82  4934.5  438.38  4940.1  437.83  4950.1  437.09  4960.1  436.64
  4980.1  436.17  4990.2  435.62  5010.2  435.84  5020.5  435.77  5038.2  435.46
  5038.5  434.96  5042.0  434.96  5042.2  435.46  5050.2  435.62  5070.3  435.59
  5080.3  436.19  5090.3  436.60  5097.9  436.67  5102.9  437.09  5110.3  437.52
  5120.4  438.24  5130.4  438.76  5150.4  439.07  5168.9  439.12  5200.1  439.31
#Mann=6,-1,0
  4852.9   0.045       0  4934.5    0.05       0  5020.5   0.045       0
  5038.2    0.05       0  5042.2   0.045       0  5168.9    0.05       0
Bank Sta=5038.2,5042.2
Exp/Cntr=0.3,0.1

Type RM Length L Ch R = 1,434,116,116,116
BEGIN DESCRIPTION:
Mapping XS bdf2c30e
END DESCRIPTION:
XS GIS Cut Line= 3
      2735536.50      6847261.13      2735535.07      6847050.04
      2735455.16      6846897.73
#Sta/Elev= 30
  4790.6  441.36  4800.7  441.02  4820.7  440.93  4890.7  439.88  4910.7  438.82
  4920.7  436.91  4950.7  435.15  4960.7  434.79  4970.7  434.82  4978.7  434.62
  4979.0  434.12  4982.5  434.12  4982.7  434.62  4990.7  435.23  4998.7  435.62
  5004.0  435.62  5008.4  436.62  5014.0  437.10  5023.2  438.56  5036.1  438.54
  5052.5  437.94  5068.4  437.77  5074.5  437.54  5083.9  437.66  5113.0  437.90
  5118.3  438.39  5135.0  438.54  5140.7  438.96  5162.7  438.96  5173.7  438.78
#Mann=5,-1,0
  4790.6   0.045       0  4978.7   0.045       0  4982.7   0.045       0
  5083.9    0.05       0  5118.3   0.045       0
Bank Sta=4978.7,4982.7
Exp/Cntr=0.3,0.1

Type RM Length L Ch R = 1,318,144,144,144
BEGIN DESCRIPTION:
Mapping XS a289b1ff
END DESCRIPTION:
XS GIS Cut Line= 3
      2735635.29      6847237.48      2735615.95      6846968.61
      2735433.78      6846832.28
#Sta/Elev= 30
  4731.4  441.63  4798.1  440.53  4868.2  440.14  4918.4  438.88  4927.0  438.52
  4932.0  437.39  4948.4  435.38  4956.5  434.03  4956.7  433.53  4960.2  433.53
  4960.5  434.03  4984.4  434.35  5006.2  434.26  5013.4  434.94  5035.4  437.64
  5041.7  437.28  5050.0  437.53  5056.2  437.04  5077.1  436.58  5091.7  436.42
  5101.0  436.78  5106.3  436.65  5135.4  437.17  5156.3  437.26  5185.5  438.10
  5191.7  437.95  5200.0  438.62  5206.3  438.49  5213.2  438.91  5228.5  438.93
#Mann=5,-1,0
  4731.4   0.045       0  4956.5    0.05       0  4960.5   0.045       0
  4984.4    0.05       0  5101.0   0.045       0
Bank Sta=4956.5,4960.5
Exp/Cntr=0.3,0.1

Type RM Length L Ch R = 1,174,112,112,112
BEGIN DESCRIPTION:
Mapping XS 660830e6
END DESCRIPTION:
XS GIS Cut Line= 3
      2735634.33      6847316.53      2735688.52      6846850.19
      2735420.92      6846794.07
#Sta/Elev= 30
  4528.9  443.17  4534.5  442.76  4583.2  441.79  4760.5  440.69  4844.1  438.86
  4850.0  438.99  4896.9  437.87  4932.7  433.94  4937.7  434.57  4957.3  433.19
  4985.5  432.87  4985.7  432.37  4989.2  432.37  4989.5  432.87  5002.2  433.22
  5025.9  435.33  5041.8  436.83  5062.3  437.18  5072.5  437.12  5092.9  436.04
  5112.2  436.05  5133.8  436.64  5167.3  436.47  5205.3  437.37  5212.1  437.80
  5217.2  437.59  5256.4  439.23  5262.0  439.78  5267.1  439.46  5271.8  439.63
#Mann=5,-1,0
  4528.9   0.045       0  4850.0    0.05       0  4985.5    0.05       0
  4989.5    0.05       0  5025.9   0.045       0
Bank Sta=4985.5,4989.5
Exp/Cntr=0.3,0.1

Type RM Length L Ch R = 1,62,0,0,0
BEGIN DESCRIPTION:
Twin Creek268944.77
END DESCRIPTION:
XS GIS Cut Line= 3
      2735663.74      6847326.45      2735765.48      6846770.79
      2735175.98      6846712.25
#Sta/Elev= 30
  4435.1  442.70  4443.6  442.64  4562.6  442.01  4684.6  440.53  4776.1  438.35
  4847.3  436.56  4898.1  436.63  4908.3  435.36  4938.8  434.22  4964.8  432.63
  4989.6  432.16  4995.3  431.52  4995.6  431.02  4999.1  431.02  4999.3  431.52
  5039.7  434.21  5046.6  435.43  5059.8  436.59  5130.1  436.06  5160.3  435.38
  5260.8  436.42  5331.1  438.60  5441.6  443.21  5455.0  443.21  5501.9  445.01
  5532.1  444.96  5555.8  445.98  5562.2  447.04  5572.3  446.63  5592.4  447.38
#Mann=6,-1,0
  4435.1    0.05       0  4443.6   0.045       0  4776.1    0.05       0
  4964.8   0.045       0  4995.3   0.045       0  4999.3   0.045       0
Bank Sta=4995.3,4999.3
Exp/Cntr=0.3,0.1

Chan Stop Cuts=-1