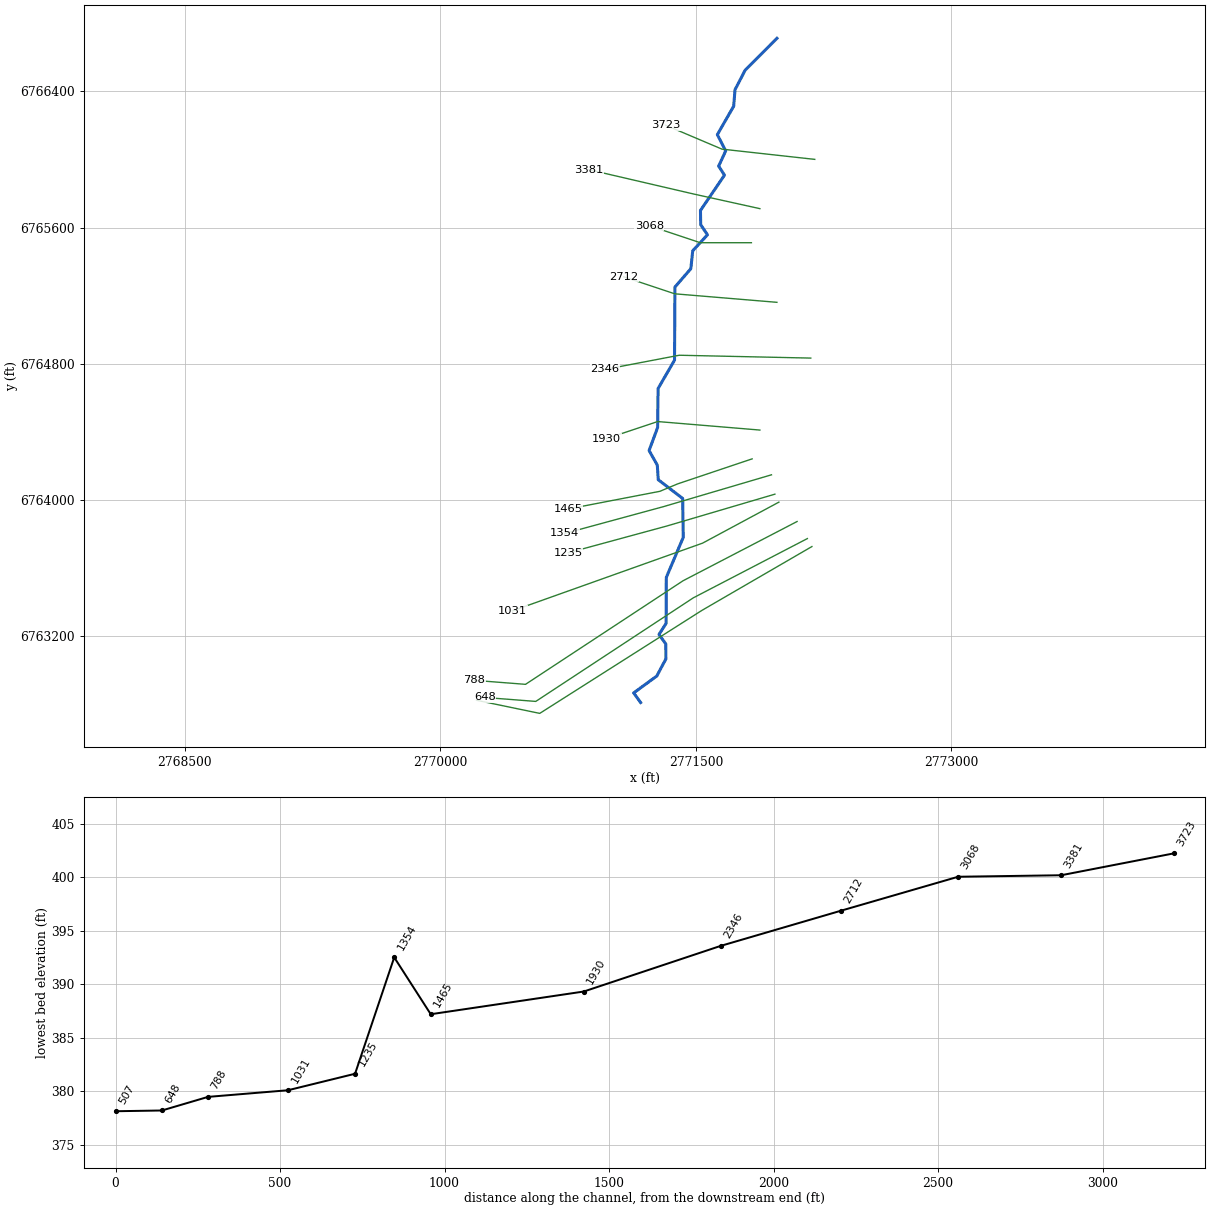
--- Walnut1.prj (project) ---

Proj Title=Walnut1 Base Level Engineering
Current Plan=p01
Default Exp/Contr=0.3,0.1
English Units
Geom File=g01
Flow File=f01
Plan File=p01
BEGIN DESCRIPTION:
Walnut1
END DESCRIPTION:

--- Walnut1.p01 (plan) ---

Plan Title=Multiple Run
Short Identifier=Multiple
Geom File=g01
Flow File=f01
Subcritical Flow
K Sum by GR= 0
Std Step Tol= 0.01
Critical Tol= 0.01
Num of Std Step Trials= 20
Max Error Tol= 0.3
Flow Tol Ratio= 0.001
Split Flow NTrial= 30
Split Flow Tol= 0.02
Split Flow Ratio= 0.02
Log Output Level= 0
Friction Slope Method= 1
Unsteady Friction Slope Method= 2
Unsteady Bridges Friction Slope Method= 1
Parabolic Critical Depth
Global Vel Dist=  1 , 1 , 1
Global Log Level= 0
CheckData=True
Encroach Param= -1, 0, 0, 0
BEGIN DESCRIPTION:
Multiple Run
END DESCRIPTION:

--- Walnut1.f01 (steady flow) ---

Flow Title=Multiple
Number of Profiles=7
Profile Names=10-year,25-year,50-year,1pct_min,100-year,1pct_plu,500-year
River Rch & RM= Walnut1,Reach-1,3723
     489     659     798     482     962    1919    1396
River Rch & RM= Walnut1,Reach-1,2712
     718     990    1218     745    1486    2965    2217
Boundary for River Rch & Prof#=Walnut1,Reach-1,1
Up Type=0
Dn Type=3
Dn Slope=0.005
Boundary for River Rch & Prof#=Walnut1,Reach-1,2
Up Type=0
Dn Type=3
Dn Slope=0.005
Boundary for River Rch & Prof#=Walnut1,Reach-1,3
Up Type=0
Dn Type=3
Dn Slope=0.005
Boundary for River Rch & Prof#=Walnut1,Reach-1,4
Up Type=0
Dn Type=3
Dn Slope=0.005
Boundary for River Rch & Prof#=Walnut1,Reach-1,5
Up Type=0
Dn Type=3
Dn Slope=0.005
Boundary for River Rch & Prof#=Walnut1,Reach-1,6
Up Type=0
Dn Type=3
Dn Slope=0.005
Boundary for River Rch & Prof#=Walnut1,Reach-1,7
Up Type=0
Dn Type=3
Dn Slope=0.005

--- Walnut1.g01 (geometry) ---

Geom Title=Existing Conditions

River Reach=Walnut1,Reach-1
Reach XY= 30
      2771976.00      6766711.00      2771789.62      6766524.22
      2771729.83      6766409.42      2771722.17      6766312.58
      2771626.08      6766145.61      2771675.17      6766050.30
      2771633.84      6765960.91      2771667.99      6765907.67
      2771527.09      6765700.45      2771528.37      6765616.89
      2771568.19      6765557.59      2771481.55      6765463.43
      2771470.46      6765358.58      2771377.06      6765250.56
      2771374.80      6764821.50      2771278.24      6764655.07
      2771275.48      6764426.22      2771225.40      6764290.95
      2771273.60      6764204.94      2771279.16      6764119.34
      2771422.47      6764009.55      2771425.93      6763781.03
      2771326.52      6763545.78      2771325.34      6763276.16
      2771283.56      6763211.00      2771323.64      6763155.11
      2771323.86      6763066.94      2771270.41      6762966.61
      2771134.76      6762867.69      2771176.00      6762811.00

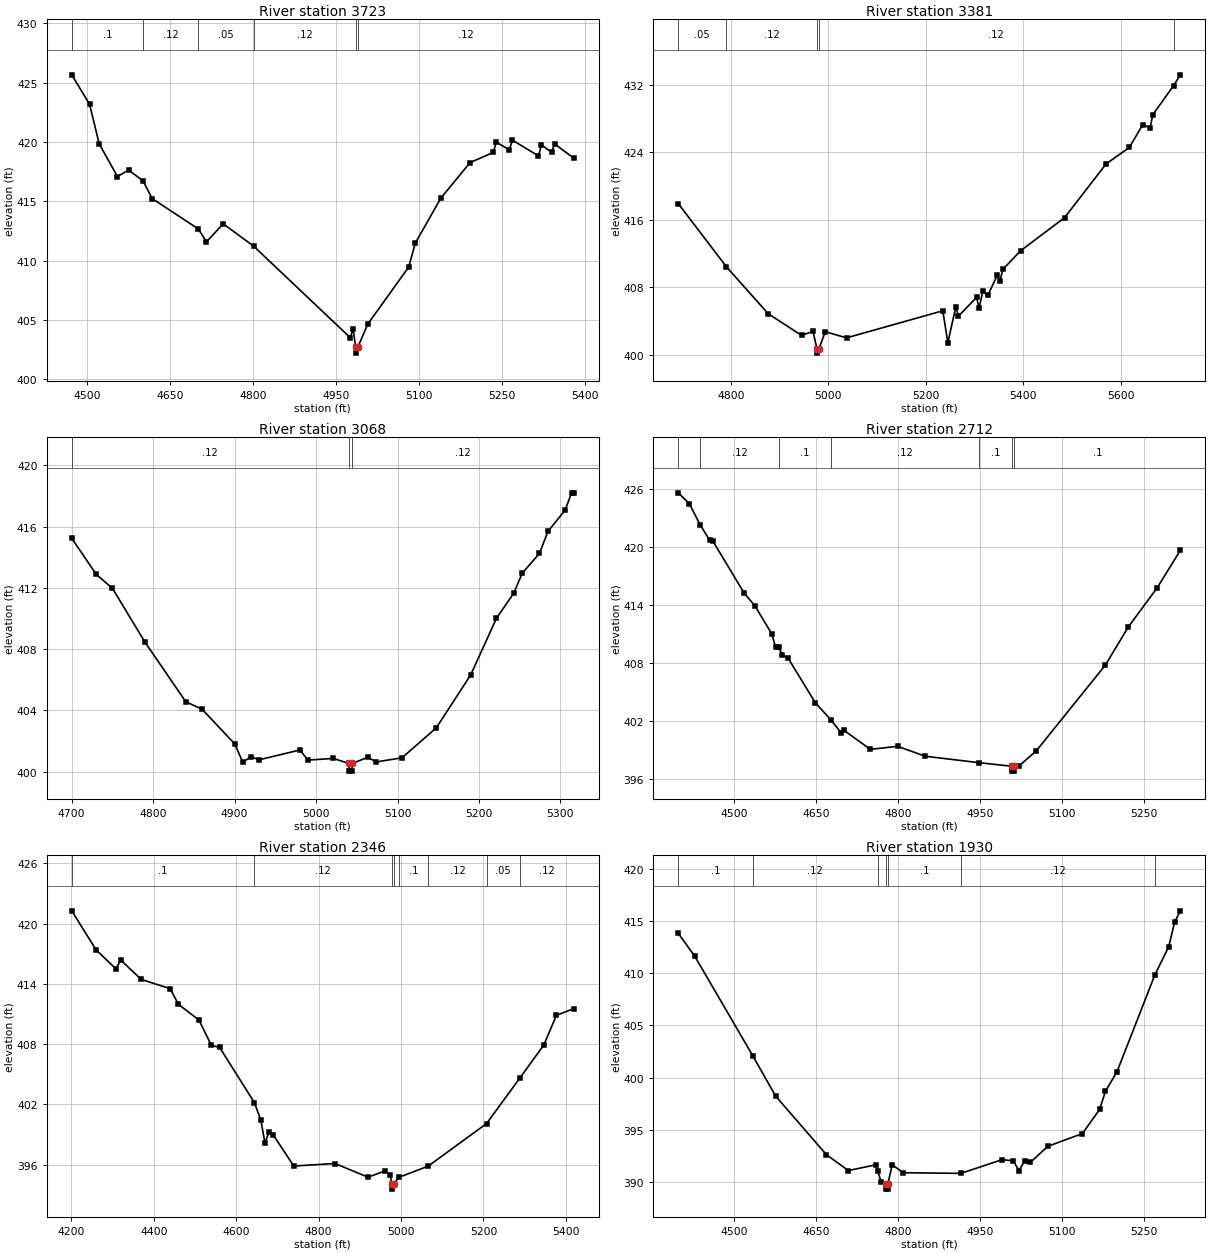
Type RM Length L Ch R = 1,3723,342,342,342
BEGIN DESCRIPTION:
Walnut1 9.0
END DESCRIPTION:
XS GIS Cut Line= 3
      2772198.10      6766000.34      2771653.20      6766060.51
      2771322.26      6766200.91
#Sta/Elev= 30
  4471.6  425.65  4503.9  423.16  4521.1  419.85  4554.2  417.08  4574.3  417.63
  4600.5  416.72  4617.0  415.23  4700.3  412.67  4715.2  411.59  4745.4  413.10
  4800.2  411.23  4975.2  403.51  4980.3  404.26  4984.8  402.71  4985.1  402.21
  4988.8  402.71  5006.9  404.66  5080.8  409.46  5092.8  411.48  5139.0  415.27
  5191.8  418.26  5233.7  419.11  5239.1  419.98  5262.8  419.33  5268.2  420.15
  5315.5  418.82  5320.9  419.75  5339.2  419.12  5344.6  419.83  5379.3  418.63
#Mann=6,-1,0
  4471.6     0.1       0  4600.5    0.12       0  4700.3    0.05       0
  4800.2    0.12       0  4984.8    0.07       0  4988.8    0.12       0
Bank Sta=4984.8,4988.8
Exp/Cntr=0.3,0.1

Type RM Length L Ch R = 1,3381,313,313,313
BEGIN DESCRIPTION:
Walnut1 8.0
END DESCRIPTION:
XS GIS Cut Line= 3
      2771876.05      6765710.99      2771489.39      6765796.41
      2770870.95      6765940.15
#Sta/Elev= 30
  4691.8  417.89  4790.4  410.42  4876.2  404.85  4944.8  402.28  4968.4  402.74
  4976.6  400.67  4976.8  400.17  4980.6  400.67  4993.6  402.71  5037.2  401.98
  5235.0  405.19  5245.3  401.40  5261.7  405.67  5266.8  404.54  5304.3  406.78
  5309.4  405.50  5317.1  407.49  5327.4  407.01  5346.9  409.42  5352.0  408.67
  5358.2  410.09  5394.6  412.30  5485.0  416.23  5570.3  422.60  5618.0  424.55
  5645.7  427.27  5660.6  426.85  5666.2  428.43  5709.0  431.89  5722.7  433.16
#Mann=5,-1,0
  4691.8    0.05       0  4790.4    0.12       0  4976.6    0.07       0
  4980.6    0.12       0  5709.0     0.1       0
Bank Sta=4976.6,4980.6
Exp/Cntr=0.3,0.1

Type RM Length L Ch R = 1,3068,356,356,356
BEGIN DESCRIPTION:
Walnut1 7.0
END DESCRIPTION:
XS GIS Cut Line= 3
      2771826.04      6765511.00      2771526.00      6765511.00
      2771225.97      6765611.01
#Sta/Elev= 30
  4700.1  415.23  4730.1  412.88  4750.1  411.96  4790.1  408.44  4840.1  404.56
  4860.1  404.07  4900.1  401.81  4910.1  400.61  4920.1  400.97  4930.1  400.77
  4980.1  401.41  4990.1  400.75  5021.2  400.86  5040.3  400.53  5040.6  400.03
  5044.1  400.03  5044.3  400.53  5063.4  400.93  5073.9  400.63  5105.5  400.90
  5147.7  402.86  5189.9  406.32  5221.5  410.01  5242.6  411.64  5253.1  412.95
  5274.2  414.24  5284.7  415.68  5305.8  417.07  5313.7  418.20  5316.4  418.20
#Mann=3,-1,0
  4700.1    0.12       0  5040.3    0.07       0  5044.3    0.12       0
Bank Sta=5040.3,5044.3
Exp/Cntr=0.3,0.1

Type RM Length L Ch R = 1,2712,366,366,366
BEGIN DESCRIPTION:
Walnut1 6.0
END DESCRIPTION:
XS GIS Cut Line= 3
      2771975.98      6765161.00      2771376.00      6765211.00
      2771075.99      6765311.00
#Sta/Elev= 30
  4397.5  425.60  4417.5  424.49  4437.7  422.28  4455.2  420.68  4460.2  420.67
  4517.9  415.25  4538.0  413.90  4568.1  411.07  4575.6  409.65  4581.2  409.63
  4588.1  408.84  4598.2  408.54  4648.3  403.91  4676.2  402.18  4696.0  400.77
  4701.0  401.06  4748.7  399.11  4798.9  399.42  4849.0  398.40  4947.8  397.73
  5008.1  397.36  5008.4  396.86  5011.9  396.86  5012.1  397.36  5020.6  397.39
  5052.3  398.95  5178.8  407.82  5220.9  411.77  5273.6  415.80  5315.8  419.66
#Mann=7,-1,0
  4397.5    0.05       0  4437.7    0.12       0  4581.2     0.1       0
  4676.2    0.12       0  4947.8     0.1       0  5008.1    0.07       0
  5012.1     0.1       0
Bank Sta=5008.1,5012.1
Exp/Cntr=0.3,0.1

Type RM Length L Ch R = 1,2346,416,416,416
BEGIN DESCRIPTION:
Walnut1 5.0
END DESCRIPTION:
XS GIS Cut Line= 3
      2772174.67      6764833.61      2771402.47      6764850.32
      2770964.56      6764766.75
#Sta/Elev= 30
  4201.1  421.28  4259.8  417.41  4308.2  415.50  4319.8  416.38  4369.8  414.45
  4439.8  413.53  4459.8  411.98  4509.8  410.40  4539.9  407.88  4559.9  407.68
  4644.3  402.18  4659.9  400.44  4669.9  398.16  4679.9  399.26  4689.9  398.97
  4739.9  395.87  4839.9  396.12  4919.9  394.76  4960.0  395.36  4973.5  395.02
  4978.1  394.07  4978.3  393.57  4982.1  394.07  4994.6  394.74  5066.0  395.86
  5207.7  400.10  5288.6  404.64  5346.6  407.92  5377.1  410.87  5419.3  411.54
#Mann=8,-1,0
  4201.1     0.1       0  4644.3    0.12       0  4978.1    0.07       0
  4982.1    0.12       0  4994.6     0.1       0  5066.0    0.12       0
  5207.7    0.05       0  5288.6    0.12       0
Bank Sta=4978.1,4982.1
Exp/Cntr=0.3,0.1

Type RM Length L Ch R = 1,1930,465,465,465
BEGIN DESCRIPTION:
Walnut1 4.0
END DESCRIPTION:
XS GIS Cut Line= 3
      2771876.00      6764411.00      2771276.00      6764461.00
      2770976.01      6764361.00
#Sta/Elev= 30
  4398.3  413.81  4428.4  411.62  4534.6  402.08  4576.4  398.22  4669.2  392.61
  4709.4  391.09  4759.6  391.64  4763.2  391.03  4769.6  389.95  4777.6  389.81
  4777.9  389.31  4781.4  389.31  4781.6  389.81  4789.7  391.64  4809.7  390.88
  4915.3  390.82  4990.3  392.13  5010.9  392.03  5021.5  391.09  5032.0  392.02
  5042.5  391.88  5074.2  393.41  5137.4  394.63  5169.0  396.94  5179.6  398.68
  5200.7  400.55  5269.9  409.81  5295.5  412.55  5306.1  414.88  5316.6  415.97
#Mann=7,-1,0
  4398.3     0.1       0  4534.6    0.12       0  4763.2     0.1       0
  4777.6    0.07       0  4781.6     0.1       0  4915.3    0.12       0
  5269.9    0.05       0
Bank Sta=4777.6,4781.6
Exp/Cntr=0.3,0.1

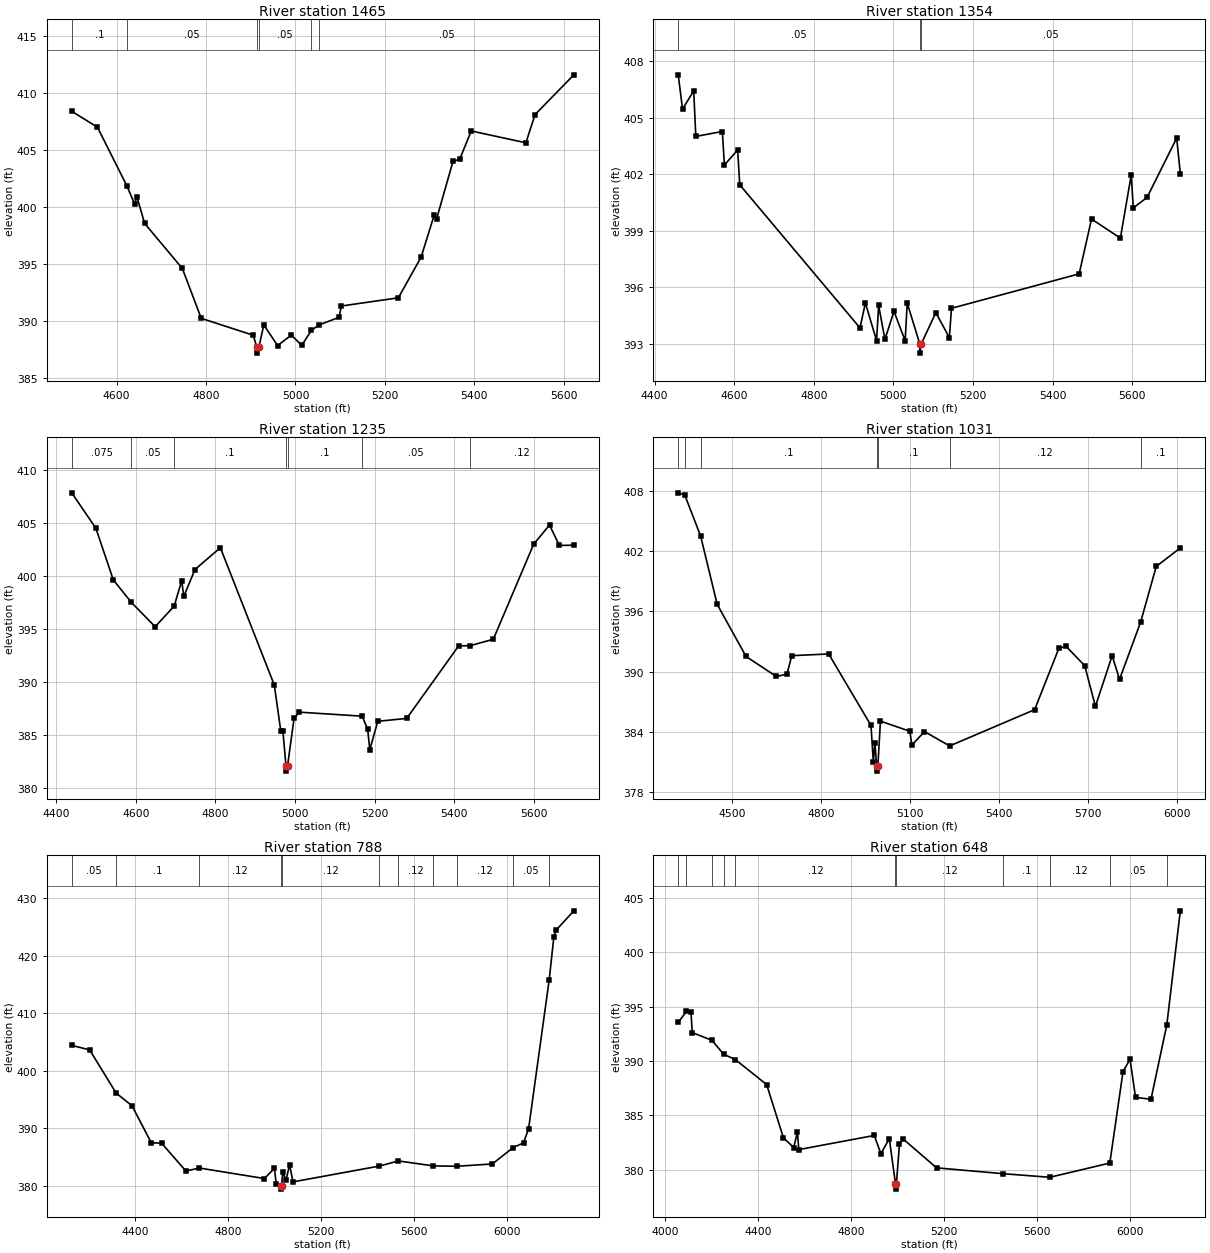
Type RM Length L Ch R = 1,1465,111,111,111
BEGIN DESCRIPTION:
Walnut1 3.0
END DESCRIPTION:
XS GIS Cut Line= 4
      2771830.38      6764241.89      2771392.44      6764094.79
      2771288.80      6764051.33      2770750.75      6763947.73
#Sta/Elev= 30
  4500.0  408.39  4557.4  407.00  4623.2  401.85  4640.3  400.28  4645.6  400.90
  4662.9  398.56  4747.2  394.61  4789.4  390.24  4905.5  388.76  4914.0  387.69
  4914.3  387.19  4918.0  387.69  4929.3  389.66  4960.1  387.85  4990.7  388.77
  5014.2  387.87  5035.7  389.19  5052.9  389.66  5097.5  390.33  5102.6  391.32
  5230.0  392.04  5280.9  395.61  5310.2  399.30  5315.3  398.93  5352.2  404.01
  5367.2  404.19  5392.9  406.67  5515.1  405.63  5535.5  408.10  5622.3  411.59
#Mann=6,-1,0
  4500.0     0.1       0  4623.2    0.05       0  4914.0    0.05       0
  4918.0    0.05       0  5035.7    0.12       0  5052.9    0.05       0
Bank Sta=4914,4918
Exp/Cntr=0.3,0.1

Type RM Length L Ch R = 1,1354,119,119,119
BEGIN DESCRIPTION:
Walnut1 2.5
END DESCRIPTION:
XS GIS Cut Line= 3
      2771944.01      6764148.27      2771308.86      6763961.07
      2770730.77      6763804.02
#Sta/Elev= 30
  4459.6  407.28  4470.4  405.46  4498.5  406.43  4503.7  404.01  4570.4  404.27
  4575.6  402.49  4608.9  403.29  4614.1  401.44  4916.2  393.84  4929.7  395.16
  4957.8  393.17  4963.0  395.03  4978.8  393.23  5001.5  394.72  5029.6  393.16
  5034.8  395.16  5066.2  393.00  5066.4  392.50  5070.2  393.00  5106.7  394.65
  5140.7  393.32  5145.9  394.88  5466.7  396.71  5497.8  399.62  5570.3  398.61
  5597.5  401.96  5602.7  400.21  5637.3  400.77  5711.7  403.92  5720.8  402.03
#Mann=3,-1,0
  4459.6    0.05       0  5066.2    0.05       0  5070.2    0.05       0
Bank Sta=5066.2,5070.2
Exp/Cntr=0.3,0.1

Type RM Length L Ch R = 1,1235,204,204,204
BEGIN DESCRIPTION:
Walnut1 2.0
END DESCRIPTION:
XS GIS Cut Line= 3
      2771964.09      6764034.61      2771328.92      6763847.41
      2770750.76      6763690.33
#Sta/Elev= 30
  4439.1  407.82  4499.7  404.48  4543.4  399.63  4588.3  397.53  4648.6  395.22
  4696.3  397.16  4715.3  399.55  4720.5  398.07  4748.6  400.60  4812.4  402.66
  4947.9  389.73  4964.2  385.41  4969.4  385.45  4977.2  382.13  4977.5  381.63
  4981.2  382.13  4997.5  386.59  5010.5  387.18  5168.7  386.80  5182.5  385.55
  5187.7  383.65  5207.9  386.32  5280.5  386.59  5410.9  393.41  5440.5  393.44
  5498.1  394.04  5599.5  402.99  5639.3  404.79  5663.9  402.87  5700.4  402.89
#Mann=7,-1,0
  4439.1   0.075       0  4588.3    0.05       0  4696.3     0.1       0
  4977.2    0.07       0  4981.2     0.1       0  5168.7    0.05       0
  5440.5    0.12       0
Bank Sta=4977.2,4981.2
Exp/Cntr=0.3,0.1

Type RM Length L Ch R = 1,1031,243,243,243
BEGIN DESCRIPTION:
Walnut1 1.5
END DESCRIPTION:
XS GIS Cut Line= 3
      2771987.51      6763987.82      2771539.53      6763747.11
      2770422.94      6763349.28
#Sta/Elev= 30
  4318.0  407.81  4340.2  407.58  4393.6  403.50  4449.4  396.70  4546.8  391.51
  4648.9  389.52  4684.8  389.75  4701.1  391.59  4825.7  391.76  4968.3  384.64
  4976.2  381.00  4981.5  382.88  4987.5  380.59  4987.8  380.09  4991.5  380.59
  5000.2  385.07  5099.5  384.06  5106.3  382.68  5148.8  384.03  5233.6  382.60
  5520.4  386.21  5602.2  392.32  5626.5  392.52  5689.4  390.59  5725.5  386.54
  5781.9  391.58  5806.9  389.23  5878.3  394.96  5930.7  400.48  6011.9  402.32
#Mann=7,-1,0
  4318.0   0.075       0  4340.2    0.05       0  4393.6     0.1       0
  4987.5    0.07       0  4991.5     0.1       0  5233.6    0.12       0
  5878.3     0.1       0
Bank Sta=4987.5,4991.5
Exp/Cntr=0.3,0.1

Type RM Length L Ch R = 1,788,140,140,140
BEGIN DESCRIPTION:
Walnut1 1.0
END DESCRIPTION:
XS GIS Cut Line= 4
      2772094.44      6763874.13      2771424.89      6763526.22
      2770499.84      6762918.03      2770199.96      6762941.36
#Sta/Elev= 30
  4127.0  404.42  4204.1  403.63  4318.1  396.14  4386.6  393.93  4469.5  387.51
  4513.7  387.45  4618.6  382.61  4676.5  383.13  4956.4  381.31  4999.9  383.07
  5007.6  380.34  5026.7  379.97  5026.9  379.47  5030.7  379.97  5035.8  382.45
  5049.8  380.99  5064.8  383.72  5079.9  380.73  5451.2  383.47  5533.8  384.36
  5684.4  383.50  5787.1  383.44  5938.5  383.84  6027.5  386.67  6072.7  387.50
  6094.6  389.98  6183.2  415.78  6203.1  423.17  6213.1  424.42  6289.4  427.77
#Mann=11,-1,0
  4127.0    0.05       0  4318.1     0.1       0  4676.5    0.12       0
  5026.7    0.07       0  5030.7    0.12       0  5451.2     0.1       0
  5533.8    0.12       0  5684.4     0.1       0  5787.1    0.12       0
  6027.5    0.05       0  6183.2   0.075       0
Bank Sta=5026.7,5030.7
Exp/Cntr=0.3,0.1

Type RM Length L Ch R = 1,648,141,141,141
BEGIN DESCRIPTION:
Walnut1 0.8
END DESCRIPTION:
XS GIS Cut Line= 4
      2772154.65      6763773.85      2771485.07      6763425.92
      2770560.02      6762817.74      2770260.07      6762841.07
#Sta/Elev= 30
  4055.4  393.54  4090.6  394.56  4110.2  394.54  4115.8  392.61  4200.7  391.90
  4250.8  390.62  4301.2  390.13  4436.3  387.82  4508.2  382.94  4552.5  382.03
  4568.9  383.44  4574.6  381.84  4899.7  383.14  4928.5  381.45  4964.4  382.85
  4991.1  378.70  4991.4  378.20  4995.1  378.70  5008.2  382.34  5023.3  382.83
  5167.9  380.16  5455.1  379.62  5655.7  379.29  5914.2  380.60  5971.2  389.02
  6001.3  390.16  6025.0  386.65  6091.6  386.47  6159.7  393.31  6217.9  403.82
#Mann=11,-1,0
  4055.4    0.12       0  4090.6     0.1       0  4200.7    0.12       0
  4250.8     0.1       0  4301.2    0.12       0  4991.1    0.07       0
  4995.1    0.12       0  5455.1     0.1       0  5655.7    0.12       0
  5914.2    0.05       0  6159.7   0.075       0
Bank Sta=4991.1,4995.1
Exp/Cntr=0.3,0.1

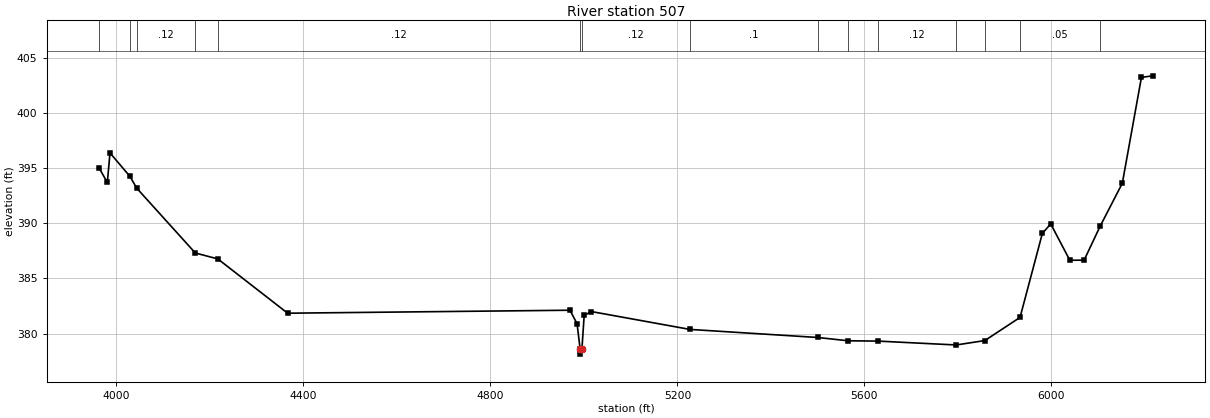
Type RM Length L Ch R = 1,507,0,0,0
BEGIN DESCRIPTION:
Walnut1 0.6
END DESCRIPTION:
XS GIS Cut Line= 4
      2772181.43      6763727.07      2771536.19      6763352.63
      2770583.42      6762747.54      2770212.29      6762824.44
#Sta/Elev= 30
  3963.3  394.97  3980.4  393.69  3986.1  396.37  4028.6  394.25  4043.4  393.17
  4168.6  387.30  4216.8  386.76  4366.2  381.84  4970.2  382.11  4985.4  380.88
  4991.8  378.63  4992.1  378.13  4995.8  378.63  5000.6  381.64  5015.9  381.99
  5226.9  380.37  5499.9  379.64  5565.2  379.34  5629.6  379.31  5796.3  378.96
  5857.8  379.36  5933.1  381.46  5980.8  389.07  5998.7  389.94  6039.6  386.64
  6070.2  386.65  6104.4  389.72  6151.9  393.62  6192.8  403.22  6217.0  403.36
#Mann=15,-1,0
  3963.3    0.12       0  4028.6     0.1       0  4043.4    0.12       0
  4168.6     0.1       0  4216.8    0.12       0  4991.8    0.07       0
  4995.8    0.12       0  5226.9     0.1       0  5499.9    0.12       0
  5565.2     0.1       0  5629.6    0.12       0  5796.3     0.1       0
  5857.8    0.12       0  5933.1    0.05       0  6104.4   0.075       0
Bank Sta=4991.8,4995.8
Exp/Cntr=0.3,0.1

Chan Stop Cuts=-1