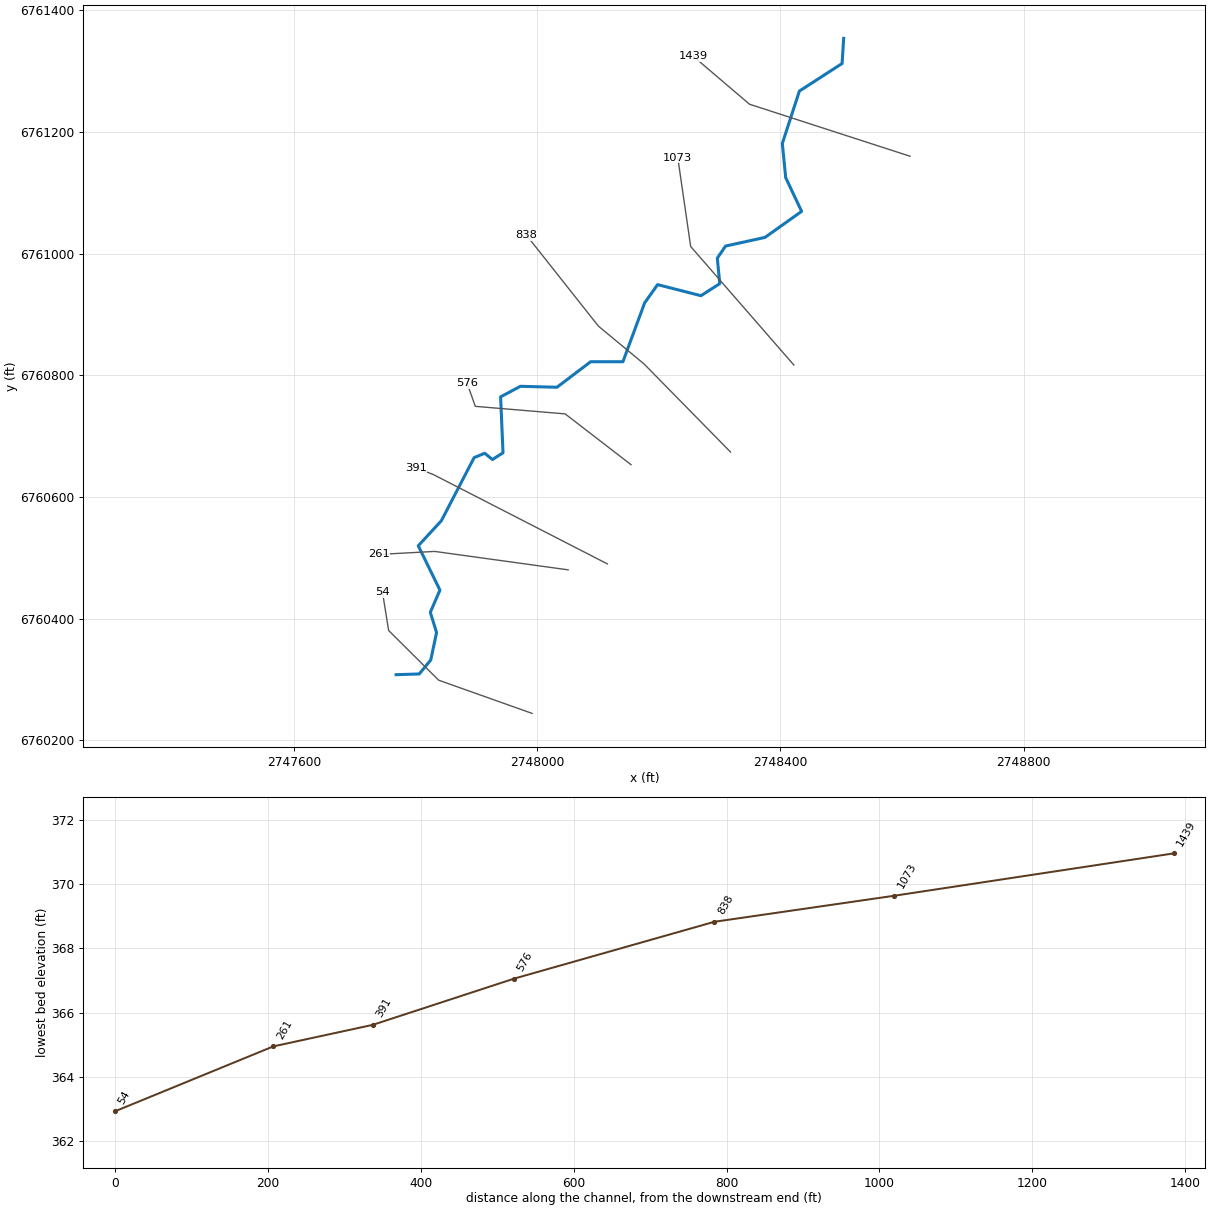
--- Walnut100.prj (project) ---

Proj Title=Walnut100 Base Level Engineering
Current Plan=p01
Default Exp/Contr=0.3,0.1
English Units
Geom File=g01
Flow File=f01
Plan File=p01
Y Axis Title=Elevation
X Axis Title(PF)=Main Channel Distance
X Axis Title(XS)=Station
BEGIN DESCRIPTION:
Walnut100
END DESCRIPTION:
DSS Export Rating Curves= 0
DSS Export Rating Curve Sorted= 0
DSS Export Volume Flow Curves= 0
DXF OffsetX= 0
DXF OffsetY= 0
DXF ScaleX= 1
DXF ScaleY= 10

--- Walnut100.p01 (plan) ---

Plan Title=Multiple Run
Program Version=4.10
Short Identifier=Multiple
Geom File=g01
Flow File=f01
Subcritical Flow
K Sum by GR= 0
Std Step Tol= 0.01
Critical Tol= 0.01
Num of Std Step Trials= 20
Max Error Tol= 0.3
Flow Tol Ratio= 0.001
Split Flow NTrial= 30
Split Flow Tol= 0.02
Split Flow Ratio= 0.02
Log Output Level= 0
Friction Slope Method= 1
Unsteady Friction Slope Method= 2
Unsteady Bridges Friction Slope Method= 1
Parabolic Critical Depth
Global Vel Dist= 1 , 1 , 1
Global Log Level= 0
CheckData=True
Encroach Param=-1 ,0,0, 0
BEGIN DESCRIPTION:
Multiple Run
END DESCRIPTION:
Computation Interval=1HOUR
Output Interval=1HOUR
Run HTab= 0
Run UNet= 0
Run PostProcess= 0
Run WQNet= 0
UNET Theta= 1
UNET Theta Warmup= 1
UNET ZTol= 0.02
UNET ZSATol= 0.05
UNET MxIter= 20
UNET MaxInSteps= 0
UNET DtIC= 0
UNET DtMin= 0
UNET MaxCRTS= 20
UNET WFStab= 2
UNET SFStab= 1
UNET WFX= 1
UNET SFX= 1
UNET DSS MLevel= 4
UNET DZMax Abort= 100
UNET Convert EG Bridges= 0
UNET Use Existing IB Tables=-1
UNET Froude Reduction=False
UNET Froude Limit= 1
UNET Froude Power= 10
UNET Time Slicing=0,0, 5
UNET Junction Losses=0
Instantaneous Interval=1HOUR
Write IC File= 0
Write IC File at Sim End=0
Echo Input=False
Echo Parameters=False
Echo Output=False
Write Detailed= 0
WQ AD Non Conservative
WQ ULTIMATE=-1
WQ Max Comp Step=1HOUR
WQ Output Interval=15MIN
WQ Output Selected Increments= 0
WQ Output face flow=0
WQ Output face velocity=0
WQ Output face area=0
WQ Output face dispersion=0
WQ Output cell volume=0
WQ Output cell surface area=0
WQ Output cell continuity=0
WQ Output cumulative cell continuity=0
WQ Output face conc=0
WQ Output face dconc_dx=0
WQ Output face courant=0
WQ Output face peclet=0
WQ Output face adv mass=0
WQ Output face disp mass=0
WQ Output cell mass=0
WQ Output cell source sink temp=0
WQ Output cell source sink nsm=0
WQ Output MaxMinRange=-1
WQ Daily Max Min Mean=-1
WQ Daily Range=0
WQ Daily Time=0
WQ Create Restart=0
WQ Fixed Restart=0
WQ System Summary=0
WQ Use Fixed Temperature=0
Sorting and Armoring Iterations= 10
XS Update Threshold= 0.02
Hydraulics Update Threshold= 0.02
Energy Slope Method= 1
Volume Change Method= 0
XS Weighting Method= 0
Number of US Weighted Cross Sections= 1
Number of DS Weighted Cross Sections= 1
Upstream XS Weight=0.25
Main XS Weight=0.5
Downstream XS Weight=0.25
Number of DS XS's Weighted with US Boundary= 1
Upstream Boundary Weight= 1
Weight of XSs Associated with US Boundary= 0
Number of US XS's Weighted with DS Boundary= 1
Downstream Boundary Weight= 0.5
Weight of XSs Associated with DS Boundary= 0.5
Sediment Output Level= 4
Mass or Volume Output= 0
Output Increment Type= 1
Profile and TS Output Increment= 10
XS Output Flag= 0
XS Output Increment= 10
Disregard all LS=0
Disregard all Conn=0
Disregard all Breaches=0
Disregard all Pumps=0

--- Walnut100.f01 (steady flow) ---

Flow Title=Multiple
Number of Profiles=7
Profile Names=10-year,25-year,50-year,1pct_min,100-year,1pct_plu,500-year
River Rch & RM= Walnut100,Reach-1,1439
     264     340     399     234     467     931     638
River Rch & RM= Walnut100,Reach-1,54
     390     509     602     354     707    1411     976
Boundary for River Rch & Prof#=Walnut100,Reach-1,1
Up Type=0
Dn Type=3
Dn Slope=0.01
Boundary for River Rch & Prof#=Walnut100,Reach-1,2
Up Type=0
Dn Type=3
Dn Slope=0.01
Boundary for River Rch & Prof#=Walnut100,Reach-1,3
Up Type=0
Dn Type=3
Dn Slope=0.01
Boundary for River Rch & Prof#=Walnut100,Reach-1,4
Up Type=0
Dn Type=3
Dn Slope=0.01
Boundary for River Rch & Prof#=Walnut100,Reach-1,5
Up Type=0
Dn Type=3
Dn Slope=0.01
Boundary for River Rch & Prof#=Walnut100,Reach-1,6
Up Type=0
Dn Type=3
Dn Slope=0.01
Boundary for River Rch & Prof#=Walnut100,Reach-1,7
Up Type=0
Dn Type=3
Dn Slope=0.01

--- Walnut100.g01 (geometry) ---

Geom Title=Existing Conditions
Program Version=4.10

River Reach=Walnut100       ,Reach-1
Reach XY= 30
      2748504.04        6761354.      2748501.45      6761312.63
      2748431.19       6761267.3      2748403.14      6761181.21
      2748408.69      6761124.97      2748434.83      6761069.53
      2748374.63      6761026.75      2748309.68       6761012.5
      2748296.21      6760992.69      2748300.17      6760950.71
      2748269.28      6760930.91      2748197.99      6760949.13
       2748176.6      6760919.03      2748140.96      6760822.39
      2748087.89      6760822.39      2748032.44      6760780.41
      2747972.24      6760781.99      2747939.76      6760764.57
      2747943.72      6760672.68       2747926.3      6760661.59
      2747913.62      6760671.89       2747896.2      6760664.76
      2747842.34        6760561.      2747804.31      6760519.81
      2747839.96      6760446.93      2747824.12       6760410.5
      2747834.41      6760377.23      2747824.91      6760332.08
       2747805.9      6760309.11      2747767.95       6760307.9

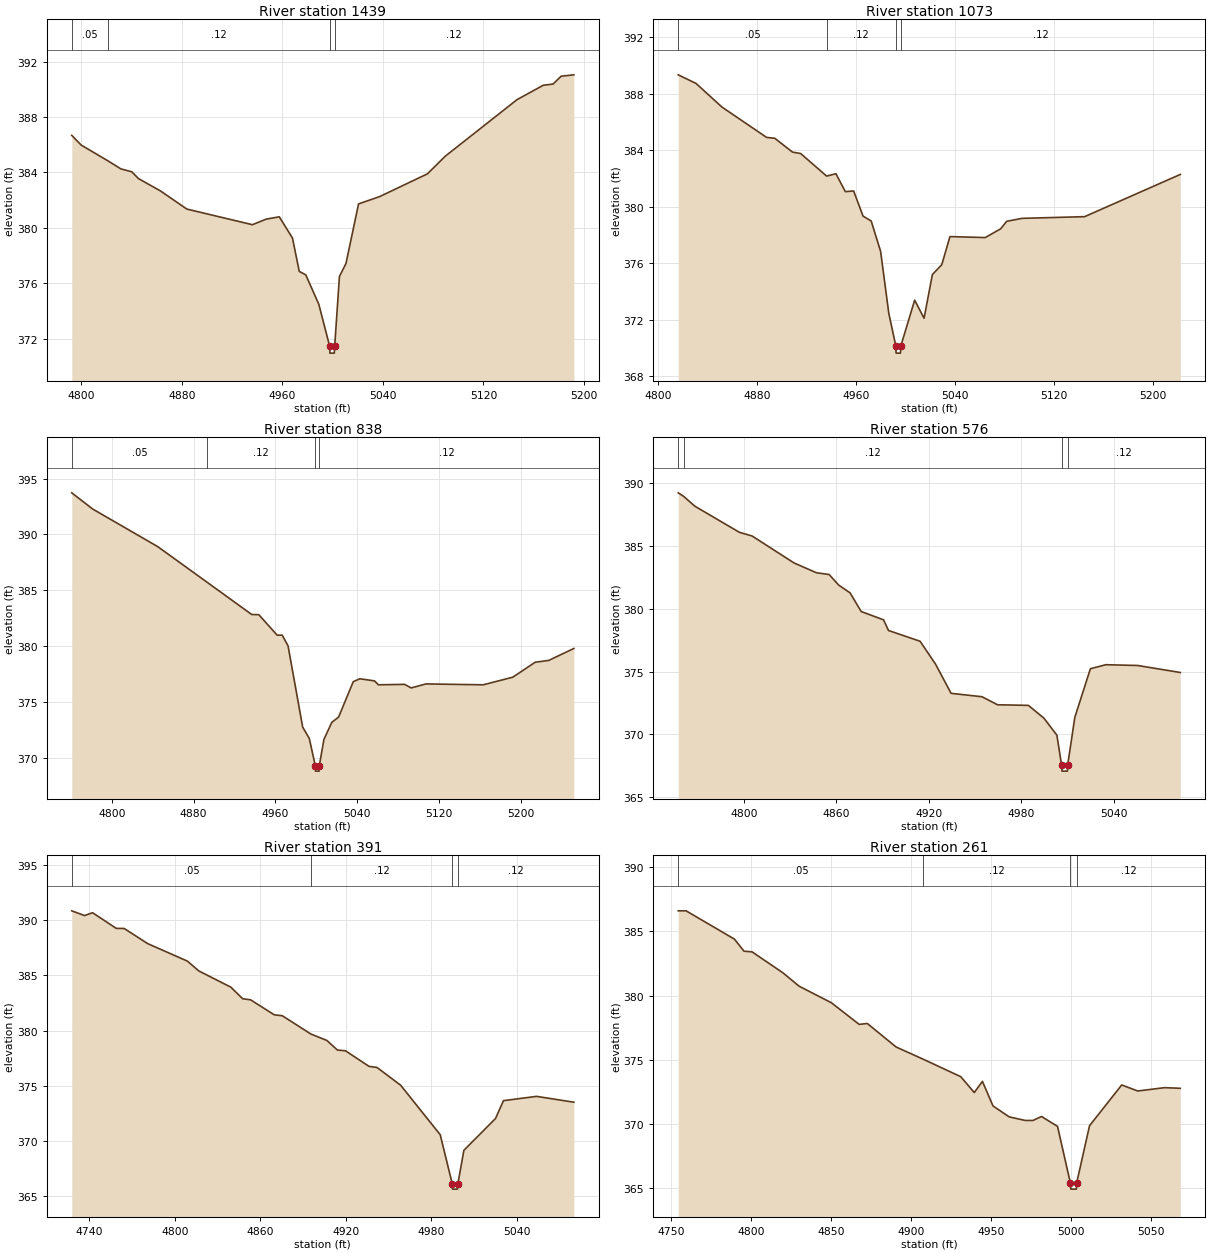
Type RM Length L Ch R = 1 ,1439    ,366,366,366
BEGIN DESCRIPTION:
Walnut100 10.0
END DESCRIPTION:
XS GIS Cut Line= 3
      2748613.18      6761160.19      2748349.19      6761245.67
      2748256.13       6761324.9
#Sta/Elev= 30
  4792.3  386.68  4799.8  385.98  4821.3  384.83  4831.4  384.26  4840.1  384.05
  4845.4  383.56  4862.9  382.67  4883.9  381.36  4936.1  380.23    4947  380.63
  4957.5   380.8    4968  379.27  4973.4  376.86  4978.6  376.61    4989  374.48
  4997.6  371.46  4997.8  370.96  5001.3  370.96  5001.6  371.46  5005.4   376.5
  5010.6  377.43  5020.6  381.73  5037.4  382.26  5075.4   383.9  5089.7  385.18
  5146.8  389.26  5167.7   390.3  5175.4  390.38  5181.9  390.95    5192  391.05
#Mann= 4 ,-1 , 0
  4792.3     .05       0  4821.3     .12       0  4997.6     .07       0
  5001.6     .12       0
Bank Sta=4997.6,5001.6
XS Rating Curve= 0 ,0
Exp/Cntr=0.3,0.1

Type RM Length L Ch R = 1 ,1073    ,235,235,235
BEGIN DESCRIPTION:
Walnut100 6.0
END DESCRIPTION:
XS GIS Cut Line= 3
       2748422.1      6760816.96      2748252.38      6761011.82
      2748231.22      6761157.48
#Sta/Elev= 30
  4816.2  389.34  4830.6  388.73  4851.5  387.06  4887.6  384.91  4894.2  384.85
  4908.5  383.87  4915.1  383.77  4936.1  382.17  4943.6  382.34  4951.2  381.07
  4957.9  381.12  4965.5  379.34  4972.1  378.99  4979.7  376.84  4986.3  372.46
    4992  370.14  4992.2  369.64  4995.7  369.64    4996  370.14  5007.2  373.39
  5014.8  372.11  5021.5   375.2  5029.1   375.9  5035.7  377.89  5064.2  377.82
  5076.7  378.44  5081.5  378.97    5094  379.18  5144.5   379.3  5221.8  382.29
#Mann= 4 ,-1 , 0
  4816.2     .05       0  4936.1     .12       0    4992     .07       0
    4996     .12       0
Bank Sta=4992,4996
XS Rating Curve= 0 ,0
Exp/Cntr=0.3,0.1

Type RM Length L Ch R = 1 ,838     ,262,262,262
BEGIN DESCRIPTION:
Walnut100 3.0
END DESCRIPTION:
XS GIS Cut Line= 4
      2748317.89      6760673.95      2748175.66      6760818.77
      2748100.68      6760880.83      2747982.08      6761030.66
#Sta/Elev= 30
  4760.8  393.72  4781.3  392.27  4844.9  388.91  4893.6   385.7  4936.9  382.84
  4943.9  382.82  4961.8  380.99  4966.8  380.99  4972.5  380.03  4986.8  372.77
  4993.3  371.75  4999.1  369.33  4999.4  368.83  5002.9  368.83  5003.1  369.33
  5007.6  371.67  5015.3  373.19    5022  373.67  5036.3  376.83  5042.8  377.09
  5057.1   376.9  5060.9  376.55  5086.6  376.59    5093  376.27  5107.5  376.63
  5163.5  376.55  5192.4  377.23  5214.4  378.57  5227.6  378.73  5252.2   379.8
#Mann= 4 ,-1 , 0
  4760.8     .05       0  4893.6     .12       0  4999.1     .07       0
  5003.1     .12       0
Bank Sta=4999.1,5003.1
XS Rating Curve= 0 ,0
Exp/Cntr=0.3,0.1

Type RM Length L Ch R = 1 ,576     ,185,185,185
BEGIN DESCRIPTION:
Walnut100 2.0
END DESCRIPTION:
XS GIS Cut Line= 4
      2748154.28      6760653.13       2748045.9      6760736.64
      2747898.14      6760749.02      2747884.63       6760787.1
#Sta/Elev= 30
  4757.5  389.24  4761.1  388.95  4768.2  388.18  4797.2  386.09  4805.4   385.8
  4832.6  383.65  4847.1  382.87  4855.3  382.73  4861.6  381.88  4868.9  381.27
  4876.1  379.78  4890.6  379.12  4893.8  378.27  4914.3  377.41  4924.3  375.59
  4934.4  373.26  4954.4  372.99  4964.5  372.35  4984.5   372.3  4994.6  371.28
    5003  369.92    5006  367.56  5006.3  367.06  5009.8  367.06    5010  367.56
  5014.6  371.34  5024.7  375.22  5034.7  375.54  5055.3  375.48    5083  374.92
#Mann= 4 ,-1 , 0
  4757.5     .05       0  4761.1     .12       0    5006     .07       0
    5010     .12       0
Bank Sta=5006,5010
XS Rating Curve= 0 ,0
Exp/Cntr=0.3,0.1

Type RM Length L Ch R = 1 ,391     ,130,130,130
BEGIN DESCRIPTION:
Walnut100 1.0
END DESCRIPTION:
XS GIS Cut Line= 3
      2748115.38      6760490.03      2747828.68      6760637.15
      2747800.37      6760647.83
#Sta/Elev= 30
  4727.6  390.85  4736.6  390.42  4742.2  390.68  4758.8  389.26  4764.4  389.25
    4781  387.87  4808.8  386.29  4816.8   385.4  4839.3  383.93  4847.6  382.88
  4853.2  382.78  4869.8  381.42  4875.4  381.34  4895.5  379.68  4906.7   379.1
  4914.1  378.23  4919.8  378.16  4936.3  376.75  4941.9  376.65  4958.5  375.04
  4986.3  370.55  4994.7  366.12  4994.9  365.62  4998.4  365.62  4998.7  366.12
  5002.9  369.14  5025.1  372.02  5030.7  373.64  5053.9  374.03  5080.1   373.5
#Mann= 4 ,-1 , 0
  4727.6     .05       0  4895.5     .12       0  4994.7     .07       0
  4998.7     .12       0
Bank Sta=4994.7,4998.7
XS Rating Curve= 0 ,0
Exp/Cntr=0.3,0.1

Type RM Length L Ch R = 1 ,261     ,207,207,207
BEGIN DESCRIPTION:
Walnut100 0.7
END DESCRIPTION:
XS GIS Cut Line= 3
       2748050.8      6760480.26      2747831.27      6760510.54
      2747739.41      6760505.57
#Sta/Elev= 30
  4754.7  386.59  4759.6  386.59  4789.8  384.39  4795.8  383.45  4800.8   383.4
  4820.1  381.77  4830.2  380.73  4850.4  379.44  4867.7  377.76  4872.8  377.83
  4890.8     376  4907.4  375.07  4931.2  373.69  4939.6  372.46  4944.7  373.33
  4951.3  371.42  4961.4  370.57  4971.4  370.29  4976.3  370.29  4981.6   370.6
  4991.6  369.83  4999.6  365.45  4999.9  364.95  5003.4  364.95  5003.6  365.45
  5011.6  369.88  5031.7  373.05  5041.7  372.58  5058.5  372.84  5068.3  372.79
#Mann= 4 ,-1 , 0
  4754.7     .05       0  4907.4     .12       0  4999.6     .07       0
  5003.6     .12       0
Bank Sta=4999.6,5003.6
XS Rating Curve= 0 ,0
Exp/Cntr=0.3,0.1

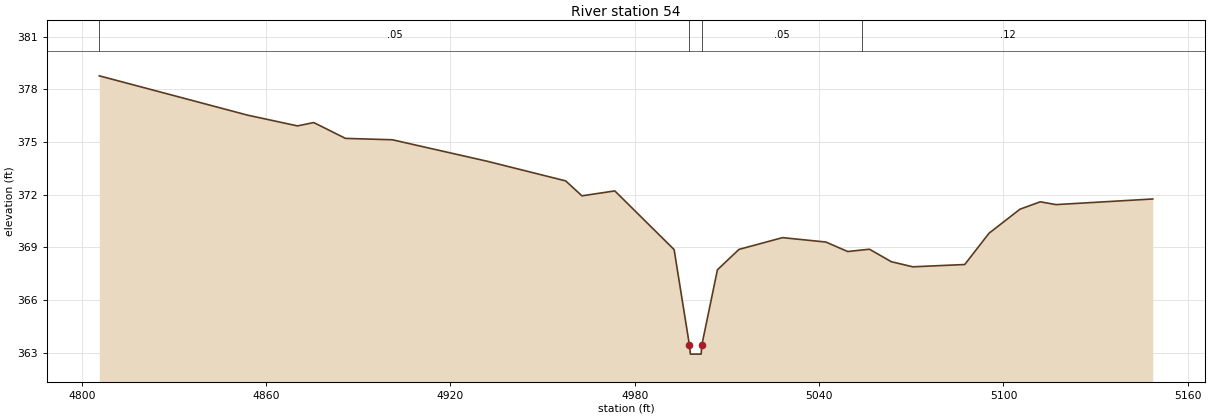
Type RM Length L Ch R = 1 ,54      ,0,0,0
BEGIN DESCRIPTION:
Walnut100 0.4
END DESCRIPTION:
XS GIS Cut Line= 4
      2747991.48      6760244.31      2747837.86      6760298.86
      2747755.56      6760380.57      2747745.46      6760443.68
#Sta/Elev= 30
  4805.7  378.77    4854  376.53  4870.2  375.92  4875.5  376.11  4885.8  375.21
  4901.1  375.13  4931.9  373.91  4957.5  372.79  4962.8  371.94  4973.5  372.22
  4992.8  368.88  4997.8  363.43  4998.1  362.93  5001.6  362.93  5001.8  363.43
  5006.9  367.73  5013.9  368.89  5028.1  369.56  5042.2  369.31  5049.3  368.77
  5054.1  368.86  5056.4   368.9  5063.5  368.19  5070.5   367.9  5087.4  368.03
  5095.3  369.81  5105.4  371.18    5112   371.6  5117.1  371.44  5148.6  371.76
#Mann= 4 ,-1 , 0
  4805.7     .05       0  4997.8     .07       0  5001.8     .05       0
  5054.1     .12       0
Bank Sta=4997.8,5001.8
XS Rating Curve= 0 ,0
Exp/Cntr=0.3,0.1

Chan Stop Cuts=-1
Use User Specified Reach Order=0
Composite Channel Slope=5