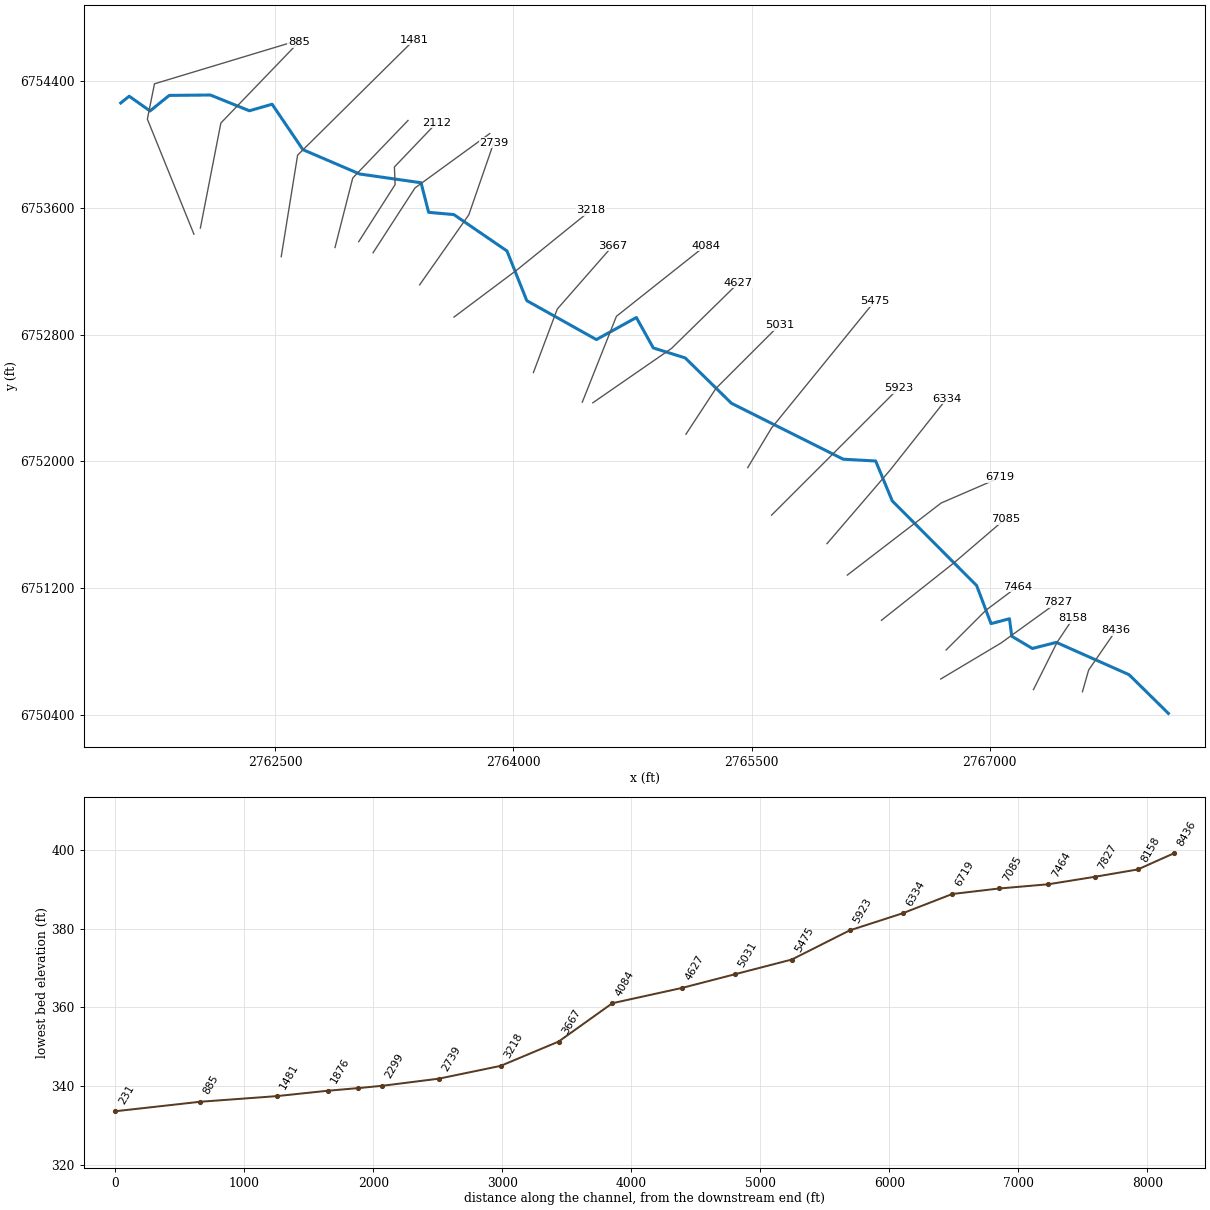
--- Walnut12.prj (project) ---

Proj Title=Walnut12 Base Level Engineering
Current Plan=p01
Default Exp/Contr=0.3,0.1
English Units
Geom File=g01
Flow File=f01
Plan File=p01
Y Axis Title=Elevation
X Axis Title(PF)=Main Channel Distance
X Axis Title(XS)=Station
BEGIN DESCRIPTION:
Walnut12
END DESCRIPTION:
DSS Export Rating Curves= 0
DSS Export Rating Curve Sorted= 0
DSS Export Volume Flow Curves= 0
DXF OffsetX= 0
DXF OffsetY= 0
DXF ScaleX= 1
DXF ScaleY= 10

--- Walnut12.p01 (plan) ---

Plan Title=Multiple Run
Short Identifier=Multiple
Geom File=g01
Flow File=f01
Subcritical Flow
K Sum by GR= 0
Std Step Tol= 0.01
Critical Tol= 0.01
Num of Std Step Trials= 20
Max Error Tol= 0.3
Flow Tol Ratio= 0.001
Split Flow NTrial= 30
Split Flow Tol= 0.02
Split Flow Ratio= 0.02
Log Output Level= 0
Friction Slope Method= 1
Unsteady Friction Slope Method= 2
Unsteady Bridges Friction Slope Method= 1
Parabolic Critical Depth
Global Vel Dist=  1 , 1 , 1
Global Log Level= 0
CheckData=True
Encroach Param= -1, 0, 0, 0
BEGIN DESCRIPTION:
Multiple Run
END DESCRIPTION:

--- Walnut12.f01 (steady flow) ---

Flow Title=Multiple
Number of Profiles=7
Profile Names=10-year,25-year,50-year,1pct_min,100-year,1pct_plu,500-year
River Rch & RM= Walnut12,Reach-1,8436
     688     950    1171     719    1434    2861    2151
River Rch & RM= Walnut12,Reach-1,7085
     902    1264    1572     973    1940    3872    2961
River Rch & RM= Walnut12,Reach-1,4084
    1071    1511    1888    1172    2338    4665    3593
Boundary for River Rch & Prof#=Walnut12,Reach-1,1
Up Type=0
Dn Type=3
Dn Slope=0.005
Boundary for River Rch & Prof#=Walnut12,Reach-1,2
Up Type=0
Dn Type=3
Dn Slope=0.005
Boundary for River Rch & Prof#=Walnut12,Reach-1,3
Up Type=0
Dn Type=3
Dn Slope=0.005
Boundary for River Rch & Prof#=Walnut12,Reach-1,4
Up Type=0
Dn Type=3
Dn Slope=0.005
Boundary for River Rch & Prof#=Walnut12,Reach-1,5
Up Type=0
Dn Type=3
Dn Slope=0.005
Boundary for River Rch & Prof#=Walnut12,Reach-1,6
Up Type=0
Dn Type=3
Dn Slope=0.005
Boundary for River Rch & Prof#=Walnut12,Reach-1,7
Up Type=0
Dn Type=3
Dn Slope=0.005

--- Walnut12.g01 (geometry) ---

Geom Title=Existing Conditions

River Reach=Walnut12,Reach-1
Reach XY= 30
      2768126.00      6750411.00      2767878.31      6750655.18
      2767420.02      6750858.83      2767269.38      6750820.41
      2767139.51      6750897.32      2767124.82      6751007.84
      2767008.92      6750977.15      2766918.14      6751217.17
      2766386.48      6751751.20      2766282.07      6752002.89
      2766077.65      6752014.17      2765373.70      6752366.83
      2765082.32      6752652.93      2764881.11      6752716.11
      2764774.37      6752907.91      2764522.59      6752768.77
      2764084.29      6753014.16      2763959.36      6753327.71
      2763624.44      6753557.24      2763465.82      6753571.32
      2763418.05      6753758.00      2763031.86      6753813.07
      2762673.69      6753966.82      2762479.67      6754253.31
      2762336.48      6754211.95      2762091.20      6754311.37
      2761831.86      6754308.93      2761710.64      6754210.90
      2761579.33      6754303.73      2761526.00      6754261.00

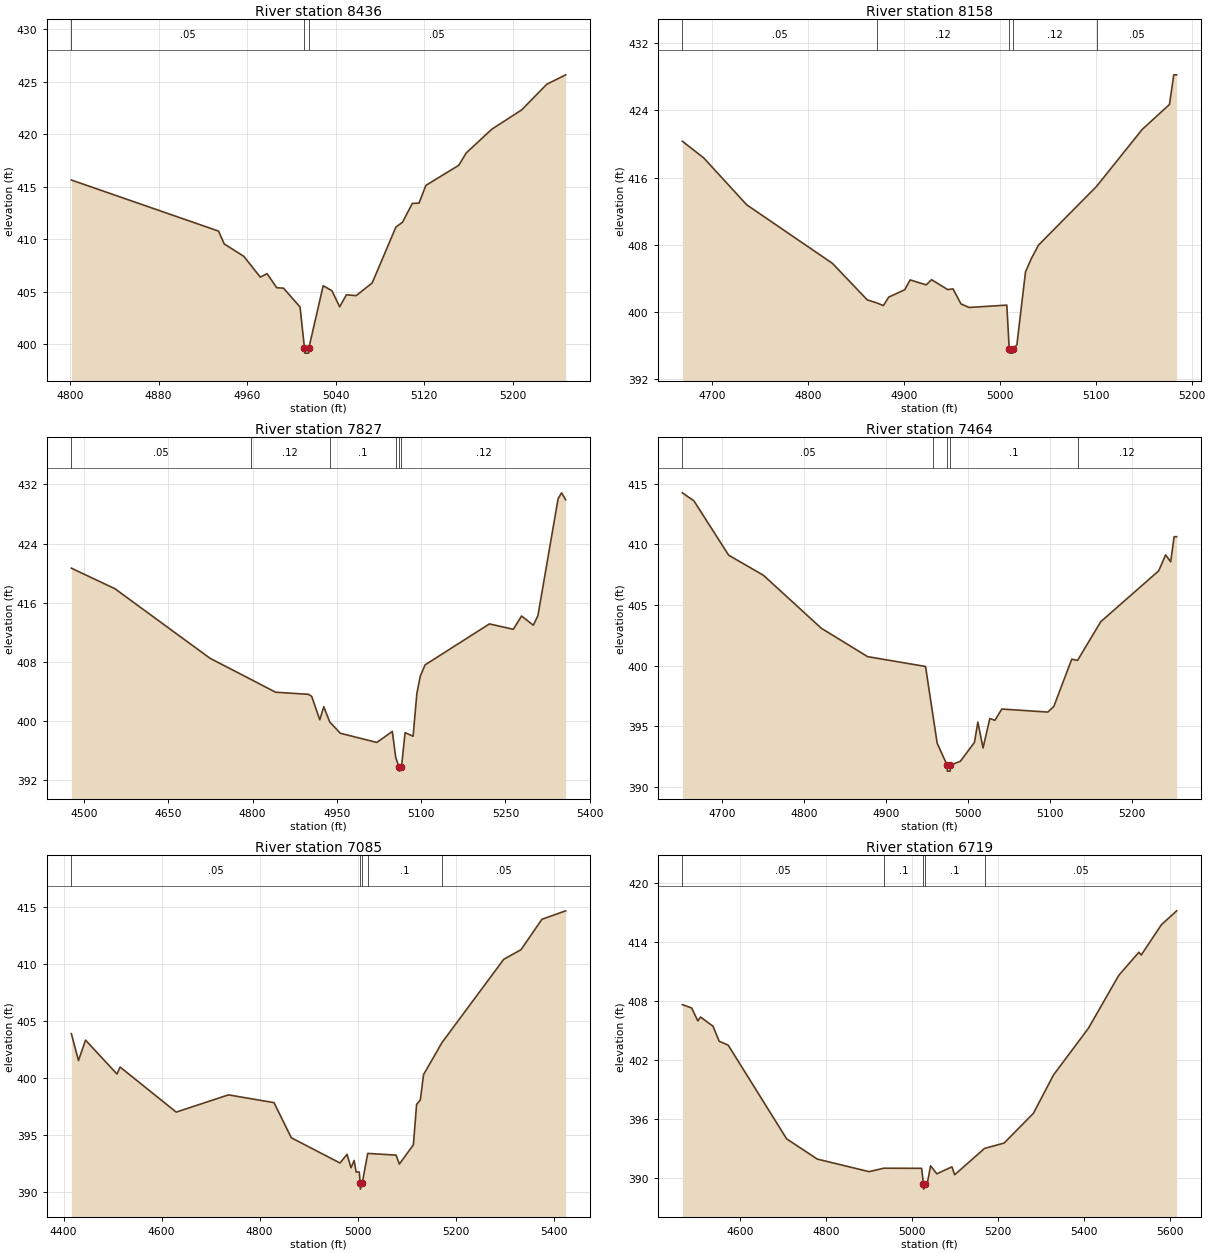
Type RM Length L Ch R = 1,8436,278,278,278
BEGIN DESCRIPTION:
Walnut12 18.0
END DESCRIPTION:
XS GIS Cut Line= 3
      2767584.67      6750547.46      2767623.82      6750684.48
      2767796.10      6750935.07
#Sta/Elev= 30
  4801.2  415.63  4934.2  410.77  4939.3  409.55  4957.0  408.37  4971.9  406.39
  4978.0  406.72  4986.8  405.38  4992.9  405.34  5007.8  403.55  5011.8  399.66
  5012.1  399.16  5015.6  399.16  5015.8  399.66  5028.7  405.57  5036.6  405.10
  5043.6  403.57  5049.7  404.71  5058.5  404.63  5073.0  405.84  5094.4  411.15
  5100.4  411.62  5109.3  413.41  5115.3  413.43  5121.5  415.12  5151.2  417.03
  5157.9  418.20  5181.0  420.46  5208.0  422.30  5230.7  424.74  5247.8  425.64
#Mann=3,-1,0
  4801.2    0.05       0  5011.8    0.05       0  5015.8    0.05       0
Bank Sta=5011.8,5015.8
Exp/Cntr=0.3,0.1

Type RM Length L Ch R = 1,8158,331,331,331
BEGIN DESCRIPTION:
Walnut12 17.0
END DESCRIPTION:
XS GIS Cut Line= 3
      2767275.98      6750560.96      2767426.00      6750861.00
      2767525.98      6751010.97
#Sta/Elev= 30
  4668.6  420.32  4691.0  418.32  4735.7  412.75  4825.2  405.77  4861.5  401.42
  4871.3  401.07  4878.3  400.74  4883.9  401.75  4900.6  402.63  4906.2  403.80
  4923.0  403.21  4928.6  403.83  4945.4  402.65  4951.0  402.73  4959.3  400.94
  4967.7  400.52  5007.1  400.80  5009.6  395.58  5009.8  395.08  5013.3  395.08
  5013.6  395.58  5017.6  396.07  5026.6  404.76  5032.6  406.32  5040.1  407.94
  5100.7  414.94  5148.3  421.72  5176.8  424.70  5181.3  428.23  5184.3  428.23
#Mann=5,-1,0
  4668.6    0.05       0  4871.3    0.12       0  5009.6    0.07       0
  5013.6    0.12       0  5100.7    0.05       0
Bank Sta=5009.6,5013.6
Exp/Cntr=0.3,0.1

Type RM Length L Ch R = 1,7827,363,363,363
BEGIN DESCRIPTION:
Walnut12 16.0
END DESCRIPTION:
XS GIS Cut Line= 3
      2766691.93      6750627.71      2767071.73      6750854.80
      2767425.99      6751110.99
#Sta/Elev= 30
  4477.5  420.67  4555.0  417.89  4724.3  408.48  4796.4  405.65  4841.0  403.89
  4899.4  403.61  4905.2  403.33  4919.6  400.17  4926.7  401.93  4937.2  399.88
  4956.2  398.34  5021.1  397.10  5048.7  398.59  5054.8  395.04  5060.9  393.72
  5061.1  393.22  5064.9  393.72  5071.4  398.43  5085.7  397.94  5092.3  403.68
  5098.5  406.08  5107.0  407.59  5221.5  413.13  5264.0  412.40  5278.7  414.20
  5299.6  412.96  5307.8  414.24  5343.7  430.05  5349.9  430.86  5357.2  429.92
#Mann=6,-1,0
  4477.5    0.05       0  4796.4    0.12       0  4937.2     0.1       0
  5054.8    0.12       0  5060.9    0.07       0  5064.9    0.12       0
Bank Sta=5060.9,5064.9
Exp/Cntr=0.3,0.1

Type RM Length L Ch R = 1,7464,379,379,379
BEGIN DESCRIPTION:
Walnut12 15.0
END DESCRIPTION:
XS GIS Cut Line= 3
      2766726.03      6750811.03      2766976.00      6751061.00
      2767175.99      6751210.99
#Sta/Elev= 30
  4651.6  414.26  4665.7  413.60  4708.1  409.12  4750.6  407.46  4821.3  403.09
  4877.8  400.75  4948.5  399.94  4957.6  395.88  4962.7  393.61  4974.8  391.81
  4975.1  391.31  4978.6  391.31  4978.8  391.81  4991.0  392.12  5008.2  393.68
  5012.4  395.35  5018.7  393.22  5027.0  395.65  5033.2  395.50  5041.6  396.43
  5097.8  396.18  5105.1  396.64  5127.0  400.54  5134.1  400.44  5162.4  403.63
  5233.2  407.83  5241.6  409.14  5247.8  408.57  5252.0  410.64  5255.1  410.64
#Mann=5,-1,0
  4651.6    0.05       0  4957.6     0.1       0  4974.8    0.07       0
  4978.8     0.1       0  5134.1    0.12       0
Bank Sta=4974.8,4978.8
Exp/Cntr=0.3,0.1

Type RM Length L Ch R = 1,7085,366,366,366
BEGIN DESCRIPTION:
Walnut12 14.0
END DESCRIPTION:
XS GIS Cut Line= 3
      2766318.39      6750998.03      2766776.00      6751361.00
      2767098.00      6751637.33
#Sta/Elev= 30
  4415.9  403.86  4430.4  401.51  4444.8  403.30  4508.9  400.33  4515.3  400.94
  4629.8  396.99  4736.4  398.50  4829.3  397.82  4864.6  394.74  4963.9  392.53
  4978.3  393.29  4986.4  392.11  4992.8  392.75  4996.8  391.74  5003.3  391.74
  5005.1  390.74  5005.4  390.24  5009.1  390.74  5020.5  393.37  5078.4  393.22
  5085.0  392.44  5113.6  394.12  5120.2  397.67  5127.8  398.05  5134.4  400.28
  5172.1  403.09  5297.9  410.38  5333.1  411.22  5375.9  413.89  5424.3  414.63
#Mann=5,-1,0
  4415.9    0.05       0  5005.1    0.04       0  5009.1    0.05       0
  5020.5     0.1       0  5172.1    0.05       0
Bank Sta=5005.1,5009.1
Exp/Cntr=0.3,0.1

Type RM Length L Ch R = 1,6719,385,385,385
BEGIN DESCRIPTION:
Walnut12 13.0
END DESCRIPTION:
XS GIS Cut Line= 3
      2766103.54      6751283.21      2766694.49      6751737.78
      2767066.42      6751898.95
#Sta/Elev= 30
  4464.8  407.62  4486.3  407.29  4500.8  405.97  4507.1  406.36  4536.1  405.43
  4550.6  403.89  4571.5  403.50  4707.6  393.95  4779.0  391.89  4899.5  390.61
  4933.8  390.96  5021.9  390.95  5026.2  389.33  5026.4  388.83  5030.2  389.33
  5035.6  389.53  5042.7  391.21  5057.2  390.39  5092.5  391.10  5098.8  390.29
  5168.5  392.98  5213.9  393.52  5282.1  396.55  5329.0  400.46  5410.4  405.23
  5480.8  410.60  5527.7  412.96  5533.2  412.68  5580.1  415.76  5615.7  417.18
#Mann=5,-1,0
  4464.8    0.05       0  4933.8     0.1       0  5026.2    0.07       0
  5030.2     0.1       0  5168.5    0.05       0
Bank Sta=5026.2,5030.2
Exp/Cntr=0.3,0.1

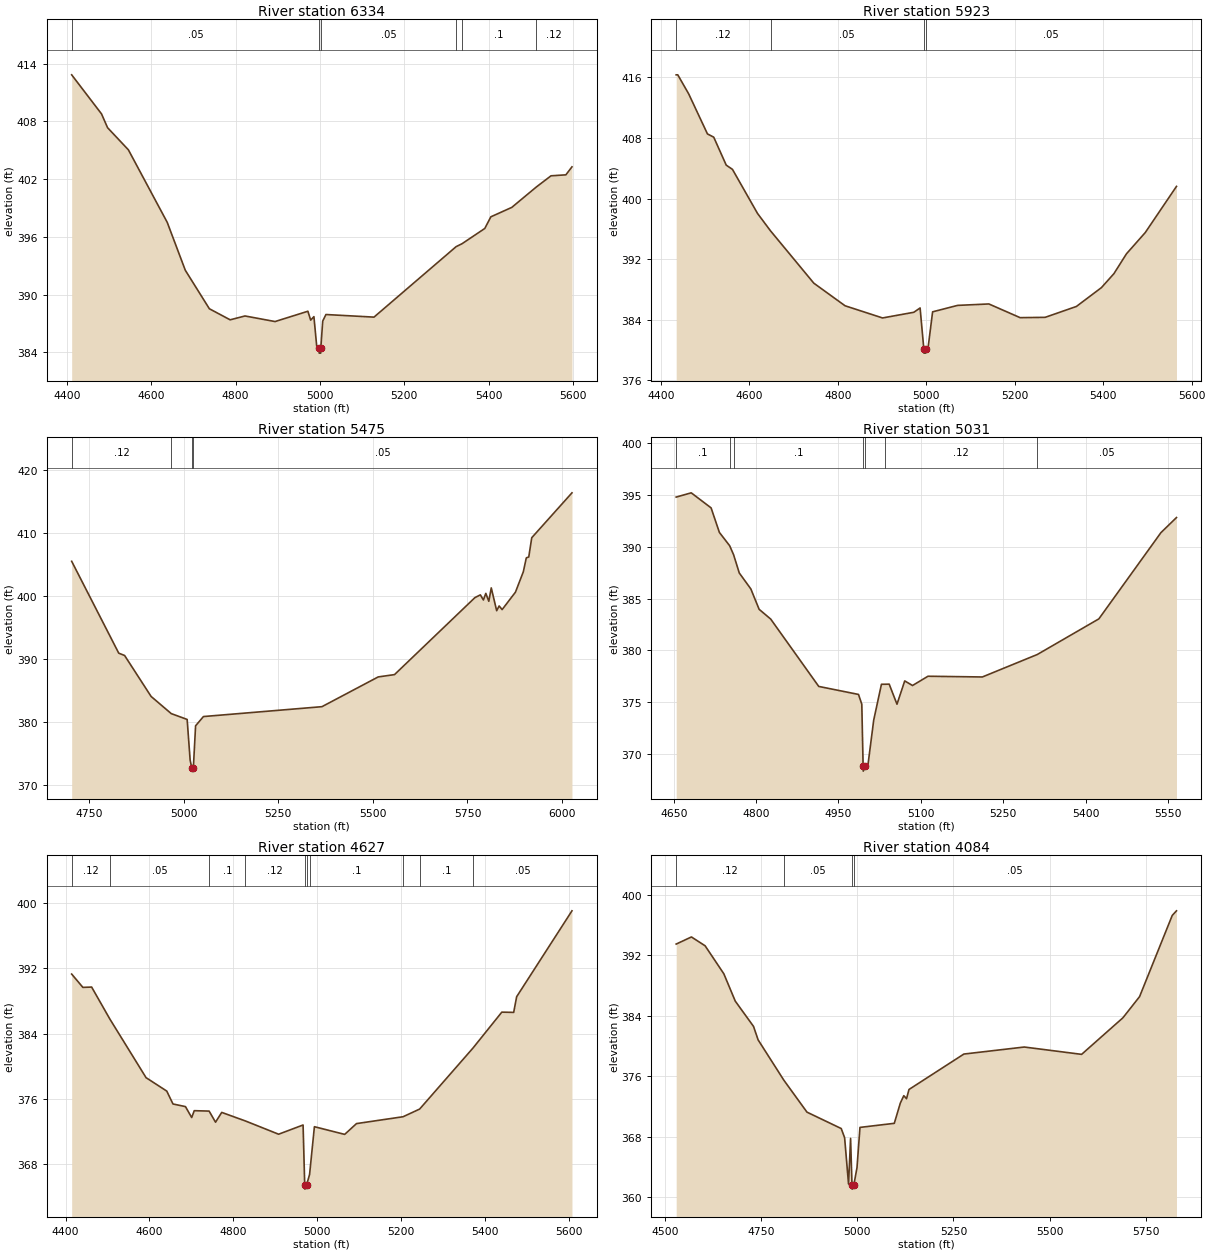
Type RM Length L Ch R = 1,6334,411,411,411
BEGIN DESCRIPTION:
Walnut12 12.0
END DESCRIPTION:
XS GIS Cut Line= 3
      2765975.45      6751481.60      2766372.15      6751944.41
      2766730.17      6752397.08
#Sta/Elev= 30
  4411.1  412.83  4481.9  408.77  4496.2  407.34  4545.6  405.04  4637.8  397.50
  4680.6  392.53  4737.7  388.53  4787.0  387.38  4822.2  387.78  4893.5  387.20
  4971.4  388.27  4978.0  387.35  4985.7  387.71  4992.3  384.65  4998.0  384.42
  4998.2  383.92  5001.7  383.92  5002.0  384.42  5006.6  387.25  5014.2  387.93
  5128.2  387.66  5323.0  394.98  5337.2  395.29  5391.0  396.87  5405.4  398.08
  5455.1  399.06  5513.3  401.18  5548.1  402.34  5583.3  402.44  5597.8  403.27
#Mann=6,-1,0
  4411.1    0.05       0  4998.0    0.04       0  5002.0    0.05       0
  5323.0    0.12       0  5337.2     0.1       0  5513.3    0.12       0
Bank Sta=4998,5002
Exp/Cntr=0.3,0.1

Type RM Length L Ch R = 1,5923,448,448,448
BEGIN DESCRIPTION:
Walnut12 11.0
END DESCRIPTION:
XS GIS Cut Line= 3
      2765625.98      6751660.98      2766026.00      6752061.00
      2766426.00      6752461.00
#Sta/Elev= 30
  4434.3  416.35  4437.9  416.35  4462.6  413.83  4505.0  408.54  4519.2  408.11
  4547.5  404.41  4561.6  403.85  4618.2  398.03  4647.7  395.72  4745.5  388.81
  4816.2  385.82  4901.0  384.21  4971.7  384.96  4985.9  385.53  4994.4  380.06
  4994.7  379.56  4998.3  379.56  4998.6  380.06  5003.5  380.06  5014.2  385.02
  5070.7  385.87  5141.4  386.06  5212.1  384.25  5268.7  384.29  5339.4  385.73
  5396.0  388.22  5424.3  390.07  5452.6  392.69  5495.0  395.49  5565.7  401.60
#Mann=4,-1,0
  4434.3    0.12       0  4647.7    0.05       0  4994.4    0.04       0
  4998.6    0.05       0
Bank Sta=4994.4,4998.6
Exp/Cntr=0.3,0.1

Type RM Length L Ch R = 1,5475,444,444,444
BEGIN DESCRIPTION:
Walnut12 10.0
END DESCRIPTION:
XS GIS Cut Line= 3
      2765476.01      6751961.01      2765626.00      6752211.00
      2766275.99      6753010.99
#Sta/Elev= 30
  4703.9  405.53  4828.3  390.92  4843.8  390.55  4913.8  384.04  4967.0  381.31
  5009.1  380.38  5017.0  373.91  5021.3  372.66  5021.6  372.16  5025.5  372.66
  5031.4  379.37  5052.2  380.84  5365.4  382.41  5514.0  387.14  5557.2  387.51
  5769.8  399.76  5784.1  400.19  5792.1  399.38  5798.5  400.43  5806.4  399.17
  5812.9  401.30  5827.2  397.67  5833.7  398.43  5841.6  397.85  5876.8  400.62
  5897.6  403.86  5905.5  406.08  5912.0  406.22  5919.9  409.28  6026.2  416.42
#Mann=4,-1,0
  4703.9    0.12       0  4967.0    0.05       0  5021.3    0.04       0
  5025.5    0.05       0
Bank Sta=5021.3,5025.5
Exp/Cntr=0.3,0.1

Type RM Length L Ch R = 1,5031,404,404,404
BEGIN DESCRIPTION:
Walnut12 9.0
END DESCRIPTION:
XS GIS Cut Line= 3
      2765086.92      6752171.70      2765276.00      6752461.00
      2765676.00      6752861.00
#Sta/Elev= 30
  4654.4  394.76  4681.8  395.17  4718.0  393.72  4733.1  391.36  4751.8  390.08
  4759.0  389.21  4769.3  387.46  4790.4  385.92  4805.5  383.96  4826.6  383.02
  4914.1  376.54  4986.5  375.77  4992.5  374.83  4994.9  368.89  4995.2  368.39
  4999.2  368.89  5003.5  368.89  5014.2  373.30  5028.3  376.75  5034.9  376.75
  5042.4  376.76  5056.6  374.83  5070.7  377.07  5084.9  376.63  5113.1  377.52
  5212.1  377.45  5312.1  379.61  5424.3  383.04  5537.4  391.34  5565.7  392.79
#Mann=7,-1,0
  4654.4     0.1       0  4751.8    0.12       0  4759.0     0.1       0
  4994.9    0.07       0  4999.2     0.1       0  5034.9    0.12       0
  5312.1    0.05       0
Bank Sta=4994.9,4999.2
Exp/Cntr=0.3,0.1

Type RM Length L Ch R = 1,4627,543,543,543
BEGIN DESCRIPTION:
Walnut12 8.0
END DESCRIPTION:
XS GIS Cut Line= 3
      2764500.14      6752370.09      2764996.01      6752713.07
      2765417.36      6753126.16
#Sta/Elev= 30
  4414.6  391.28  4441.3  389.65  4462.2  389.69  4505.6  385.78  4592.0  378.60
  4641.3  376.96  4656.2  375.38  4685.9  375.06  4700.8  373.72  4706.9  374.56
  4742.4  374.51  4757.6  373.15  4772.4  374.35  4829.0  373.30  4908.1  371.68
  4966.4  372.81  4970.3  365.46  4970.7  364.96  4974.7  365.46  4981.9  366.75
  4993.4  372.60  5065.6  371.66  5093.8  372.98  5204.9  373.82  5244.4  374.76
  5371.3  382.21  5440.3  386.62  5468.6  386.59  5475.7  388.51  5607.6  399.02
#Mann=10,-1,0
  4414.6    0.12       0  4505.6    0.05       0  4742.4     0.1       0
  4829.0    0.12       0  4970.3    0.07       0  4974.7    0.12       0
  4981.9     0.1       0  5204.9    0.12       0  5244.4     0.1       0
  5371.3    0.05       0
Bank Sta=4970.3,4974.7
Exp/Cntr=0.3,0.1

Type RM Length L Ch R = 1,4084,417,417,417
BEGIN DESCRIPTION:
Walnut12 7.0
END DESCRIPTION:
XS GIS Cut Line= 3
      2764433.99      6752374.21      2764648.87      6752915.56
      2765210.88      6753361.86
#Sta/Elev= 30
  4529.6  393.49  4569.2  394.43  4604.8  393.26  4653.5  389.55  4683.1  385.94
  4730.6  382.59  4742.5  380.81  4809.4  375.47  4869.5  371.24  4958.5  369.07
  4967.3  367.86  4977.5  361.72  4982.8  367.76  4986.5  361.55  4986.9  361.05
  4991.1  361.55  4999.5  363.91  5007.2  369.22  5096.4  369.76  5112.0  372.43
  5121.1  373.42  5128.2  373.02  5134.6  374.24  5277.2  378.93  5434.2  379.86
  5583.2  378.89  5690.5  383.73  5733.8  386.53  5818.7  397.28  5829.7  397.89
#Mann=4,-1,0
  4529.6    0.12       0  4809.4    0.05       0  4986.5    0.04       0
  4991.1    0.05       0
Bank Sta=4986.5,4991.1
Exp/Cntr=0.3,0.1

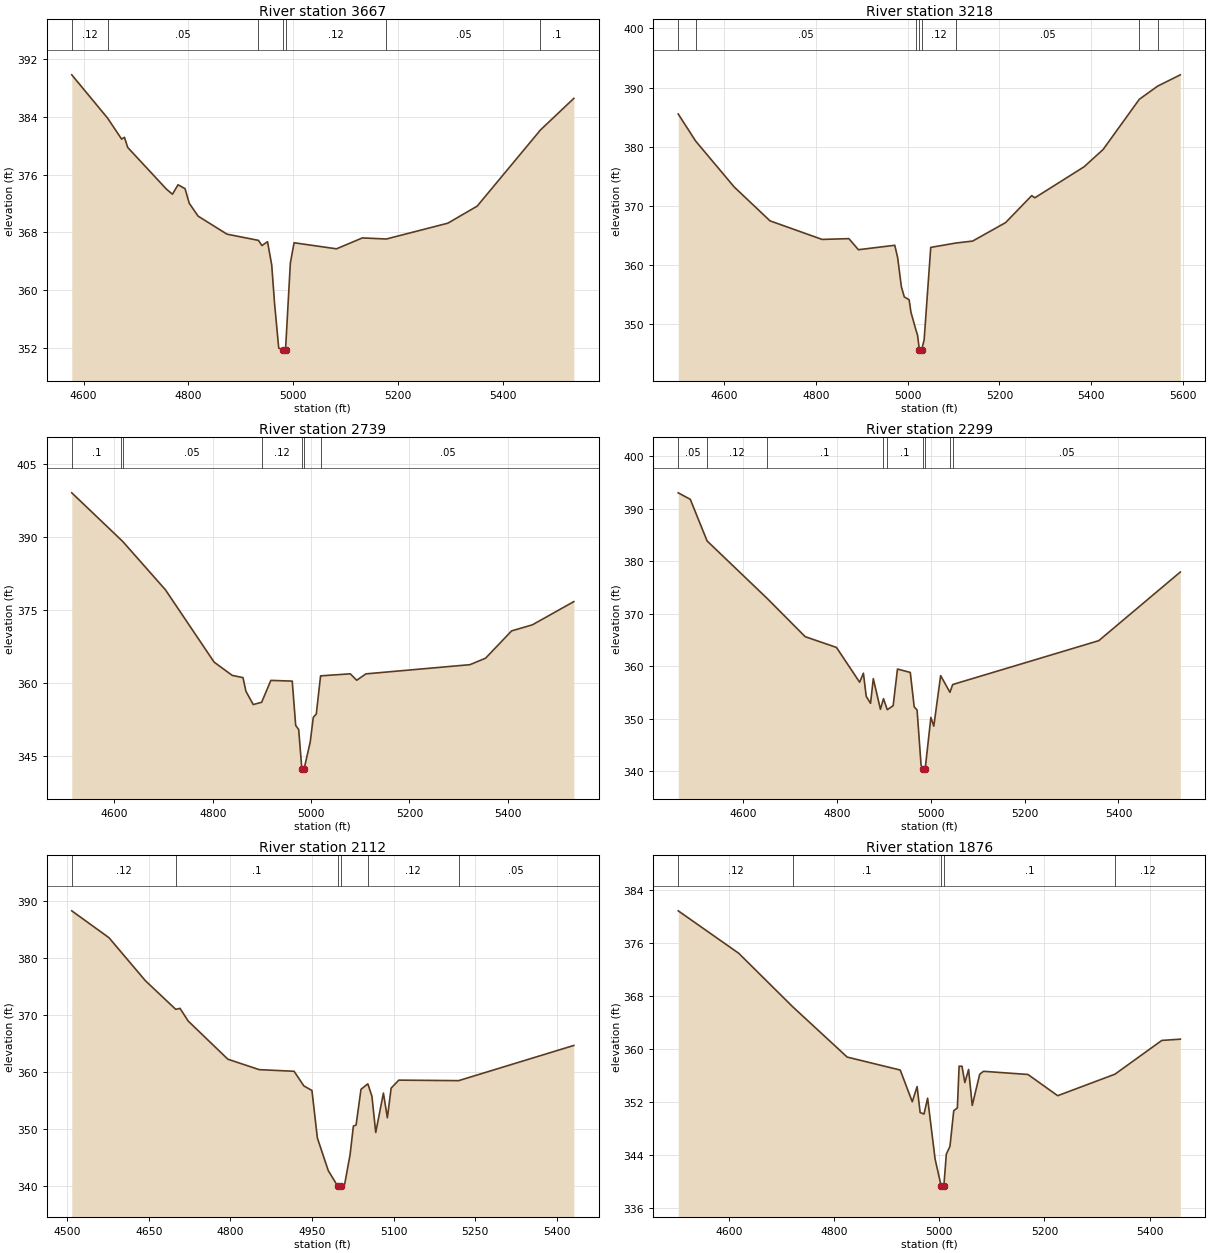
Type RM Length L Ch R = 1,3667,449,449,449
BEGIN DESCRIPTION:
Walnut12 6.0
END DESCRIPTION:
XS GIS Cut Line= 3
      2764126.00      6752560.99      2764276.00      6752961.00
      2764625.99      6753360.99
#Sta/Elev= 30
  4577.3  389.82  4645.7  383.83  4672.5  380.92  4677.9  381.17  4684.1  379.77
  4758.0  374.00  4769.6  373.29  4780.2  374.60  4793.6  374.06  4801.6  372.04
  4818.5  370.26  4873.7  367.76  4933.8  366.90  4940.4  366.18  4951.1  366.72
  4959.1  363.50  4964.5  358.20  4972.5  351.98  4980.8  351.79  4981.3  351.29
  4985.5  351.79  4994.7  363.77  5001.8  366.57  5082.8  365.73  5132.2  367.24
  5177.9  367.09  5295.4  369.28  5351.4  371.64  5472.2  382.18  5536.0  386.56
#Mann=7,-1,0
  4577.3    0.12       0  4645.7    0.05       0  4933.8    0.12       0
  4980.8    0.07       0  4985.5    0.12       0  5177.9    0.05       0
  5472.2     0.1       0
Bank Sta=4980.8,4985.5
Exp/Cntr=0.3,0.1

Type RM Length L Ch R = 1,3218,479,479,479
BEGIN DESCRIPTION:
Walnut12 5.0
END DESCRIPTION:
XS GIS Cut Line= 3
      2763626.01      6752911.01      2764026.00      6753211.00
      2764487.71      6753585.04
#Sta/Elev= 30
  4499.9  385.53  4537.9  380.95  4621.8  373.20  4699.9  367.47  4813.4  364.33
  4871.8  364.46  4892.6  362.59  4971.8  363.34  4978.0  361.28  4986.3  356.29
  4992.6  354.61  5003.1  354.13  5007.1  352.02  5017.8  349.06  5021.5  348.12
  5025.5  345.61  5026.0  345.11  5030.2  345.61  5035.8  347.35  5050.2  362.98
  5105.0  363.72  5141.5  364.05  5213.3  367.17  5270.2  371.73  5277.2  371.37
  5384.3  376.60  5425.9  379.53  5504.8  388.02  5544.5  390.23  5594.1  392.15
#Mann=8,-1,0
  4499.9    0.12       0  4537.9    0.05       0  5017.8    0.12       0
  5025.5    0.04       0  5030.2    0.12       0  5105.0    0.05       0
  5504.8     0.1       0  5544.5    0.05       0
Bank Sta=5025.5,5030.2
Exp/Cntr=0.3,0.1

Type RM Length L Ch R = 1,2739,440,440,440
BEGIN DESCRIPTION:
Walnut12 4.0
END DESCRIPTION:
XS GIS Cut Line= 3
      2763409.10      6753113.91      2763719.05      6753556.11
      2763876.07      6754010.64
#Sta/Elev= 30
  4513.3  399.06  4614.3  389.32  4616.7  389.09  4703.6  379.15  4802.8  364.26
  4839.5  361.54  4861.4  361.08  4867.5  358.26  4882.3  355.54  4899.4  356.01
  4918.1  360.51  4961.6  360.36  4968.6  351.26  4974.7  350.41  4981.1  342.36
  4981.6  341.86  4985.8  342.36  4998.2  347.87  5004.4  352.91  5010.5  353.60
  5019.2  361.42  5020.4  361.45  5079.6  361.86  5092.7  360.54  5111.4  361.85
  5323.0  363.74  5354.7  365.07  5407.6  370.68  5449.9  371.93  5534.2  376.70
#Mann=7,-1,0
  4513.3     0.1       0  4614.3    0.12       0  4616.7    0.05       0
  4899.4    0.12       0  4981.1    0.07       0  4985.8    0.12       0
  5020.4    0.05       0
Bank Sta=4981.1,4985.8
Exp/Cntr=0.3,0.1

Type RM Length L Ch R = 1,2299,187,187,187
BEGIN DESCRIPTION:
Walnut12 3.0
END DESCRIPTION:
XS GIS Cut Line= 3
      2763115.70      6753316.43      2763380.18      6753725.54
      2763851.13      6754068.43
#Sta/Elev= 30
  4462.0  393.07  4487.7  391.83  4523.5  383.90  4651.1  372.98  4732.5  365.66
  4799.1  363.61  4848.5  356.98  4856.5  358.70  4862.5  354.30  4871.7  352.96
  4877.6  357.66  4892.8  351.82  4899.3  353.85  4907.4  351.74  4919.9  352.51
  4929.1  359.49  4956.4  358.85  4964.7  352.30  4970.9  351.68  4979.4  341.16
  4983.0  340.54  4983.7  340.04  4988.2  340.54  5000.3  350.27  5006.5  348.61
  5021.1  358.24  5040.9  355.06  5046.7  356.54  5358.0  364.90  5531.7  377.98
#Mann=9,-1,0
  4462.0    0.05       0  4523.5    0.12       0  4651.1     0.1       0
  4899.3    0.12       0  4907.4     0.1       0  4983.0    0.07       0
  4988.2     0.1       0  5040.9    0.12       0  5046.7    0.05       0
Bank Sta=4983,4988.2
Exp/Cntr=0.3,0.1

Type RM Length L Ch R = 1,2112,236,236,236
BEGIN DESCRIPTION:
Walnut12 2.5
END DESCRIPTION:
XS GIS Cut Line= 4
      2763025.43      6753386.46      2763254.53      6753746.17
      2763250.25      6753857.50      2763515.72      6754135.81
#Sta/Elev= 30
  4508.5  388.22  4576.9  383.51  4643.8  375.97  4699.6  370.95  4707.3  371.13
  4722.5  368.90  4795.3  362.22  4852.9  360.39  4917.0  360.10  4934.9  357.54
  4949.8  356.73  4959.8  348.40  4979.8  342.70  4997.3  339.95  4998.0  339.45
  5002.5  339.95  5009.9  340.32  5019.9  345.50  5025.9  350.49  5030.9  350.68
  5039.9  356.94  5052.5  357.90  5060.0  355.73  5067.0  349.38  5081.1  356.28
  5088.4  351.96  5095.3  357.15  5109.4  358.55  5219.3  358.46  5431.0  364.63
#Mann=6,-1,0
  4508.5    0.12       0  4699.6     0.1       0  4997.3    0.07       0
  5002.5     0.1       0  5052.5    0.12       0  5219.3    0.05       0
Bank Sta=4997.3,5002.5
Exp/Cntr=0.3,0.1

Type RM Length L Ch R = 1,1876,395,395,395
BEGIN DESCRIPTION:
Walnut12 2.0
END DESCRIPTION:
XS GIS Cut Line= 4
      2762876.01      6753349.49      2762987.59      6753787.53
      2763045.47      6753848.22      2763335.89      6754150.81
#Sta/Elev= 30
  4503.3  380.87  4618.4  374.45  4721.4  366.34  4824.8  358.75  4925.7  356.79
  4948.6  351.99  4957.8  354.29  4963.6  350.36  4970.9  350.14  4977.8  352.53
  4992.0  343.35  5003.5  339.28  5004.2  338.78  5008.7  339.28  5013.4  344.08
  5020.3  345.24  5027.5  350.64  5034.4  351.06  5037.7  357.37  5043.2  357.37
  5048.6  354.90  5055.8  356.88  5062.7  351.44  5076.9  356.15  5084.1  356.60
  5168.7  356.12  5225.3  352.91  5334.2  356.16  5423.4  361.27  5458.6  361.46
#Mann=5,-1,0
  4503.3    0.12       0  4721.4     0.1       0  5003.5    0.07       0
  5008.7     0.1       0  5334.2    0.12       0
Bank Sta=5003.5,5008.7
Exp/Cntr=0.3,0.1

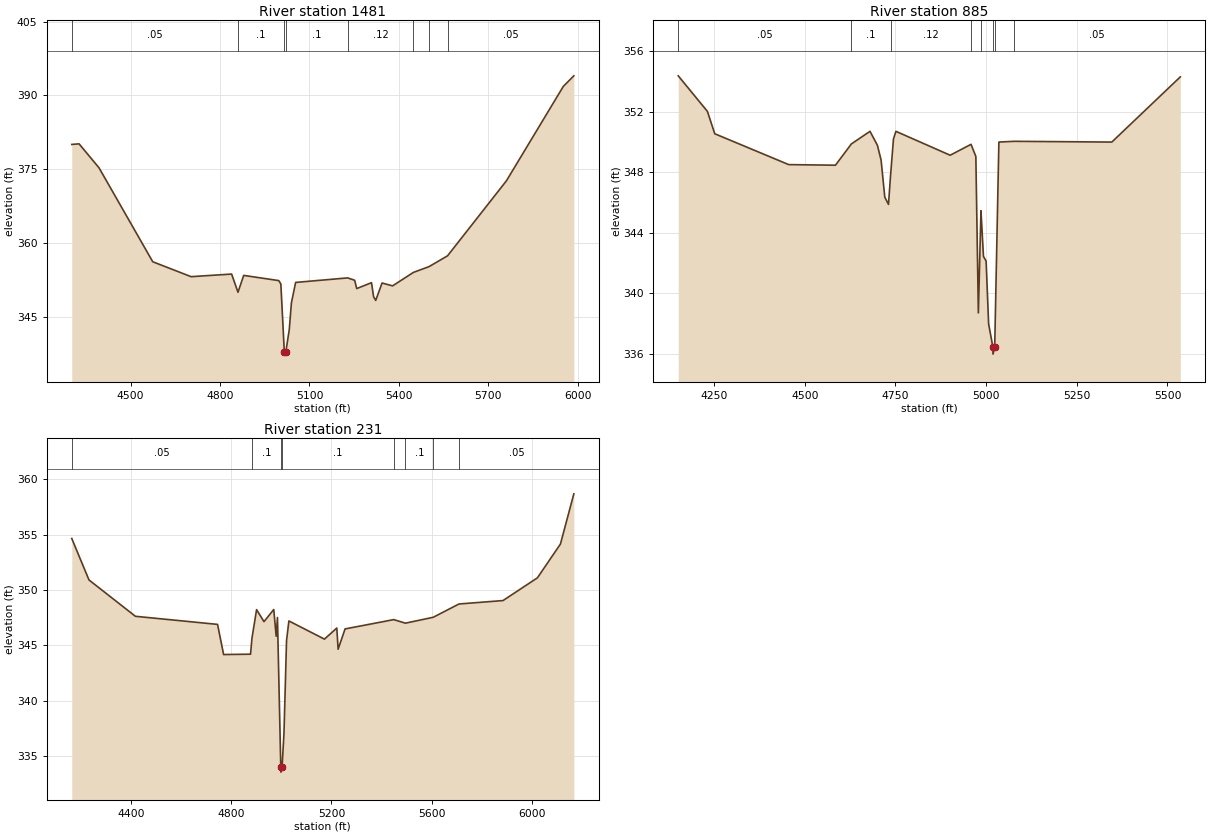
Type RM Length L Ch R = 1,1481,596,596,596
BEGIN DESCRIPTION:
Walnut12 1.0
END DESCRIPTION:
XS GIS Cut Line= 3
      2762537.13      6753291.59      2762640.45      6753932.17
      2763375.97      6754660.97
#Sta/Elev= 30
  4302.7  380.05  4327.2  380.17  4394.1  375.30  4574.4  356.19  4703.0  353.16
  4839.0  353.69  4860.3  349.99  4879.5  353.42  4997.1  352.36  5004.1  351.67
  5015.7  337.91  5016.4  337.41  5020.9  337.91  5032.4  342.42  5039.5  347.83
  5053.7  351.99  5228.3  352.91  5251.7  352.43  5258.7  350.74  5308.2  351.94
  5315.3  349.07  5322.4  348.34  5343.6  351.87  5378.9  351.29  5448.9  354.03
  5501.5  355.21  5563.3  357.40  5760.8  372.65  5951.7  391.85  5987.0  394.00
#Mann=8,-1,0
  4302.7    0.05       0  4860.3     0.1       0  5015.7    0.07       0
  5020.9     0.1       0  5228.3    0.12       0  5448.9     0.1       0
  5501.5    0.12       0  5563.3    0.05       0
Bank Sta=5015.7,5020.9
Exp/Cntr=0.3,0.1

Type RM Length L Ch R = 1,885,654,654,654
BEGIN DESCRIPTION:
Walnut12 0.5
END DESCRIPTION:
XS GIS Cut Line= 3
      2762027.80      6753472.13      2762156.94      6754134.67
      2762648.46      6754645.63
#Sta/Elev= 30
  4151.4  354.37  4231.8  352.02  4252.1  350.54  4455.9  348.50  4584.8  348.46
  4628.8  349.87  4680.0  350.70  4700.4  349.78  4710.6  348.80  4720.8  346.35
  4731.0  345.87  4736.8  347.82  4744.7  350.19  4751.4  350.70  4901.0  349.12
  4958.5  349.84  4971.8  349.04  4978.7  338.70  4985.9  345.45  4987.2  344.88
  4992.8  342.43  5000.1  342.12  5007.0  337.97  5018.5  336.47  5019.2  335.97
  5023.8  336.47  5035.3  349.99  5077.3  350.04  5346.6  349.99  5535.4  354.30
#Mann=8,-1,0
  4151.4    0.05       0  4628.8     0.1       0  4736.8    0.12       0
  4958.5    0.05       0  4987.2    0.12       0  5018.5    0.07       0
  5023.8    0.12       0  5077.3    0.05       0
Bank Sta=5018.5,5023.8
Exp/Cntr=0.3,0.1

Type RM Length L Ch R = 1,231,0,0,0
BEGIN DESCRIPTION:
Walnut12 0.3
END DESCRIPTION:
XS GIS Cut Line= 4
      2761987.14      6753433.55      2761693.82      6754159.36
      2761738.78      6754382.01      2762687.16      6754668.88
#Sta/Elev= 30
  4165.0  354.65  4233.6  350.91  4418.6  347.63  4746.0  346.90  4770.1  344.18
  4877.4  344.21  4883.0  345.64  4901.5  348.23  4931.0  347.15  4969.9  348.24
  4979.6  345.83  4984.7  347.52  4997.9  334.07  4998.6  333.57  5003.2  334.07
  5010.7  337.10  5020.9  345.45  5030.3  347.21  5171.9  345.57  5221.2  346.57
  5226.4  344.66  5254.1  346.49  5448.1  347.33  5494.6  347.01  5605.4  347.54
  5708.0  348.74  5883.6  349.05  6020.6  351.10  6112.4  354.15  6165.8  358.68
#Mann=8,-1,0
  4165.0    0.05       0  4883.0     0.1       0  4997.9    0.07       0
  5003.2     0.1       0  5448.1    0.12       0  5494.6     0.1       0
  5605.4    0.12       0  5708.0    0.05       0
Bank Sta=4997.9,5003.2
Exp/Cntr=0.3,0.1

Chan Stop Cuts=-1