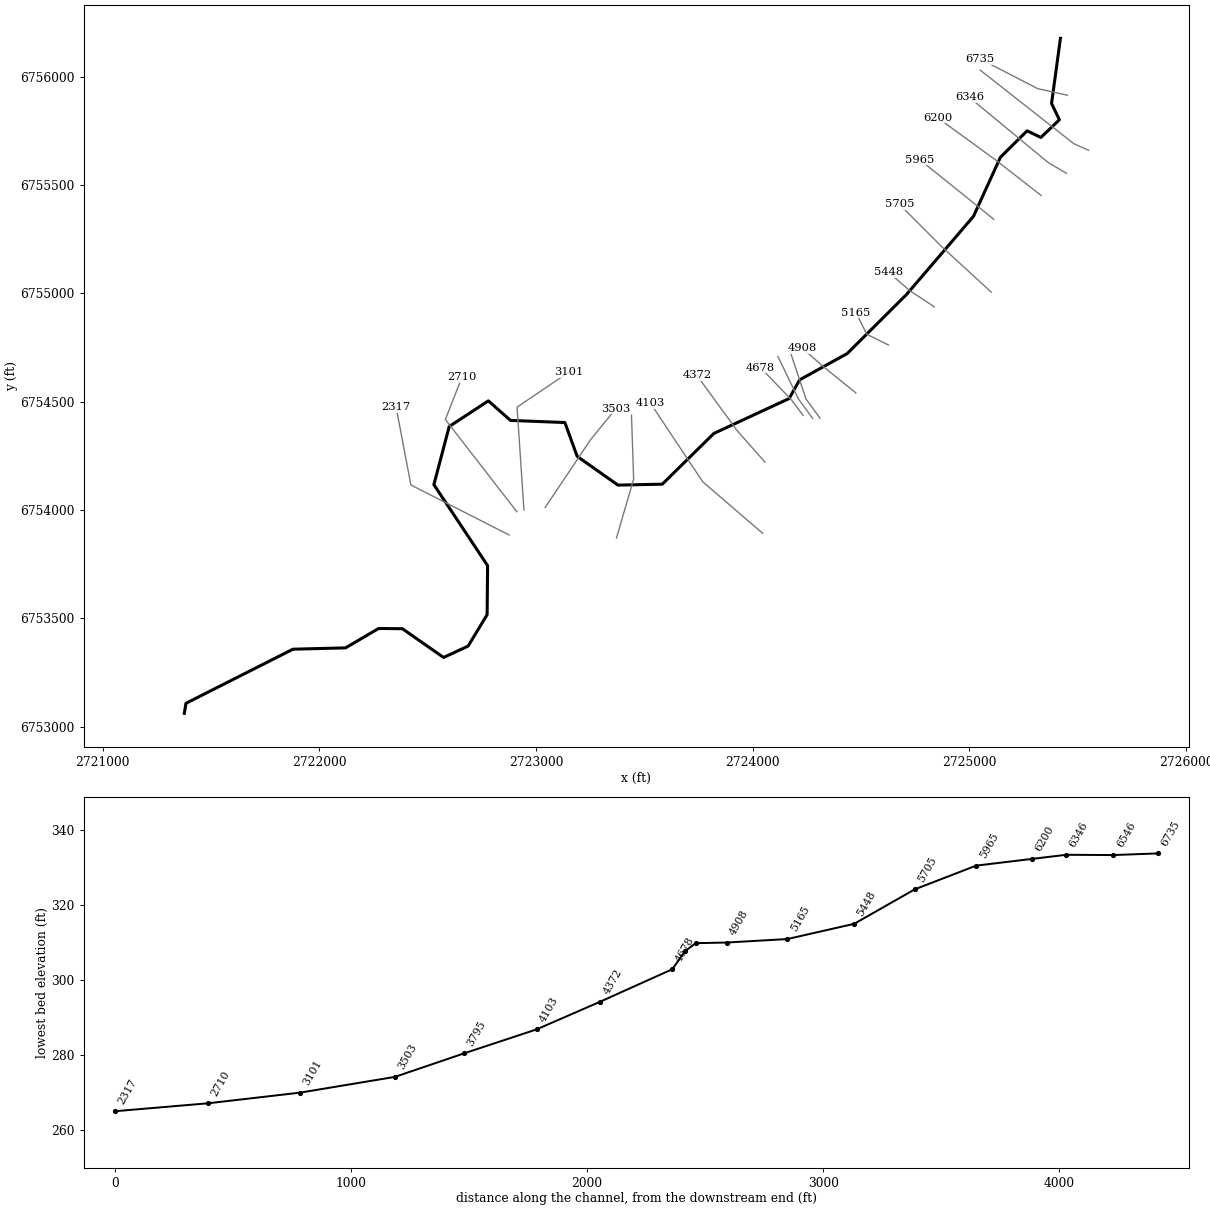
--- Walnut16.prj (project) ---

Proj Title=Walnut16 Base Level Engineering
Current Plan=p01
Default Exp/Contr=0.3,0.1
English Units
Geom File=g01
Flow File=f01
Plan File=p01
Y Axis Title=Elevation
X Axis Title(PF)=Main Channel Distance
X Axis Title(XS)=Station
BEGIN DESCRIPTION:
Walnut16
END DESCRIPTION:
DSS Export Rating Curves= 0
DSS Export Rating Curve Sorted= 0
DSS Export Volume Flow Curves= 0
DXF OffsetX= 0
DXF OffsetY= 0
DXF ScaleX= 1
DXF ScaleY= 10

--- Walnut16.p01 (plan) ---

Plan Title=Multiple Run
Program Version=4.10
Short Identifier=Multiple
Geom File=g01
Flow File=f01
Subcritical Flow
K Sum by GR= 0
Std Step Tol= 0.01
Critical Tol= 0.01
Num of Std Step Trials= 20
Max Error Tol= 0.3
Flow Tol Ratio= 0.001
Split Flow NTrial= 30
Split Flow Tol= 0.02
Split Flow Ratio= 0.02
Log Output Level= 0
Friction Slope Method= 1
Unsteady Friction Slope Method= 2
Unsteady Bridges Friction Slope Method= 1
Parabolic Critical Depth
Global Vel Dist= 1 , 1 , 1
Global Log Level= 0
CheckData=True
Encroach Param=-1 ,0,0, 0
BEGIN DESCRIPTION:
Multiple Run
END DESCRIPTION:
Computation Interval=1HOUR
Output Interval=1HOUR
Run HTab= 0
Run UNet= 0
Run PostProcess= 0
Run WQNet= 0
UNET Theta= 1
UNET Theta Warmup= 1
UNET ZTol= 0.02
UNET ZSATol= 0.05
UNET MxIter= 20
UNET MaxInSteps= 0
UNET DtIC= 0
UNET DtMin= 0
UNET MaxCRTS= 20
UNET WFStab= 2
UNET SFStab= 1
UNET WFX= 1
UNET SFX= 1
UNET DSS MLevel= 4
UNET DZMax Abort= 100
UNET Convert EG Bridges= 0
UNET Use Existing IB Tables=-1
UNET Froude Reduction=False
UNET Froude Limit= 1
UNET Froude Power= 10
UNET Time Slicing=0,0, 5
UNET Junction Losses=0
Instantaneous Interval=1HOUR
Write IC File= 0
Write IC File at Sim End=0
Echo Input=False
Echo Parameters=False
Echo Output=False
Write Detailed= 0
WQ AD Non Conservative
WQ ULTIMATE=-1
WQ Max Comp Step=1HOUR
WQ Output Interval=15MIN
WQ Output Selected Increments= 0
WQ Output face flow=0
WQ Output face velocity=0
WQ Output face area=0
WQ Output face dispersion=0
WQ Output cell volume=0
WQ Output cell surface area=0
WQ Output cell continuity=0
WQ Output cumulative cell continuity=0
WQ Output face conc=0
WQ Output face dconc_dx=0
WQ Output face courant=0
WQ Output face peclet=0
WQ Output face adv mass=0
WQ Output face disp mass=0
WQ Output cell mass=0
WQ Output cell source sink temp=0
WQ Output cell source sink nsm=0
WQ Output MaxMinRange=-1
WQ Daily Max Min Mean=-1
WQ Daily Range=0
WQ Daily Time=0
WQ Create Restart=0
WQ Fixed Restart=0
WQ System Summary=0
WQ Use Fixed Temperature=0
Sorting and Armoring Iterations= 10
XS Update Threshold= 0.02
Hydraulics Update Threshold= 0.02
Energy Slope Method= 1
Volume Change Method= 0
XS Weighting Method= 0
Number of US Weighted Cross Sections= 1
Number of DS Weighted Cross Sections= 1
Upstream XS Weight=0.25
Main XS Weight=0.5
Downstream XS Weight=0.25
Number of DS XS's Weighted with US Boundary= 1
Upstream Boundary Weight= 1
Weight of XSs Associated with US Boundary= 0
Number of US XS's Weighted with DS Boundary= 1
Downstream Boundary Weight= 0.5
Weight of XSs Associated with DS Boundary= 0.5
Sediment Output Level= 4
Mass or Volume Output= 0
Output Increment Type= 1
Profile and TS Output Increment= 10
XS Output Flag= 0
XS Output Increment= 10
Disregard all LS=0
Disregard all Conn=0
Disregard all Breaches=0
Disregard all Pumps=0

--- Walnut16.f01 (steady flow) ---

Flow Title=Multiple
Number of Profiles=7
Profile Names=10-year,25-year,50-year,1pct_min,100-year,1pct_plu,500-year
River Rch & RM= Walnut16,Reach-1,6735
      99     119     133      75     149     297     186
Boundary for River Rch & Prof#=Walnut16,Reach-1,1
Up Type=0
Dn Type=3
Dn Slope=0.005
Boundary for River Rch & Prof#=Walnut16,Reach-1,2
Up Type=0
Dn Type=3
Dn Slope=0.005
Boundary for River Rch & Prof#=Walnut16,Reach-1,3
Up Type=0
Dn Type=3
Dn Slope=0.005
Boundary for River Rch & Prof#=Walnut16,Reach-1,4
Up Type=0
Dn Type=3
Dn Slope=0.005
Boundary for River Rch & Prof#=Walnut16,Reach-1,5
Up Type=0
Dn Type=3
Dn Slope=0.005
Boundary for River Rch & Prof#=Walnut16,Reach-1,6
Up Type=0
Dn Type=3
Dn Slope=0.005
Boundary for River Rch & Prof#=Walnut16,Reach-1,7
Up Type=0
Dn Type=3
Dn Slope=0.005

--- Walnut16.g01 (geometry) ---

Geom Title=Existing Conditions

River Reach=Walnut16,Reach-1
Reach XY= 30
      2725419.71      6756176.58      2725378.80      6755875.95
      2725414.87      6755800.90      2725329.36      6755719.00
      2725266.00      6755749.76      2725142.65      6755627.68
      2725018.14      6755354.83      2724709.35      6754994.33
      2724435.68      6754721.78      2724216.03      6754600.29
      2724167.65      6754514.19      2723819.94      6754352.86
      2723582.19      6754118.81      2723377.47      6754114.55
      2723189.26      6754247.35      2723132.52      6754403.32
      2722881.44      6754413.19      2722779.33      6754503.39
      2722598.71      6754384.90      2722527.92      6754116.70
      2722775.91      6753742.78      2722773.65      6753516.52
      2722686.00      6753371.61      2722572.69      6753319.02
      2722382.66      6753451.69      2722272.77      6753452.77
      2722120.48      6753363.35      2721877.55      6753357.25
      2721383.68      6753107.45      2721376.00      6753061.00

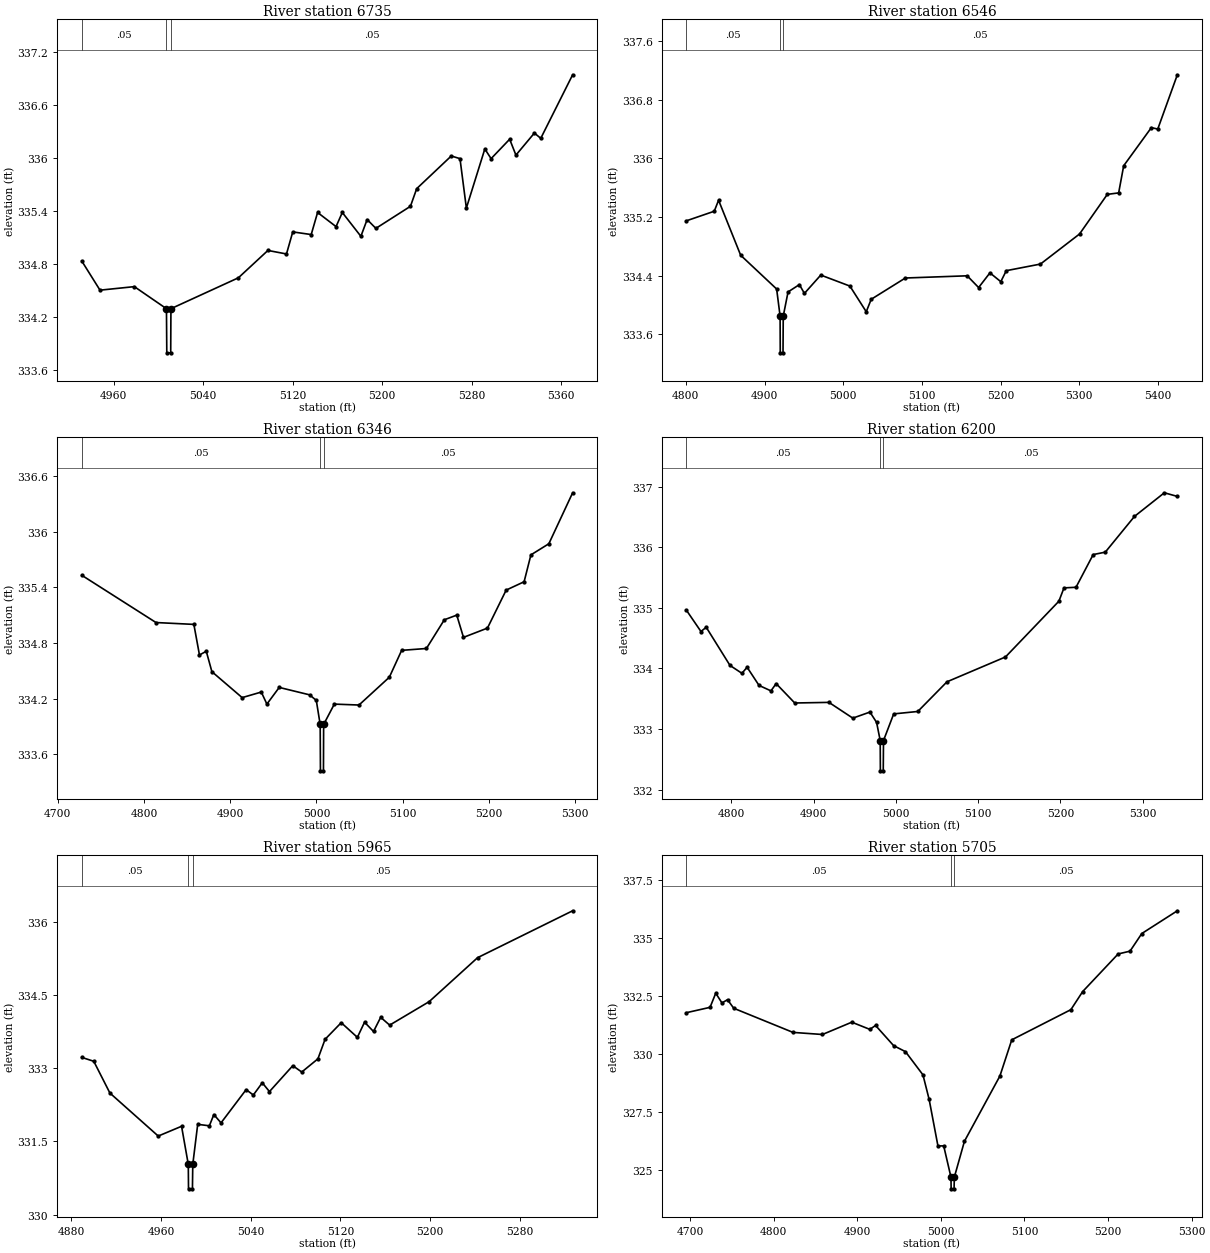
Type RM Length L Ch R = 1,6735,189,189,189
BEGIN DESCRIPTION:
Walnut16 13.0
END DESCRIPTION:
XS GIS Cut Line= 3
      2725451.88      6755913.91      2725315.17      6755944.30
      2725049.59      6756081.11
#Sta/Elev= 30
  4931.6  334.83  4947.9  334.50  4978.6  334.54  5007.3  334.29  5007.6  333.79
  5011.1  333.79  5011.3  334.29  5071.6  334.64  5098.0  334.95  5114.6  334.91
  5120.2  335.16  5136.7  335.13  5142.4  335.38  5158.9  335.22  5164.5  335.38
  5181.1  335.11  5186.7  335.30  5194.5  335.20  5225.4  335.45  5231.0  335.65
  5261.9  336.02  5269.7  335.99  5275.4  335.43  5291.9  336.10  5297.5  335.99
  5314.1  336.21  5319.7  336.03  5336.2  336.28  5341.9  336.22  5370.4  336.94
#Mann=3,-1,0
  4931.6    0.05       0  5007.3    0.04       0  5011.3    0.05       0
Bank Sta=5007.3,5011.3
Exp/Cntr=0.3,0.1

Type RM Length L Ch R = 1,6546,200,200,200
BEGIN DESCRIPTION:
Walnut16 12.0
END DESCRIPTION:
XS GIS Cut Line= 3
      2725549.51      6755660.02      2725482.06      6755689.97
      2725049.55      6756029.90
#Sta/Elev= 30
  4800.8  335.15  4836.1  335.28  4841.6  335.43  4869.7  334.68  4915.4  334.22
  4919.8  333.85  4920.0  333.35  4923.5  333.35  4923.8  333.85  4929.9  334.18
  4944.3  334.28  4950.7  334.16  4971.5  334.41  5008.5  334.26  5029.3  333.91
  5035.6  334.08  5079.0  334.37  5157.6  334.40  5172.1  334.24  5186.5  334.44
  5200.3  334.32  5207.3  334.47  5250.7  334.56  5300.4  334.97  5335.7  335.51
  5350.1  335.53  5356.5  335.90  5391.7  336.42  5399.8  336.40  5424.7  337.14
#Mann=3,-1,0
  4800.8    0.05       0  4919.8    0.04       0  4923.8    0.05       0
Bank Sta=4919.8,4923.8
Exp/Cntr=0.3,0.1

Type RM Length L Ch R = 1,6346,146,146,146
BEGIN DESCRIPTION:
Walnut16 11.0
END DESCRIPTION:
XS GIS Cut Line= 3
      2725447.56      6755553.66      2725364.10      6755602.79
      2724999.85      6755903.69
#Sta/Elev= 30
  4727.8  335.53  4813.9  335.02  4857.8  335.00  4864.3  334.67  4872.2  334.71
  4878.7  334.49  4913.8  334.21  4936.0  334.27  4942.5  334.14  4956.8  334.32
  4992.0  334.24  4999.8  334.18  5004.3  333.92  5004.6  333.42  5008.1  333.42
  5008.3  333.92  5020.7  334.14  5049.3  334.13  5084.5  334.43  5098.8  334.72
  5127.5  334.74  5148.3  335.05  5162.7  335.10  5170.5  334.86  5198.3  334.96
  5220.0  335.37  5240.8  335.46  5248.7  335.75  5269.5  335.87  5297.1  336.42
#Mann=3,-1,0
  4727.8    0.05       0  5004.3    0.04       0  5008.3    0.05       0
Bank Sta=5004.3,5008.3
Exp/Cntr=0.3,0.1

Type RM Length L Ch R = 1,6200,235,235,235
BEGIN DESCRIPTION:
Walnut16 10.0
END DESCRIPTION:
XS GIS Cut Line= 3
      2725330.38      6755451.65      2725126.00      6755611.00
      2724853.24      6755809.84
#Sta/Elev= 30
  4745.4  334.96  4763.0  334.61  4769.4  334.68  4798.3  334.05  4812.8  333.92
  4819.1  334.02  4833.6  333.72  4848.1  333.63  4854.4  333.75  4877.0  333.43
  4918.6  333.44  4947.6  333.18  4968.4  333.28  4976.5  333.11  4980.9  332.81
  4981.1  332.31  4984.6  332.31  4984.9  332.81  4997.3  333.25  5026.6  333.29
  5062.1  333.78  5133.2  334.19  5198.1  335.11  5204.3  335.33  5218.9  335.34
  5239.8  335.88  5254.5  335.92  5290.0  336.51  5326.3  336.90  5342.1  336.84
#Mann=3,-1,0
  4745.4    0.05       0  4980.9    0.04       0  4984.9    0.05       0
Bank Sta=4980.9,4984.9
Exp/Cntr=0.3,0.1

Type RM Length L Ch R = 1,5965,260,260,260
BEGIN DESCRIPTION:
Walnut16 9.0
END DESCRIPTION:
XS GIS Cut Line= 3
      2725111.94      6755341.36      2725026.00      6755411.00
      2724771.08      6755616.11
#Sta/Elev= 30
  4889.4  333.22  4900.1  333.14  4914.5  332.49  4957.6  331.61  4978.4  331.81
  4984.4  331.03  4984.6  330.53  4988.1  330.53  4988.4  331.03  4992.8  331.85
  5003.2  331.82  5007.2  332.05  5013.6  331.88  5036.0  332.56  5042.4  332.45
  5050.4  332.70  5056.8  332.52  5077.6  333.05  5085.6  332.92  5100.0  333.19
  5106.4  333.59  5120.8  333.93  5135.2  333.63  5141.6  333.94  5149.6  333.75
  5156.0  334.04  5164.0  333.88  5199.2  334.36  5242.4  335.26  5327.2  336.22
#Mann=3,-1,0
  4889.4    0.05       0  4984.4   0.035       0  4988.4    0.05       0
Bank Sta=4984.4,4988.4
Exp/Cntr=0.3,0.1

Type RM Length L Ch R = 1,5705,257,257,257
BEGIN DESCRIPTION:
Walnut16 8.0
END DESCRIPTION:
XS GIS Cut Line= 3
      2725100.18      6755005.51      2724876.00      6755211.00
      2724675.97      6755411.03
#Sta/Elev= 30
  4695.9  331.79  4724.1  332.02  4730.9  332.63  4738.3  332.21  4745.0  332.35
  4752.4  331.98  4823.3  330.94  4858.5  330.85  4893.6  331.38  4915.2  331.07
  4922.0  331.24  4943.6  330.37  4957.8  330.11  4978.7  329.11  4986.1  328.05
  4996.6  326.05  5003.5  326.05  5012.2  324.70  5012.4  324.20  5015.9  324.20
  5016.2  324.70  5028.3  326.25  5070.7  329.06  5084.9  330.62  5155.6  331.92
  5169.7  332.70  5212.1  334.32  5226.3  334.44  5240.4  335.20  5282.9  336.18
#Mann=3,-1,0
  4695.9    0.05       0  5012.2   0.035       0  5016.2    0.05       0
Bank Sta=5012.2,5016.2
Exp/Cntr=0.3,0.1

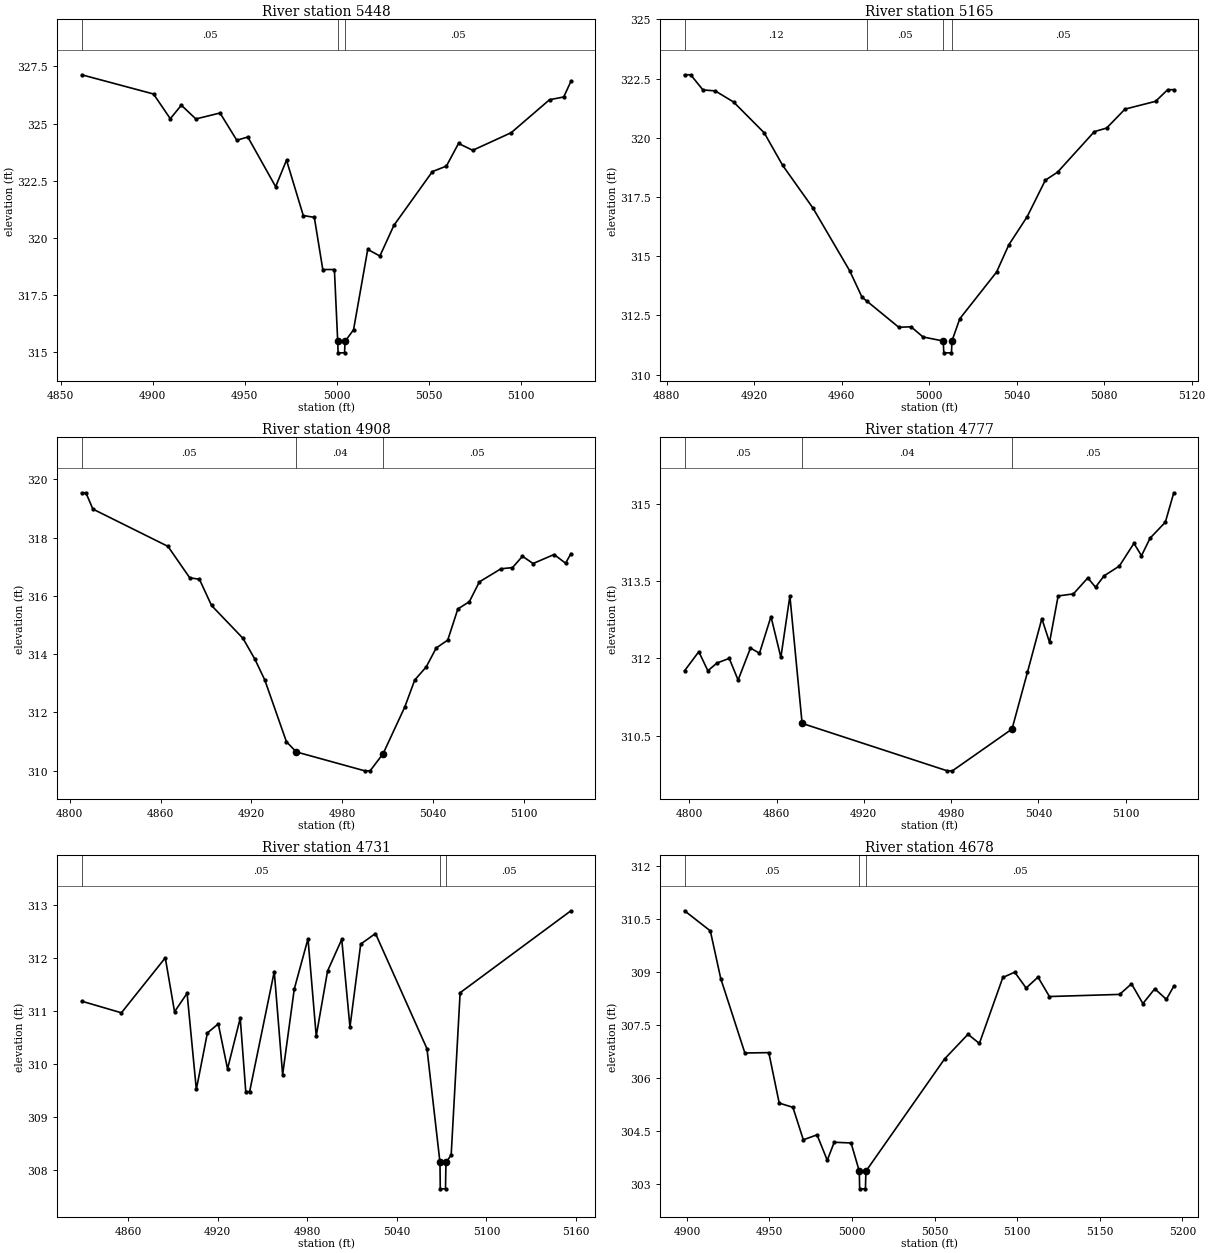
Type RM Length L Ch R = 1,5448,283,283,283
BEGIN DESCRIPTION:
Walnut16 7.0
END DESCRIPTION:
XS GIS Cut Line= 3
      2724837.77      6754937.33      2724726.00      6755011.00
      2724626.18      6755096.98
#Sta/Elev= 30
  4861.5  327.13  4900.5  326.29  4909.6  325.21  4915.6  325.80  4923.5  325.20
  4936.6  325.46  4945.7  324.27  4951.7  324.41  4966.8  322.24  4972.7  323.40
  4981.8  320.98  4987.8  320.90  4992.4  318.62  4998.7  318.62  5000.5  315.48
  5000.7  314.98  5004.2  314.98  5004.5  315.48  5009.1  315.99  5016.8  319.50
  5023.4  319.21  5031.0  320.55  5051.9  322.90  5059.5  323.14  5066.1  324.13
  5073.8  323.83  5094.7  324.60  5115.5  326.04  5123.2  326.16  5127.1  326.84
#Mann=3,-1,0
  4861.5    0.05       0  5000.5    0.04       0  5004.5    0.05       0
Bank Sta=5000.5,5004.5
Exp/Cntr=0.3,0.1

Type RM Length L Ch R = 1,5165,257,257,257
BEGIN DESCRIPTION:
Walnut16 6.0
END DESCRIPTION:
XS GIS Cut Line= 3
      2724626.03      6754760.99      2724526.00      6754811.00
      2724476.02      6754910.96
#Sta/Elev= 30
  4888.2  322.66  4891.0  322.66  4896.6  322.02  4902.2  321.98  4910.6  321.51
  4924.6  320.21  4933.0  318.84  4946.9  317.03  4963.7  314.38  4969.3  313.27
  4971.7  313.09  4986.1  312.00  4991.7  312.02  4997.2  311.59  5006.4  311.42
  5006.7  310.92  5010.2  310.92  5010.4  311.42  5014.0  312.36  5030.8  314.33
  5036.4  315.48  5044.8  316.67  5053.1  318.21  5058.7  318.55  5075.5  320.26
  5081.1  320.41  5089.5  321.21  5103.5  321.54  5109.0  322.03  5111.8  322.03
#Mann=4,-1,0
  4888.2    0.12       0  4971.7    0.05       0  5006.4    0.04       0
  5010.4    0.05       0
Bank Sta=5006.4,5010.4
Exp/Cntr=0.3,0.1

Type RM Length L Ch R = 1,4908,131,131,131
BEGIN DESCRIPTION:
Walnut16 5.0
END DESCRIPTION:
XS GIS Cut Line= 3
      2724475.36      6754540.19      2724326.00      6754661.00
      2724227.18      6754747.31
#Sta/Elev= 30
  4807.9  319.54  4810.7  319.54  4815.3  318.98  4864.9  317.70  4879.3  316.62
  4885.7  316.57  4893.7  315.67  4914.5  314.54  4922.4  313.82  4928.9  313.11
  4943.2  310.99  4949.7  310.64  4995.0  309.99  4998.5  309.99  5007.1  310.58
  5021.4  312.18  5028.0  313.11  5035.6  313.56  5042.2  314.21  5049.8  314.48
  5056.5  315.55  5064.1  315.80  5070.7  316.48  5085.0  316.93  5092.6  316.97
  5099.2  317.36  5106.2  317.11  5120.1  317.42  5127.7  317.12  5131.2  317.45
#Mann=3,-1,0
  4807.9    0.05       0  4949.7    0.04       0  5007.1    0.05       0
Bank Sta=4949.7,5007.1
Exp/Cntr=0.3,0.1

Type RM Length L Ch R = 1,4777,46,46,46
BEGIN DESCRIPTION:
Walnut16 4.2
END DESCRIPTION:
XS GIS Cut Line= 3
      2724310.39      6754423.03      2724245.29      6754512.00
      2724173.81      6754726.46
#Sta/Elev= 29
  4796.8  311.76  4806.6  312.13  4812.8  311.76  4819.1  311.91  4827.5  312.00
  4833.6  311.58  4842.1  312.20  4848.3  312.10  4856.2  312.81  4863.0  312.02
  4869.2  313.21  4877.6  310.74  4977.4  309.82  4980.9  309.82  5021.9  310.63
  5032.5  311.73  5042.4  312.77  5047.7  312.31  5053.6  313.21  5064.1  313.25
  5074.0  313.56  5079.3  313.38  5085.2  313.60  5095.7  313.79  5105.7  314.23
  5110.9  313.99  5116.8  314.33  5127.3  314.64  5133.1  315.21
#Mann=3,-1,0
  4796.8    0.05       0  4877.6    0.04       0  5021.9    0.05       0
Bank Sta=4877.6,5021.9
Exp/Cntr=0.3,0.1

Type RM Length L Ch R = 1,4731,53,53,53
BEGIN DESCRIPTION:
Walnut16 4.1
END DESCRIPTION:
XS GIS Cut Line= 3
      2724275.66      6754423.04      2724210.57      6754512.00
      2724115.91      6754707.78
#Sta/Elev= 30
  4828.9  311.19  4855.5  310.97  4884.9  312.01  4891.1  310.99  4899.5  311.34
  4905.7  309.52  4913.1  310.59  4920.4  310.76  4926.6  309.91  4935.1  310.87
  4938.8  309.48  4941.4  309.48  4957.9  311.75  4963.5  309.80  4971.3  311.42
  4980.5  312.37  4986.0  310.53  4993.6  311.76  5003.1  312.36  5008.6  310.70
  5015.8  312.27  5025.7  312.47  5060.2  310.29  5068.9  308.14  5069.1  307.64
  5072.6  307.64  5072.9  308.14  5076.4  308.28  5082.4  311.35  5156.6  312.90
#Mann=3,-1,0
  4828.9    0.05       0  5068.9    0.04       0  5072.9    0.05       0
Bank Sta=5068.9,5072.9
Exp/Cntr=0.3,0.1

Type RM Length L Ch R = 1,4678,306,306,306
BEGIN DESCRIPTION:
Walnut16 4.0
END DESCRIPTION:
XS GIS Cut Line= 3
      2724232.28      6754436.04      2724176.00      6754511.00
      2724035.44      6754656.72
#Sta/Elev= 30
  4898.6  310.74  4914.2  310.17  4920.5  308.82  4935.1  306.71  4949.6  306.72
  4955.9  305.29  4964.2  305.17  4970.5  304.25  4978.8  304.39  4985.0  303.67
  4989.2  304.18  4999.4  304.16  5004.4  303.36  5004.6  302.86  5008.1  302.86
  5008.4  303.36  5056.0  306.54  5070.2  307.24  5077.1  306.98  5091.3  308.85
  5098.5  309.00  5105.4  308.55  5112.6  308.86  5119.5  308.31  5162.0  308.37
  5169.2  308.67  5176.1  308.11  5183.3  308.53  5190.3  308.23  5194.8  308.60
#Mann=3,-1,0
  4898.6    0.05       0  5004.4    0.04       0  5008.4    0.05       0
Bank Sta=5004.4,5008.4
Exp/Cntr=0.3,0.1

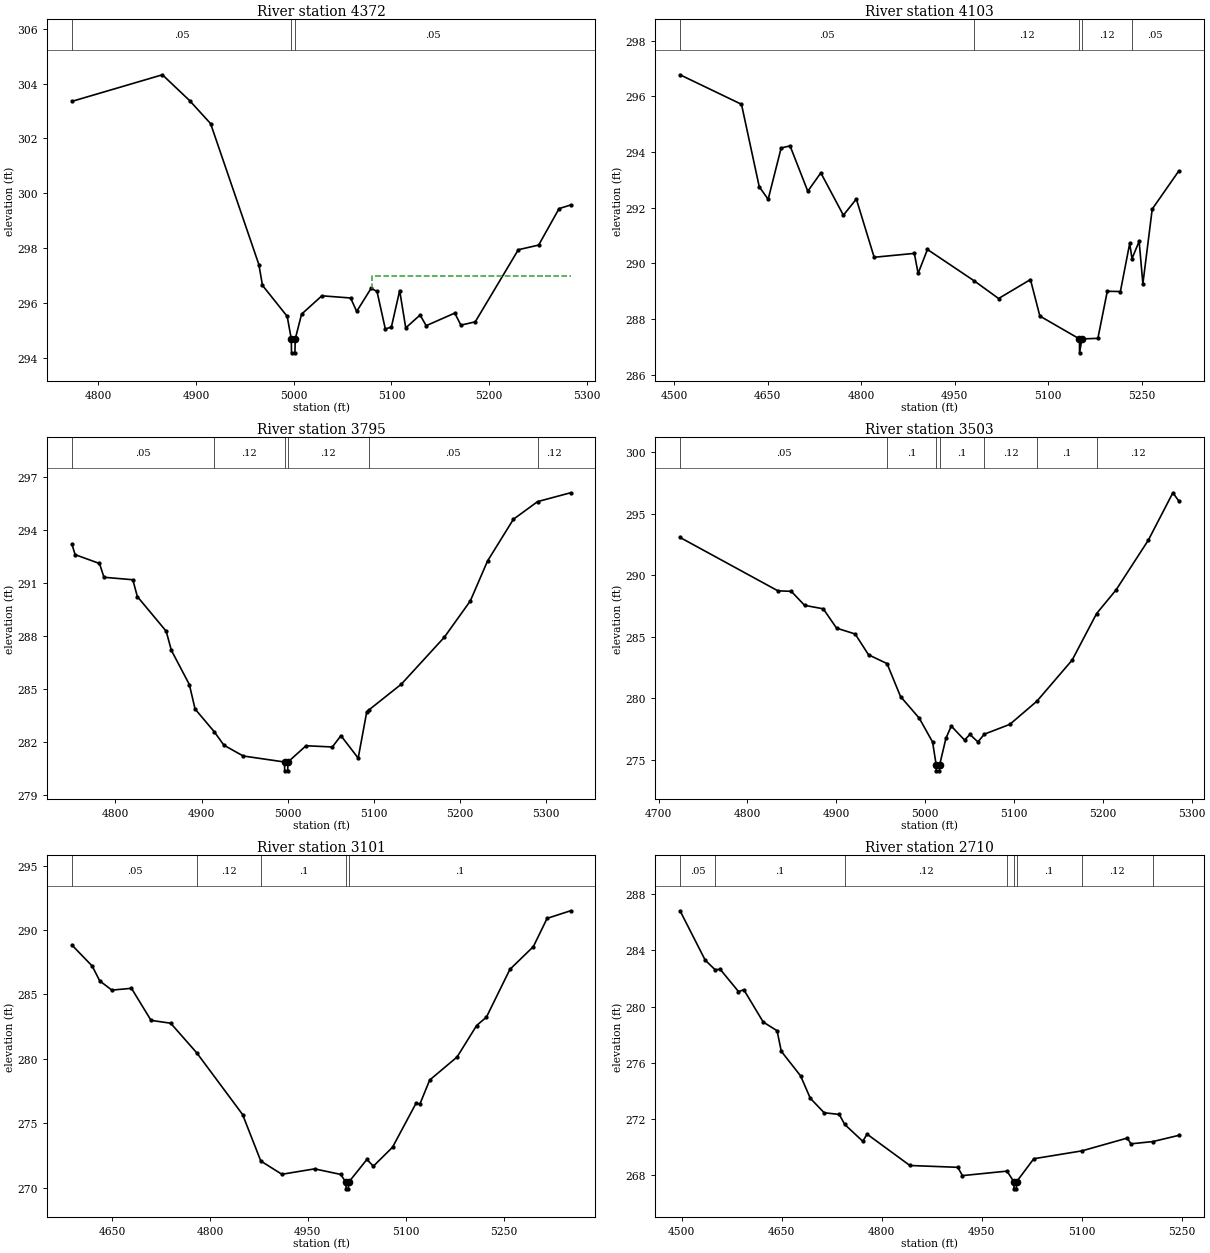
Type RM Length L Ch R = 1,4372,269,269,269
BEGIN DESCRIPTION:
Walnut16 3.0
END DESCRIPTION:
XS GIS Cut Line= 3
      2724055.93      6754220.72      2723926.10      6754367.87
      2723741.43      6754621.78
#Sta/Elev= 30
  4773.1  303.35  4865.7  304.32  4893.5  303.38  4915.0  302.54  4964.4  297.40
  4968.1  296.64  4993.4  295.51  4997.6  294.68  4997.8  294.18  5001.3  294.18
  5001.6  294.68  5008.1  295.59  5028.9  296.26  5058.3  296.18  5064.5  295.69
  5079.2  296.53  5085.3  296.42  5093.8  295.05  5100.0  295.12  5108.5  296.45
  5114.7  295.09  5129.4  295.56  5135.6  295.17  5164.9  295.63  5171.1  295.19
  5185.8  295.31  5229.9  297.94  5250.7  298.11  5271.6  299.44  5283.3  299.57
#Mann=3,-1,0
  4773.1    0.05       0  4997.6    0.04       0  5001.6    0.05       0
#XS Ineff=2,0
       0                 5080.00    0.00  297.00
Permanent Ineff=
       F       F
Bank Sta=4997.6,5001.6
Exp/Cntr=0.3,0.1

Type RM Length L Ch R = 1,4103,308,308,308
BEGIN DESCRIPTION:
Walnut16 2.0
END DESCRIPTION:
XS GIS Cut Line= 3
      2724045.81      6753891.79      2723768.84      6754129.82
      2723527.93      6754491.90
#Sta/Elev= 30
  4509.3  296.77  4607.9  295.71  4636.4  292.75  4650.7  292.30  4671.5  294.14
  4685.8  294.22  4714.3  292.59  4735.2  293.25  4771.4  291.73  4792.2  292.31
  4820.8  290.22  4885.3  290.36  4891.3  289.64  4906.3  290.50  4980.9  289.38
  5020.5  288.74  5071.6  289.42  5086.7  288.11  5150.2  287.29  5150.4  286.79
  5154.2  287.29  5179.8  287.31  5194.9  289.00  5215.9  288.99  5230.9  290.72
  5234.5  290.17  5246.0  290.79  5252.0  289.27  5267.0  291.95  5309.4  293.31
#Mann=5,-1,0
  4509.3    0.05       0  4980.9    0.12       0  5150.2    0.07       0
  5154.2    0.12       0  5234.5    0.05       0
Bank Sta=5150.2,5154.2
Exp/Cntr=0.3,0.1

Type RM Length L Ch R = 1,3795,292,292,292
BEGIN DESCRIPTION:
Walnut16 1.0
END DESCRIPTION:
XS GIS Cut Line= 3
      2723370.66      6753870.16      2723450.00      6754142.80
      2723439.94      6754437.28
#Sta/Elev= 30
  4749.5  293.20  4753.2  292.60  4781.5  292.10  4786.7  291.32  4820.2  291.18
  4825.4  290.23  4858.9  288.27  4864.9  287.19  4885.8  285.25  4892.4  283.87
  4914.7  282.58  4925.9  281.82  4948.3  281.21  4996.2  280.87  4996.4  280.37
  4999.9  280.37  5000.2  280.87  5021.2  281.79  5051.7  281.72  5061.7  282.36
  5081.7  281.09  5091.7  283.72  5094.0  283.81  5131.7  285.27  5181.7  287.93
  5211.8  289.98  5231.8  292.24  5261.8  294.60  5289.9  295.60  5328.1  296.10
#Mann=6,-1,0
  4749.5    0.05       0  4914.7    0.12       0  4996.2    0.07       0
  5000.2    0.12       0  5094.0    0.05       0  5289.9    0.12       0
Bank Sta=4996.2,5000.2
Exp/Cntr=0.3,0.1

Type RM Length L Ch R = 1,3503,402,402,402
BEGIN DESCRIPTION:
Walnut16 0.5
END DESCRIPTION:
XS GIS Cut Line= 3
      2723041.69      6754011.49      2723252.35      6754326.03
      2723368.06      6754467.46
#Sta/Elev= 30
  4724.1  293.08  4834.3  288.74  4849.3  288.70  4864.3  287.56  4885.3  287.28
  4900.3  285.71  4921.3  285.23  4936.3  283.54  4957.1  282.83  4972.3  280.15
  4993.4  278.39  5008.4  276.45  5012.4  274.61  5012.6  274.11  5016.1  274.11
  5016.4  274.61  5023.4  276.75  5029.4  277.75  5044.4  276.61  5050.4  277.07
  5059.4  276.46  5066.7  277.09  5095.4  277.89  5125.8  279.77  5165.5  283.11
  5193.0  286.89  5215.0  288.82  5251.2  292.85  5278.9  296.71  5285.4  296.06
#Mann=7,-1,0
  4724.1    0.05       0  4957.1     0.1       0  5012.4    0.07       0
  5016.4     0.1       0  5066.7    0.12       0  5125.8     0.1       0
  5193.0    0.12       0
Bank Sta=5012.4,5016.4
Exp/Cntr=0.3,0.1

Type RM Length L Ch R = 1,3101,391,391,391
BEGIN DESCRIPTION:
Walnut16 0.2
END DESCRIPTION:
XS GIS Cut Line= 3
      2722943.61      6753999.95      2722911.87      6754474.63
      2723150.99      6754635.96
#Sta/Elev= 30
  4588.5  288.83  4619.6  287.20  4631.1  286.05  4649.7  285.33  4679.8  285.47
  4709.8  282.98  4739.9  282.76  4780.0  280.45  4850.1  275.67  4878.0  272.06
  4910.3  271.03  4960.4  271.45  5000.5  271.02  5008.5  270.40  5008.7  269.90
  5012.2  269.90  5012.5  270.40  5040.6  272.18  5050.6  271.66  5079.9  273.13
  5115.9  276.54  5121.9  276.49  5136.9  278.35  5178.9  280.14  5208.8  282.58
  5223.8  283.23  5259.8  286.94  5295.8  288.71  5316.8  290.90  5352.7  291.49
#Mann=5,-1,0
  4588.5    0.05       0  4780.0    0.12       0  4878.0     0.1       0
  5008.5    0.07       0  5012.5     0.1       0
Bank Sta=5008.5,5012.5
Exp/Cntr=0.3,0.1

Type RM Length L Ch R = 1,2710,393,393,393
BEGIN DESCRIPTION:
Walnut16 0.1
END DESCRIPTION:
XS GIS Cut Line= 3
      2722910.67      6753991.75      2722581.00      6754417.23
      2722657.35      6754612.16
#Sta/Elev= 30
  4497.5  286.82  4535.2  283.31  4549.8  282.64  4557.9  282.65  4585.1  281.08
  4593.2  281.20  4622.2  278.91  4643.0  278.29  4649.3  276.83  4678.3  275.08
  4692.8  273.49  4713.6  272.46  4736.2  272.34  4744.4  271.63  4771.5  270.43
  4777.9  270.94  4842.1  268.71  4914.0  268.58  4920.9  267.99  4987.8  268.31
  4998.0  267.55  4998.3  267.05  5001.8  267.05  5002.0  267.55  5027.9  269.19
  5100.1  269.75  5168.1  270.66  5173.5  270.25  5206.3  270.41  5245.1  270.85
#Mann=8,-1,0
  4497.5    0.05       0  4549.8     0.1       0  4744.4    0.12       0
  4987.8     0.1       0  4998.0    0.07       0  5002.0     0.1       0
  5100.1    0.12       0  5206.3    0.05       0
Bank Sta=4998,5002
Exp/Cntr=0.3,0.1

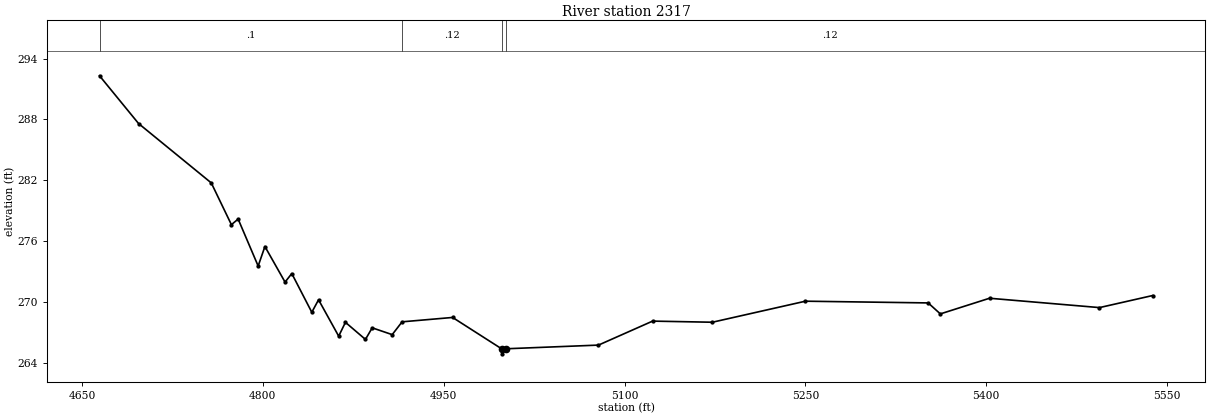
Type RM Length L Ch R = 1,2317,0,0,0
BEGIN DESCRIPTION:
Walnut16 0.0
END DESCRIPTION:
XS GIS Cut Line= 3
      2722874.91      6753884.57      2722421.84      6754115.16
      2722353.64      6754474.06
#Sta/Elev= 30
  4664.5  292.30  4696.9  287.60  4757.2  281.76  4773.9  277.65  4779.5  278.20
  4796.1  273.58  4801.7  275.50  4818.4  272.00  4824.0  272.84  4840.6  269.03
  4846.2  270.26  4862.9  266.68  4868.5  268.04  4885.1  266.36  4890.7  267.50
  4907.3  266.83  4915.5  268.09  4957.4  268.52  4998.0  265.44  4998.3  264.94
  5002.0  265.44  5078.4  265.80  5123.3  268.16  5172.9  268.05  5250.1  270.12
  5351.9  269.95  5362.0  268.87  5402.8  270.41  5494.0  269.49  5538.2  270.68
#Mann=4,-1,0
  4664.5     0.1       0  4915.5    0.12       0  4998.0    0.07       0
  5002.0    0.12       0
Bank Sta=4998,5002
Exp/Cntr=0.3,0.1

Chan Stop Cuts=-1