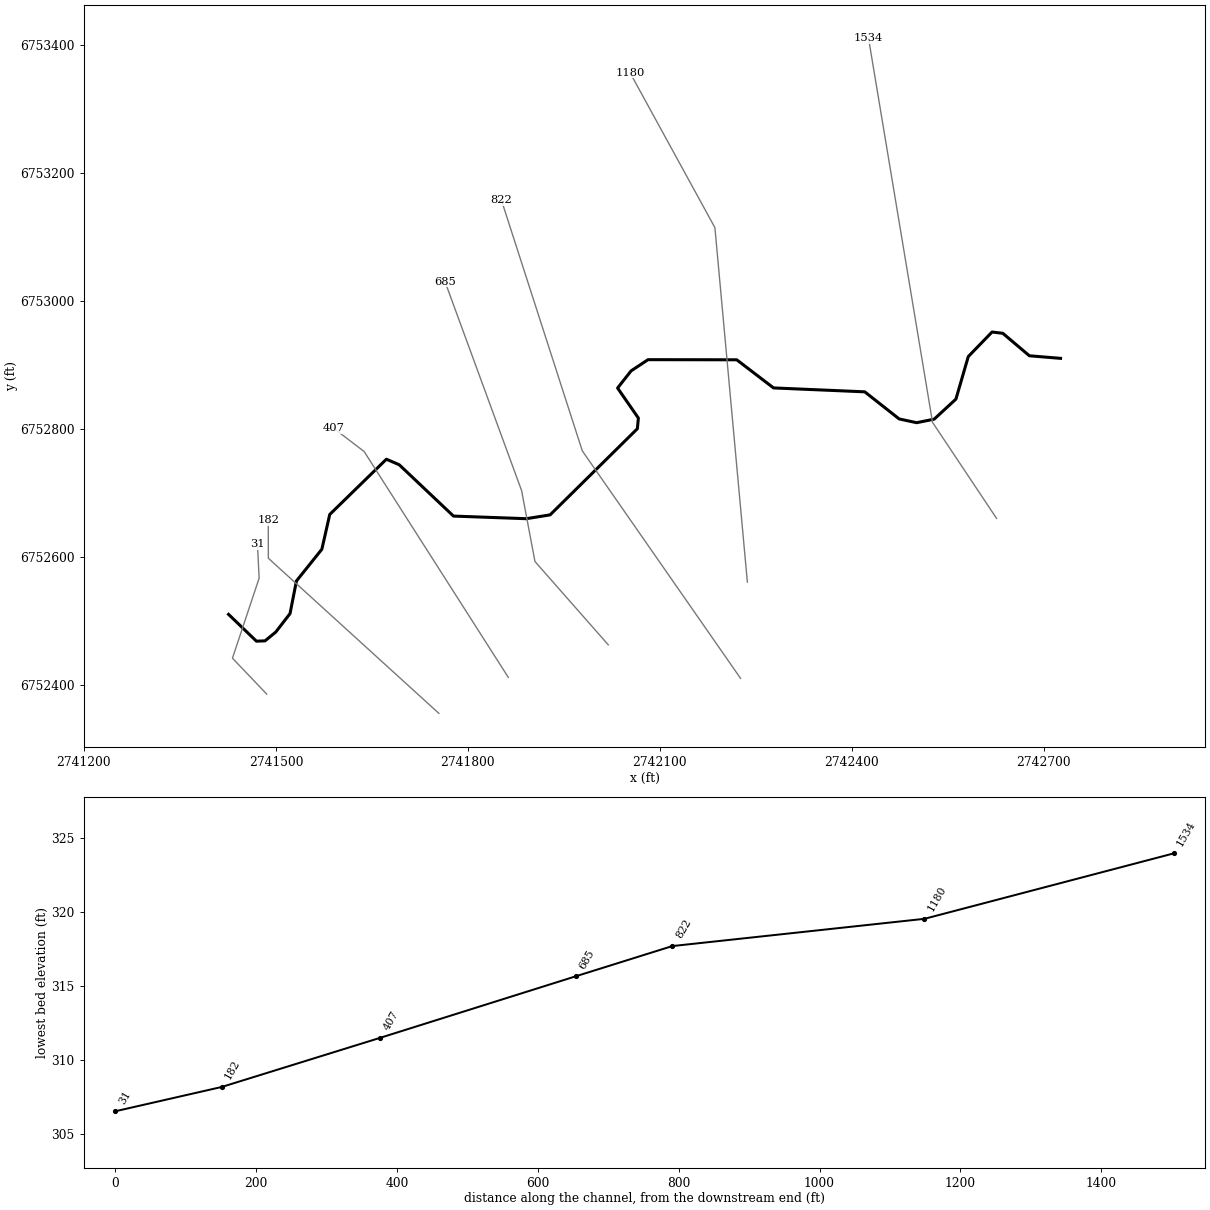
--- Walnut17.prj (project) ---

Proj Title=Walnut17 Base Level Engineering
Current Plan=p01
Default Exp/Contr=0.3,0.1
English Units
Geom File=g01
Flow File=f01
Plan File=p01
Y Axis Title=Elevation
X Axis Title(PF)=Main Channel Distance
X Axis Title(XS)=Station
BEGIN DESCRIPTION:
Walnut17
END DESCRIPTION:
DSS Export Rating Curves= 0
DSS Export Rating Curve Sorted= 0
DSS Export Volume Flow Curves= 0
DXF OffsetX= 0
DXF OffsetY= 0
DXF ScaleX= 1
DXF ScaleY= 10

--- Walnut17.p01 (plan) ---

Plan Title=Multiple Run
Program Version=4.10
Short Identifier=Multiple
Geom File=g01
Flow File=f01
Subcritical Flow
K Sum by GR= 0
Std Step Tol= 0.01
Critical Tol= 0.01
Num of Std Step Trials= 20
Max Error Tol= 0.3
Flow Tol Ratio= 0.001
Split Flow NTrial= 30
Split Flow Tol= 0.02
Split Flow Ratio= 0.02
Log Output Level= 0
Friction Slope Method= 1
Unsteady Friction Slope Method= 2
Unsteady Bridges Friction Slope Method= 1
Parabolic Critical Depth
Global Vel Dist= 1 , 1 , 1
Global Log Level= 0
CheckData=True
Encroach Param=-1 ,0,0, 0
BEGIN DESCRIPTION:
Multiple Run
END DESCRIPTION:
Computation Interval=1HOUR
Output Interval=1HOUR
Run HTab= 0
Run UNet= 0
Run PostProcess= 0
Run WQNet= 0
UNET Theta= 1
UNET Theta Warmup= 1
UNET ZTol= 0.02
UNET ZSATol= 0.05
UNET MxIter= 20
UNET MaxInSteps= 0
UNET DtIC= 0
UNET DtMin= 0
UNET MaxCRTS= 20
UNET WFStab= 2
UNET SFStab= 1
UNET WFX= 1
UNET SFX= 1
UNET DSS MLevel= 4
UNET DZMax Abort= 100
UNET Convert EG Bridges= 0
UNET Use Existing IB Tables=-1
UNET Froude Reduction=False
UNET Froude Limit= 1
UNET Froude Power= 10
UNET Time Slicing=0,0, 5
UNET Junction Losses=0
Instantaneous Interval=1HOUR
Write IC File= 0
Write IC File at Sim End=0
Echo Input=False
Echo Parameters=False
Echo Output=False
Write Detailed= 0
WQ AD Non Conservative
WQ ULTIMATE=-1
WQ Max Comp Step=1HOUR
WQ Output Interval=15MIN
WQ Output Selected Increments= 0
WQ Output face flow=0
WQ Output face velocity=0
WQ Output face area=0
WQ Output face dispersion=0
WQ Output cell volume=0
WQ Output cell surface area=0
WQ Output cell continuity=0
WQ Output cumulative cell continuity=0
WQ Output face conc=0
WQ Output face dconc_dx=0
WQ Output face courant=0
WQ Output face peclet=0
WQ Output face adv mass=0
WQ Output face disp mass=0
WQ Output cell mass=0
WQ Output cell source sink temp=0
WQ Output cell source sink nsm=0
WQ Output MaxMinRange=-1
WQ Daily Max Min Mean=-1
WQ Daily Range=0
WQ Daily Time=0
WQ Create Restart=0
WQ Fixed Restart=0
WQ System Summary=0
WQ Use Fixed Temperature=0
Sorting and Armoring Iterations= 10
XS Update Threshold= 0.02
Hydraulics Update Threshold= 0.02
Energy Slope Method= 1
Volume Change Method= 0
XS Weighting Method= 0
Number of US Weighted Cross Sections= 1
Number of DS Weighted Cross Sections= 1
Upstream XS Weight=0.25
Main XS Weight=0.5
Downstream XS Weight=0.25
Number of DS XS's Weighted with US Boundary= 1
Upstream Boundary Weight= 1
Weight of XSs Associated with US Boundary= 0
Number of US XS's Weighted with DS Boundary= 1
Downstream Boundary Weight= 0.5
Weight of XSs Associated with DS Boundary= 0.5
Sediment Output Level= 4
Mass or Volume Output= 0
Output Increment Type= 1
Profile and TS Output Increment= 10
XS Output Flag= 0
XS Output Increment= 10
Disregard all LS=0
Disregard all Conn=0
Disregard all Breaches=0
Disregard all Pumps=0

--- Walnut17.f01 (steady flow) ---

Flow Title=Multiple
Program Version=4.10
Number of Profiles= 7
Profile Names=10-year,25-year,50-year,1pct_min,100-year,1pct_plu,500-year
River Rch & RM=Walnut17,Reach-1         ,1534
     392     517     618     368     734    1464    1035
River Rch & RM=Walnut17,Reach-1         ,31
     716     965    1168     700    1397    2788    2006
Boundary for River Rch & Prof#=Walnut17,Reach-1         , 1
Up Type= 0
Dn Type= 3
Dn Slope=0.01
Boundary for River Rch & Prof#=Walnut17,Reach-1         , 2
Up Type= 0
Dn Type= 3
Dn Slope=0.01
Boundary for River Rch & Prof#=Walnut17,Reach-1         , 3
Up Type= 0
Dn Type= 3
Dn Slope=0.01
Boundary for River Rch & Prof#=Walnut17,Reach-1         , 4
Up Type= 0
Dn Type= 3
Dn Slope=0.01
Boundary for River Rch & Prof#=Walnut17,Reach-1         , 5
Up Type= 0
Dn Type= 3
Dn Slope=0.01
Boundary for River Rch & Prof#=Walnut17,Reach-1         , 6
Up Type= 0
Dn Type= 3
Dn Slope=0.01
Boundary for River Rch & Prof#=Walnut17,Reach-1         , 7
Up Type= 0
Dn Type= 3
Dn Slope=0.01
DSS Import GetInterval= 0
DSS Import GetPeak= 0
DSS Import FillOption= 0

--- Walnut17.g01 (geometry) ---

Geom Title=Existing Conditions
Program Version=4.10

River Reach=Walnut17        ,Reach-1
Reach XY= 30
        2742726.        6752911.      2742677.34      6752915.03
      2742635.75      6752950.17      2742618.98      6752952.15
      2742581.85      6752913.81      2742562.52      6752847.32
      2742528.55      6752815.99      2742501.12      6752810.47
      2742473.85      6752816.34      2742420.07       6752858.7
      2742277.57      6752864.79      2742220.06      6752908.75
      2742081.46      6752908.95      2742054.94       6752891.4
      2742033.88      6752864.62      2742066.38      6752817.69
      2742064.75      6752801.01      2741928.45      6752666.45
      2741891.19      6752660.47      2741777.47      6752664.55
      2741692.65      6752744.77      2741672.65      6752753.41
      2741584.14      6752667.09      2741571.81      6752612.74
      2741532.09      6752563.15      2741522.08      6752512.21
       2741499.8      6752483.35      2741483.04      6752469.61
      2741469.55       6752469.1        2741426.        6752511.

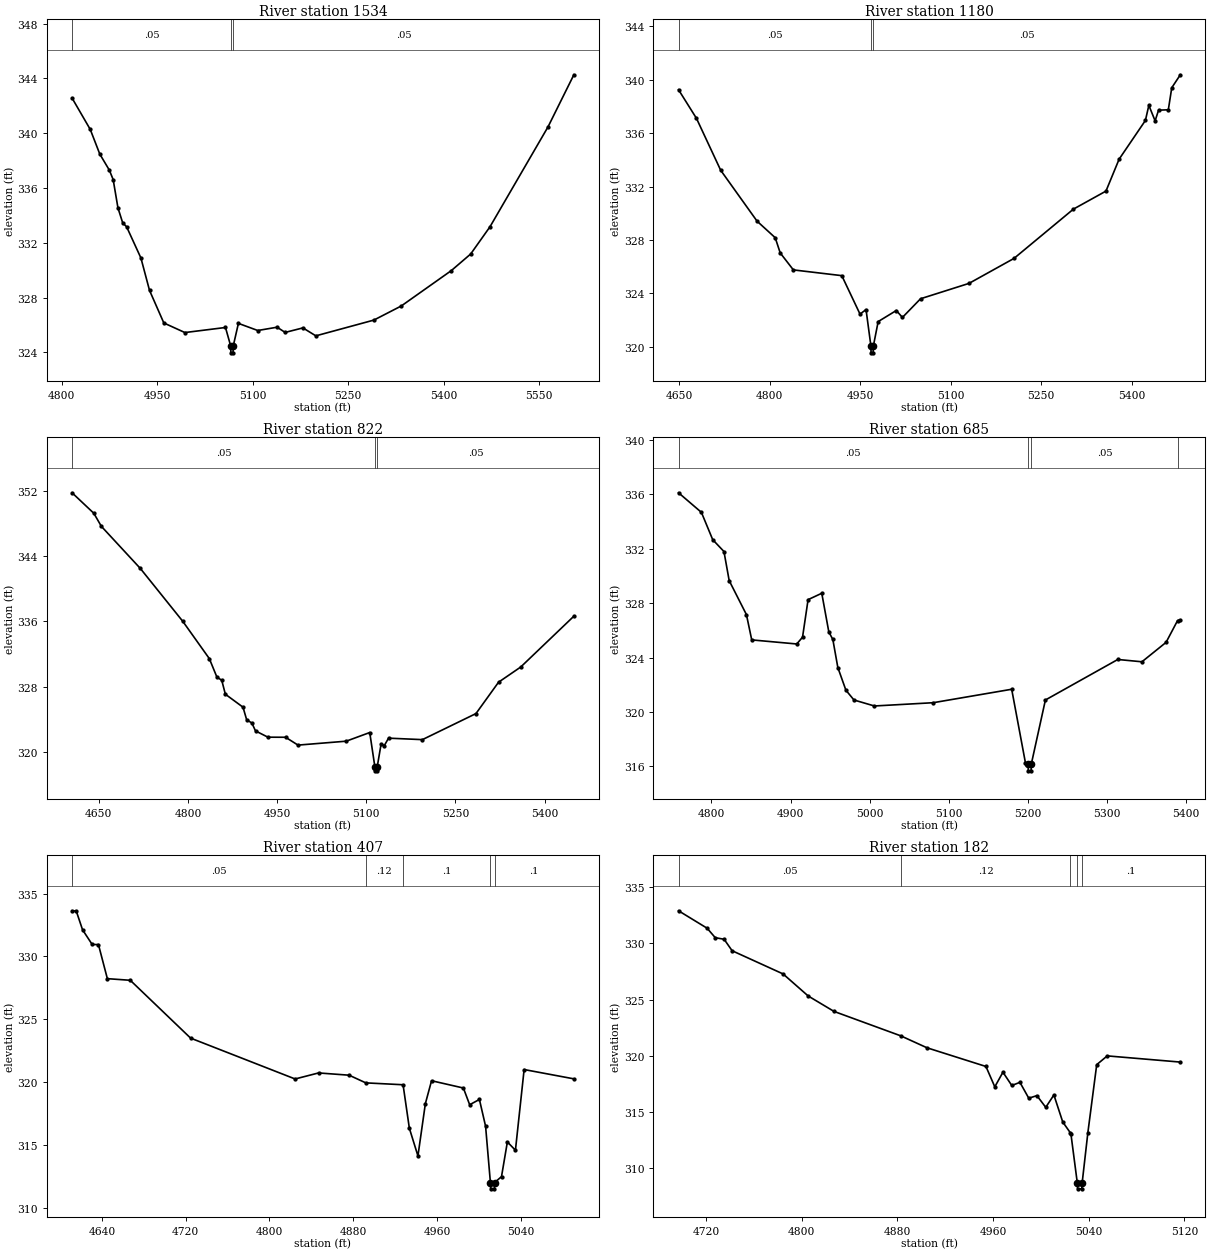
Type RM Length L Ch R = 1 ,1534    ,354,354,354
BEGIN DESCRIPTION:
Walnut17 4.0
END DESCRIPTION:
XS GIS Cut Line= 3
      2742626.01      6752660.98        2742526.        6752811.
        2742426.      6753411.03
#Sta/Elev= 30
  4816.2  342.56  4844.8  340.27  4859.8  338.47  4874.8   337.3  4880.8  336.61
  4888.3  334.55  4895.8  333.45  4901.9  333.17  4924.4  330.89  4937.9  328.53
  4960.4  326.15  4993.5  325.45  5057.3  325.82  5065.5  324.47  5065.7  323.97
  5069.2  323.97  5069.5  324.47  5077.6  326.12    5108   325.6  5138.4  325.84
  5151.1  325.46    5179  325.79  5199.3  325.21  5290.5  326.36  5333.6  327.39
  5412.2  329.97  5442.6  331.18    5473  333.17  5564.2  340.46  5604.8  344.26
#Mann= 3 ,-1 , 0
  4816.2     .05       0  5065.5     .04       0  5069.5     .05       0
Bank Sta=5065.5,5069.5
XS Rating Curve= 0 ,0
Exp/Cntr=0.3,0.1

Type RM Length L Ch R = 1 ,1180    ,358,358,358
BEGIN DESCRIPTION:
Walnut17 3.0
END DESCRIPTION:
XS GIS Cut Line= 3
      2742236.68      6752561.39      2742185.94      6753115.24
      2742053.42      6753357.15
#Sta/Elev= 30
  4648.9  339.25  4678.6  337.11  4718.8  333.22  4779.1  329.41  4809.2  328.17
  4817.5  327.03  4839.3  325.76  4919.6  325.33  4949.8  322.45  4959.8  322.79
  4967.9  320.05  4968.1  319.55  4971.6  319.55  4971.9  320.05  4979.9  321.89
    5010  322.72  5020.1   322.2  5050.2   323.6  5130.5  324.75  5205.1  326.62
  5303.6  330.31  5357.6  331.66  5379.4  334.05    5423  336.95  5428.7  338.08
  5439.1  336.92  5444.8  337.72    5461  337.75  5466.7   339.4  5480.9  340.37
#Mann= 3 ,-1 , 0
  4648.9     .05       0  4967.9     .05       0  4971.9     .05       0
Bank Sta=4967.9,4971.9
XS Rating Curve= 0 ,0
Exp/Cntr=0.3,0.1

Type RM Length L Ch R = 1 ,822     ,137,137,137
BEGIN DESCRIPTION:
Walnut17 2.0
END DESCRIPTION:
XS GIS Cut Line= 3
      2742226.02      6752410.98      2741978.76      6752766.42
      2741852.52      6753157.78
#Sta/Elev= 30
    4605  351.75  4641.6  349.24  4654.3  347.64  4719.8  342.49  4791.4     336
  4835.9  331.45  4848.7  329.18  4856.8   328.8  4862.9  327.09  4892.6   325.5
  4898.7  323.97  4907.5  323.56  4913.6   322.6  4934.5  321.83  4964.2  321.82
  4985.1  320.86  5066.2  321.34  5105.8   322.4  5114.4  318.21  5114.6  317.71
  5118.1  317.71  5118.4  318.21    5125  321.03  5130.3   320.8  5137.4  321.71
  5194.4  321.53  5284.5  324.72  5322.5  328.56  5359.8  330.42  5449.2  336.64
#Mann= 3 ,-1 , 0
    4605     .05       0  5114.4     .05       0  5118.4     .05       0
Bank Sta=5114.4,5118.4
XS Rating Curve= 0 ,0
Exp/Cntr=0.3,0.1

Type RM Length L Ch R = 1 ,685     ,278,278,278
BEGIN DESCRIPTION:
Walnut17 1.8
END DESCRIPTION:
XS GIS Cut Line= 4
      2742019.33      6752463.39      2741904.78      6752593.56
      2741883.94      6752704.24      2741764.15      6753031.06
#Sta/Elev= 30
  4758.5  336.12  4787.4  334.68  4801.7  332.67  4815.9   331.8  4822.5  329.66
  4844.3  327.16    4851   325.3  4907.9     325  4915.2   325.5  4922.2  328.26
  4939.5  328.73  4948.4  325.89  4953.5  325.33  4959.8  323.27    4970   321.6
  4980.2  320.88    5006  320.44  5080.2  320.68  5179.5  321.67  5196.9  316.25
  5200.3  316.17  5200.5  315.67    5204  315.67  5204.3  316.17  5222.1  320.88
  5313.6  323.86  5344.1  323.69  5374.6  325.12  5389.1  326.72  5392.6  326.77
#Mann= 4 ,-1 , 0
  4758.5     .05       0  5200.3     .05       0  5204.3     .05       0
  5389.1     .12       0
Bank Sta=5200.3,5204.3
XS Rating Curve= 0 ,0
Exp/Cntr=0.3,0.1

Type RM Length L Ch R = 1 ,407     ,225,225,225
BEGIN DESCRIPTION:
Walnut17 1.5
END DESCRIPTION:
XS GIS Cut Line= 3
      2741863.12      6752412.56      2741637.85      6752765.44
      2741589.72      6752802.17
#Sta/Elev= 30
  4611.5  333.63  4615.5  333.61  4621.5  332.12  4630.7  330.95  4636.7  330.94
  4645.2  328.23  4667.1   328.1  4724.7   323.5  4824.5  320.25  4846.9  320.73
  4876.1  320.55    4892  319.94  4927.6  319.79  4933.6  316.33  4941.8  314.13
  4948.9  318.29  4954.8  320.11  4985.2  319.53  4991.2   318.2  5000.5  318.62
  5006.4  316.49    5011  312.01  5011.3  311.51  5014.8  311.51    5015  312.01
  5021.6  312.48  5027.2  315.24  5034.9  314.58  5043.2     321  5090.7  320.26
#Mann= 5 ,-1 , 0
  4611.5     .05       0    4892     .12       0  4927.6      .1       0
    5011     .05       0    5015      .1       0
Bank Sta=5011,5015
XS Rating Curve= 0 ,0
Exp/Cntr=0.3,0.1

Type RM Length L Ch R = 1 ,182     ,151,151,151
BEGIN DESCRIPTION:
Walnut17 1.0
END DESCRIPTION:
XS GIS Cut Line= 3
      2741754.67      6752356.28      2741488.18      6752598.72
      2741488.11      6752657.95
#Sta/Elev= 30
  4697.1  332.89    4721  331.34  4727.8   330.5  4735.2  330.36  4741.9  329.34
  4784.5  327.28  4805.5  325.32  4827.1  323.95  4882.9  321.78  4904.8  320.72
  4954.1  319.06  4961.5  317.25  4968.3  318.55  4975.7  317.37  4982.5  317.65
  4989.9  316.24  4996.7  316.47  5004.1  315.43  5010.9  316.53  5018.3  314.13
  5024.7  313.16  5025.1   313.1  5030.5  308.69  5030.7  308.19  5034.2  308.19
  5034.5  308.69  5039.3  313.18  5046.7  319.22  5055.5     320  5116.6  319.45
#Mann= 5 ,-1 , 0
  4697.1     .05       0  4882.9     .12       0  5024.7      .1       0
  5030.5     .05       0  5034.5      .1       0
Bank Sta=5030.5,5034.5
XS Rating Curve= 0 ,0
Exp/Cntr=0.3,0.1

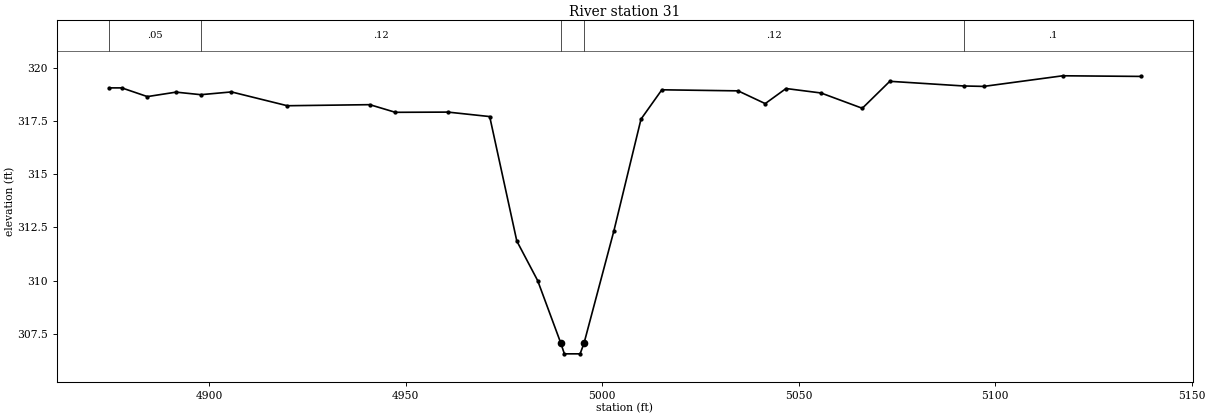
Type RM Length L Ch R = 1 ,31      ,0,0,0
BEGIN DESCRIPTION:
Walnut17 0.3
END DESCRIPTION:
XS GIS Cut Line= 4
      2741485.52      6752386.52      2741432.12      6752442.52
      2741473.79      6752567.52      2741471.18      6752620.92
#Sta/Elev= 30
  4874.5  319.07  4877.8  319.07  4884.3  318.66  4891.6  318.87  4897.9  318.75
  4905.7  318.88  4919.9  318.23  4940.9  318.28  4947.4  317.92  4960.8  317.93
  4971.4  317.72  4978.3  311.86  4983.6     310  4989.5  307.05  4990.4  306.55
  4994.4  306.55  4995.4  307.05    5003  312.34  5009.9   317.6  5015.2  318.98
  5034.6  318.93  5041.5  318.33  5046.8  319.04  5055.7  318.83  5066.2  318.11
  5073.2  319.38    5092  319.16  5097.1  319.14  5117.2  319.64  5137.1  319.61
#Mann= 5 ,-1 , 0
  4874.5     .05       0  4897.9     .12       0  4989.5     .05       0
  4995.4     .12       0    5092      .1       0
Bank Sta=4989.5,4995.4
XS Rating Curve= 0 ,0
Exp/Cntr=0.3,0.1

Chan Stop Cuts=-1
Use User Specified Reach Order=0
Composite Channel Slope=5