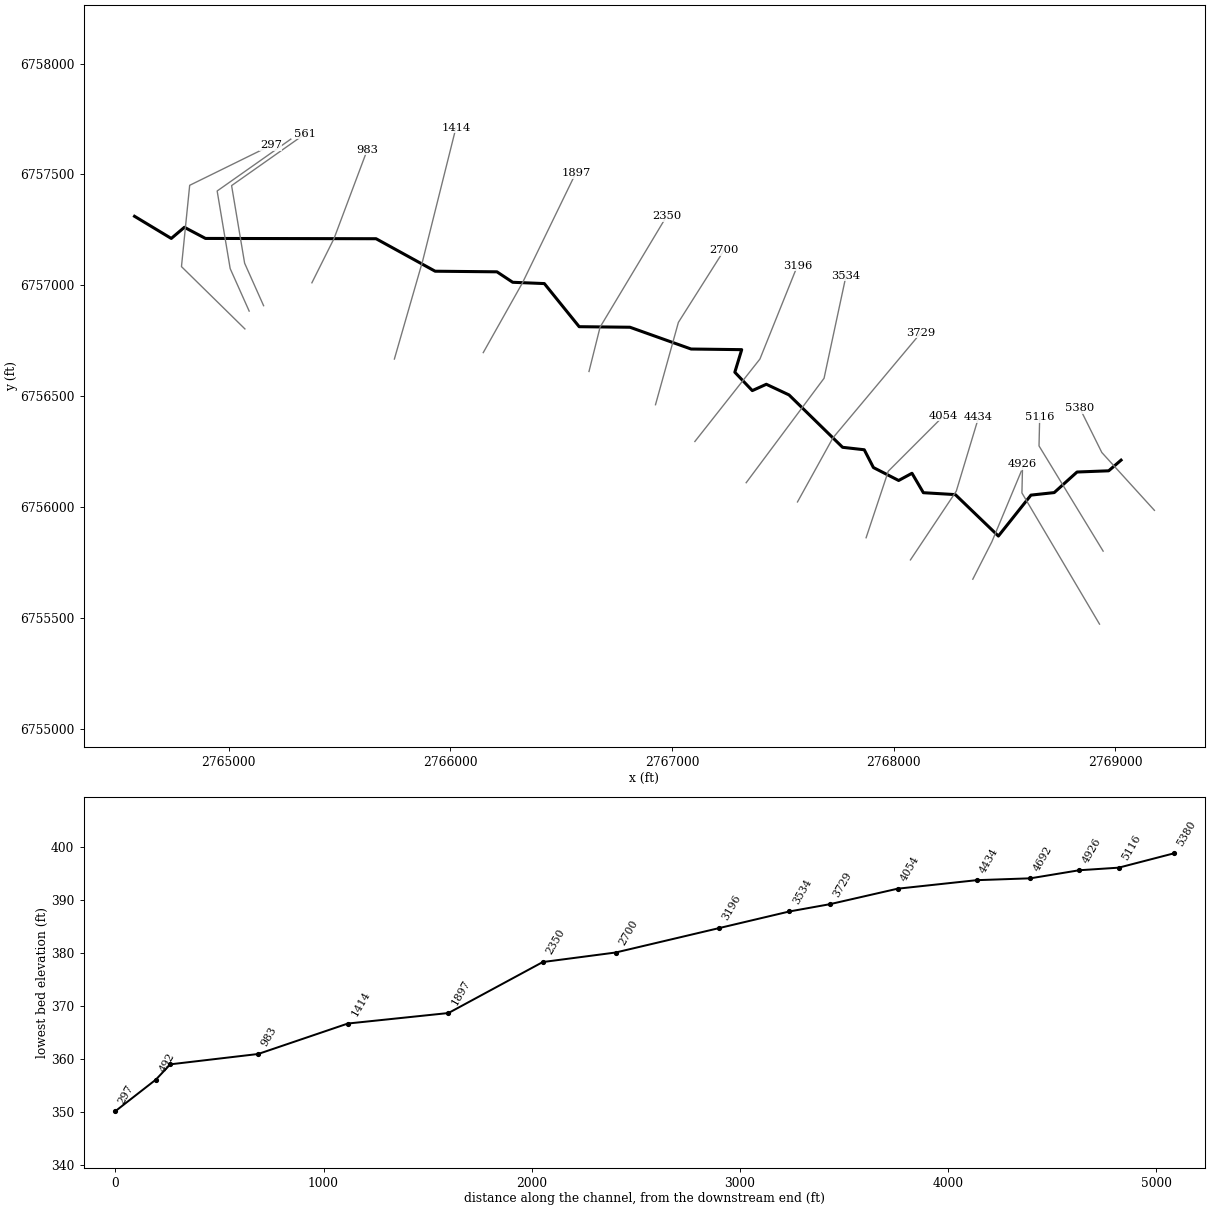
--- Walnut19.prj (project) ---

Proj Title=Walnut19 Base Level Engineering
Current Plan=p01
Default Exp/Contr=0.3,0.1
English Units
Geom File=g01
Flow File=f01
Plan File=p01
Y Axis Title=Elevation
X Axis Title(PF)=Main Channel Distance
X Axis Title(XS)=Station
BEGIN DESCRIPTION:
Walnut19
END DESCRIPTION:
DSS Export Rating Curves= 0
DSS Export Rating Curve Sorted= 0
DSS Export Volume Flow Curves= 0
DXF OffsetX= 0
DXF OffsetY= 0
DXF ScaleX= 1
DXF ScaleY= 10

--- Walnut19.p01 (plan) ---

Plan Title=Multiple Run
Program Version=4.10
Short Identifier=Multiple
Geom File=g01
Flow File=f01
Subcritical Flow
K Sum by GR= 0
Std Step Tol= 0.01
Critical Tol= 0.01
Num of Std Step Trials= 20
Max Error Tol= 0.3
Flow Tol Ratio= 0.001
Split Flow NTrial= 30
Split Flow Tol= 0.02
Split Flow Ratio= 0.02
Log Output Level= 0
Friction Slope Method= 1
Unsteady Friction Slope Method= 2
Unsteady Bridges Friction Slope Method= 1
Parabolic Critical Depth
Global Vel Dist= 1 , 1 , 1
Global Log Level= 0
CheckData=True
Encroach Param=-1 ,0,0, 0
BEGIN DESCRIPTION:
Multiple Run
END DESCRIPTION:
Computation Interval=1HOUR
Output Interval=1HOUR
Run HTab= 0
Run UNet= 0
Run PostProcess= 0
Run WQNet= 0
UNET Theta= 1
UNET Theta Warmup= 1
UNET ZTol= 0.02
UNET ZSATol= 0.05
UNET MxIter= 20
UNET MaxInSteps= 0
UNET DtIC= 0
UNET DtMin= 0
UNET MaxCRTS= 20
UNET WFStab= 2
UNET SFStab= 1
UNET WFX= 1
UNET SFX= 1
UNET DSS MLevel= 4
UNET DZMax Abort= 100
UNET Convert EG Bridges= 0
UNET Use Existing IB Tables=-1
UNET Froude Reduction=False
UNET Froude Limit= 1
UNET Froude Power= 10
UNET Time Slicing=0,0, 5
UNET Junction Losses=0
Instantaneous Interval=1HOUR
Write IC File= 0
Write IC File at Sim End=0
Echo Input=False
Echo Parameters=False
Echo Output=False
Write Detailed= 0
WQ AD Non Conservative
WQ ULTIMATE=-1
WQ Max Comp Step=1HOUR
WQ Output Interval=15MIN
WQ Output Selected Increments= 0
WQ Output face flow=0
WQ Output face velocity=0
WQ Output face area=0
WQ Output face dispersion=0
WQ Output cell volume=0
WQ Output cell surface area=0
WQ Output cell continuity=0
WQ Output cumulative cell continuity=0
WQ Output face conc=0
WQ Output face dconc_dx=0
WQ Output face courant=0
WQ Output face peclet=0
WQ Output face adv mass=0
WQ Output face disp mass=0
WQ Output cell mass=0
WQ Output cell source sink temp=0
WQ Output cell source sink nsm=0
WQ Output MaxMinRange=-1
WQ Daily Max Min Mean=-1
WQ Daily Range=0
WQ Daily Time=0
WQ Create Restart=0
WQ Fixed Restart=0
WQ System Summary=0
WQ Use Fixed Temperature=0
Sorting and Armoring Iterations= 10
XS Update Threshold= 0.02
Hydraulics Update Threshold= 0.02
Energy Slope Method= 1
Volume Change Method= 0
XS Weighting Method= 0
Number of US Weighted Cross Sections= 1
Number of DS Weighted Cross Sections= 1
Upstream XS Weight=0.25
Main XS Weight=0.5
Downstream XS Weight=0.25
Number of DS XS's Weighted with US Boundary= 1
Upstream Boundary Weight= 1
Weight of XSs Associated with US Boundary= 0
Number of US XS's Weighted with DS Boundary= 1
Downstream Boundary Weight= 0.5
Weight of XSs Associated with DS Boundary= 0.5
Sediment Output Level= 4
Mass or Volume Output= 0
Output Increment Type= 1
Profile and TS Output Increment= 10
XS Output Flag= 0
XS Output Increment= 10
Disregard all LS=0
Disregard all Conn=0
Disregard all Breaches=0
Disregard all Pumps=0

--- Walnut19.f01 (steady flow) ---

Flow Title=Multiple
Program Version=4.10
Number of Profiles= 7
Profile Names=10-year,25-year,50-year,1pct_min,100-year,1pct_plu,500-year
River Rch & RM=Walnut19,Reach-1         ,5380
     711     985    1216     747    1491    2975    2245
River Rch & RM=Walnut19,Reach-1         ,2700
     854    1194    1484     917    1829    3650    2786
Boundary for River Rch & Prof#=Walnut19,Reach-1         , 1
Up Type= 0
Dn Type= 3
Dn Slope=0.03
Boundary for River Rch & Prof#=Walnut19,Reach-1         , 2
Up Type= 0
Dn Type= 3
Dn Slope=0.03
Boundary for River Rch & Prof#=Walnut19,Reach-1         , 3
Up Type= 0
Dn Type= 3
Dn Slope=0.03
Boundary for River Rch & Prof#=Walnut19,Reach-1         , 4
Up Type= 0
Dn Type= 3
Dn Slope=0.03
Boundary for River Rch & Prof#=Walnut19,Reach-1         , 5
Up Type= 0
Dn Type= 3
Dn Slope=0.03
Boundary for River Rch & Prof#=Walnut19,Reach-1         , 6
Up Type= 0
Dn Type= 3
Dn Slope=0.03
Boundary for River Rch & Prof#=Walnut19,Reach-1         , 7
Up Type= 0
Dn Type= 3
Dn Slope=0.03
DSS Import GetInterval= 0
DSS Import GetPeak= 0
DSS Import FillOption= 0

--- Walnut19.g01 (geometry) ---

Geom Title=Existing Conditions

River Reach=Walnut19,Reach-1
Reach XY= 30
      2769026.00      6756211.00      2768970.21      6756162.91
      2768827.47      6756157.45      2768724.50      6756064.63
      2768619.55      6756053.25      2768472.68      6755868.58
      2768278.44      6756055.53      2768134.31      6756064.13
      2768082.93      6756151.77      2768022.78      6756119.25
      2767908.99      6756177.56      2767867.65      6756257.81
      2767769.88      6756268.88      2767528.29      6756505.19
      2767425.91      6756553.22      2767362.61      6756524.64
      2767283.83      6756607.59      2767314.82      6756709.38
      2767086.50      6756712.22      2766810.78      6756810.48
      2766581.67      6756812.98      2766424.54      6757007.46
      2766281.94      6757013.27      2766210.78      6757060.48
      2765931.93      6757063.24      2765665.50      6757209.80
      2764896.01      6757211.09      2764800.95      6757261.30
      2764741.71      6757211.03      2764576.00      6757311.00

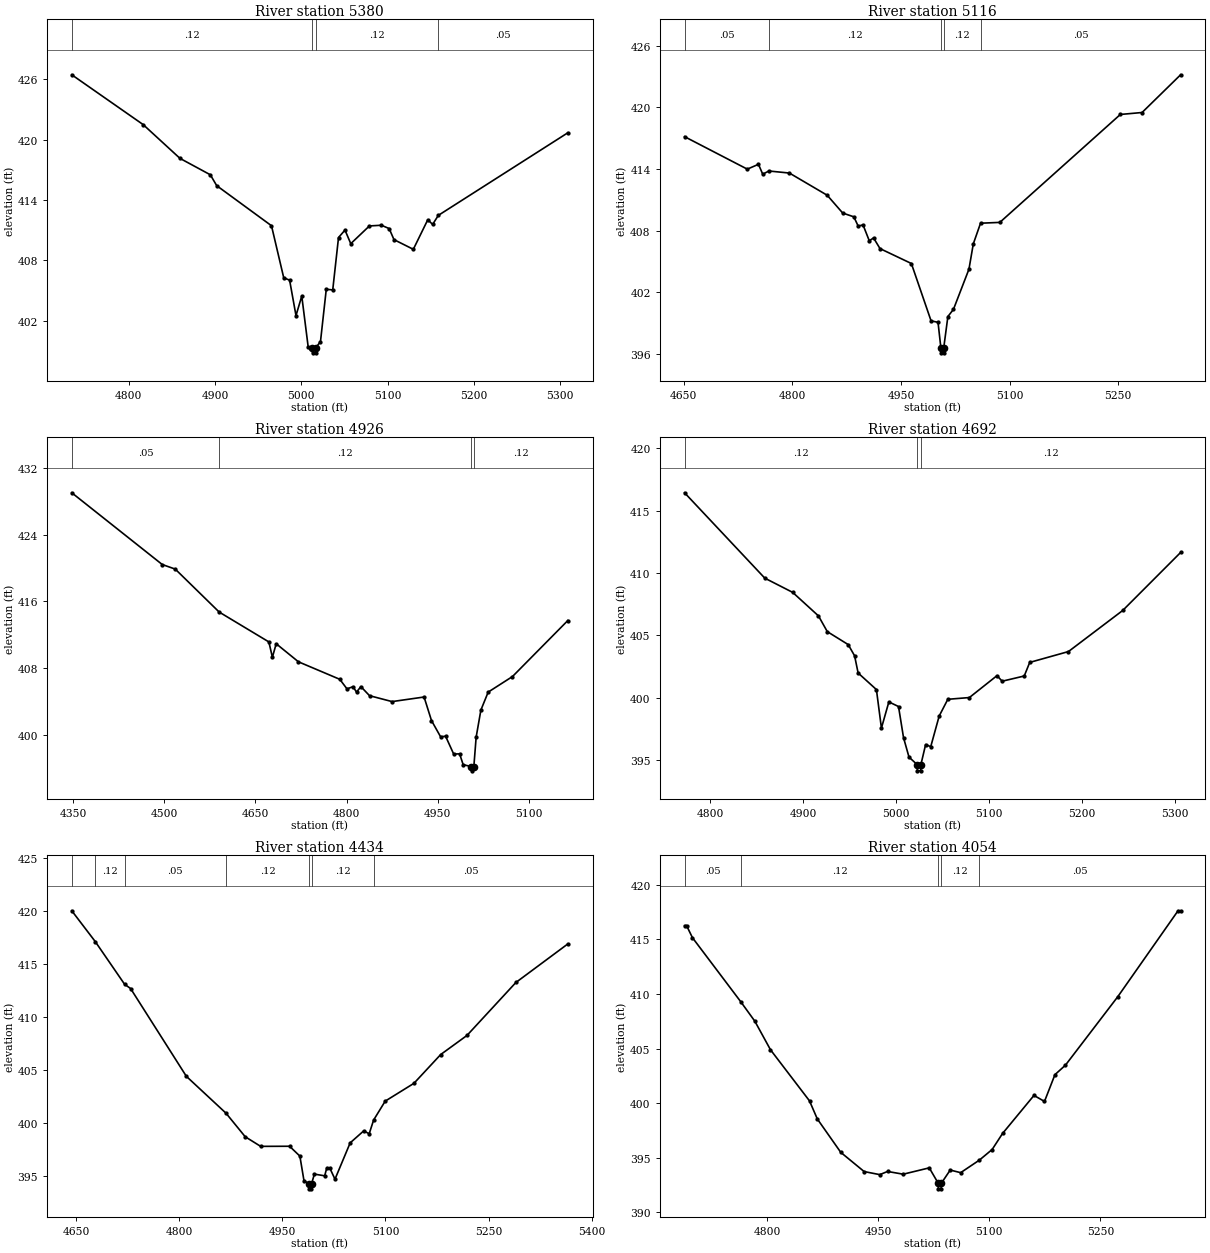
Type RM Length L Ch R = 1,5380,264,264,264
BEGIN DESCRIPTION:
Walnut19 14.0
END DESCRIPTION:
XS GIS Cut Line= 3
      2769176.53      6755984.48      2768939.24      6756245.50
      2768840.44      6756444.57
#Sta/Elev= 30
  4733.9  426.43  4816.7  421.48  4859.3  418.13  4894.5  416.50  4901.9  415.42
  4965.4  411.44  4979.6  406.27  4986.4  406.04  4993.8  402.52  5000.5  404.46
  5008.0  399.36  5012.7  399.32  5013.0  398.82  5016.5  398.82  5016.7  399.32
  5022.2  399.94  5028.9  405.13  5036.4  405.07  5043.1  410.27  5050.6  411.01
  5057.3  409.66  5078.9  411.42  5092.8  411.49  5101.8  411.16  5107.4  410.06
  5129.8  409.10  5146.6  412.04  5152.2  411.57  5158.8  412.47  5308.9  420.67
#Mann=4,-1,0
  4733.9    0.12       0  5012.7    0.07       0  5016.7    0.12       0
  5158.8    0.05       0
Bank Sta=5012.7,5016.7
Exp/Cntr=0.3,0.1

Type RM Length L Ch R = 1,5116,190,190,190
BEGIN DESCRIPTION:
Walnut19 13.0
END DESCRIPTION:
XS GIS Cut Line= 3
      2768945.17      6755800.60      2768655.98      6756275.16
      2768658.95      6756404.20
#Sta/Elev= 30
  4651.3  417.16  4737.9  414.00  4753.3  414.47  4759.2  413.51  4767.7  413.82
  4796.0  413.62  4848.2  411.46  4869.6  409.73  4885.0  409.36  4890.9  408.47
  4897.7  408.57  4906.3  407.03  4912.2  407.31  4921.1  406.27  4964.4  404.82
  4991.6  399.24  5001.2  399.10  5005.1  396.63  5005.3  396.13  5008.8  396.13
  5009.1  396.63  5014.8  399.66  5022.5  400.36  5043.9  404.27  5049.9  406.73
  5059.9  408.74  5086.5  408.82  5252.9  419.32  5282.9  419.51  5336.1  423.18
#Mann=5,-1,0
  4651.3    0.05       0  4767.7    0.12       0  5005.1    0.07       0
  5009.1    0.12       0  5059.9    0.05       0
Bank Sta=5005.1,5009.1
Exp/Cntr=0.3,0.1

Type RM Length L Ch R = 1,4926,234,234,234
BEGIN DESCRIPTION:
Walnut19 12.0
END DESCRIPTION:
XS GIS Cut Line= 3
      2768928.86      6755471.37      2768578.86      6756063.09
      2768581.83      6756192.08
#Sta/Elev= 30
  4347.7  429.05  4496.6  420.43  4518.0  419.88  4590.3  414.72  4672.1  411.13
  4677.9  409.29  4684.2  410.91  4720.8  408.74  4788.8  406.64  4800.7  405.49
  4810.6  405.75  4816.4  405.10  4823.6  405.76  4837.8  404.67  4874.9  403.96
  4927.6  404.51  4939.8  401.68  4954.8  399.73  4963.0  399.80  4976.3  397.66
  4986.1  397.68  4991.9  396.39  5005.5  396.14  5005.8  395.64  5009.5  396.14
  5013.3  399.68  5021.1  402.94  5033.1  405.10  5073.1  406.97  5164.2  413.70
#Mann=4,-1,0
  4347.7    0.05       0  4590.3    0.12       0  5005.5    0.07       0
  5009.5    0.12       0
Bank Sta=5005.5,5009.5
Exp/Cntr=0.3,0.1

Type RM Length L Ch R = 1,4692,258,258,258
BEGIN DESCRIPTION:
Walnut19 11.0
END DESCRIPTION:
XS GIS Cut Line= 3
      2768357.26      6755674.03      2768443.34      6755842.87
      2768576.00      6756161.00
#Sta/Elev= 30
  4772.1  416.43  4858.5  409.58  4888.5  408.44  4916.3  406.55  4925.8  405.29
  4948.3  404.25  4955.2  403.35  4959.0  401.97  4978.7  400.64  4984.1  397.55
  4992.1  399.65  5002.5  399.28  5007.9  396.78  5013.8  395.22  5022.6  394.62
  5022.8  394.12  5026.3  394.12  5026.6  394.62  5031.7  396.23  5037.2  396.06
  5046.3  398.52  5055.6  399.86  5078.8  400.00  5108.6  401.76  5114.1  401.31
  5137.9  401.73  5143.8  402.82  5185.5  403.69  5244.0  406.99  5306.3  411.64
#Mann=3,-1,0
  4772.1    0.12       0  5022.6    0.07       0  5026.6    0.12       0
Bank Sta=5022.6,5026.6
Exp/Cntr=0.3,0.1

Type RM Length L Ch R = 1,4434,380,380,380
BEGIN DESCRIPTION:
Walnut19 10.0
END DESCRIPTION:
XS GIS Cut Line= 3
      2768075.99      6755760.99      2768282.82      6756071.23
      2768383.75      6756405.46
#Sta/Elev= 30
  4643.4  420.02  4677.6  417.11  4720.3  413.08  4729.0  412.68  4810.2  404.39
  4867.9  400.91  4895.8  398.69  4918.3  397.78  4960.4  397.79  4975.4  396.86
  4981.4  394.53  4988.5  394.27  4988.7  393.77  4992.2  393.77  4992.5  394.27
  4996.5  395.16  5011.5  395.00  5014.6  395.75  5018.8  395.75  5026.5  394.68
  5048.6  398.11  5068.3  399.24  5076.3  398.97  5082.7  400.26  5099.6  402.05
  5141.4  403.73  5180.4  406.45  5218.6  408.25  5289.8  413.25  5365.4  416.89
#Mann=7,-1,0
  4643.4    0.05       0  4677.6    0.12       0  4720.3    0.05       0
  4867.9    0.12       0  4988.5    0.07       0  4992.5    0.12       0
  5082.7    0.05       0
Bank Sta=4988.5,4992.5
Exp/Cntr=0.3,0.1

Type RM Length L Ch R = 1,4054,325,325,325
BEGIN DESCRIPTION:
Walnut19 9.0
END DESCRIPTION:
XS GIS Cut Line= 3
      2767875.98      6755860.95      2767976.00      6756161.00
      2768225.98      6756410.98
#Sta/Elev= 30
  4688.5  416.25  4691.2  416.25  4699.1  415.15  4764.2  409.30  4783.4  407.50
  4804.5  404.89  4857.2  400.21  4867.7  398.56  4899.4  395.50  4931.0  393.74
  4952.1  393.46  4962.6  393.75  4983.7  393.50  5018.9  394.08  5031.1  392.66
  5031.3  392.16  5034.8  392.16  5035.1  392.66  5047.2  393.88  5061.3  393.64
  5086.6  394.79  5103.8  395.76  5117.9  397.23  5160.3  400.71  5174.5  400.16
  5188.6  402.61  5202.8  403.48  5273.5  409.75  5354.8  417.61  5358.3  417.61
#Mann=5,-1,0
  4688.5    0.05       0  4764.2    0.12       0  5031.1    0.07       0
  5035.1    0.12       0  5086.6    0.05       0
Bank Sta=5031.1,5035.1
Exp/Cntr=0.3,0.1

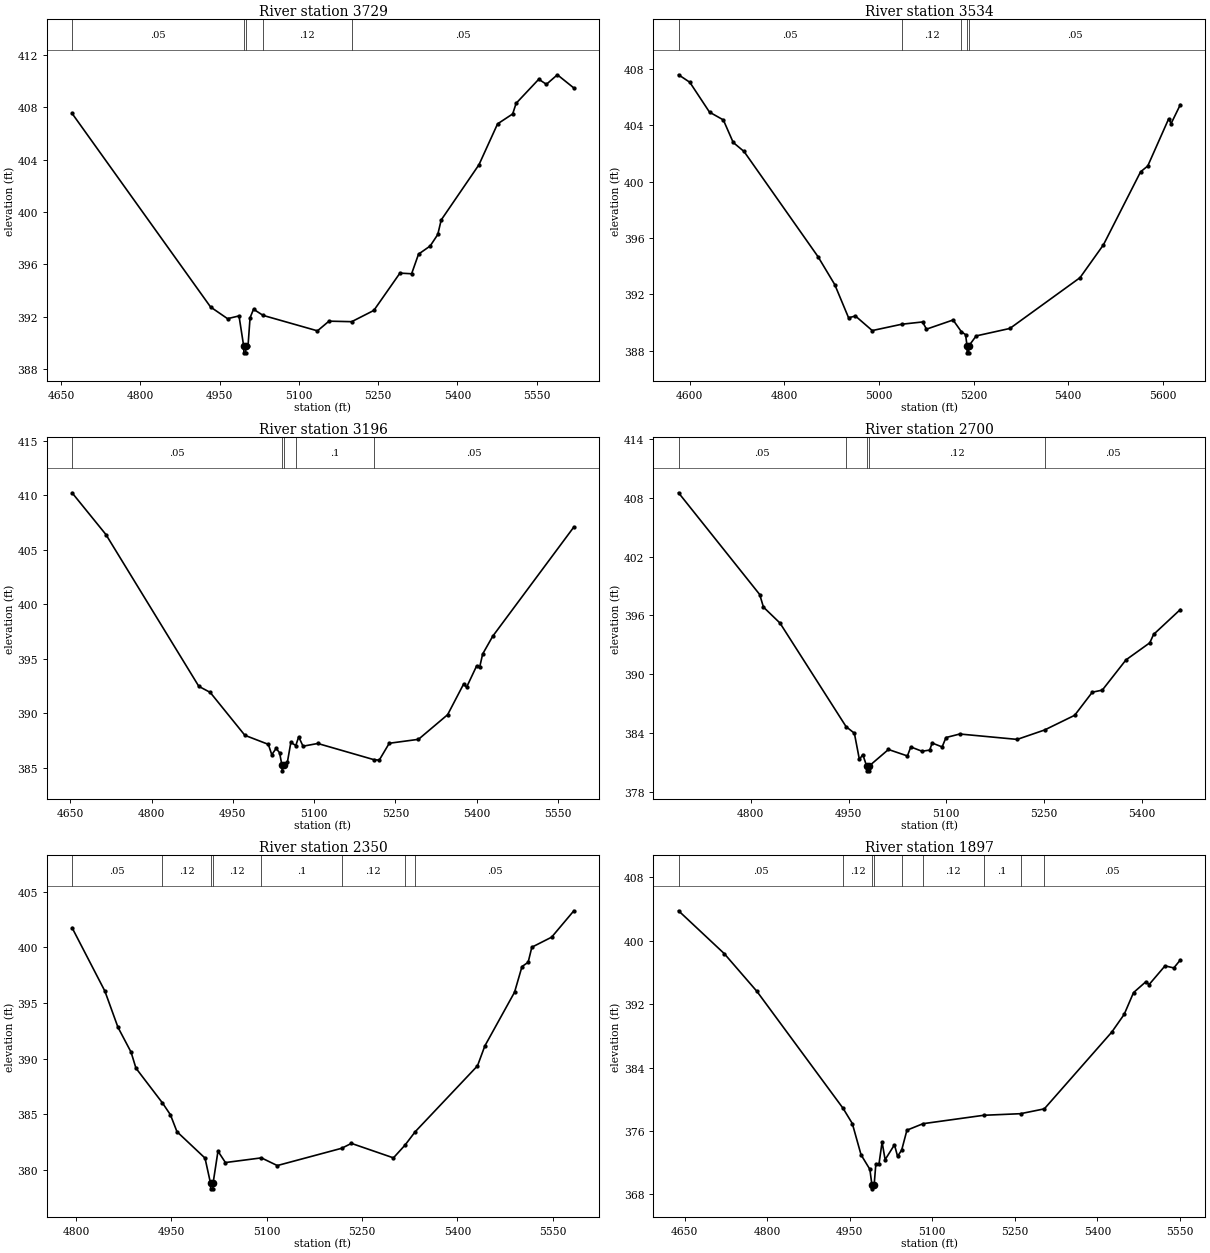
Type RM Length L Ch R = 1,3729,195,195,195
BEGIN DESCRIPTION:
Walnut19 8.0
END DESCRIPTION:
XS GIS Cut Line= 3
      2767566.44      6756022.39      2767726.00      6756311.00
      2768123.95      6756786.46
#Sta/Elev= 30
  4670.5  407.53  4932.7  392.74  4964.8  391.85  4986.5  392.06  4995.4  389.74
  4995.7  389.24  4999.2  389.24  4999.4  389.74  5003.5  389.74  5007.4  391.92
  5014.0  392.57  5032.1  392.10  5135.0  390.92  5156.8  391.66  5199.8  391.62
  5241.7  392.48  5291.1  395.33  5313.2  395.28  5326.3  396.78  5348.3  397.40
  5362.7  398.28  5369.2  399.39  5440.7  403.61  5475.9  406.73  5504.5  407.49
  5511.0  408.30  5553.9  410.14  5568.3  409.75  5589.1  410.48  5620.3  409.47
#Mann=5,-1,0
  4670.5    0.05       0  4995.4    0.04       0  4999.4    0.05       0
  5032.1    0.12       0  5199.8    0.05       0
Bank Sta=4995.4,4999.4
Exp/Cntr=0.3,0.1

Type RM Length L Ch R = 1,3534,338,338,338
BEGIN DESCRIPTION:
Walnut19 7.0
END DESCRIPTION:
XS GIS Cut Line= 3
      2767335.03      6756109.20      2767686.30      6756580.31
      2767785.48      6757043.15
#Sta/Elev= 30
  4576.3  407.58  4600.1  407.05  4641.8  404.93  4671.0  404.38  4691.9  402.78
  4714.8  402.14  4871.2  394.68  4906.6  392.70  4935.8  390.35  4950.4  390.47
  4985.9  389.44  5048.5  389.89  5092.2  390.05  5100.6  389.54  5156.8  390.19
  5174.3  389.36  5183.2  389.15  5186.3  388.36  5186.5  387.86  5190.0  387.86
  5190.3  388.36  5205.6  389.06  5276.9  389.59  5425.2  393.19  5474.7  395.52
  5553.3  400.70  5568.4  401.11  5612.7  404.46  5617.8  404.12  5637.3  405.46
#Mann=5,-1,0
  4576.3    0.05       0  5048.5    0.12       0  5174.3    0.05       0
  5186.3    0.04       0  5190.3    0.05       0
Bank Sta=5186.3,5190.3
Exp/Cntr=0.3,0.1

Type RM Length L Ch R = 1,3196,496,496,496
BEGIN DESCRIPTION:
Walnut19 6.0
END DESCRIPTION:
XS GIS Cut Line= 3
      2767103.62      6756295.17      2767397.03      6756667.10
      2767565.93      6757087.29
#Sta/Elev= 30
  4653.1  410.23  4715.6  406.40  4887.2  392.47  4908.1  391.92  4972.2  387.98
  5015.5  387.15  5021.9  386.20  5029.9  386.78  5036.3  386.38  5040.7  385.22
  5040.9  384.72  5044.7  385.22  5050.8  385.54  5057.1  387.33  5066.2  387.04
  5071.6  387.84  5079.6  386.98  5106.8  387.23  5210.1  385.75  5220.3  385.70
  5238.8  387.25  5292.7  387.61  5346.6  389.87  5376.2  392.69  5381.6  392.39
  5400.3  394.36  5405.7  394.22  5411.3  395.44  5429.9  397.07  5579.7  407.09
#Mann=5,-1,0
  4653.1    0.05       0  5040.7    0.04       0  5044.7    0.05       0
  5066.2     0.1       0  5210.1    0.05       0
Bank Sta=5040.7,5044.7
Exp/Cntr=0.3,0.1

Type RM Length L Ch R = 1,2700,350,350,350
BEGIN DESCRIPTION:
Walnut19 5.0
END DESCRIPTION:
XS GIS Cut Line= 3
      2766925.99      6756460.96      2767029.23      6756832.40
      2767234.95      6757157.45
#Sta/Elev= 30
  4689.0  408.51  4813.6  398.12  4819.3  396.84  4844.7  395.21  4946.2  384.63
  4958.9  383.96  4966.6  381.28  4971.8  381.78  4977.7  380.62  4977.9  380.12
  4981.4  380.12  4981.7  380.62  5011.2  382.30  5040.3  381.64  5045.5  382.56
  5062.7  382.12  5074.5  382.24  5078.3  382.96  5093.6  382.56  5099.5  383.52
  5120.7  383.88  5208.8  383.33  5250.8  384.29  5297.0  385.79  5324.1  388.15
  5339.4  388.36  5375.8  391.45  5412.3  393.19  5418.2  394.05  5459.2  396.59
#Mann=5,-1,0
  4689.0    0.05       0  4946.2    0.12       0  4977.7    0.07       0
  4981.7    0.12       0  5250.8    0.05       0
Bank Sta=4977.7,4981.7
Exp/Cntr=0.3,0.1

Type RM Length L Ch R = 1,2350,453,453,453
BEGIN DESCRIPTION:
Walnut19 4.0
END DESCRIPTION:
XS GIS Cut Line= 3
      2766625.99      6756610.96      2766676.00      6756811.00
      2766976.00      6757311.01
#Sta/Elev= 30
  4793.9  401.76  4845.5  396.07  4866.1  392.82  4886.7  390.59  4894.4  389.15
  4936.1  386.03  4948.6  384.97  4958.9  383.45  5003.0  381.08  5011.7  378.82
  5012.0  378.32  5015.5  378.32  5015.7  378.82  5023.4  381.70  5035.1  380.68
  5091.7  381.10  5116.7  380.41  5217.9  381.96  5233.3  382.40  5299.4  381.10
  5317.4  382.23  5333.7  383.45  5431.6  389.36  5443.2  391.15  5489.9  395.97
  5501.6  398.27  5511.3  398.66  5517.1  400.01  5548.2  400.91  5583.2  403.28
#Mann=8,-1,0
  4793.9    0.05       0  4936.1    0.12       0  5011.7    0.07       0
  5015.7    0.12       0  5091.7     0.1       0  5217.9    0.12       0
  5317.4     0.1       0  5333.7    0.05       0
Bank Sta=5011.7,5015.7
Exp/Cntr=0.3,0.1

Type RM Length L Ch R = 1,1897,483,483,483
BEGIN DESCRIPTION:
Walnut19 3.0
END DESCRIPTION:
XS GIS Cut Line= 3
      2766149.01      6756696.05      2766326.00      6757011.00
      2766566.40      6757506.04
#Sta/Elev= 30
  4639.1  403.78  4722.1  398.38  4781.4  393.62  4938.1  378.85  4954.8  376.94
  4970.7  372.99  4986.7  371.16  4990.4  369.20  4990.7  368.70  4994.5  369.20
  4997.5  371.81  5003.2  371.81  5008.9  374.60  5014.4  372.38  5031.4  374.26
  5037.0  372.80  5044.5  373.59  5054.0  376.10  5083.3  376.92  5193.5  377.98
  5260.4  378.18  5303.6  378.79  5426.1  388.47  5448.7  390.71  5465.7  393.46
  5488.3  394.84  5493.8  394.46  5522.9  396.83  5538.9  396.57  5550.7  397.58
#Mann=9,-1,0
  4639.1    0.05       0  4938.1    0.12       0  4990.4    0.07       0
  4994.5    0.12       0  5044.5     0.1       0  5083.3    0.12       0
  5193.5     0.1       0  5260.4    0.12       0  5303.6    0.05       0
Bank Sta=4990.4,4994.5
Exp/Cntr=0.3,0.1

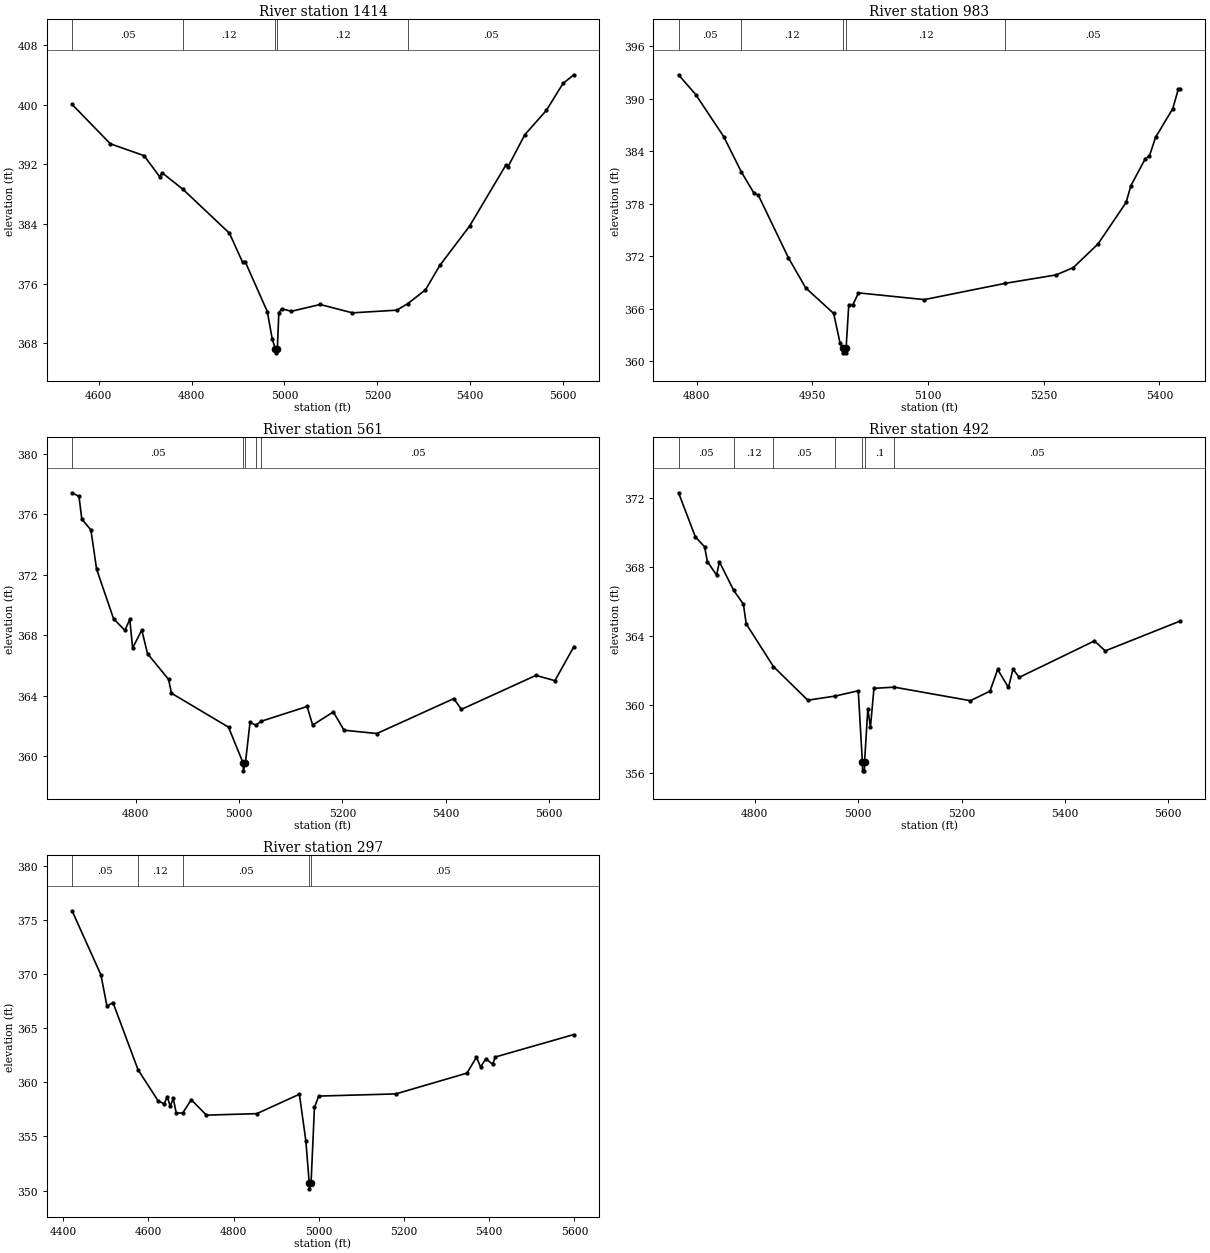
Type RM Length L Ch R = 1,1414,431,431,431
BEGIN DESCRIPTION:
Walnut19 2.0
END DESCRIPTION:
XS GIS Cut Line= 3
      2765748.12      6756667.05      2765876.00      6757111.00
      2766026.01      6757711.03
#Sta/Elev= 30
  4542.6  400.02  4625.0  394.74  4697.6  393.15  4731.2  390.33  4736.4  390.86
  4781.2  388.65  4881.5  382.75  4910.0  378.83  4915.2  378.96  4963.0  372.25
  4973.4  368.64  4980.5  367.22  4980.8  366.72  4984.6  367.22  4987.8  372.11
  4994.2  372.62  5014.9  372.29  5076.8  373.20  5146.3  372.08  5241.7  372.44
  5265.6  373.32  5303.5  375.16  5334.4  378.43  5398.9  383.74  5476.2  391.84
  5481.3  391.66  5517.4  395.95  5563.8  399.21  5599.9  402.84  5623.1  403.99
#Mann=5,-1,0
  4542.6    0.05       0  4781.2    0.12       0  4980.5    0.07       0
  4984.6    0.12       0  5265.6    0.05       0
Bank Sta=4980.5,4984.6
Exp/Cntr=0.3,0.1

Type RM Length L Ch R = 1,983,422,422,422
BEGIN DESCRIPTION:
Walnut19 1.0
END DESCRIPTION:
XS GIS Cut Line= 3
      2765376.01      6757011.02      2765476.00      6757211.00
      2765626.01      6757611.02
#Sta/Elev= 30
  4776.4  392.73  4798.7  390.47  4835.1  385.65  4857.9  381.63  4874.2  379.21
  4879.8  378.99  4918.9  371.83  4941.3  368.39  4977.6  365.47  4986.0  362.05
  4989.5  361.47  4989.8  360.97  4993.3  360.97  4993.7  361.47  4997.2  366.47
  5002.6  366.47  5009.8  367.82  5095.2  367.05  5200.2  368.91  5266.1  369.87
  5288.3  370.70  5320.4  373.40  5356.9  378.15  5363.1  380.07  5381.8  383.15
  5387.1  383.45  5395.1  385.59  5417.4  388.86  5424.5  391.06  5427.2  391.06
#Mann=5,-1,0
  4776.4    0.05       0  4857.9    0.12       0  4989.5    0.07       0
  4993.7    0.12       0  5200.2    0.05       0
Bank Sta=4989.5,4993.7
Exp/Cntr=0.3,0.1

Type RM Length L Ch R = 1,561,69,69,69
BEGIN DESCRIPTION:
Walnut19 0.5
END DESCRIPTION:
XS GIS Cut Line= 4
      2765158.19      6756907.70      2765072.60      6757099.32
      2765013.83      6757449.39      2765346.05      6757683.22
#Sta/Elev= 30
  4676.9  377.43  4690.3  377.19  4695.7  375.70  4713.4  374.96  4724.4  372.37
  4757.2  369.09  4779.1  368.32  4788.6  369.05  4794.1  367.15  4811.8  368.34
  4822.9  366.78  4863.7  365.07  4869.2  364.16  4979.7  361.91  5008.1  359.52
  5008.4  359.02  5012.3  359.52  5021.3  362.24  5032.3  362.04  5042.7  362.30
  5131.8  363.28  5142.5  362.05  5182.5  362.92  5203.2  361.71  5266.7  361.49
  5415.6  363.80  5430.4  363.09  5574.6  365.34  5611.3  364.99  5648.0  367.24
#Mann=5,-1,0
  4676.9    0.05       0  5008.1    0.04       0  5012.3    0.05       0
  5032.3     0.1       0  5042.7    0.05       0
Bank Sta=5008.1,5012.3
Exp/Cntr=0.3,0.1

Type RM Length L Ch R = 1,492,195,195,195
BEGIN DESCRIPTION:
Walnut19 0.3
END DESCRIPTION:
XS GIS Cut Line= 4
      2765093.05      6756883.38      2765007.44      6757075.04
      2764948.67      6757425.12      2765280.85      6757658.92
#Sta/Elev= 30
  4652.3  372.32  4684.9  369.75  4702.7  369.18  4708.2  368.31  4725.9  367.53
  4731.4  368.30  4759.1  366.64  4777.8  365.84  4783.3  364.69  4835.9  362.21
  4902.4  360.25  4955.2  360.49  5000.1  360.80  5008.1  356.64  5008.5  356.14
  5012.0  356.14  5012.3  356.64  5018.6  359.75  5023.7  358.69  5030.5  360.94
  5069.8  361.01  5217.2  360.22  5255.1  360.78  5269.9  362.04  5290.8  360.99
  5299.5  362.06  5311.7  361.58  5457.2  363.70  5478.1  363.12  5623.4  364.86
#Mann=7,-1,0
  4652.3    0.05       0  4759.1    0.12       0  4835.9    0.05       0
  4955.2     0.1       0  5008.1    0.07       0  5012.3     0.1       0
  5069.8    0.05       0
Bank Sta=5008.1,5012.3
Exp/Cntr=0.3,0.1

Type RM Length L Ch R = 1,297,0,0,0
BEGIN DESCRIPTION:
Walnut19 0.2
END DESCRIPTION:
XS GIS Cut Line= 4
      2765073.86      6756802.92      2764787.69      6757083.98
      2764824.74      6757450.67      2765191.23      6757630.72
#Sta/Elev= 30
  4420.7  375.83  4488.5  369.91  4502.6  367.03  4516.8  367.35  4575.7  361.15
  4622.9  358.28  4637.1  358.01  4644.1  358.68  4651.2  357.78  4658.2  358.53
  4665.3  357.15  4680.6  357.18  4700.6  358.39  4736.1  356.97  4854.4  357.11
  4954.4  358.90  4969.6  354.57  4977.5  350.67  4977.9  350.17  4981.7  350.67
  4989.7  357.68  4999.7  358.73  5180.6  358.93  5347.8  360.85  5370.0  362.32
  5379.7  361.42  5392.3  362.18  5407.8  361.67  5414.6  362.34  5598.7  364.41
#Mann=5,-1,0
  4420.7    0.05       0  4575.7    0.12       0  4680.6    0.05       0
  4977.5    0.04       0  4981.7    0.05       0
Bank Sta=4977.5,4981.7
Exp/Cntr=0.3,0.1

Chan Stop Cuts=-1