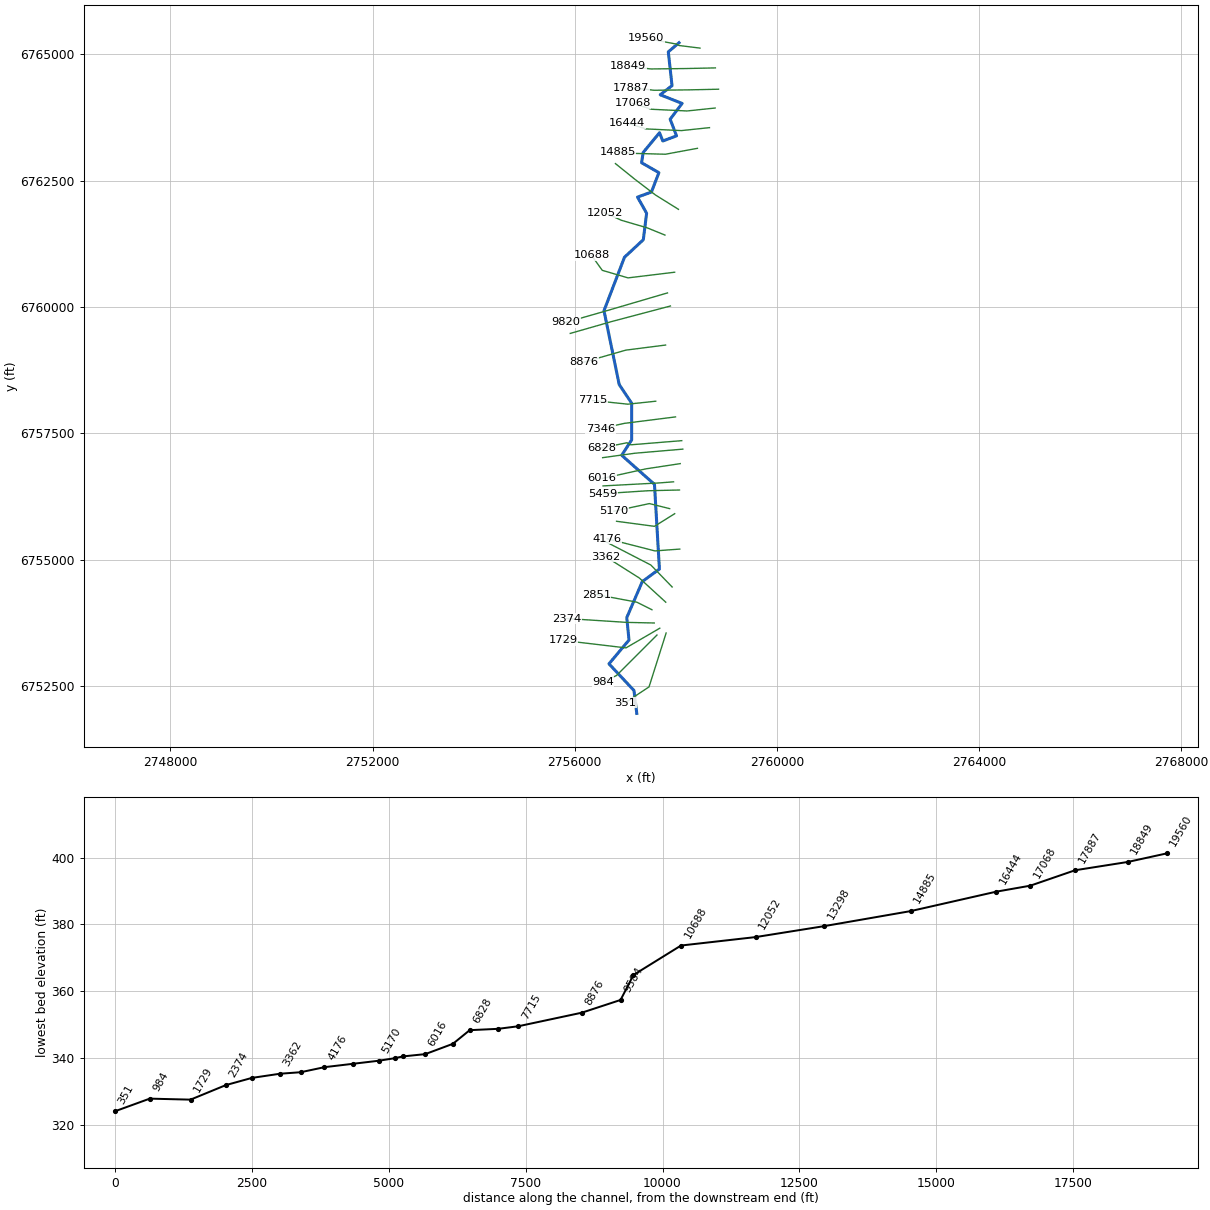
--- Walnut21.prj (project) ---

Proj Title=Walnut21 Base Level Engineering
Current Plan=p01
Default Exp/Contr=0.3,0.1
English Units
Geom File=g01
Flow File=f01
Plan File=p01
Y Axis Title=Elevation
X Axis Title(PF)=Main Channel Distance
X Axis Title(XS)=Station
BEGIN DESCRIPTION:
Walnut21
END DESCRIPTION:
DSS Export Rating Curves= 0
DSS Export Rating Curve Sorted= 0
DSS Export Volume Flow Curves= 0
DXF OffsetX= 0
DXF OffsetY= 0
DXF ScaleX= 1
DXF ScaleY= 10

--- Walnut21.p01 (plan) ---

Plan Title=Multiple Run
Program Version=4.10
Short Identifier=Multiple
Geom File=g01
Flow File=f01
Subcritical Flow
K Sum by GR= 0
Std Step Tol= 0.01
Critical Tol= 0.01
Num of Std Step Trials= 20
Max Error Tol= 0.3
Flow Tol Ratio= 0.001
Split Flow NTrial= 30
Split Flow Tol= 0.02
Split Flow Ratio= 0.02
Log Output Level= 0
Friction Slope Method= 1
Unsteady Friction Slope Method= 2
Unsteady Bridges Friction Slope Method= 1
Parabolic Critical Depth
Global Vel Dist= 1 , 1 , 1
Global Log Level= 0
CheckData=True
Encroach Param=-1 ,0,0, 0
BEGIN DESCRIPTION:
Multiple Run
END DESCRIPTION:
Computation Interval=1HOUR
Output Interval=1HOUR
Run HTab= 0
Run UNet= 0
Run PostProcess= 0
Run WQNet= 0
UNET Theta= 1
UNET Theta Warmup= 1
UNET ZTol= 0.02
UNET ZSATol= 0.05
UNET MxIter= 20
UNET MaxInSteps= 0
UNET DtIC= 0
UNET DtMin= 0
UNET MaxCRTS= 20
UNET WFStab= 2
UNET SFStab= 1
UNET WFX= 1
UNET SFX= 1
UNET DSS MLevel= 4
UNET DZMax Abort= 100
UNET Convert EG Bridges= 0
UNET Use Existing IB Tables=-1
UNET Froude Reduction=False
UNET Froude Limit= 1
UNET Froude Power= 10
UNET Time Slicing=0,0, 5
UNET Junction Losses=0
Instantaneous Interval=1HOUR
Write IC File= 0
Write IC File at Sim End=0
Echo Input=False
Echo Parameters=False
Echo Output=False
Write Detailed= 0
WQ AD Non Conservative
WQ ULTIMATE=-1
WQ Max Comp Step=1HOUR
WQ Output Interval=15MIN
WQ Output Selected Increments= 0
WQ Output face flow=0
WQ Output face velocity=0
WQ Output face area=0
WQ Output face dispersion=0
WQ Output cell volume=0
WQ Output cell surface area=0
WQ Output cell continuity=0
WQ Output cumulative cell continuity=0
WQ Output face conc=0
WQ Output face dconc_dx=0
WQ Output face courant=0
WQ Output face peclet=0
WQ Output face adv mass=0
WQ Output face disp mass=0
WQ Output cell mass=0
WQ Output cell source sink temp=0
WQ Output cell source sink nsm=0
WQ Output MaxMinRange=-1
WQ Daily Max Min Mean=-1
WQ Daily Range=0
WQ Daily Time=0
WQ Create Restart=0
WQ Fixed Restart=0
WQ System Summary=0
WQ Use Fixed Temperature=0
Sorting and Armoring Iterations= 10
XS Update Threshold= 0.02
Hydraulics Update Threshold= 0.02
Energy Slope Method= 1
Volume Change Method= 0
XS Weighting Method= 0
Number of US Weighted Cross Sections= 1
Number of DS Weighted Cross Sections= 1
Upstream XS Weight=0.25
Main XS Weight=0.5
Downstream XS Weight=0.25
Number of DS XS's Weighted with US Boundary= 1
Upstream Boundary Weight= 1
Weight of XSs Associated with US Boundary= 0
Number of US XS's Weighted with DS Boundary= 1
Downstream Boundary Weight= 0.5
Weight of XSs Associated with DS Boundary= 0.5
Sediment Output Level= 4
Mass or Volume Output= 0
Output Increment Type= 1
Profile and TS Output Increment= 10
XS Output Flag= 0
XS Output Increment= 10
Disregard all LS=0
Disregard all Conn=0
Disregard all Breaches=0
Disregard all Pumps=0

--- Walnut21.f01 (steady flow) ---

Flow Title=Multiple
Number of Profiles=7
Profile Names=10-year,25-year,50-year,1pct_min,100-year,1pct_plu,500-year
River Rch & RM= Walnut21,Reach-1,19560
     506     679     820     493     984    1964    1419
River Rch & RM= Walnut21,Reach-1,13298
     758    1041    1277     779    1553    3100    2303
River Rch & RM= Walnut21,Reach-1,9820
    1188    1672    2084    1289    2573    5133    3930
River Rch & RM= Walnut21,Reach-1,7346
    1265    1779    2216    1369    2732    5451    4163
River Rch & RM= Walnut21,Reach-1,1729
    1357    1914    2388    1478    2948    5882    4506
Boundary for River Rch & Prof#=Walnut21,Reach-1,1
Up Type=0
Dn Type=3
Dn Slope=0.005
Boundary for River Rch & Prof#=Walnut21,Reach-1,2
Up Type=0
Dn Type=3
Dn Slope=0.005
Boundary for River Rch & Prof#=Walnut21,Reach-1,3
Up Type=0
Dn Type=3
Dn Slope=0.005
Boundary for River Rch & Prof#=Walnut21,Reach-1,4
Up Type=0
Dn Type=3
Dn Slope=0.005
Boundary for River Rch & Prof#=Walnut21,Reach-1,5
Up Type=0
Dn Type=3
Dn Slope=0.005
Boundary for River Rch & Prof#=Walnut21,Reach-1,6
Up Type=0
Dn Type=3
Dn Slope=0.005
Boundary for River Rch & Prof#=Walnut21,Reach-1,7
Up Type=0
Dn Type=3
Dn Slope=0.005

--- Walnut21.g01 (geometry) ---

Geom Title=Existing Conditions
Program Version=4.10

River Reach=Walnut21        ,Reach-1
Reach XY= 30
        2758062.      6765227.29      2757849.61      6765047.41
       2757923.3      6764377.74      2757689.24      6764197.86
      2758122.68      6764026.65      2757886.45      6763714.57
      2758012.15      6763385.15      2757741.25      6763283.29
      2757676.17      6763447.14      2757353.32       6763057.9
      2757320.81      6762854.18      2757663.23      6762656.96
      2757515.86      6762273.36      2757240.62      6762173.67
       2757420.5      6761855.09      2757355.48      6761330.62
      2756982.72      6760983.87      2756577.45      6759926.26
       2756878.1      6758466.87      2757125.62      6758095.84
      2757125.07      6757371.48      2756927.96      6757066.65
      2757576.04      6756491.02      2757674.03      6754816.65
      2757335.02      6754568.02      2757028.06      6753855.14
      2757072.55      6753412.25      2756675.94      6752941.01
       2757170.6      6752413.71        2757226.        6751961.

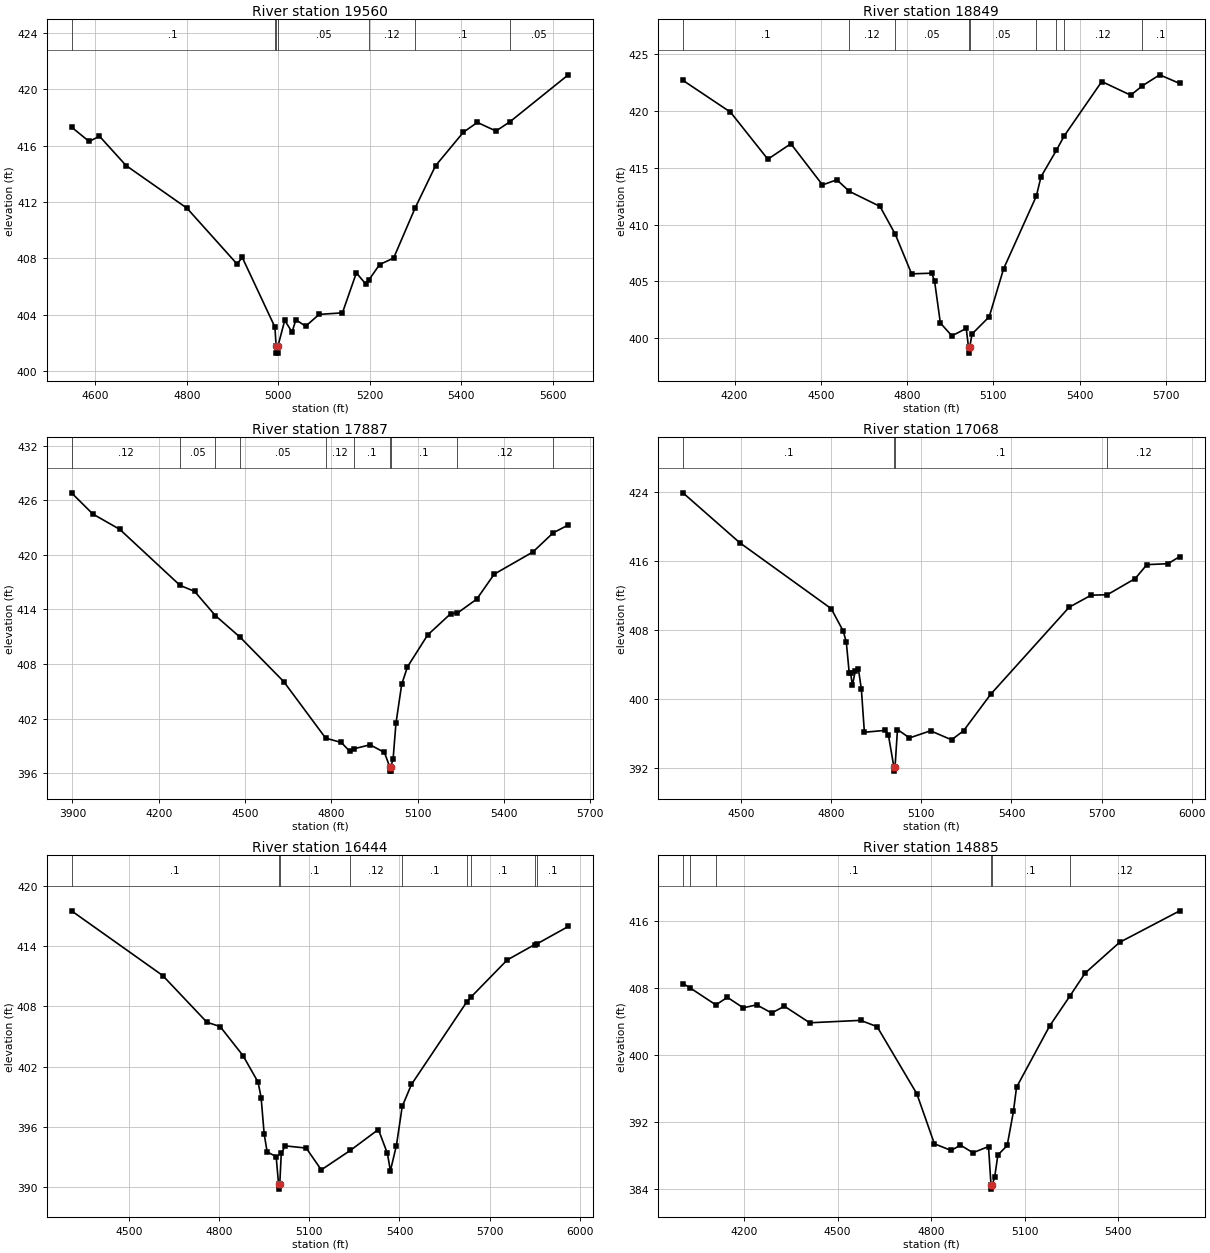
Type RM Length L Ch R = 1 ,19560   ,711,711,711
BEGIN DESCRIPTION:
Walnut21 25.0
END DESCRIPTION:
XS GIS Cut Line= 4
      2758476.71      6765120.96      2758064.46      6765172.14
       2758007.6      6765200.57      2757410.72      6765314.26
#Sta/Elev= 30
  4547.6  417.31  4586.1  416.29  4608.8  416.66  4666.9  414.58  4800.2  411.55
  4909.6  407.59  4921.2  408.05  4992.5  403.11  4995.2  401.76  4995.5  401.26
    4999  401.26  4999.2  401.76    5014  403.59    5030  402.75  5038.4  403.63
  5059.7  403.17  5089.3  404.01  5140.2  404.12  5170.7  406.96  5191.1  406.17
  5198.1  406.46  5221.6  407.55  5252.2  408.01  5299.3  411.57  5343.8  414.56
  5404.9  416.95  5435.4  417.64  5476.1  417.03  5507.1   417.7  5634.2  421.02
#Mann= 7 ,-1 , 0
  4547.6      .1       0  4992.5     .05       0  4995.2     .05       0
  4999.2     .05       0  5198.1     .12       0  5299.3      .1       0
  5507.1     .05       0
Bank Sta=4995.2,4999.2
XS Rating Curve= 0 ,0
Exp/Cntr=0.3,0.1

Type RM Length L Ch R = 1 ,18849   ,962,962,962
BEGIN DESCRIPTION:
Walnut21 23.0
END DESCRIPTION:
XS GIS Cut Line= 4
      2758781.18      6764729.33      2758196.65       6764716.8
      2757503.54      6764708.45      2757056.75      6764762.73
#Sta/Elev= 30
  4020.4  422.68  4185.6  419.89  4315.6  415.75  4395.7  417.11  4505.7  413.49
  4555.7  413.94  4598.6  412.93  4705.7   411.6  4758.9  409.15  4815.7  405.67
  4885.7  405.73  4895.7  405.01  4915.7  401.35  4955.7  400.22  5005.7  400.87
  5013.7   399.2    5014   398.7  5017.7   399.2  5025.7  400.38  5085.7   401.9
  5135.7  406.12  5249.6  412.51  5265.8  414.21    5319  416.52  5346.5   417.8
  5477.1  422.58  5577.8  421.38  5618.7  422.21  5678.5  423.17  5748.3  422.41
#Mann= 9 ,-1 , 0
  4020.4      .1       0  4598.6     .12       0  4758.9     .05       0
  5013.7     .05       0  5017.7     .05       0  5249.6     .12       0
    5319      .1       0  5346.5     .12       0  5618.7      .1       0
Bank Sta=5013.7,5017.7
XS Rating Curve= 0 ,0
Exp/Cntr=0.3,0.1

Type RM Length L Ch R = 1 ,17887   ,819,819,819
BEGIN DESCRIPTION:
Walnut21 22.0
END DESCRIPTION:
XS GIS Cut Line= 4
      2758843.87      6764307.61      2758259.28      6764295.09
      2757566.17      6764286.74      2757120.24      6764340.91
#Sta/Elev= 30
  3896.7  426.83  3970.8   424.5  4064.6  422.81  4274.1  416.65  4324.7  415.99
  4396.8  413.33  4483.5  410.93  4634.7  406.06  4780.3  399.85  4834.7  399.37
  4864.7  398.38  4879.3  398.68  4934.7  399.12  4984.7  398.27  5002.7  396.72
    5003  396.22  5006.5  396.22  5006.7  396.72  5014.7  397.53  5024.7  401.47
  5044.7  405.77  5064.8  407.69  5134.8  411.19  5215.1  413.54  5238.6  413.61
  5305.7  415.14  5366.2  417.88  5501.1  420.33  5571.3  422.43  5623.8  423.29
#Mann= 10 ,-1 , 0
  3896.7     .12       0  4274.1     .05       0  4396.8     .12       0
  4483.5     .05       0  4780.3     .12       0  4879.3      .1       0
  5002.7     .07       0  5006.7      .1       0  5238.6     .12       0
  5571.3     .05       0
Bank Sta=5002.7,5006.7
XS Rating Curve= 0 ,0
Exp/Cntr=0.3,0.1

Type RM Length L Ch R = 1 ,17068   ,624,624,624
BEGIN DESCRIPTION:
Walnut21 21.0
END DESCRIPTION:
XS GIS Cut Line= 4
      2758777.01        6763936.      2758221.71      6763877.55
      2757520.24      6763910.95      2757144.44      6764027.87
#Sta/Elev= 30
  4306.2  423.96  4495.2  418.16  4799.9  410.49  4840.1  407.87  4850.2  406.57
  4859.9  402.98  4864.6  402.98  4870.3  401.56  4880.3   403.3  4890.3   403.5
  4900.3  401.12  4910.3  396.12  4980.4  396.34  4990.4  395.79  5008.4   392.1
  5008.7   391.6  5012.4   392.1  5020.5  396.44  5060.5  395.46  5130.6  396.29
  5200.7  395.24  5240.7   396.3  5330.8  400.53  5592.2  410.66  5665.5  412.06
  5719.3  412.11  5812.1  413.99    5851  415.61  5921.3  415.72  5960.4  416.55
#Mann= 4 ,-1 , 0
  4306.2      .1       0  5008.4     .07       0  5012.4      .1       0
  5719.3     .12       0
Bank Sta=5008.4,5012.4
XS Rating Curve= 0 ,0
Exp/Cntr=0.3,0.1

Type RM Length L Ch R = 1 ,16444   ,1559,1559,1559
BEGIN DESCRIPTION:
Walnut21 20.0
END DESCRIPTION:
XS GIS Cut Line= 4
      2758664.29      6763547.69      2758108.97      6763489.24
      2757407.51      6763522.64      2757031.72      6763639.55
#Sta/Elev= 30
  4307.8  417.53  4611.6  411.08  4758.6  406.43  4802.7     406  4879.2  403.09
  4929.2  400.45  4939.2  398.92  4949.3  395.31  4959.3  393.51  4989.3  393.04
  4997.3   390.3  4997.6   389.8  5001.3   390.3  5006.3  393.35  5019.3  394.11
  5089.4  393.89  5139.5  391.72  5236.4  393.66  5329.7  395.74  5359.7  393.36
  5369.7  391.63  5389.7  394.14  5409.1  398.04  5439.8  400.23  5623.5  408.43
  5638.8  408.96  5758.5  412.63  5850.3  414.17  5856.7  414.22    5962  415.97
#Mann= 9 ,-1 , 0
  4307.8      .1       0  4997.3     .07       0  5001.3      .1       0
  5236.4     .12       0  5409.1      .1       0  5623.5     .12       0
  5638.8      .1       0  5850.3     .12       0  5856.7      .1       0
Bank Sta=4997.3,5001.3
XS Rating Curve= 0 ,0
Exp/Cntr=0.3,0.1

Type RM Length L Ch R = 1 ,14885   ,1587,1587,1587
BEGIN DESCRIPTION:
Walnut21 19.0
END DESCRIPTION:
XS GIS Cut Line= 4
      2758426.31      6763138.51      2757791.64      6763021.59
      2757173.68       6763038.3       2756843.8       6763071.7
#Sta/Elev= 30
  4003.3  408.57  4024.6  408.09  4108.9  406.02    4146  406.92  4196.8  405.67
  4240.2  406.02  4288.2  405.05    4329  405.86  4410.3  403.88  4573.6  404.17
  4626.6  403.42  4754.3  395.39  4810.6  389.42  4864.4  388.62  4894.4  389.26
  4934.4  388.35  4984.4  389.09  4992.4   384.5  4992.7     384  4996.4   384.5
  5004.4  385.48  5014.4  388.07  5044.4  389.22  5064.4  393.28  5074.4  396.18
  5180.7   403.5  5245.6  407.07  5294.7  409.82  5405.2  413.49  5598.4  417.26
#Mann= 6 ,-1 , 0
  4003.3      .1       0  4024.6     .12       0  4108.9      .1       0
  4992.4     .07       0  4996.4      .1       0  5245.6     .12       0
Bank Sta=4992.4,4996.4
XS Rating Curve= 0 ,0
Exp/Cntr=0.3,0.1

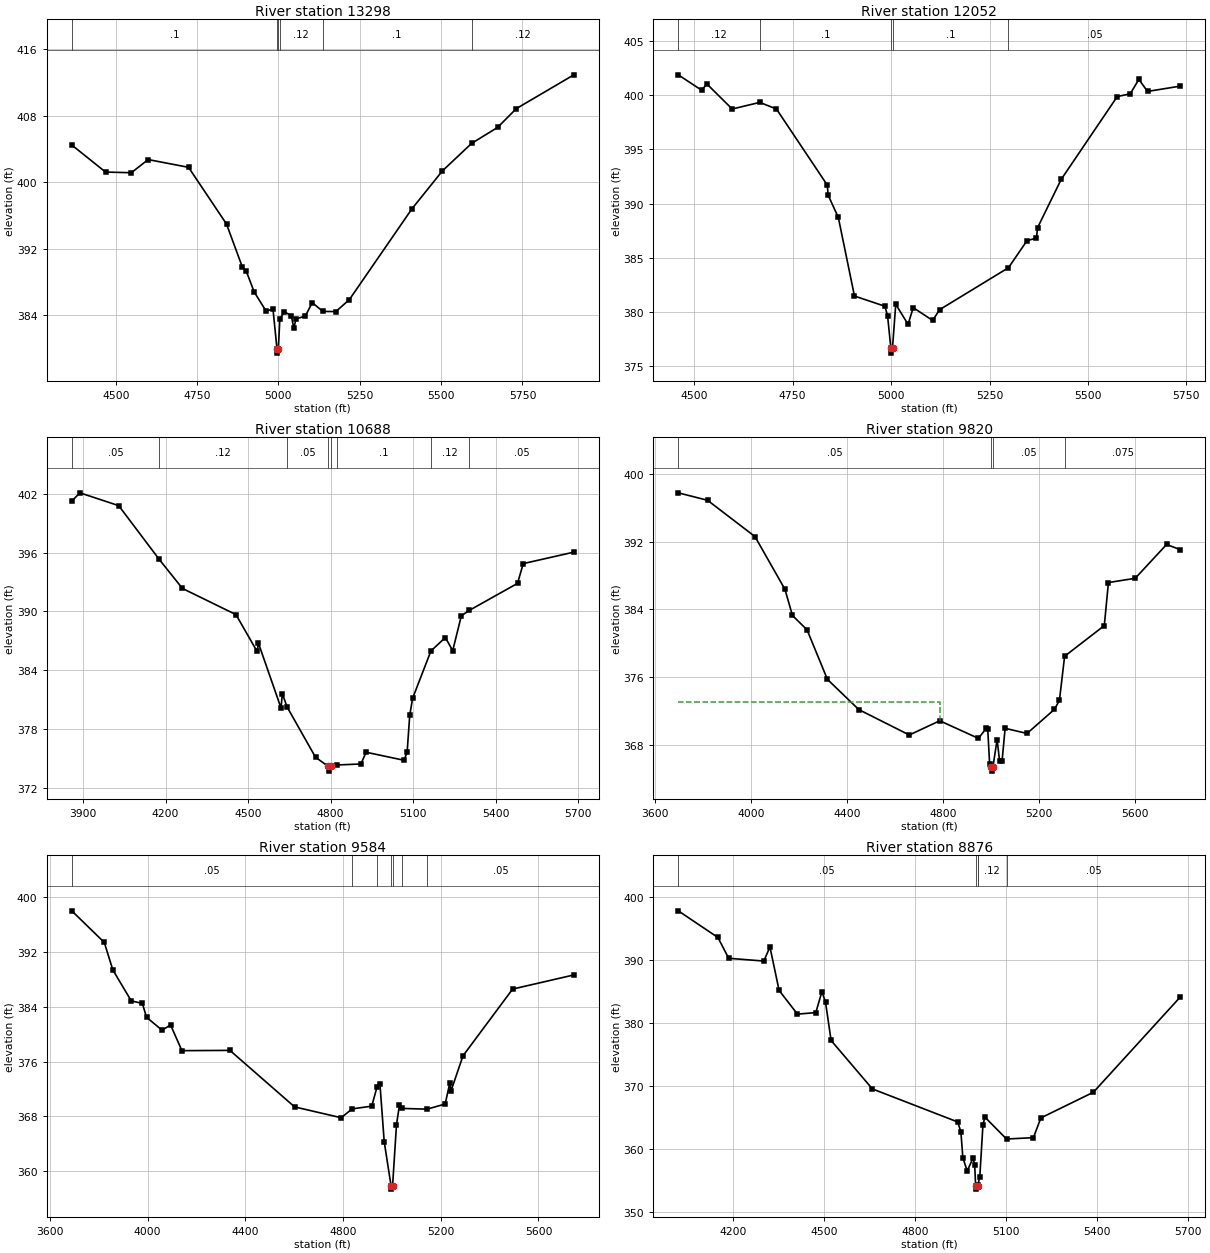
Type RM Length L Ch R = 1 ,13298   ,1246,1246,1246
BEGIN DESCRIPTION:
Walnut21 18.0
END DESCRIPTION:
XS GIS Cut Line= 4
      2758050.53      6761931.81       2757595.4      6762215.74
      2757190.39      6762524.72      2756803.24      6762836.94
#Sta/Elev= 30
  4364.8  404.48  4468.7  401.23  4547.8  401.15  4599.7  402.73  4723.7   401.8
  4840.4  394.99  4888.7  389.86  4901.2  389.32  4925.6  386.82  4962.3  384.52
  4983.2  384.79  4995.6  379.98  4995.9  379.48  4999.8  379.98  5004.3  383.59
  5018.5  384.45  5039.3  383.97  5047.6  382.49  5053.9  383.58  5082.9  383.94
  5103.8  385.55  5136.4  384.49  5176.4  384.47  5218.1  385.91  5410.3  396.81
    5504  401.37  5593.9  404.68  5673.6  406.59  5731.2  408.85    5908  412.91
#Mann= 6 ,-1 , 0
  4364.8      .1       0  4995.6     .07       0  4999.8      .1       0
  5004.3     .12       0  5136.4      .1       0  5593.9     .12       0
Bank Sta=4995.6,4999.8
XS Rating Curve= 0 ,0
Exp/Cntr=0.3,0.1

Type RM Length L Ch R = 1 ,12052   ,1364,1364,1364
BEGIN DESCRIPTION:
Walnut21 17.0
END DESCRIPTION:
XS GIS Cut Line= 4
      2757783.31      6761422.41      2757432.83      6761565.31
      2756923.16       6761714.7      2756590.04       6761864.6
#Sta/Elev= 30
  4459.6  401.86  4519.1  400.44  4532.3  401.02  4596.6  398.71  4666.6  399.32
    4709  398.71  4838.1   391.7  4840.3  390.77  4866.1  388.72  4907.1  381.48
  4984.3  380.54  4991.1  379.68  4999.4  376.72  4999.7  376.22  5003.7  376.72
  5011.9  380.72  5043.2  378.87  5056.3  380.41  5105.7  379.23  5123.2  380.22
  5298.2  384.09  5345.4  386.59  5369.2  386.81    5372  387.77  5431.9  392.22
  5574.4  399.86  5607.3  400.11  5629.3  401.44  5651.2  400.33  5734.5  400.82
#Mann= 5 ,-1 , 0
  4459.6     .12       0  4666.6      .1       0  4999.4     .07       0
  5003.7      .1       0  5298.2     .05       0
Bank Sta=4999.4,5003.7
XS Rating Curve= 0 ,0
Exp/Cntr=0.3,0.1

Type RM Length L Ch R = 1 ,10688   ,868,868,868
BEGIN DESCRIPTION:
Walnut21 16.0
END DESCRIPTION:
XS GIS Cut Line= 4
      2757975.38      6760687.56      2757052.87      6760575.75
       2756543.2      6760725.13      2756330.65      6761021.04
#Sta/Elev= 30
  3859.3  401.27  3888.9  402.12  4029.9  400.81  4176.8  395.33  4261.6  392.35
    4456  389.68  4532.8  385.92  4537.9  386.75  4619.7  380.14  4624.7   381.6
  4641.7  380.25  4745.1  375.11  4790.5  374.19  4793.9  373.69  4800.9  374.19
  4824.8  374.32  4910.3  374.42  4928.8  375.62  5066.7   374.8  5078.1  375.62
  5087.5  379.38  5097.9  381.12  5164.5  385.96  5216.9  387.34  5243.8     386
  5275.1  389.56  5304.6  390.12  5479.3  392.87  5500.1  394.89    5684  396.06
#Mann= 8 ,-1 , 0
  3859.3     .05       0  4176.8     .12       0  4641.7     .05       0
  4790.5     .07       0  4800.9     .05       0  4824.8      .1       0
  5164.5     .12       0  5304.6     .05       0
Bank Sta=4790.5,4800.9
XS Rating Curve= 0 ,0
Exp/Cntr=0.3,0.1

Type RM Length L Ch R = 1 ,9820    ,236,236,236
BEGIN DESCRIPTION:
Walnut21 15.5
END DESCRIPTION:
XS GIS Cut Line= 3
       2757833.4      6760278.37      2756651.76      6759931.81
      2755820.98      6759693.84
#Sta/Elev= 30
  3695.3  397.76  3817.6  396.88  4015.6  392.59  4140.7  386.36    4172  383.27
    4233  381.57  4317.9  375.72    4449  372.15  4659.8  369.15  4786.8  370.83
  4948.1  368.75  4981.8  369.96    4987  369.89  4995.1  365.67  5002.4  365.38
  5003.4  364.88  5008.7  365.38  5026.3  368.61  5036.7  366.05  5047.1  366.13
  5059.7  369.94  5151.1  369.33  5265.6  372.18  5286.4  373.25    5308  378.45
  5473.6  382.07  5490.9  387.16  5602.6  387.66  5733.7  391.66  5790.9  391.04
#Mann= 4 ,-1 , 0
  3695.3     .05       0  5002.4     .04       0  5008.7     .05       0
    5308    .075       0
#XS Ineff= 2 , 0
       0  4786.8     373               0
Permanent Ineff=
       F       F
Bank Sta=5002.4,5008.7
XS Rating Curve= 0 ,0
Exp/Cntr=0.3,0.1

Type RM Length L Ch R = 1 ,9584    ,708,708,708
BEGIN DESCRIPTION:
Walnut21 15.0
END DESCRIPTION:
XS GIS Cut Line= 3
      2757891.81      6760019.48      2756739.44      6759714.69
       2755909.8      6759477.05
#Sta/Elev= 30
  3689.7  397.98  3822.8  393.37  3857.9  389.35  3933.2  384.85  3978.6  384.48
  3995.7  382.46  4059.1  380.58  4094.2  381.33  4140.5  377.59    4337  377.63
  4601.8  369.39  4792.2  367.81  4837.3   369.1  4917.5   369.5  4939.3  372.32
  4951.2  372.68  4968.5  364.32  4996.5   357.9  4997.6   357.4  5002.8   357.9
  5018.8   366.8  5030.9  369.65  5041.5  369.17  5143.7  369.06  5218.1  369.81
  5236.9  372.87  5242.1  371.74    5291  376.84  5494.1  386.57  5744.7  388.63
#Mann= 7 ,-1 , 0
  3689.7     .05       0  4837.3     .12       0  4939.3     .05       0
  4996.5     .04       0  5002.8     .05       0  5041.5     .12       0
  5143.7     .05       0
Bank Sta=4996.5,5002.8
XS Rating Curve= 0 ,0
Exp/Cntr=0.3,0.1

Type RM Length L Ch R = 1 ,8876    ,1161,1161,1161
BEGIN DESCRIPTION:
Walnut21 14.5
END DESCRIPTION:
XS GIS Cut Line= 3
      2757795.86      6759247.05      2757010.84      6759146.84
      2756180.52        6758909.
#Sta/Elev= 30
    4019  397.75  4149.9  393.52  4185.2  390.22  4301.1  389.78  4321.3  392.01
  4351.5  385.12    4412  381.36  4472.5   381.6  4492.7  384.93  4504.5  383.26
  4522.9  377.18    4659  369.49  4940.2  364.25  4950.7  362.69  4957.3  358.58
  4971.5  356.47    4991  358.52  4996.2  357.46  4999.4  354.09  5000.4  353.59
    5006  354.09  5007.1  354.31  5013.1  355.53  5023.5  363.81    5030  365.01
  5101.2  361.54  5189.9  361.76  5214.4  364.89  5387.5  368.96  5674.1  384.08
#Mann= 5 ,-1 , 0
    4019     .05       0  4999.4     .04       0    5006     .05       0
  5007.1     .12       0  5101.2     .05       0
Bank Sta=4999.4,5006
XS Rating Curve= 0 ,0
Exp/Cntr=0.3,0.1

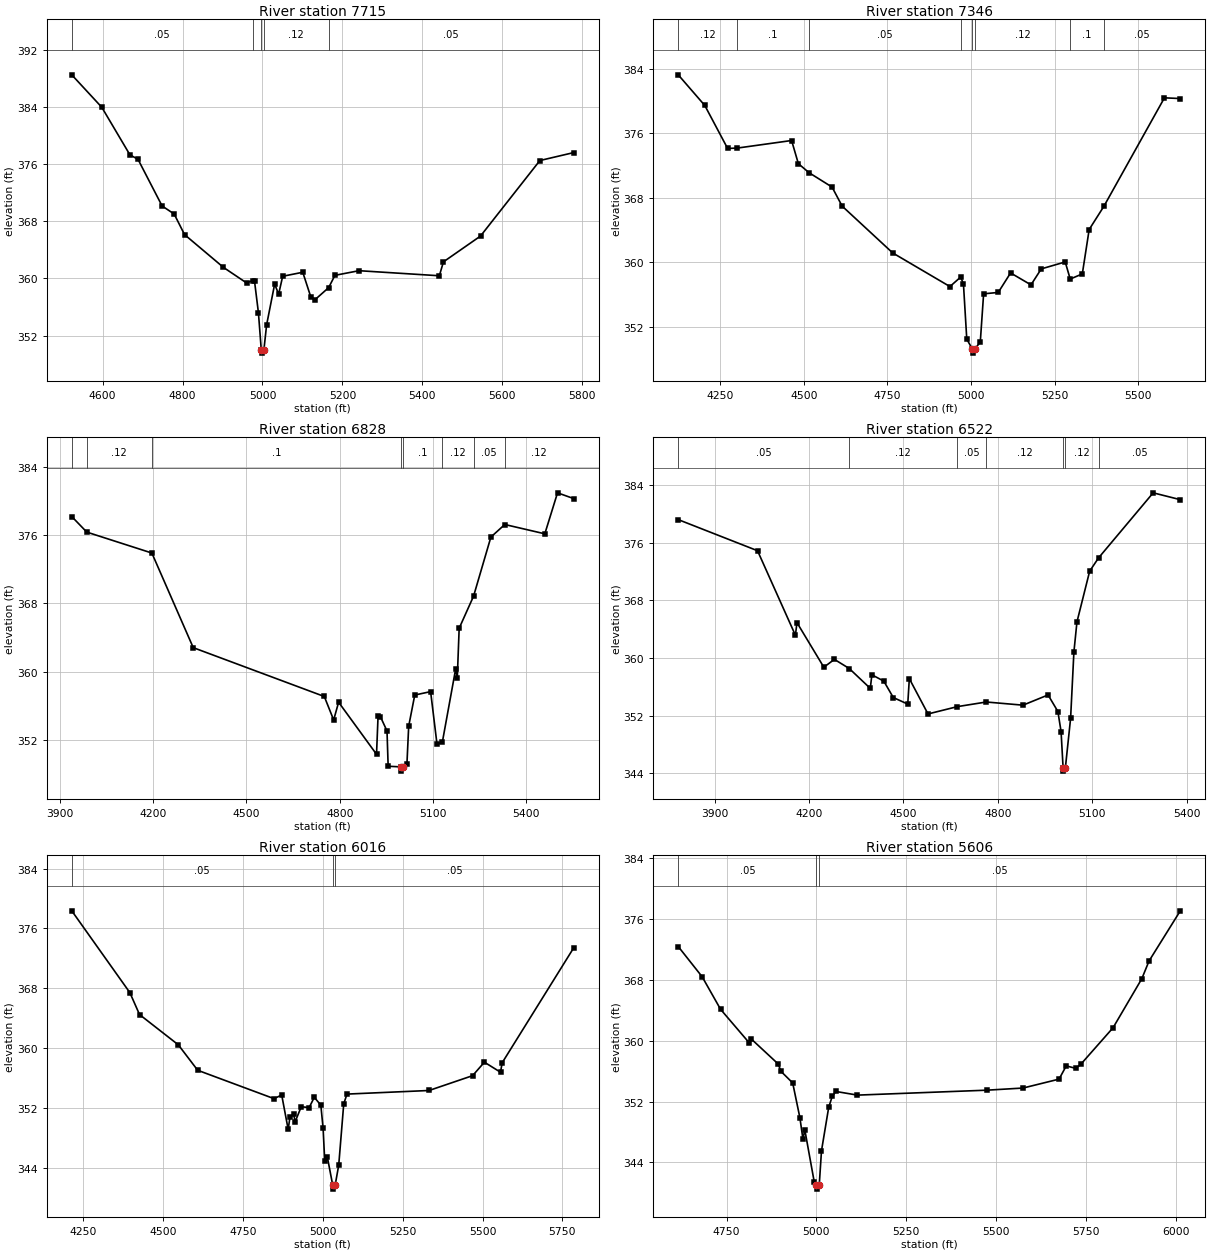
Type RM Length L Ch R = 1 ,7715    ,369,369,369
BEGIN DESCRIPTION:
Walnut21 14.0
END DESCRIPTION:
XS GIS Cut Line= 3
      2757600.72      6758136.03      2757049.58      6758077.24
      2756351.51      6758150.72
#Sta/Elev= 30
  4522.9  388.56    4598  384.01  4668.4  377.34  4688.6  376.71  4748.9  370.17
  4779.1  369.04  4805.1  366.15  4902.5  361.55  4960.1  359.38  4975.4   359.7
  4980.2   359.6  4989.9   355.2    4997  350.03    4998  349.53  5003.7  350.03
  5010.4  353.49  5030.5  359.21  5040.5   357.8  5050.6  360.31  5100.9  360.87
    5121   357.4    5131     357  5165.7  358.72  5181.3  360.44  5241.7  361.09
  5442.6  360.38  5452.8  362.33  5545.6  365.95  5694.1  376.54  5779.1  377.66
#Mann= 5 ,-1 , 0
  4522.9     .05       0  4975.4     .12       0    4997     .07       0
  5003.7     .12       0  5165.7     .05       0
Bank Sta=4997,5003.7
XS Rating Curve= 0 ,0
Exp/Cntr=0.3,0.1

Type RM Length L Ch R = 1 ,7346    ,518,518,518
BEGIN DESCRIPTION:
Walnut21 13.0
END DESCRIPTION:
XS GIS Cut Line= 3
      2757992.56       6757825.6        2756983.      6757698.25
      2756509.63      6757594.34
#Sta/Elev= 30
  4124.2  383.25  4203.7  379.45  4271.9  374.13  4300.6  374.17  4463.4  375.11
  4483.6  372.24    4516  371.11  4584.4  369.34  4614.6  366.98  4765.8  361.18
  4937.1  357.01    4969  358.18  4977.5  357.37  4987.5  350.49  5004.3  349.26
  5005.4  348.76  5011.1  349.26  5027.9  350.12  5037.9  356.11  5081.6  356.28
  5118.6   358.7  5179.6  357.22  5210.4   359.2    5282  360.06    5297  357.94
  5333.2  358.58  5353.7  364.08  5397.8  366.96  5578.9   380.4  5626.4  380.31
#Mann= 8 ,-1 , 0
  4124.2     .12       0  4300.6      .1       0    4516     .05       0
    4969     .12       0  5004.3     .07       0  5011.1     .12       0
    5297      .1       0  5397.8     .05       0
Bank Sta=5004.3,5011.1
XS Rating Curve= 0 ,0
Exp/Cntr=0.3,0.1

Type RM Length L Ch R = 1 ,6828    ,306,306,306
BEGIN DESCRIPTION:
Walnut21 12.0
END DESCRIPTION:
XS GIS Cut Line= 4
      2758115.26      6757355.55       2757107.6      6757273.67
      2757031.63      6757313.87       2756524.5      6757211.98
#Sta/Elev= 30
  3938.5  378.17  3986.8  376.35    4196   373.9    4329  362.82  4750.4   357.1
  4780.5  354.35  4796.4  356.43  4918.3  350.33  4923.3  354.85    4931  354.72
    4952  353.06  4955.7  348.93    4996  348.86  4997.2  348.36  5003.4  348.86
  5016.1  349.24  5021.7  353.62  5041.2  357.27  5092.2  357.67  5112.6  351.56
  5129.8  351.73  5172.8  360.34  5177.9  359.22    5184  365.09  5230.3  368.85
    5286  375.77  5330.7  377.24  5459.4  376.15  5500.2  380.95  5552.7  380.27
#Mann= 8 ,-1 , 0
  3938.5     .05       0  3986.8     .12       0    4196      .1       0
    4996     .07       0  5003.4      .1       0  5129.8     .12       0
  5230.3     .05       0  5330.7     .12       0
Bank Sta=4996,5003.4
XS Rating Curve= 0 ,0
Exp/Cntr=0.3,0.1

Type RM Length L Ch R = 1 ,6522    ,506,506,506
BEGIN DESCRIPTION:
Walnut21 11.0
END DESCRIPTION:
XS GIS Cut Line= 3
      2758137.19      6757188.07      2757189.21      6757107.23
      2756550.47      6757019.13
#Sta/Elev= 30
  3783.9  379.21    4036  374.89  4156.4  363.15  4161.4   364.9  4246.8  358.71
  4280.4   359.8  4327.6  358.53  4394.5  355.77  4399.5  357.66  4437.4  356.78
  4467.6   354.5  4513.6  353.59  4518.6  357.12    4578  352.22  4671.6  353.24
  4763.3  353.88  4879.9  353.44  4959.7  354.86  4990.9  352.56    5001  349.78
  5007.4  344.78  5008.6  344.28  5014.8  344.78  5031.3  351.61  5041.8  360.82
  5051.5     365  5091.9  372.05  5120.3   373.9  5293.8  382.93  5380.1  381.98
#Mann= 7 ,-1 , 0
  3783.9     .05       0  4327.6     .12       0  4671.6     .05       0
  4763.3     .12       0  5007.4     .07       0  5014.8     .12       0
  5120.3     .05       0
Bank Sta=5007.4,5014.8
XS Rating Curve= 0 ,0
Exp/Cntr=0.3,0.1

Type RM Length L Ch R = 1 ,6016    ,410,410,410
BEGIN DESCRIPTION:
Walnut21 10.0
END DESCRIPTION:
XS GIS Cut Line= 3
       2758085.7      6756901.46      2757409.66      6756798.59
      2756542.58      6756607.54
#Sta/Elev= 30
  4214.1  378.35  4395.9  367.43  4426.2   364.5  4547.6  360.46  4608.3  357.06
  4847.3  353.27  4871.3  353.76  4891.5  349.17  4897.2   350.8  4908.4  351.21
  4913.5  350.19  4932.4  352.19  4957.2  352.08  4973.3  353.45  4993.8   352.4
  5000.9   349.3    5006   344.9  5014.3  345.44  5031.1  341.69  5032.2  341.19
  5038.5  341.69  5049.8   344.4  5065.5  352.59  5075.7  353.88  5332.5  354.36
  5468.8  356.34  5505.8  358.14  5556.2   356.8  5561.4  358.06  5785.8  373.44
#Mann= 3 ,-1 , 0
  4214.1     .05       0  5031.1     .04       0  5038.5     .05       0
Bank Sta=5031.1,5038.5
XS Rating Curve= 0 ,0
Exp/Cntr=0.3,0.1

Type RM Length L Ch R = 1 ,5606    ,147,147,147
BEGIN DESCRIPTION:
Walnut21 9.0
END DESCRIPTION:
XS GIS Cut Line= 3
      2757953.46      6756541.39      2757666.86      6756519.35
      2756559.16      6756460.66
#Sta/Elev= 30
  4615.6  372.37  4682.1   368.4  4733.4  364.12  4812.5  359.75  4817.5  360.28
  4893.9  356.93    4901  355.99    4934  354.45    4954  349.89  4962.6  347.04
  4967.6  348.32    4994  341.43  5000.2     341  5001.4   340.5  5007.8     341
  5014.1  345.53  5034.1  351.23  5044.1   352.7  5054.1  353.33  5114.2  352.85
  5474.7   353.5  5574.8  353.78    5675  354.95    5695  356.69  5721.2  356.37
  5735.1  356.88  5825.2   361.7  5905.3  368.15  5925.3  370.47  6012.3  377.06
#Mann= 3 ,-1 , 0
  4615.6     .05       0  5000.2     .04       0  5007.8     .05       0
Bank Sta=5000.2,5007.8
XS Rating Curve= 0 ,0
Exp/Cntr=0.3,0.1

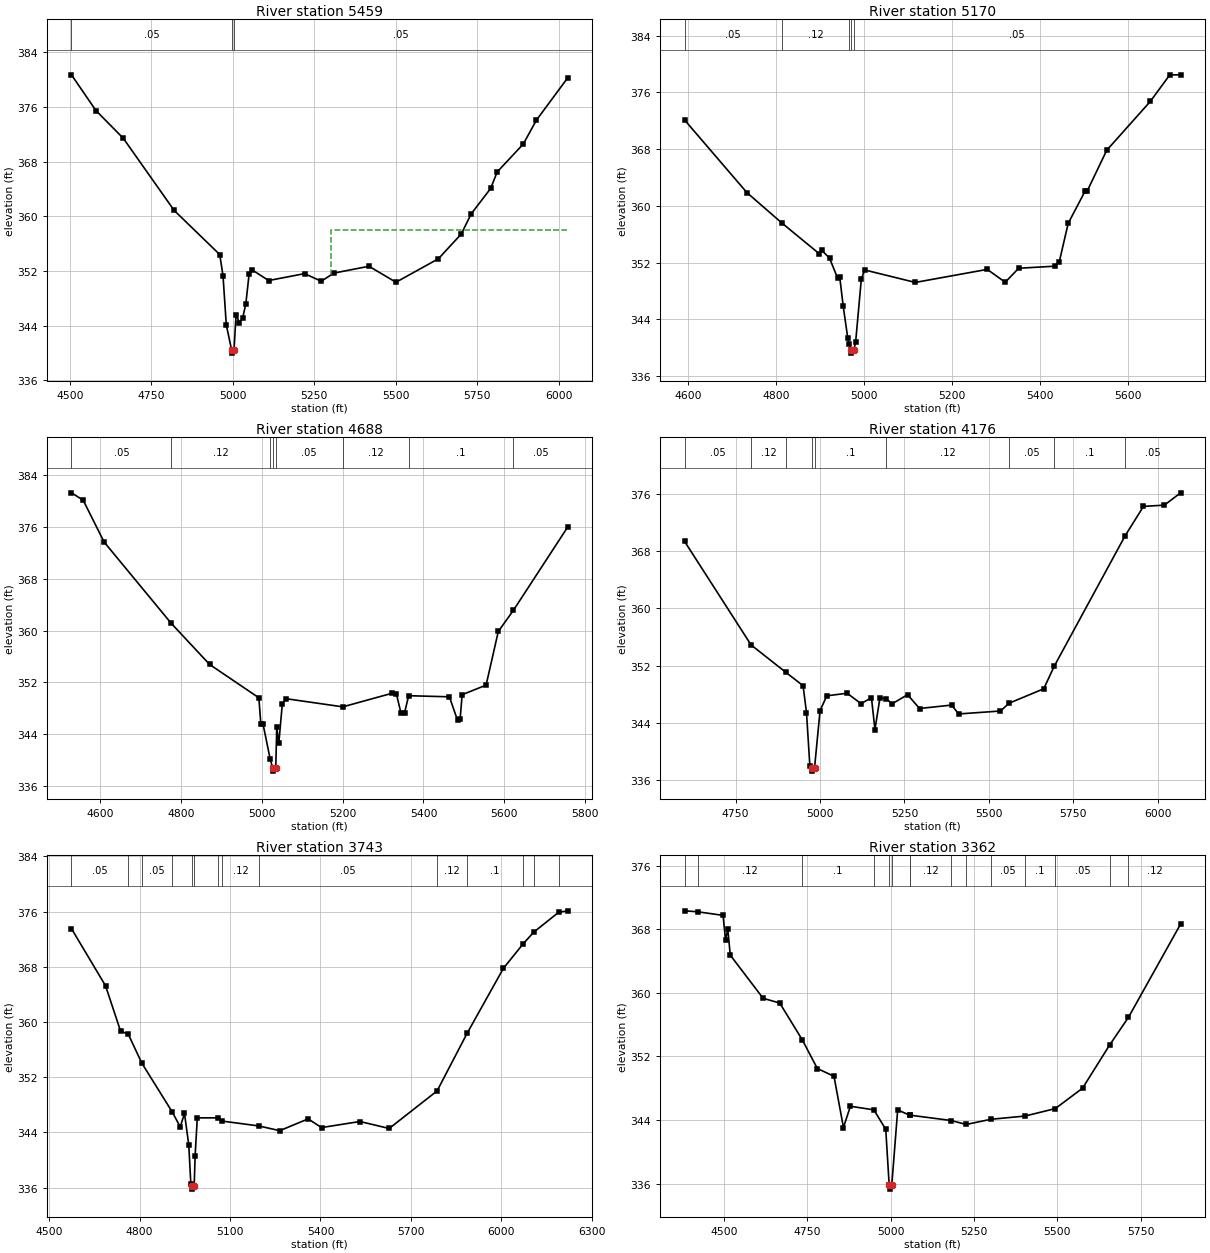
Type RM Length L Ch R = 1 ,5459    ,289,289,289
BEGIN DESCRIPTION:
Walnut21 8.5
END DESCRIPTION:
XS GIS Cut Line= 3
      2758071.05      6756379.72      2757446.41      6756365.03
      2756550.45      6756306.27
#Sta/Elev= 30
  4504.9  380.72    4580  375.49  4664.1  371.42    4820  360.87  4960.1   354.4
  4970.1  351.28  4980.1  344.11  4996.3  340.47  4997.4  339.97  5003.9  340.47
  5010.1  345.61  5020.1  344.45  5030.1  345.06  5040.1   347.2  5050.1  351.53
  5060.1  352.14  5110.1   350.6  5220.3  351.61  5271.6   350.5  5310.5  351.69
  5418.1  352.69  5500.9  350.35  5631.2  353.79  5701.4  357.41  5731.4  360.33
  5791.5  364.08  5811.6   366.5  5891.8  370.59  5931.8  374.07  6027.6  380.25
#Mann= 3 ,-1 , 0
  4504.9     .05       0  4996.3     .04       0  5003.9     .05       0
#XS Ineff= 2 , 0
       0                    5300       0     358
Permanent Ineff=
       F       F
Bank Sta=4996.3,5003.9
XS Rating Curve= 0 ,0
Exp/Cntr=0.3,0.1

Type RM Length L Ch R = 1 ,5170    ,482,482,482
BEGIN DESCRIPTION:
Walnut21 8.0
END DESCRIPTION:
XS GIS Cut Line= 3
      2757875.98        6756011.        2757476.        6756111.
      2756775.99        6755961.
#Sta/Elev= 30
  4591.8  372.11  4733.5  361.87  4813.4  357.56  4898.4  353.23  4903.6  353.74
  4921.6  352.61  4939.7  349.83  4944.8  349.94  4952.6  345.88  4962.9  341.39
  4966.5  340.47  4969.4  339.72  4970.5  339.22    4977  339.72  4980.9  340.76
  4993.8  349.62  5001.5  350.95  5116.6  349.19  5280.2  351.03  5321.1  349.22
  5351.8  351.19  5433.6  351.48  5443.9  352.06  5464.3  357.52  5502.7  362.06
  5507.8  362.12  5552.1  367.84    5651  374.71  5695.3  378.46    5720  378.47
#Mann= 5 ,-1 , 0
  4591.8     .05       0  4813.4     .12       0  4966.5     .05       0
  4969.4     .04       0    4977     .05       0
Bank Sta=4969.4,4977
XS Rating Curve= 0 ,0
Exp/Cntr=0.3,0.1

Type RM Length L Ch R = 1 ,4688    ,512,512,512
BEGIN DESCRIPTION:
Walnut21 7.0
END DESCRIPTION:
XS GIS Cut Line= 3
        2757976.        6755911.        2757576.        6755661.
      2756826.04        6755761.
#Sta/Elev= 30
  4528.4  381.27  4557.3  380.14  4609.2  373.67  4775.3  361.12  4870.4  354.76
  4992.4  349.61  4997.2  345.59  5002.6  345.59  5020.5  340.11  5026.6  338.78
  5027.7  338.28  5034.2  338.78  5036.7  345.04  5041.7  342.55  5050.5   348.7
  5060.6  349.46  5200.2  348.21  5322.9  350.32    5333  350.19  5344.4   347.2
  5353.2  347.32  5363.3  349.93  5464.2  349.76  5484.3  346.12  5490.7  346.31
  5495.7  350.09    5555  351.56  5585.2  359.85  5622.5  363.11  5756.7  375.95
#Mann= 8 ,-1 , 0
  4528.4     .05       0  4775.3     .12       0  5020.5     .05       0
  5026.6     .07       0  5034.2     .05       0  5200.2     .12       0
  5363.3      .1       0  5622.5     .05       0
Bank Sta=5026.6,5034.2
XS Rating Curve= 0 ,0
Exp/Cntr=0.3,0.1

Type RM Length L Ch R = 1 ,4176    ,433,433,433
BEGIN DESCRIPTION:
Walnut21 6.0
END DESCRIPTION:
XS GIS Cut Line= 3
      2758075.97        6755211.      2757586.03      6755174.56
       2756639.5      6755416.69
#Sta/Elev= 30
  4599.1  369.36  4796.1   354.9  4898.7  351.09    4950  349.21  4960.1  345.47
  4970.1  337.98  4976.3  337.79  4977.4  337.29    4984  337.79  5000.2  345.73
  5020.2   347.8  5080.4  348.16  5121.4  346.71  5152.4  347.53  5162.7  343.08
  5177.5  347.51  5196.1  347.42  5213.2  346.67  5259.2  347.96  5294.8  346.03
  5389.8  346.51  5410.4  345.27  5534.3  345.68  5559.8  346.77  5662.2  348.78
  5693.8  351.97  5903.1  370.13  5957.5  374.24  6019.2  374.41  6067.4  376.13
#Mann= 9 ,-1 , 0
  4599.1     .05       0  4796.1     .12       0  4898.7      .1       0
  4976.3     .07       0    4984      .1       0  5196.1     .12       0
  5559.8     .05       0  5693.8      .1       0  5903.1     .05       0
Bank Sta=4976.3,4984
XS Rating Curve= 0 ,0
Exp/Cntr=0.3,0.1

Type RM Length L Ch R = 1 ,3743    ,381,381,381
BEGIN DESCRIPTION:
Walnut21 5.0
END DESCRIPTION:
XS GIS Cut Line= 3
      2757926.01      6754460.99      2757505.19      6754895.31
      2756580.18      6755372.51
#Sta/Elev= 30
    4574  373.53  4687.1  365.24  4736.7   358.7  4762.6  358.22  4807.2  354.05
  4908.4  346.95  4934.8   344.8  4948.9  346.75  4963.1  342.19    4970  336.49
  4973.3  336.28  4974.5  335.78  4981.1  336.28  4984.2  340.63  4991.4  346.11
  5061.1  346.11  5073.8  345.64  5195.1  344.94  5264.9  344.25  5359.1  345.96
  5403.4   344.7  5530.8  345.58  5627.9  344.57  5786.8  350.01  5886.4  358.36
    6007  367.79  6072.9  371.36  6107.5  373.02  6189.8  375.89  6219.6  376.11
#Mann= 14 ,-1 , 0
    4574     .05       0  4762.6      .1       0  4807.2     .05       0
  4908.4     .12       0  4973.3     .07       0  4981.1     .12       0
  5061.1      .1       0  5073.8     .12       0  5195.1     .05       0
  5786.8     .12       0  5886.4      .1       0  6072.9     .05       0
  6107.5      .1       0  6189.8     .05       0
Bank Sta=4973.3,4981.1
XS Rating Curve= 0 ,0
Exp/Cntr=0.3,0.1

Type RM Length L Ch R = 1 ,3362    ,511,511,511
BEGIN DESCRIPTION:
Walnut21 4.0
END DESCRIPTION:
XS GIS Cut Line= 3
      2757799.15      6754160.44      2757277.39      6754638.11
      2756616.82      6755056.48
#Sta/Elev= 30
  4380.9  370.32  4420.3   370.2  4496.6  369.75    4504  366.65  4510.8  368.02
  4518.2  364.75  4616.8  359.32  4666.8  358.72  4734.9  354.06  4779.6  350.49
  4829.6  349.51    4858  343.07  4878.9  345.74  4949.3  345.29    4985  342.84
  4995.3  335.82  4996.5  335.32  5003.1  335.82  5020.8  345.28  5057.4  344.61
  5058.3  344.62  5181.2  343.95  5226.5  343.45  5300.1   344.1    5403  344.51
    5494  345.45  5575.7  348.01  5656.9  353.43  5713.7  356.93  5870.2  368.66
#Mann= 15 ,-1 , 0
  4380.9     .05       0  4420.3     .12       0  4734.9      .1       0
  4949.3     .12       0  4995.3     .07       0  5003.1     .12       0
  5057.4      .1       0  5058.3     .12       0  5181.2     .05       0
  5226.5      .1       0  5300.1     .05       0    5403      .1       0
    5494     .05       0  5656.9      .1       0  5713.7     .12       0
Bank Sta=4995.3,5003.1
XS Rating Curve= 0 ,0
Exp/Cntr=0.3,0.1

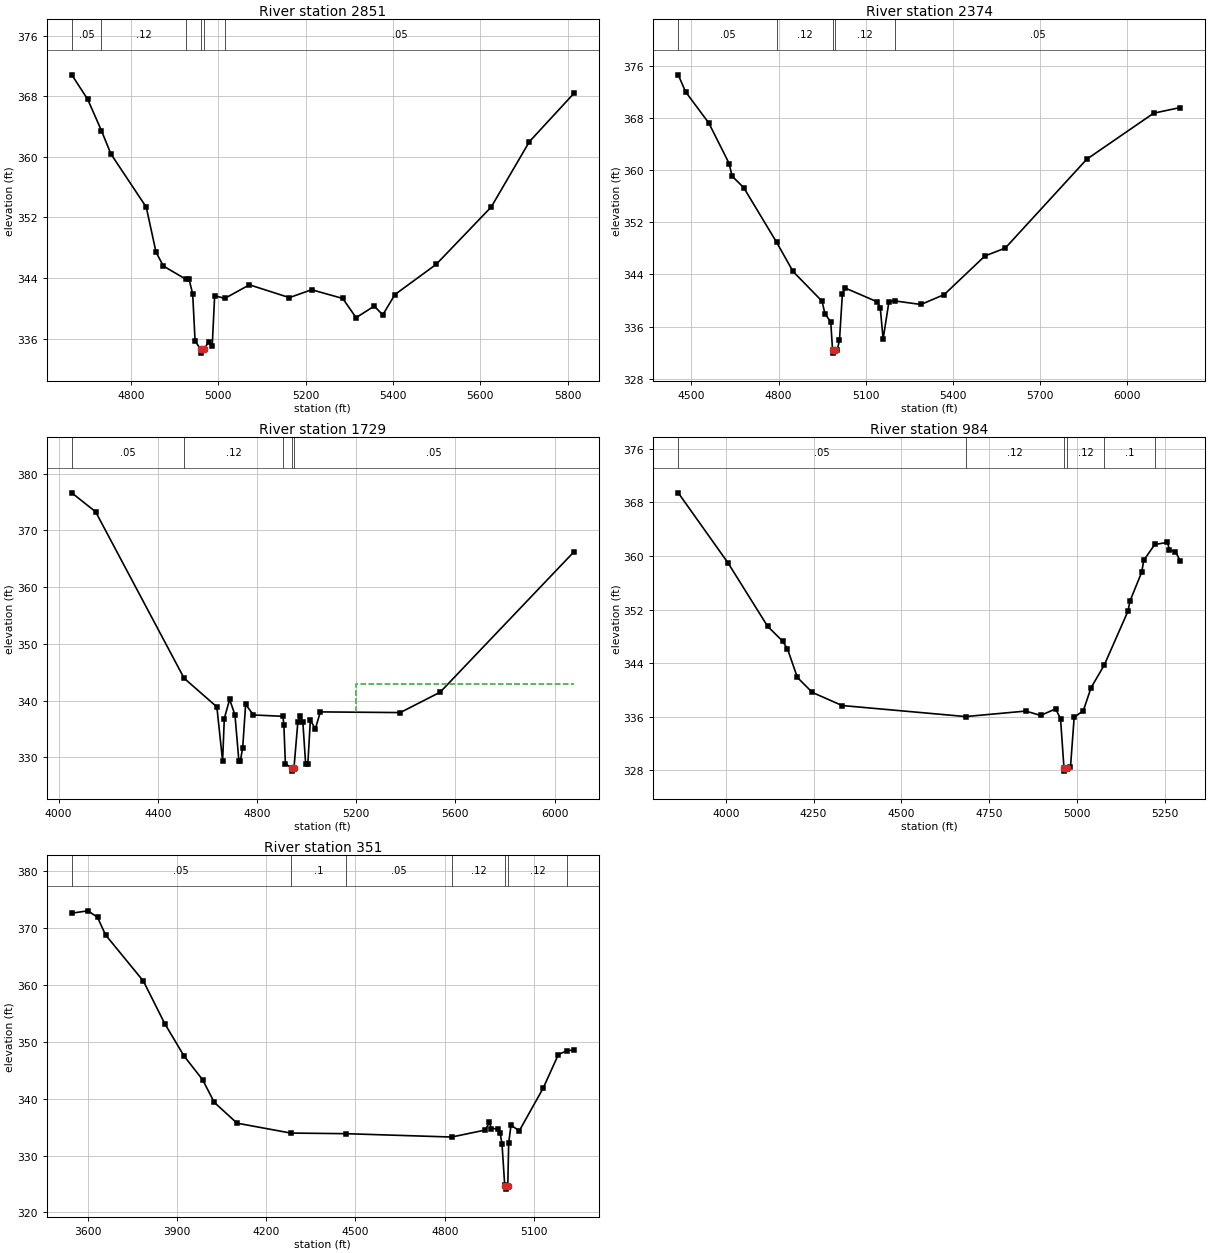
Type RM Length L Ch R = 1 ,2851    ,477,477,477
BEGIN DESCRIPTION:
Walnut21 3.0
END DESCRIPTION:
XS GIS Cut Line= 3
      2757526.04      6754010.98        2757226.        6754161.
      2756425.99        6754311.
#Sta/Elev= 30
  4664.8  370.83  4701.2   367.6  4732.8  363.45  4754.3  360.39  4835.3  353.36
  4857.7  347.41  4874.5  345.58  4925.3  343.86  4933.2  343.85  4941.6  341.91
  4947.1  335.67    4960  334.58  4961.2  334.08  4967.8  334.58  4977.9  335.58
  4986.3  334.98  4991.9  341.66  5015.2  341.31  5071.5   343.1    5163  341.41
  5213.9  342.45  5285.1   341.3  5315.7  338.76  5357.2  340.29  5376.7  339.13
  5404.7  341.82  5498.8  345.79  5625.1  353.38  5712.5  362.01  5814.2  368.37
#Mann= 6 ,-1 , 0
  4664.8     .05       0  4732.8     .12       0  4925.3      .1       0
    4960     .07       0  4967.8      .1       0  5015.2     .05       0
Bank Sta=4960,4967.8
XS Rating Curve= 0 ,0
Exp/Cntr=0.3,0.1

Type RM Length L Ch R = 1 ,2374    ,645,645,645
BEGIN DESCRIPTION:
Walnut21 2.0
END DESCRIPTION:
XS GIS Cut Line= 3
      2757571.31      6753748.94        2757026.        6753761.
      2755844.39      6753837.12
#Sta/Elev= 30
  4454.4  374.65  4479.7  372.04  4559.7  367.25  4629.8  361.03  4639.8  359.09
  4679.8  357.34  4793.4  348.93  4849.8  344.46  4949.8  339.89  4959.8  337.96
  4979.8  336.71  4985.9  332.42  4987.1  331.92  4993.8  332.42  5002.4  332.46
  5009.9  333.93  5019.9  341.06  5029.9  341.91  5140.1  339.79  5150.2   338.9
  5160.2  334.09  5180.2  339.82  5201.5  339.93  5290.4  339.39  5370.6  340.91
  5510.9  346.84    5581  348.05  5861.6  361.69  6092.1  368.76  6183.9  369.63
#Mann= 5 ,-1 , 0
  4454.4     .05       0  4793.4     .12       0  4985.9     .07       0
  4993.8     .12       0  5201.5     .05       0
Bank Sta=4985.9,4993.8
XS Rating Curve= 0 ,0
Exp/Cntr=0.3,0.1

Type RM Length L Ch R = 1 ,1729    ,745,745,745
BEGIN DESCRIPTION:
Walnut21 1.5
END DESCRIPTION:
XS GIS Cut Line= 3
      2757681.53      6753646.04      2757012.84      6753256.59
      2755770.95      6753403.56
#Sta/Elev= 30
  4053.3  376.62  4149.6  373.27  4506.3  343.94  4638.3  338.89  4661.5  329.32
  4668.3  336.84  4689.8  340.22  4711.3  337.47    4727  329.41  4732.8  329.32
  4742.5  331.69  4754.3  339.34  4785.8  337.47  4904.7  337.23  4908.4  335.76
  4914.6  328.87  4940.5  328.07  4941.7  327.57  4949.1  328.07  4964.9  336.23
    4975  337.26  4985.1  336.18  4996.3  328.79  5005.2  328.89  5015.3  336.54
  5035.4  335.03  5055.6  338.01  5377.8  337.89  5538.9  341.49  6077.7   366.2
#Mann= 5 ,-1 , 0
  4053.3     .05       0  4506.3     .12       0  4904.7     .05       0
  4940.5     .07       0  4949.1     .05       0
#XS Ineff= 2 , 0
       0                    5200       0     343
Permanent Ineff=
       F       F
Bank Sta=4940.5,4949.1
XS Rating Curve= 0 ,0
Exp/Cntr=0.3,0.1

Type RM Length L Ch R = 1 ,984     ,633,633,633
BEGIN DESCRIPTION:
Walnut21 1.0
END DESCRIPTION:
XS GIS Cut Line= 3
      2757625.99      6753510.99        2756826.        6752711.
      2756557.25      6752580.53
#Sta/Elev= 30
  3864.5  369.44  4005.9     359    4119  349.51  4161.5   347.3  4175.6  346.14
  4203.9  341.86  4246.3  339.63  4331.2  337.67  4683.1  336.02  4854.4  336.84
  4896.9  336.19  4939.3  337.17  4953.4  335.72  4963.2  328.37  4964.5  327.87
  4971.9  328.37  4981.7  328.42  4992.3  335.94  5018.1  336.86  5040.3  340.32
  5078.2  343.74  5145.3  351.74  5151.5  353.31  5184.8  357.61  5190.4  359.35
  5221.8  361.73  5258.1  362.03  5263.7  360.91  5280.7  360.64  5294.6  359.27
#Mann= 6 ,-1 , 0
  3864.5     .05       0  4683.1     .12       0  4963.2     .07       0
  4971.9     .12       0  5078.2      .1       0  5221.8     .05       0
Bank Sta=4963.2,4971.9
XS Rating Curve= 0 ,0
Exp/Cntr=0.3,0.1

Type RM Length L Ch R = 1 ,351     ,0,0,0
BEGIN DESCRIPTION:
Walnut21 0.5
END DESCRIPTION:
XS GIS Cut Line= 3
      2757806.48      6753550.51      2757468.45      6752484.99
      2756993.41      6752170.07
#Sta/Elev= 30
  3546.3  372.63  3600.5  373.04  3632.8  371.91  3659.8  368.81  3787.1  360.68
  3858.7  353.22  3923.2  347.55  3986.4  343.32  4025.3  339.36  4101.8   335.7
  4282.2  333.96  4468.3  333.85  4823.1  333.26  4935.4  334.48  4950.5  335.82
  4956.5  334.76    4979  334.68  4986.6  333.89  4992.6  332.01  5001.6   324.9
  5003.3   324.6  5004.6   324.1    5012   324.6    5015  332.17  5022.7  335.31
    5051  334.38  5130.9  341.85  5182.1  347.77  5211.3  348.44  5234.1  348.57
#Mann= 7 ,-1 , 0
  3546.3     .05       0  4282.2      .1       0  4468.3     .05       0
  4823.1     .12       0  5003.3     .07       0    5012     .12       0
  5211.3     .05       0
Bank Sta=5003.3,5012
XS Rating Curve= 0 ,0
Exp/Cntr=0.3,0.1

Chan Stop Cuts=-1
Use User Specified Reach Order=0
Composite Channel Slope=5