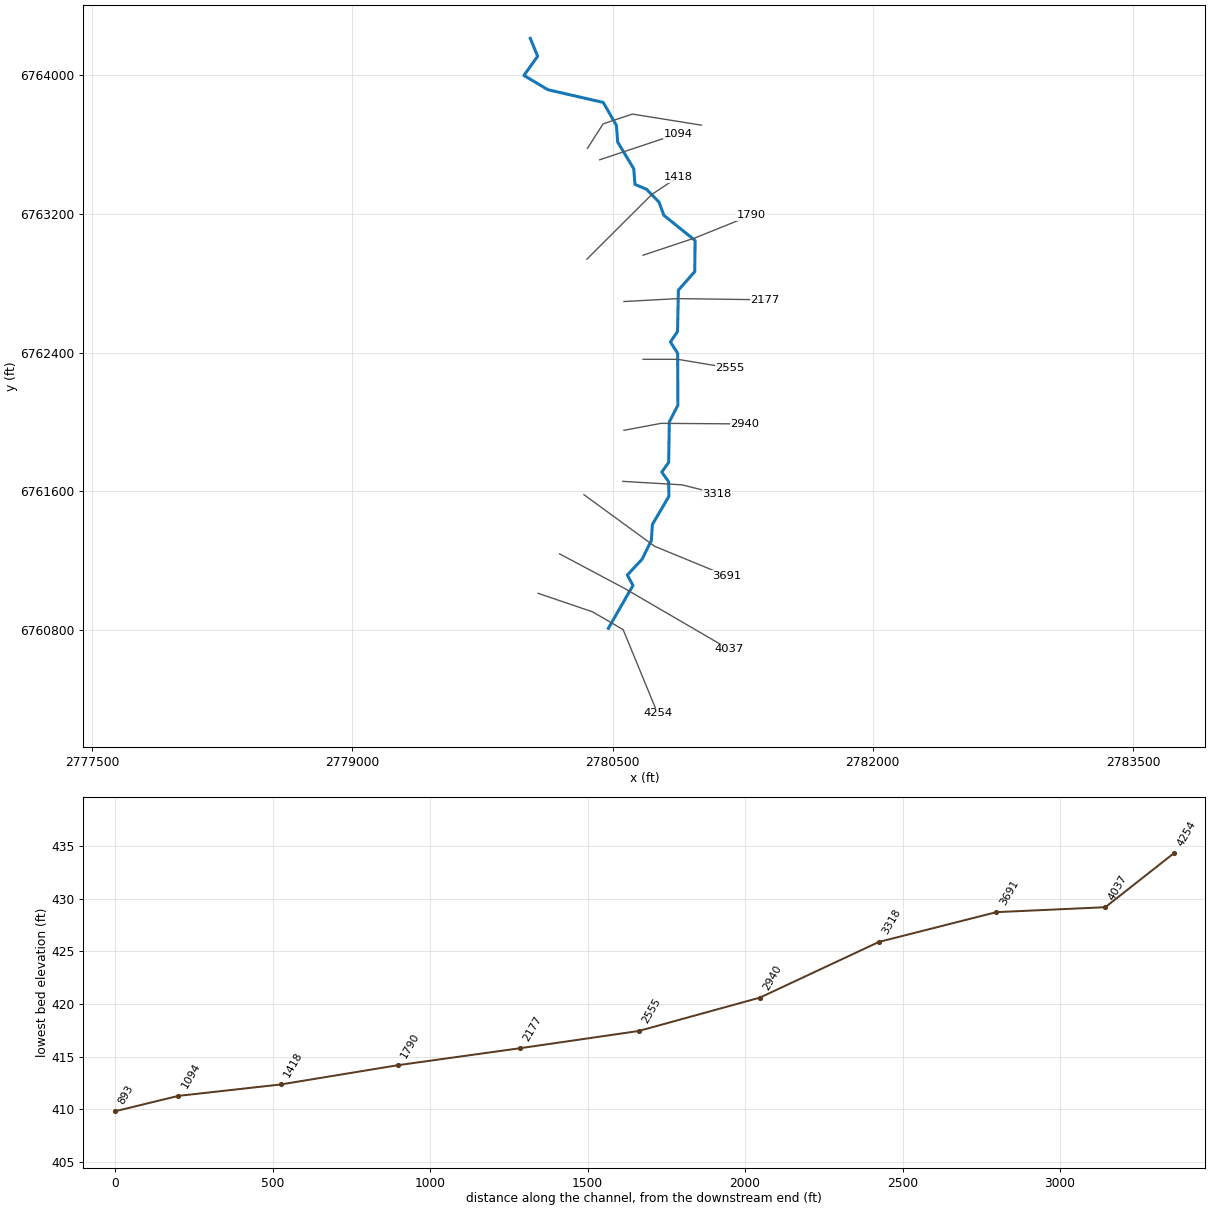
--- Walnut23.prj (project) ---

Proj Title=Walnut23 Base Level Engineering
Current Plan=p01
Default Exp/Contr=0.3,0.1
English Units
Geom File=g01
Flow File=f01
Plan File=p01
Y Axis Title=Elevation
X Axis Title(PF)=Main Channel Distance
X Axis Title(XS)=Station
BEGIN DESCRIPTION:
Walnut23
END DESCRIPTION:
DSS Export Rating Curves= 0
DSS Export Rating Curve Sorted= 0
DSS Export Volume Flow Curves= 0
DXF OffsetX= 0
DXF OffsetY= 0
DXF ScaleX= 1
DXF ScaleY= 10

--- Walnut23.p01 (plan) ---

Plan Title=Multiple Run
Program Version=4.10
Short Identifier=Multiple
Geom File=g01
Flow File=f01
Subcritical Flow
K Sum by GR= 0
Std Step Tol= 0.01
Critical Tol= 0.01
Num of Std Step Trials= 20
Max Error Tol= 0.3
Flow Tol Ratio= 0.001
Split Flow NTrial= 30
Split Flow Tol= 0.02
Split Flow Ratio= 0.02
Log Output Level= 0
Friction Slope Method= 1
Unsteady Friction Slope Method= 2
Unsteady Bridges Friction Slope Method= 1
Parabolic Critical Depth
Global Vel Dist= 1 , 1 , 1
Global Log Level= 0
CheckData=True
Encroach Param=-1 ,0,0, 0
BEGIN DESCRIPTION:
Multiple Run
END DESCRIPTION:
Computation Interval=1HOUR
Output Interval=1HOUR
Run HTab= 0
Run UNet= 0
Run PostProcess= 0
Run WQNet= 0
UNET Theta= 1
UNET Theta Warmup= 1
UNET ZTol= 0.02
UNET ZSATol= 0.05
UNET MxIter= 20
UNET MaxInSteps= 0
UNET DtIC= 0
UNET DtMin= 0
UNET MaxCRTS= 20
UNET WFStab= 2
UNET SFStab= 1
UNET WFX= 1
UNET SFX= 1
UNET DSS MLevel= 4
UNET DZMax Abort= 100
UNET Convert EG Bridges= 0
UNET Use Existing IB Tables=-1
UNET Froude Reduction=False
UNET Froude Limit= 1
UNET Froude Power= 10
UNET Time Slicing=0,0, 5
UNET Junction Losses=0
Instantaneous Interval=1HOUR
Write IC File= 0
Write IC File at Sim End=0
Echo Input=False
Echo Parameters=False
Echo Output=False
Write Detailed= 0
WQ AD Non Conservative
WQ ULTIMATE=-1
WQ Max Comp Step=1HOUR
WQ Output Interval=15MIN
WQ Output Selected Increments= 0
WQ Output face flow=0
WQ Output face velocity=0
WQ Output face area=0
WQ Output face dispersion=0
WQ Output cell volume=0
WQ Output cell surface area=0
WQ Output cell continuity=0
WQ Output cumulative cell continuity=0
WQ Output face conc=0
WQ Output face dconc_dx=0
WQ Output face courant=0
WQ Output face peclet=0
WQ Output face adv mass=0
WQ Output face disp mass=0
WQ Output cell mass=0
WQ Output cell source sink temp=0
WQ Output cell source sink nsm=0
WQ Output MaxMinRange=-1
WQ Daily Max Min Mean=-1
WQ Daily Range=0
WQ Daily Time=0
WQ Create Restart=0
WQ Fixed Restart=0
WQ System Summary=0
WQ Use Fixed Temperature=0
Sorting and Armoring Iterations= 10
XS Update Threshold= 0.02
Hydraulics Update Threshold= 0.02
Energy Slope Method= 1
Volume Change Method= 0
XS Weighting Method= 0
Number of US Weighted Cross Sections= 1
Number of DS Weighted Cross Sections= 1
Upstream XS Weight=0.25
Main XS Weight=0.5
Downstream XS Weight=0.25
Number of DS XS's Weighted with US Boundary= 1
Upstream Boundary Weight= 1
Weight of XSs Associated with US Boundary= 0
Number of US XS's Weighted with DS Boundary= 1
Downstream Boundary Weight= 0.5
Weight of XSs Associated with DS Boundary= 0.5
Sediment Output Level= 4
Mass or Volume Output= 0
Output Increment Type= 1
Profile and TS Output Increment= 10
XS Output Flag= 0
XS Output Increment= 10
Disregard all LS=0
Disregard all Conn=0
Disregard all Breaches=0
Disregard all Pumps=0

--- Walnut23.f01 (steady flow) ---

Flow Title=Multiple
Number of Profiles=7
Profile Names=10-year,25-year,50-year,1pct_min,100-year,1pct_plu,500-year
River Rch & RM= Walnut23,Reach-1,4254
     580     789     962     584    1165    2325    1711
River Rch & RM= Walnut23,Reach-1,1790
     624     850    1038     630    1258    2509    1849
Boundary for River Rch & Prof#=Walnut23,Reach-1,1
Up Type=0
Dn Type=3
Dn Slope=0.007
Boundary for River Rch & Prof#=Walnut23,Reach-1,2
Up Type=0
Dn Type=3
Dn Slope=0.007
Boundary for River Rch & Prof#=Walnut23,Reach-1,3
Up Type=0
Dn Type=3
Dn Slope=0.007
Boundary for River Rch & Prof#=Walnut23,Reach-1,4
Up Type=0
Dn Type=3
Dn Slope=0.007
Boundary for River Rch & Prof#=Walnut23,Reach-1,5
Up Type=0
Dn Type=3
Dn Slope=0.007
Boundary for River Rch & Prof#=Walnut23,Reach-1,6
Up Type=0
Dn Type=3
Dn Slope=0.007
Boundary for River Rch & Prof#=Walnut23,Reach-1,7
Up Type=0
Dn Type=3
Dn Slope=0.007

--- Walnut23.g01 (geometry) ---

Geom Title=Existing Conditions

River Reach=Walnut23,Reach-1
Reach XY= 30
      2780476.00      6760811.00      2780617.75      6761057.77
      2780585.31      6761117.66      2780670.14      6761208.70
      2780723.67      6761316.97      2780729.83      6761409.42
      2780824.91      6761571.55      2780823.64      6761655.11
      2780783.56      6761711.00      2780823.54      6761766.86
      2780827.22      6762000.50      2780876.43      6762095.82
      2780875.34      6762395.84      2780833.56      6762461.00
      2780874.62      6762521.44      2780879.55      6762759.53
      2780973.94      6762866.86      2780975.67      6763045.97
      2780795.77      6763190.87      2780767.85      6763267.06
      2780695.94      6763341.15      2780629.17      6763369.34
      2780622.14      6763459.34      2780529.83      6763612.58
      2780522.18      6763709.42      2780446.55      6763841.56
      2780127.58      6763914.82      2779989.27      6763997.31
      2780068.38      6764107.61      2780026.00      6764211.00

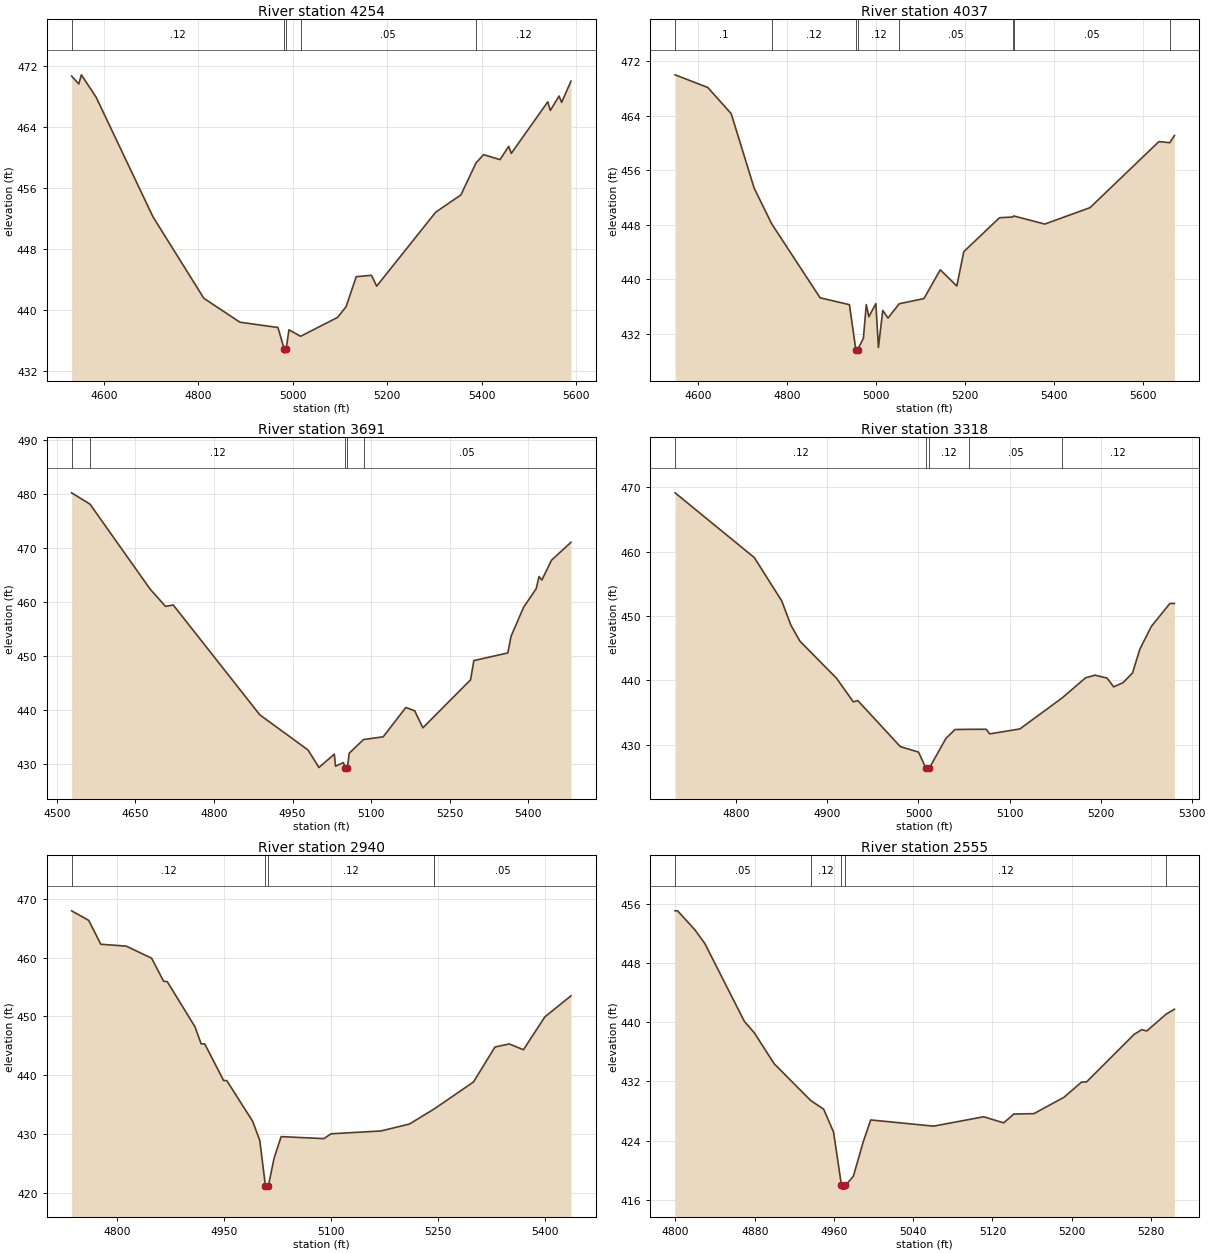
Type RM Length L Ch R = 1,4254,217,217,217
BEGIN DESCRIPTION:
Walnut23 10.0
END DESCRIPTION:
XS GIS Cut Line= 4
      2780071.03      6761012.49      2780385.27      6760905.51
      2780561.19      6760803.05      2780759.68      6760320.51
#Sta/Elev= 30
  4532.0  470.65  4547.3  469.62  4552.6  470.82  4584.0  467.87  4704.1  452.20
  4811.9  441.50  4888.3  438.36  4968.9  437.66  4982.2  434.80  4982.5  434.30
  4986.2  434.80  4992.1  437.36  5016.8  436.51  5095.1  438.99  5113.0  440.38
  5134.6  444.33  5166.9  444.51  5177.9  443.09  5302.9  452.80  5356.2  455.06
  5388.1  459.24  5404.2  460.35  5438.9  459.69  5457.5  461.43  5462.9  460.51
  5540.2  467.28  5545.6  466.15  5564.1  468.04  5569.5  467.20  5589.3  469.99
#Mann=5,-1,0
  4532.0    0.12       0  4982.2    0.07       0  4986.2    0.12       0
  5016.8    0.05       0  5388.1    0.12       0
Bank Sta=4982.2,4986.2
Exp/Cntr=0.3,0.1

Type RM Length L Ch R = 1,4037,346,346,346
BEGIN DESCRIPTION:
Walnut23 9.0
END DESCRIPTION:
XS GIS Cut Line= 3
      2780194.68      6761239.84      2780565.79      6761042.58
      2781172.60      6760689.16
#Sta/Elev= 30
  4548.5  470.03  4622.1  468.17  4674.6  464.33  4726.3  453.39  4765.7  448.16
  4874.5  437.31  4940.4  436.30  4954.8  429.69  4955.0  429.19  4958.8  429.69
  4971.8  431.37  4978.3  436.32  4984.1  434.53  4999.8  436.46  5005.6  430.02
  5015.3  435.46  5027.1  434.34  5052.4  436.44  5107.9  437.19  5144.6  441.42
  5181.8  439.04  5197.5  444.08  5277.8  449.06  5307.0  449.16  5309.8  449.32
  5379.5  448.13  5481.3  450.54  5636.0  460.23  5660.6  460.07  5671.0  461.13
#Mann=8,-1,0
  4548.5     0.1       0  4765.7    0.12       0  4954.8    0.07       0
  4958.8    0.12       0  5052.4    0.05       0  5307.0    0.12       0
  5309.8    0.05       0  5660.6    0.12       0
Bank Sta=4954.8,4958.8
Exp/Cntr=0.3,0.1

Type RM Length L Ch R = 1,3691,373,373,373
BEGIN DESCRIPTION:
Walnut23 8.0
END DESCRIPTION:
XS GIS Cut Line= 3
      2780335.08      6761580.84      2780742.97      6761283.28
      2781157.49      6761112.79
#Sta/Elev= 30
  4528.2  480.15  4563.3  478.05  4678.1  462.35  4707.5  459.16  4722.1  459.43
  4887.4  439.12  4979.4  432.63  5000.2  429.39  5029.6  431.86  5031.9  429.62
  5047.0  430.30  5050.4  429.22  5050.7  428.72  5054.4  429.22  5058.0  432.03
  5085.4  434.56  5122.9  435.06  5166.1  440.48  5183.0  439.87  5198.6  436.72
  5289.7  445.60  5295.9  449.15  5360.7  450.56  5366.9  453.63  5390.9  459.01
  5414.8  462.41  5420.3  464.68  5425.7  464.03  5444.2  467.70  5481.3  471.01
#Mann=5,-1,0
  4528.2    0.05       0  4563.3    0.12       0  5050.4    0.07       0
  5054.4    0.12       0  5085.4    0.05       0
Bank Sta=5050.4,5054.4
Exp/Cntr=0.3,0.1

Type RM Length L Ch R = 1,3318,378,378,378
BEGIN DESCRIPTION:
Walnut23 7.0
END DESCRIPTION:
XS GIS Cut Line= 3
      2780559.13      6761657.70      2780900.10      6761637.64
      2781100.67      6761587.50
#Sta/Elev= 30
  4732.8  469.16  4819.8  459.09  4849.9  452.35  4859.9  448.60  4869.9  446.09
  4910.0  440.34  4928.5  436.66  4933.5  436.85  4980.1  429.70  5000.1  428.85
  5008.1  426.39  5008.4  425.89  5012.1  426.39  5030.2  430.99  5040.2  432.36
  5055.7  432.39  5074.4  432.40  5078.2  431.68  5111.4  432.45  5157.7  437.26
  5183.5  440.40  5193.8  440.81  5207.1  440.36  5214.4  438.99  5224.7  439.65
  5235.1  441.16  5243.1  444.84  5255.7  448.38  5276.1  451.96  5281.1  451.96
#Mann=5,-1,0
  4732.8    0.12       0  5008.1    0.07       0  5012.1    0.12       0
  5055.7    0.05       0  5157.7    0.12       0
Bank Sta=5008.1,5012.1
Exp/Cntr=0.3,0.1

Type RM Length L Ch R = 1,2940,385,385,385
BEGIN DESCRIPTION:
Walnut23 6.0
END DESCRIPTION:
XS GIS Cut Line= 3
      2780565.77      6761951.89      2780779.75      6761992.01
      2781262.73      6761988.68
#Sta/Elev= 30
  4735.9  467.98  4759.9  466.35  4776.8  462.29  4812.5  461.97  4848.1  459.92
  4865.0  455.99  4870.1  455.92  4909.1  448.22  4917.6  445.34  4922.7  445.32
  4949.2  439.08  4953.6  439.08  4989.9  432.16  4999.9  428.90  5007.9  421.10
  5008.1  420.60  5011.9  421.10  5019.9  425.82  5029.9  429.54  5089.9  429.20
  5099.9  430.02  5169.9  430.50  5209.9  431.68  5244.9  434.27  5299.9  438.85
  5329.9  444.79  5349.9  445.32  5369.9  444.33  5399.9  449.92  5436.6  453.51
#Mann=4,-1,0
  4735.9    0.12       0  5007.9    0.07       0  5011.9    0.12       0
  5244.9    0.05       0
Bank Sta=5007.9,5011.9
Exp/Cntr=0.3,0.1

Type RM Length L Ch R = 1,2555,378,378,378
BEGIN DESCRIPTION:
Walnut23 5.0
END DESCRIPTION:
XS GIS Cut Line= 3
      2780675.95      6762361.00      2780876.00      6762361.00
      2781176.02      6762311.00
#Sta/Elev= 30
  4799.6  455.08  4802.1  455.08  4819.6  452.51  4829.6  450.66  4869.6  440.11
  4879.6  438.58  4899.6  434.40  4936.6  429.41  4949.6  428.25  4959.6  425.15
  4967.6  417.93  4967.9  417.43  4971.4  417.43  4971.6  417.93  4979.6  419.17
  4989.6  423.84  4997.1  426.79  5060.5  425.95  5111.2  427.22  5131.4  426.39
  5141.6  427.59  5161.9  427.64  5192.3  429.86  5210.0  431.91  5215.1  431.94
  5263.2  438.38  5270.8  439.00  5275.9  438.83  5295.5  441.11  5303.8  441.77
#Mann=5,-1,0
  4799.6    0.05       0  4936.6    0.12       0  4967.6    0.07       0
  4971.6    0.12       0  5295.5    0.05       0
Bank Sta=4967.6,4971.6
Exp/Cntr=0.3,0.1

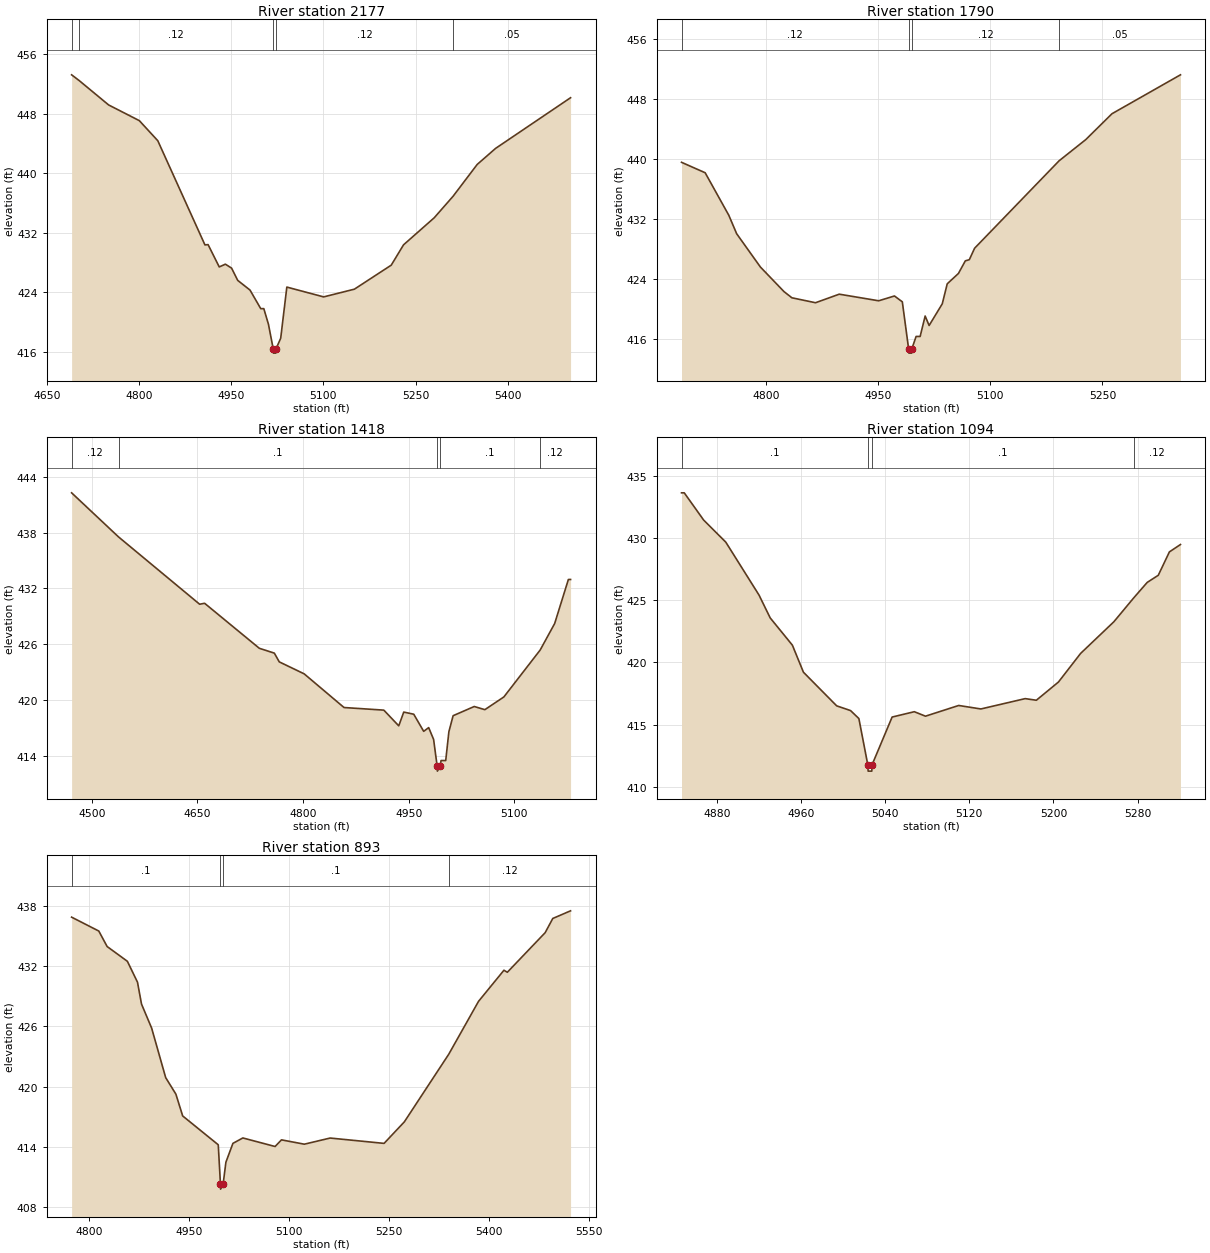
Type RM Length L Ch R = 1,2177,387,387,387
BEGIN DESCRIPTION:
Walnut23 4.0
END DESCRIPTION:
XS GIS Cut Line= 3
      2780565.83      6762694.05      2780876.00      6762711.00
      2781378.12      6762704.08
#Sta/Elev= 30
  4689.8  453.21  4701.8  452.46  4750.1  449.16  4800.1  447.05  4830.2  444.35
  4907.0  430.34  4912.1  430.38  4930.3  427.38  4940.3  427.75  4950.4  427.22
  4960.4  425.57  4980.4  424.27  4997.9  421.77  5002.9  421.77  5010.4  419.69
  5018.4  416.29  5018.7  415.79  5022.2  415.79  5022.4  416.29  5030.4  417.79
  5040.4  424.67  5100.4  423.35  5150.5  424.39  5210.5  427.62  5230.5  430.35
  5280.5  433.99  5311.1  436.87  5350.5  441.16  5380.5  443.32  5502.6  450.13
#Mann=5,-1,0
  4689.8    0.05       0  4701.8    0.12       0  5018.4    0.07       0
  5022.4    0.12       0  5311.1    0.05       0
Bank Sta=5018.4,5022.4
Exp/Cntr=0.3,0.1

Type RM Length L Ch R = 1,1790,372,372,372
BEGIN DESCRIPTION:
Walnut23 3.0
END DESCRIPTION:
XS GIS Cut Line= 3
      2780676.05      6762961.02      2780976.00      6763061.00
      2781301.18      6763192.13
#Sta/Elev= 30
  4687.5  439.59  4719.1  438.20  4750.7  432.54  4761.2  430.08  4792.9  425.65
  4824.5  422.37  4835.0  421.55  4866.6  420.89  4898.3  422.03  4951.0  421.15
  4972.1  421.79  4982.6  421.01  4991.1  414.68  4991.4  414.18  4994.9  414.18
  4995.1  414.68  5001.0  416.40  5006.4  416.40  5013.1  419.12  5018.4  417.86
  5036.0  420.75  5042.6  423.41  5057.6  424.79  5066.8  426.47  5072.1  426.62
  5079.2  428.15  5192.1  439.79  5227.8  442.62  5262.8  446.06  5354.3  451.24
#Mann=4,-1,0
  4687.5    0.12       0  4991.1    0.07       0  4995.1    0.12       0
  5192.1    0.05       0
Bank Sta=4991.1,4995.1
Exp/Cntr=0.3,0.1

Type RM Length L Ch R = 1,1418,324,324,324
BEGIN DESCRIPTION:
Walnut23 2.0
END DESCRIPTION:
XS GIS Cut Line= 3
      2780351.82      6762938.08      2780726.00      6763311.00
      2780876.04      6763411.03
#Sta/Elev= 30
  4471.3  442.28  4537.9  437.54  4653.1  430.30  4660.2  430.40  4737.9  425.56
  4759.2  425.04  4766.2  424.10  4801.6  422.81  4858.2  419.19  4914.7  418.91
  4935.9  417.22  4943.0  418.70  4957.2  418.47  4971.3  416.63  4978.4  417.03
  4985.4  415.76  4990.5  412.85  4990.8  412.35  4994.5  412.85  4996.0  413.49
  5002.6  413.49  5007.1  416.59  5013.1  418.31  5043.1  419.30  5058.2  418.96
  5085.2  420.33  5136.7  425.37  5157.3  428.22  5176.8  432.96  5179.9  432.96
#Mann=5,-1,0
  4471.3    0.12       0  4537.9     0.1       0  4990.5    0.07       0
  4994.5     0.1       0  5136.7    0.12       0
Bank Sta=4990.5,4994.5
Exp/Cntr=0.3,0.1

Type RM Length L Ch R = 1,1094,201,201,201
BEGIN DESCRIPTION:
Walnut23 1.0
END DESCRIPTION:
XS GIS Cut Line= 3
      2780426.05      6763511.02      2780576.00      6763561.00
      2780876.01      6763661.00
#Sta/Elev= 30
  4846.5  433.61  4849.1  433.61  4867.5  431.43  4888.6  429.65  4920.2  425.40
  4930.8  423.57  4951.9  421.38  4962.4  419.21  4994.0  416.51  5007.2  416.13
  5015.1  415.49  5023.6  411.77  5023.9  411.27  5027.4  411.27  5027.6  411.77
  5046.7  415.61  5067.8  416.04  5078.4  415.68  5110.0  416.54  5131.1  416.26
  5173.2  417.09  5183.8  416.96  5204.8  418.42  5225.9  420.72  5257.5  423.26
  5276.5  425.19  5289.2  426.42  5299.7  426.99  5310.3  428.87  5320.8  429.46
#Mann=4,-1,0
  4846.5     0.1       0  5023.6    0.07       0  5027.6     0.1       0
  5276.5    0.12       0
Bank Sta=5023.6,5027.6
Exp/Cntr=0.3,0.1

Type RM Length L Ch R = 1,893,0,0,0
BEGIN DESCRIPTION:
Walnut23 0.5
END DESCRIPTION:
XS GIS Cut Line= 4
      2780355.18      6763576.62      2780445.62      6763718.12
      2780614.62      6763774.46      2781012.34      6763710.57
#Sta/Elev= 30
  4774.0  436.86  4814.8  435.48  4827.3  433.94  4857.7  432.47  4872.9  430.39
  4878.9  428.22  4894.1  425.83  4915.2  420.90  4930.5  419.26  4940.7  417.09
  4994.1  414.22  4997.4  410.31  4997.6  409.81  5001.4  410.31  5005.6  412.49
  5016.1  414.36  5031.0  414.90  5079.4  414.05  5089.0  414.71  5123.3  414.28
  5162.0  414.89  5243.0  414.36  5273.4  416.50  5340.0  423.22  5384.8  428.49
  5422.9  431.58  5428.0  431.38  5484.8  435.32  5496.2  436.73  5522.9  437.49
#Mann=4,-1,0
  4774.0     0.1       0  4997.4    0.07       0  5001.4     0.1       0
  5340.0    0.12       0
Bank Sta=4997.4,5001.4
Exp/Cntr=0.3,0.1

Chan Stop Cuts=-1