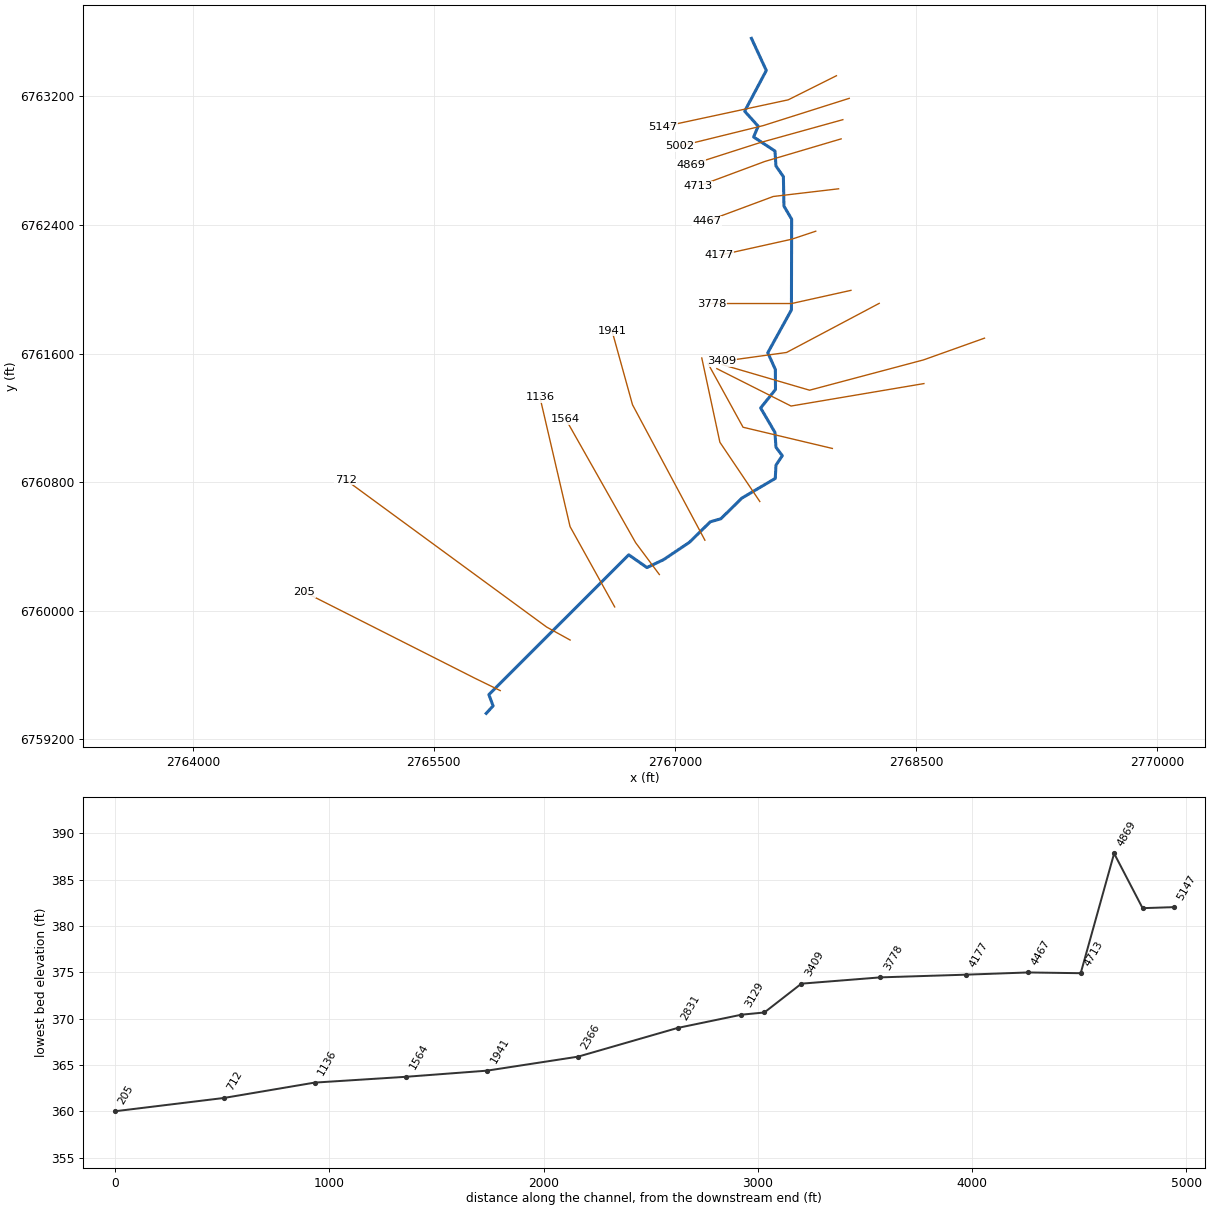
--- Walnut25.prj (project) ---

Proj Title=Walnut25 Base Level Engineering
Current Plan=p01
Default Exp/Contr=0.3,0.1
English Units
Geom File=g01
Flow File=f01
Plan File=p01
BEGIN DESCRIPTION:
Walnut25
END DESCRIPTION:

--- Walnut25.p01 (plan) ---

Plan Title=Multiple Run
Short Identifier=Multiple
Geom File=g01
Flow File=f01
Subcritical Flow
K Sum by GR= 0
Std Step Tol= 0.01
Critical Tol= 0.01
Num of Std Step Trials= 20
Max Error Tol= 0.3
Flow Tol Ratio= 0.001
Split Flow NTrial= 30
Split Flow Tol= 0.02
Split Flow Ratio= 0.02
Log Output Level= 0
Friction Slope Method= 1
Unsteady Friction Slope Method= 2
Unsteady Bridges Friction Slope Method= 1
Parabolic Critical Depth
Global Vel Dist=  1 , 1 , 1
Global Log Level= 0
CheckData=True
Encroach Param= -1, 0, 0, 0
BEGIN DESCRIPTION:
Multiple Run
END DESCRIPTION:

--- Walnut25.f01 (steady flow) ---

Flow Title=Multiple
Number of Profiles=7
Profile Names=10-year,25-year,50-year,1pct_min,100-year,1pct_plu,500-year
River Rch & RM= Walnut25,Reach-1,5147
     683     937    1147     699    1394    2782    2063
River Rch & RM= Walnut25,Reach-1,712
     852    1173    1441     879    1753    3498    2601
Boundary for River Rch & Prof#=Walnut25,Reach-1,1
Up Type=0
Dn Type=3
Dn Slope=0.005
Boundary for River Rch & Prof#=Walnut25,Reach-1,2
Up Type=0
Dn Type=3
Dn Slope=0.005
Boundary for River Rch & Prof#=Walnut25,Reach-1,3
Up Type=0
Dn Type=3
Dn Slope=0.005
Boundary for River Rch & Prof#=Walnut25,Reach-1,4
Up Type=0
Dn Type=3
Dn Slope=0.005
Boundary for River Rch & Prof#=Walnut25,Reach-1,5
Up Type=0
Dn Type=3
Dn Slope=0.005
Boundary for River Rch & Prof#=Walnut25,Reach-1,6
Up Type=0
Dn Type=3
Dn Slope=0.005
Boundary for River Rch & Prof#=Walnut25,Reach-1,7
Up Type=0
Dn Type=3
Dn Slope=0.005

--- Walnut25.g01 (geometry) ---

Geom Title=Existing Conditions

River Reach=Walnut25,Reach-1
Reach XY= 30
      2767476.00      6763561.00      2767568.50      6763361.00
      2767433.80      6763107.59      2767517.96      6763014.32
      2767489.51      6762947.32      2767622.47      6762859.72
      2767628.36      6762766.98      2767674.78      6762700.50
      2767678.26      6762516.94      2767726.20      6762436.08
      2767724.80      6761871.50      2767577.80      6761604.89
      2767624.77      6761500.50      2767625.62      6761376.16
      2767533.30      6761261.08      2767622.18      6761109.41
      2767628.55      6761016.89      2767667.93      6760964.30
      2767628.59      6760905.02      2767624.27      6760822.87
      2767416.32      6760700.22      2767285.68      6760571.78
      2767219.95      6760552.84      2767089.21      6760424.63
      2766928.28      6760316.82      2766825.91      6760268.31
      2766712.67      6760347.58      2765842.35      6759477.67
      2765868.48      6759407.67      2765826.00      6759361.00

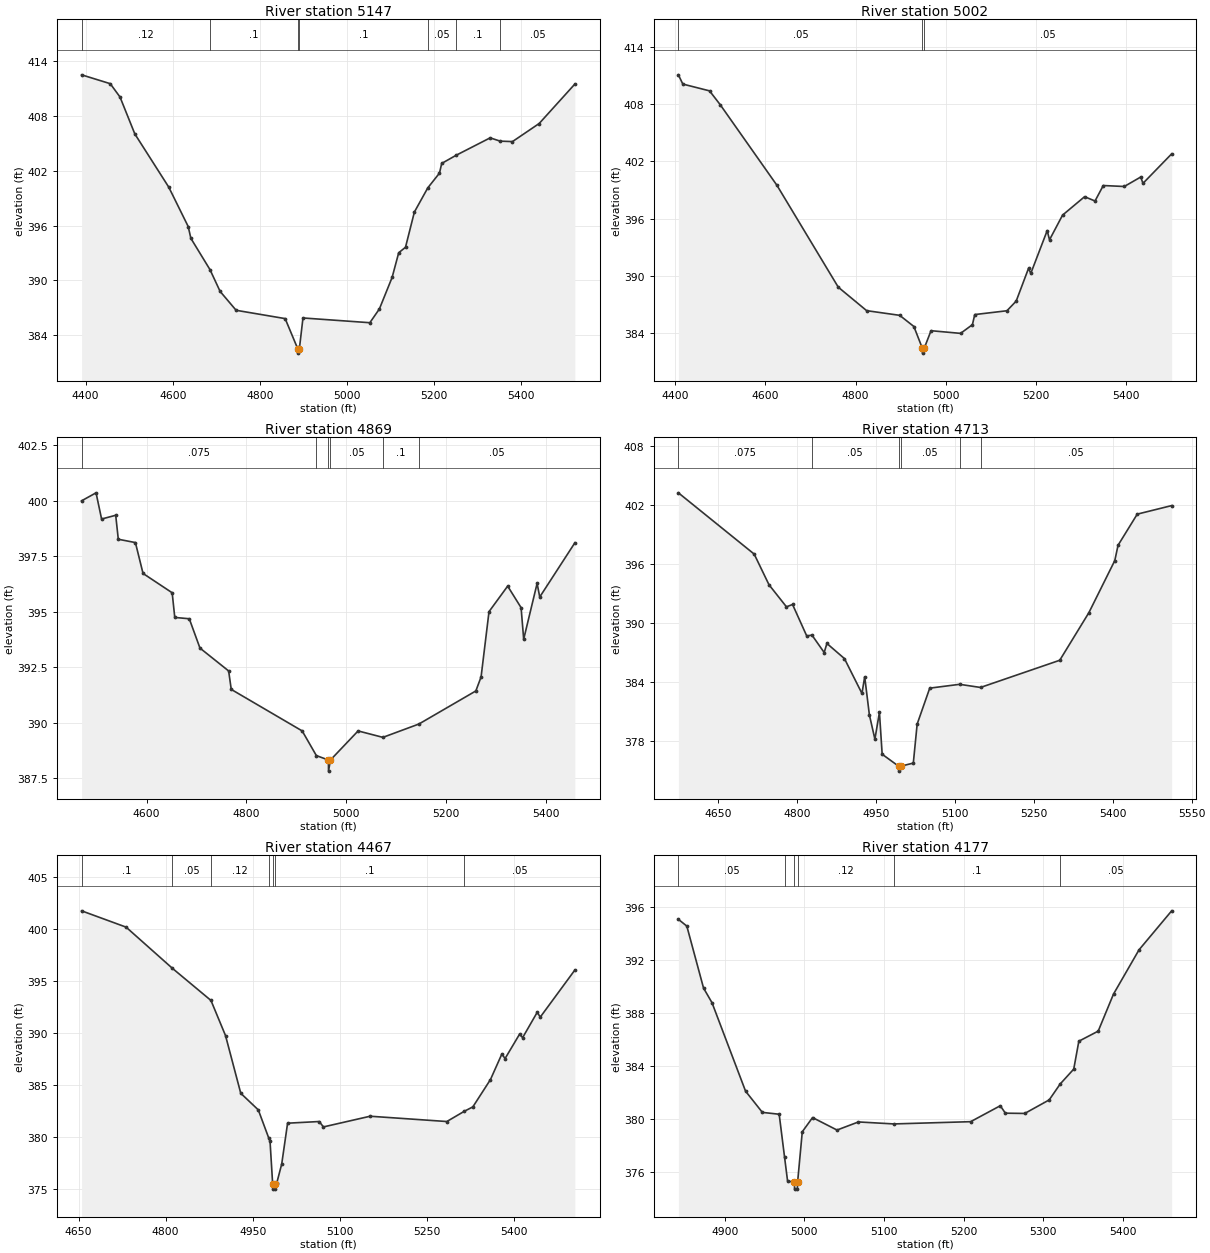
Type RM Length L Ch R = 1,5147,145,145,145
BEGIN DESCRIPTION:
Walnut25 11.0
END DESCRIPTION:
XS GIS Cut Line= 3
      2768004.87      6763328.38      2767704.89      6763178.39
      2766925.97      6763010.99
#Sta/Elev= 30
  4390.9  412.50  4456.7  411.53  4479.1  410.07  4513.1  406.03  4590.9  400.21
  4635.6  395.89  4641.7  394.60  4685.6  391.17  4708.8  388.79  4745.6  386.72
  4858.1  385.81  4886.8  382.53  4887.1  382.03  4890.8  382.53  4899.0  385.88
  5052.5  385.36  5074.4  386.87  5103.6  390.32  5118.7  393.02  5134.3  393.62
  5154.7  397.48  5185.4  400.12  5212.3  401.74  5217.4  402.80  5250.8  403.70
  5328.6  405.60  5351.5  405.24  5379.8  405.19  5441.1  407.17  5523.0  411.49
#Mann=7,-1,0
  4390.9    0.12       0  4685.6     0.1       0  4886.8    0.07       0
  4890.8     0.1       0  5185.4    0.05       0  5250.8     0.1       0
  5351.5    0.05       0
Bank Sta=4886.8,4890.8
Exp/Cntr=0.3,0.1

Type RM Length L Ch R = 1,5002,133,133,133
BEGIN DESCRIPTION:
Walnut25 10.0
END DESCRIPTION:
XS GIS Cut Line= 3
      2768084.54      6763187.68      2767548.25      6763017.76
      2767030.76      6762890.38
#Sta/Elev= 30
  4406.6  411.08  4416.5  410.11  4475.8  409.40  4499.5  407.95  4625.4  399.51
  4761.7  388.83  4824.7  386.37  4898.1  385.88  4929.6  384.71  4948.5  382.42
  4948.8  381.92  4952.5  382.42  4967.7  384.27  5033.3  383.99  5059.6  384.90
  5064.8  385.96  5136.3  386.36  5156.8  387.37  5184.2  390.80  5189.3  390.28
  5225.7  394.76  5230.8  393.79  5259.8  396.38  5308.7  398.31  5331.9  397.86
  5350.2  399.48  5396.9  399.38  5433.3  400.37  5438.4  399.71  5502.1  402.80
#Mann=3,-1,0
  4406.6    0.05       0  4948.5    0.03       0  4952.5    0.05       0
Bank Sta=4948.5,4952.5
Exp/Cntr=0.3,0.1

Type RM Length L Ch R = 1,4869,156,156,156
BEGIN DESCRIPTION:
Walnut25 9.0
END DESCRIPTION:
XS GIS Cut Line= 3
      2768044.68      6763054.92      2767526.00      6762911.00
      2767096.96      6762773.53
#Sta/Elev= 30
  4469.7  400.00  4498.7  400.36  4509.8  399.18  4538.1  399.35  4543.3  398.27
  4577.6  398.12  4592.9  396.73  4651.3  395.86  4656.5  394.75  4685.6  394.69
  4707.0  393.37  4764.5  392.34  4769.7  391.51  4911.9  389.64  4940.3  388.53
  4964.5  388.33  4964.7  387.83  4968.5  388.33  5024.0  389.64  5073.7  389.35
  5145.8  389.95  5260.0  391.44  5270.5  392.07  5286.4  395.01  5323.8  396.16
  5350.7  395.19  5355.9  393.77  5382.8  396.28  5388.1  395.67  5458.5  398.11
#Mann=6,-1,0
  4469.7   0.075       0  4940.3    0.05       0  4964.5    0.05       0
  4968.5    0.05       0  5073.7     0.1       0  5145.8    0.05       0
Bank Sta=4964.5,4968.5
Exp/Cntr=0.3,0.1

Type RM Length L Ch R = 1,4713,246,246,246
BEGIN DESCRIPTION:
Walnut25 8.5
END DESCRIPTION:
XS GIS Cut Line= 3
      2768034.09      6762935.46      2767558.87      6762794.75
      2767144.68      6762640.76
#Sta/Elev= 30
  4574.5  403.24  4718.6  397.00  4746.7  393.88  4779.9  391.63  4791.5  391.87
  4818.4  388.67  4828.4  388.75  4851.6  386.98  4856.8  387.90  4890.1  386.36
  4923.4  382.81  4928.6  384.51  4937.5  380.63  4948.0  378.15  4956.6  380.89
  4961.8  376.62  4993.1  375.40  4993.3  374.90  4997.1  375.40  5021.0  375.72
  5028.3  379.69  5052.2  383.35  5109.0  383.74  5148.7  383.42  5299.3  386.19
  5354.7  391.04  5403.9  396.34  5410.1  397.90  5446.6  401.07  5512.0  401.94
#Mann=6,-1,0
  4574.5   0.075       0  4828.4    0.05       0  4993.1    0.04       0
  4997.1    0.05       0  5109.0     0.1       0  5148.7    0.05       0
Bank Sta=4993.1,4997.1
Exp/Cntr=0.3,0.1

Type RM Length L Ch R = 1,4467,290,290,290
BEGIN DESCRIPTION:
Walnut25 8.0
END DESCRIPTION:
XS GIS Cut Line= 3
      2768018.13      6762624.84      2767611.97      6762577.05
      2767199.43      6762423.67
#Sta/Elev= 30
  4655.3  401.78  4731.9  400.21  4811.7  396.24  4878.0  393.15  4903.1  389.76
  4929.3  384.21  4959.5  382.61  4977.4  379.91  4979.7  379.58  4984.2  375.48
  4984.4  374.98  4987.9  374.98  4988.2  375.48  4991.2  375.55  4999.8  377.40
  5009.9  381.33  5064.3  381.49  5071.6  380.97  5152.0  382.00  5284.0  381.49
  5314.2  382.48  5328.8  382.90  5359.1  385.53  5378.8  388.00  5384.2  387.55
  5409.2  389.90  5414.5  389.57  5439.5  392.00  5444.9  391.55  5504.4  396.08
#Mann=7,-1,0
  4655.3     0.1       0  4811.7    0.05       0  4878.0    0.12       0
  4977.4     0.1       0  4984.2    0.07       0  4988.2     0.1       0
  5314.2    0.05       0
Bank Sta=4984.2,4988.2
Exp/Cntr=0.3,0.1

Type RM Length L Ch R = 1,4177,399,399,399
BEGIN DESCRIPTION:
Walnut25 7.0
END DESCRIPTION:
XS GIS Cut Line= 3
      2767876.01      6762361.00      2767726.00      6762311.00
      2767276.00      6762211.00
#Sta/Elev= 30
  4841.9  395.06  4852.5  394.55  4873.5  389.88  4884.1  388.78  4926.2  382.12
  4947.3  380.52  4968.4  380.38  4975.1  377.18  4978.9  375.37  4987.5  375.24
  4987.7  374.74  4991.2  374.74  4991.5  375.24  4997.4  379.06  5010.3  380.13
  5041.0  379.19  5067.9  379.80  5112.3  379.65  5208.7  379.82  5245.9  381.02
  5252.3  380.46  5276.6  380.44  5307.3  381.46  5321.1  382.66  5338.1  383.78
  5344.5  385.88  5368.8  386.64  5388.0  389.43  5420.0  392.76  5461.0  395.70
#Mann=6,-1,0
  4841.9    0.05       0  4975.1    0.12       0  4987.5    0.07       0
  4991.5    0.12       0  5112.3     0.1       0  5321.1    0.05       0
Bank Sta=4987.5,4991.5
Exp/Cntr=0.3,0.1

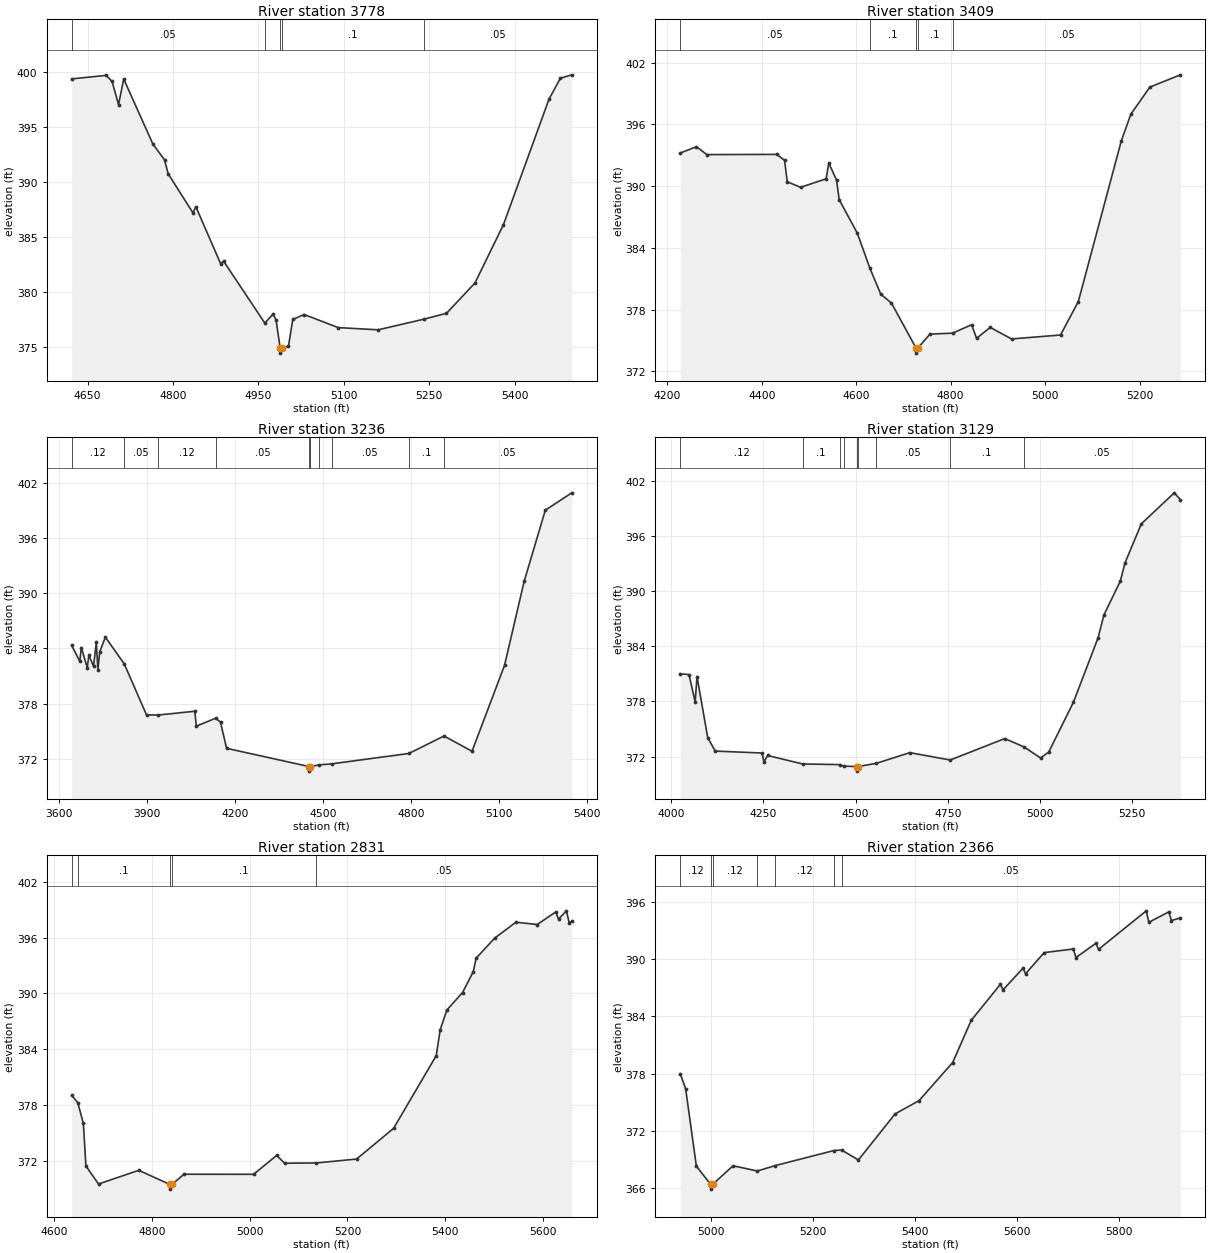
Type RM Length L Ch R = 1,3778,369,369,369
BEGIN DESCRIPTION:
Walnut25 6.0
END DESCRIPTION:
XS GIS Cut Line= 3
      2768095.20      6761992.99      2767726.00      6761911.00
      2767225.99      6761911.00
#Sta/Elev= 30
  4622.2  399.38  4682.8  399.70  4693.1  399.15  4704.5  397.05  4713.6  399.37
  4764.8  393.46  4785.3  392.02  4791.6  390.76  4835.2  387.20  4840.3  387.76
  4883.8  382.58  4889.0  382.81  4961.4  377.18  4976.1  378.02  4981.2  377.43
  4988.2  374.95  4988.4  374.45  4992.2  374.95  5002.9  375.07  5010.4  377.51
  5030.4  377.96  5090.4  376.77  5160.4  376.57  5240.1  377.53  5280.4  378.07
  5330.4  380.83  5380.4  386.13  5460.4  397.54  5480.4  399.44  5500.4  399.75
#Mann=5,-1,0
  4622.2    0.05       0  4961.4     0.1       0  4988.2    0.07       0
  4992.2     0.1       0  5240.1    0.05       0
Bank Sta=4988.2,4992.2
Exp/Cntr=0.3,0.1

Type RM Length L Ch R = 1,3409,173,173,173
BEGIN DESCRIPTION:
Walnut25 5.0
END DESCRIPTION:
XS GIS Cut Line= 3
      2768271.08      6761912.11      2767694.66      6761606.54
      2767291.88      6761550.98
#Sta/Elev= 30
  4227.5  393.21  4261.7  393.83  4283.7  393.06  4432.0  393.08  4448.3  392.49
  4454.0  390.42  4482.2  389.88  4536.3  390.71  4542.0  392.23  4558.3  390.59
  4564.0  388.68  4602.3  385.43  4628.8  382.04  4652.0  379.50  4674.7  378.63
  4726.6  374.27  4726.8  373.77  4730.6  374.27  4756.2  375.62  4804.0  375.71
  4844.4  376.53  4854.9  375.21  4883.7  376.27  4929.0  375.15  5032.6  375.53
  5070.3  378.78  5161.2  394.37  5181.5  396.98  5221.8  399.62  5286.5  400.81
#Mann=5,-1,0
  4227.5    0.05       0  4628.8     0.1       0  4726.6    0.04       0
  4730.6     0.1       0  4804.0    0.05       0
Bank Sta=4726.6,4730.6
Exp/Cntr=0.3,0.1

Type RM Length L Ch R = 1,3236,107,107,107
BEGIN DESCRIPTION:
Walnut25 4.8
END DESCRIPTION:
XS GIS Cut Line= 4
      2768926.10      6761695.62      2768546.49      6761560.23
      2767837.63      6761371.73      2767293.39      6761531.02
#Sta/Elev= 30
  3643.4  384.33  3671.0  382.60  3676.4  384.10  3696.5  381.89  3701.9  383.27
  3717.8  382.06  3727.4  384.66  3732.7  381.67  3739.1  383.64  3758.2  385.23
  3822.4  382.33  3898.3  376.78  3938.2  376.76  4062.7  377.17  4067.9  375.55
  4134.0  376.41  4150.4  375.98  4171.1  373.14  4451.8  371.16  4452.1  370.66
  4455.8  371.16  4486.6  371.34  4528.7  371.45  4792.1  372.58  4911.8  374.48
  5007.2  372.82  5117.9  382.16  5184.7  391.29  5256.8  399.03  5347.0  400.92
#Mann=10,-1,0
  3643.4    0.12       0  3822.4    0.05       0  3938.2    0.12       0
  4134.0    0.05       0  4451.8    0.04       0  4455.8    0.05       0
  4486.6     0.1       0  4528.7    0.05       0  4792.1     0.1       0
  4911.8    0.05       0
Bank Sta=4451.8,4455.8
Exp/Cntr=0.3,0.1

Type RM Length L Ch R = 1,3129,298,298,298
BEGIN DESCRIPTION:
Walnut25 4.6
END DESCRIPTION:
XS GIS Cut Line= 3
      2768549.26      6761412.96      2767722.44      6761273.21
      2767260.80      6761505.86
#Sta/Elev= 30
  4024.7  381.01  4048.3  380.92  4065.0  377.95  4070.0  380.71  4099.0  374.07
  4119.3  372.60  4246.3  372.39  4251.3  371.41  4261.3  372.12  4356.4  371.20
  4456.4  371.13  4467.8  370.96  4502.7  370.92  4502.9  370.42  4506.7  370.92
  4556.3  371.27  4646.7  372.43  4756.2  371.63  4904.1  373.96  4956.6  373.05
  5001.0  371.85  5023.3  372.50  5090.2  377.91  5157.2  384.94  5172.8  387.40
  5217.6  391.11  5229.7  393.04  5274.3  397.32  5363.5  400.69  5380.2  399.94
#Mann=9,-1,0
  4024.7    0.12       0  4356.4     0.1       0  4456.4    0.05       0
  4467.8    0.12       0  4502.7    0.04       0  4506.7    0.12       0
  4556.3    0.05       0  4756.2     0.1       0  4956.6    0.05       0
Bank Sta=4502.7,4506.7
Exp/Cntr=0.3,0.1

Type RM Length L Ch R = 1,2831,465,465,465
BEGIN DESCRIPTION:
Walnut25 4.3
END DESCRIPTION:
XS GIS Cut Line= 3
      2767979.42      6761009.31      2767423.83      6761141.26
      2767206.23      6761536.59
#Sta/Elev= 30
  4636.3  379.06  4648.8  378.27  4660.2  376.05  4665.4  371.48  4691.2  369.54
  4773.4  371.01  4837.3  369.49  4837.6  368.99  4841.3  369.49  4865.9  370.59
  5008.1  370.58  5055.4  372.61  5071.5  371.77  5136.7  371.80  5218.7  372.22
  5294.4  375.52  5381.5  383.32  5389.7  386.12  5403.3  388.22  5435.3  390.10
  5457.3  392.34  5463.0  393.78  5500.8  395.93  5544.4  397.65  5588.0  397.40
  5625.8  398.75  5631.5  397.98  5647.6  398.87  5653.3  397.60  5658.6  397.73
#Mann=5,-1,0
  4636.3    0.12       0  4648.8     0.1       0  4837.3    0.07       0
  4841.3     0.1       0  5136.7    0.05       0
Bank Sta=4837.3,4841.3
Exp/Cntr=0.3,0.1

Type RM Length L Ch R = 1,2366,425,425,425
BEGIN DESCRIPTION:
Walnut25 4.0
END DESCRIPTION:
XS GIS Cut Line= 3
      2767528.13      6760679.18      2767279.66      6761048.00
      2767167.07      6761572.14
#Sta/Elev= 30
  4939.6  377.96  4950.1  376.42  4971.1  368.30  4999.1  366.39  4999.3  365.89
  5003.1  366.39  5043.1  368.34  5090.8  367.79  5125.1  368.35  5241.3  369.94
  5255.9  369.99  5288.9  368.95  5360.9  373.78  5407.8  375.17  5473.7  379.16
  5510.1  383.58  5567.4  387.37  5572.5  386.78  5611.6  389.05  5616.8  388.48
  5653.3  390.69  5710.4  391.07  5715.5  390.17  5754.7  391.67  5759.8  391.03
  5853.4  395.07  5858.5  393.87  5897.7  394.96  5902.8  394.05  5920.4  394.33
#Mann=7,-1,0
  4939.6    0.12       0  4999.1    0.07       0  5003.1    0.12       0
  5090.8     0.1       0  5125.1    0.12       0  5241.3     0.1       0
  5255.9    0.05       0
Bank Sta=4999.1,5003.1
Exp/Cntr=0.3,0.1

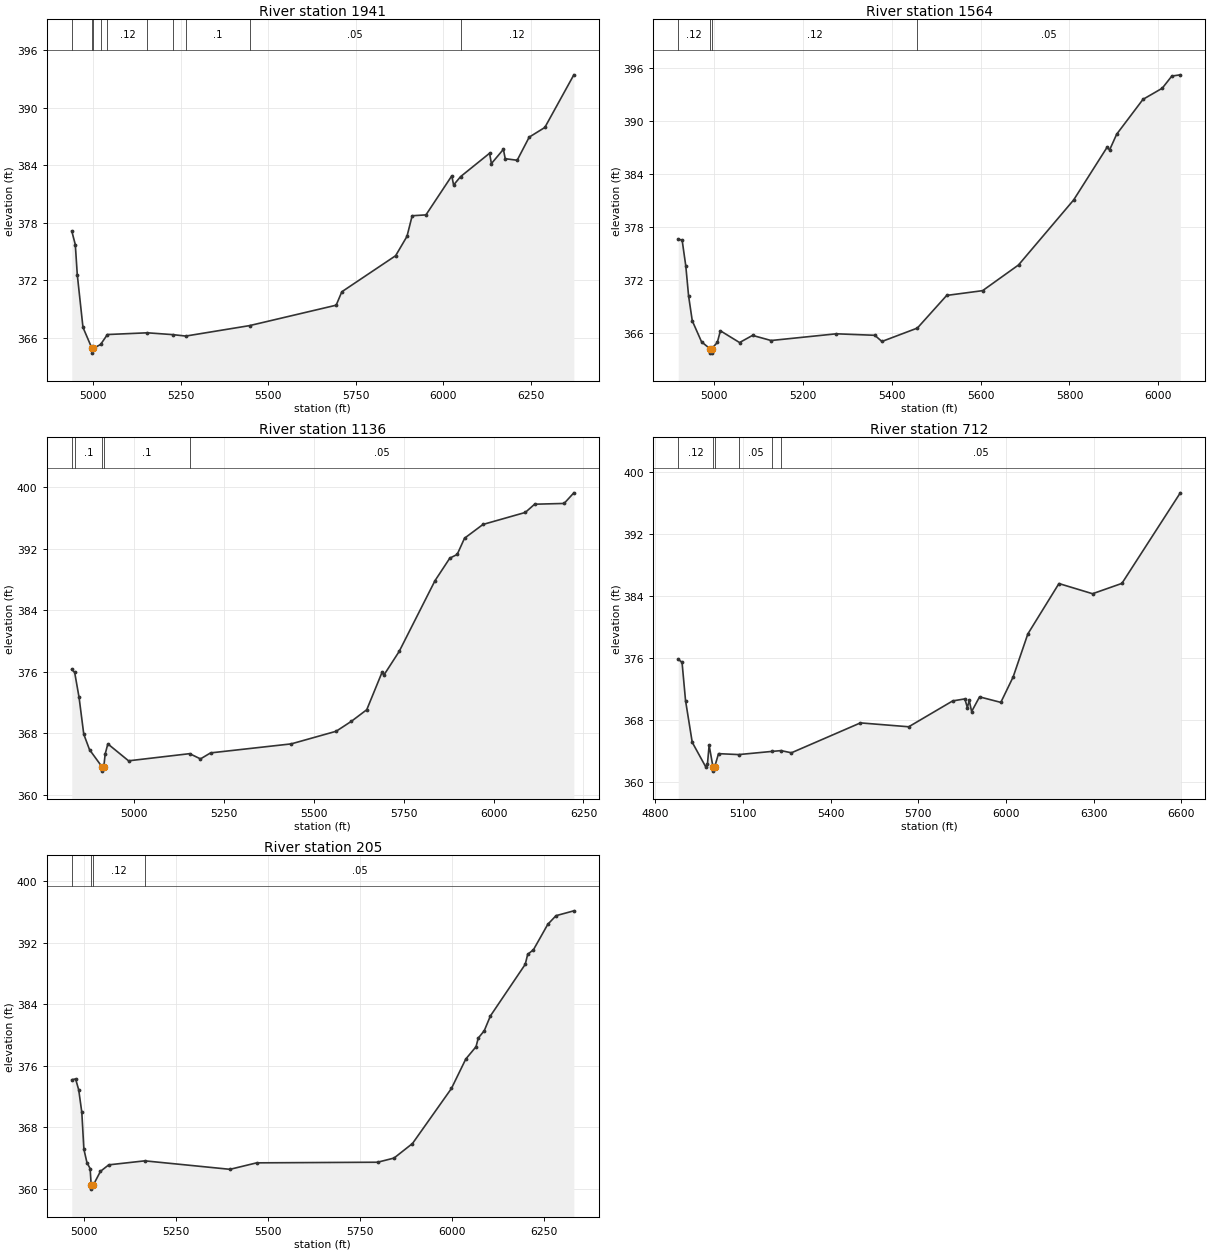
Type RM Length L Ch R = 1,1941,377,377,377
BEGIN DESCRIPTION:
Walnut25 3.0
END DESCRIPTION:
XS GIS Cut Line= 3
      2767186.47      6760438.47      2766736.11      6761280.95
      2766608.00      6761742.92
#Sta/Elev= 30
  4938.6  377.12  4948.7  375.70  4954.3  372.58  4970.6  367.07  4996.2  364.88
  4996.5  364.38  5000.2  364.88  5020.9  365.28  5040.4  366.32  5154.7  366.50
  5227.0  366.31  5264.4  366.16  5446.6  367.25  5694.1  369.38  5710.3  370.78
  5864.0  374.54  5896.5  376.56  5911.3  378.71  5950.7  378.80  6024.5  382.87
  6029.7  381.92  6049.6  382.79  6132.5  385.23  6137.7  384.15  6172.0  385.64
  6177.2  384.66  6211.4  384.50  6245.7  386.91  6290.4  387.92  6373.3  393.41
#Mann=10,-1,0
  4938.6    0.12       0  4996.2    0.07       0  5000.2    0.12       0
  5020.9     0.1       0  5040.4    0.12       0  5154.7     0.1       0
  5227.0    0.12       0  5264.4     0.1       0  5446.6    0.05       0
  6049.6    0.12       0
Bank Sta=4996.2,5000.2
Exp/Cntr=0.3,0.1

Type RM Length L Ch R = 1,1564,428,428,428
BEGIN DESCRIPTION:
Walnut25 2.0
END DESCRIPTION:
XS GIS Cut Line= 3
      2766903.08      6760224.88      2766755.53      6760422.91
      2766320.86      6761191.34
#Sta/Elev= 30
  4919.6  376.60  4928.3  376.55  4936.6  373.60  4942.9  370.20  4951.2  367.38
  4972.1  365.00  4990.9  364.22  4991.2  363.72  4994.7  363.72  4994.9  364.22
  5007.5  364.93  5014.5  366.25  5057.6  364.92  5086.8  365.73  5128.5  365.15
  5275.4  365.91  5362.0  365.74  5377.9  365.04  5457.7  366.56  5523.7  370.26
  5604.5  370.80  5685.3  373.71  5809.4  381.08  5884.5  387.04  5890.3  386.75
  5906.2  388.53  5965.4  392.48  6008.7  393.74  6030.3  395.12  6049.4  395.26
#Mann=4,-1,0
  4919.6    0.12       0  4990.9    0.07       0  4994.9    0.12       0
  5457.7    0.05       0
Bank Sta=4990.9,4994.9
Exp/Cntr=0.3,0.1

Type RM Length L Ch R = 1,1136,424,424,424
BEGIN DESCRIPTION:
Walnut25 1.0
END DESCRIPTION:
XS GIS Cut Line= 3
      2766625.21      6760023.22      2766347.44      6760523.21
      2766160.27      6761327.35
#Sta/Elev= 30
  4825.7  376.31  4833.8  375.91  4846.0  372.68  4859.1  367.89  4875.1  365.88
  4910.8  363.59  4911.1  363.09  4914.8  363.59  4918.6  365.30  4926.1  366.63
  4983.8  364.43  5153.8  365.36  5184.0  364.68  5212.1  365.46  5436.5  366.63
  5561.6  368.27  5604.2  369.57  5646.8  371.07  5689.4  375.93  5694.5  375.57
  5737.1  378.65  5836.9  387.85  5878.0  390.77  5898.5  391.25  5919.0  393.36
  5970.4  395.15  6088.1  396.71  6114.1  397.78  6196.2  397.88  6223.3  399.26
#Mann=5,-1,0
  4825.7    0.05       0  4833.8     0.1       0  4910.8    0.07       0
  4914.8     0.1       0  5153.8    0.05       0
Bank Sta=4910.8,4914.8
Exp/Cntr=0.3,0.1

Type RM Length L Ch R = 1,712,507,507,507
BEGIN DESCRIPTION:
Walnut25 0.5
END DESCRIPTION:
XS GIS Cut Line= 3
      2766347.91      6759817.22      2766201.61      6759898.21
      2764950.55      6760814.77
#Sta/Elev= 30
  4878.1  375.81  4891.1  375.45  4903.1  370.51  4926.0  365.14  4971.7  362.01
  4978.1  362.33  4983.8  364.76  4997.2  361.93  4998.0  361.43  5002.5  361.93
  5015.9  363.68  5085.0  363.56  5199.0  363.97  5230.0  364.07  5265.4  363.79
  5501.6  367.64  5666.8  367.14  5817.3  370.47  5859.0  370.73  5867.5  369.59
  5873.7  370.56  5882.1  369.10  5909.2  370.99  5982.0  370.28  6024.2  373.56
  6074.4  379.09  6180.9  385.58  6295.9  384.27  6396.3  385.60  6596.2  397.26
#Mann=6,-1,0
  4878.1    0.12       0  4997.2    0.07       0  5002.5    0.12       0
  5085.0    0.05       0  5199.0    0.12       0  5230.0    0.05       0
Bank Sta=4997.2,5002.5
Exp/Cntr=0.3,0.1

Type RM Length L Ch R = 1,205,0,0,0
BEGIN DESCRIPTION:
Walnut25 0.3
END DESCRIPTION:
XS GIS Cut Line= 3
      2765913.00      6759502.77      2765757.16      6759578.76
      2764694.12      6760116.09
#Sta/Elev= 30
  4965.9  374.19  4976.3  374.30  4984.8  372.87  4993.2  369.96  4998.8  365.19
  5007.1  363.45  5015.8  362.66  5018.7  360.50  5019.4  360.00  5024.0  360.50
  5043.9  362.31  5066.4  363.15  5164.4  363.67  5395.9  362.57  5468.4  363.41
  5797.1  363.49  5841.7  364.03  5891.9  365.92  5997.7  373.06  6036.7  376.88
  6064.6  378.48  6070.6  379.60  6086.9  380.55  6103.6  382.47  6198.3  389.17
  6205.0  390.47  6220.6  391.06  6259.6  394.36  6281.9  395.48  6330.4  396.11
#Mann=4,-1,0
  4965.9    0.12       0  5018.7    0.07       0  5024.0    0.12       0
  5164.4    0.05       0
Bank Sta=5018.7,5024
Exp/Cntr=0.3,0.1

Chan Stop Cuts=-1