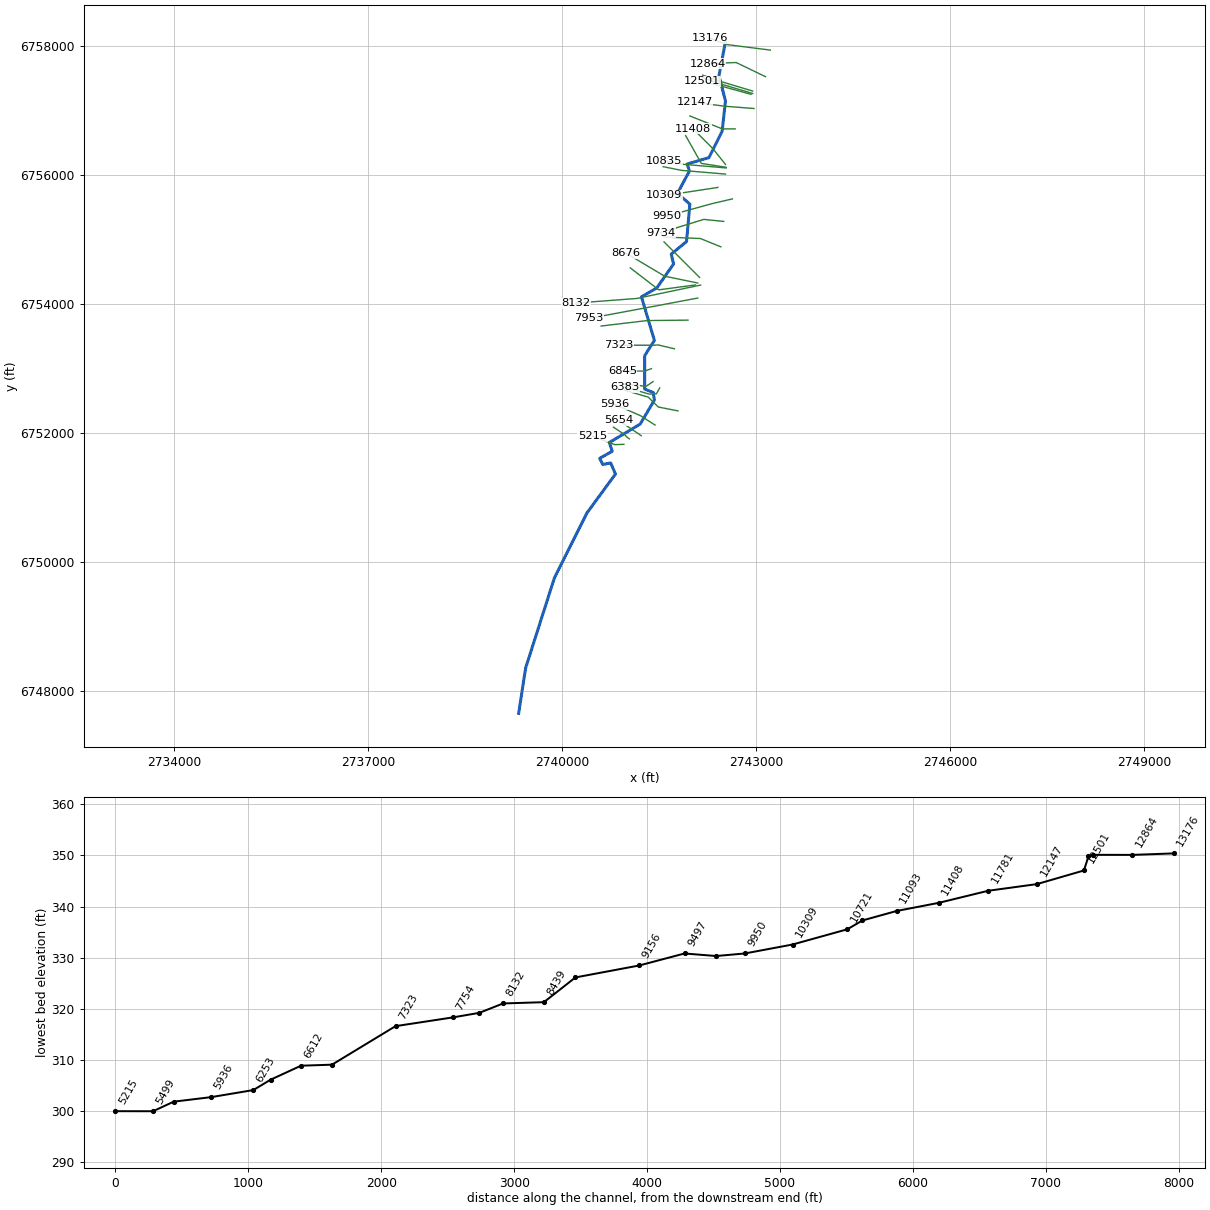
--- Walnut27.prj (project) ---

Proj Title=Walnut27 Base Level Engineering
Current Plan=p01
Default Exp/Contr=0.3,0.1
English Units
Geom File=g01
Flow File=f01
Plan File=p01
Y Axis Title=Elevation
X Axis Title(PF)=Main Channel Distance
X Axis Title(XS)=Station
BEGIN DESCRIPTION:
Walnut27
END DESCRIPTION:
DSS Export Rating Curves= 0
DSS Export Rating Curve Sorted= 0
DSS Export Volume Flow Curves= 0
DXF OffsetX= 0
DXF OffsetY= 0
DXF ScaleX= 1
DXF ScaleY= 10

--- Walnut27.p01 (plan) ---

Plan Title=Multiple Run
Program Version=4.10
Short Identifier=Multiple
Geom File=g01
Flow File=f01
Subcritical Flow
K Sum by GR= 0
Std Step Tol= 0.01
Critical Tol= 0.01
Num of Std Step Trials= 20
Max Error Tol= 0.3
Flow Tol Ratio= 0.001
Split Flow NTrial= 30
Split Flow Tol= 0.02
Split Flow Ratio= 0.02
Log Output Level= 0
Friction Slope Method= 1
Unsteady Friction Slope Method= 2
Unsteady Bridges Friction Slope Method= 1
Parabolic Critical Depth
Global Vel Dist= 1 , 1 , 1
Global Log Level= 0
CheckData=True
Encroach Param=-1 ,0,0, 0
BEGIN DESCRIPTION:
Multiple Run
END DESCRIPTION:
Computation Interval=1HOUR
Output Interval=1HOUR
Run HTab= 0
Run UNet= 0
Run PostProcess= 0
Run WQNet= 0
UNET Theta= 1
UNET Theta Warmup= 1
UNET ZTol= 0.02
UNET ZSATol= 0.05
UNET MxIter= 20
UNET MaxInSteps= 0
UNET DtIC= 0
UNET DtMin= 0
UNET MaxCRTS= 20
UNET WFStab= 2
UNET SFStab= 1
UNET WFX= 1
UNET SFX= 1
UNET DSS MLevel= 4
UNET DZMax Abort= 100
UNET Convert EG Bridges= 0
UNET Use Existing IB Tables=-1
UNET Froude Reduction=False
UNET Froude Limit= 1
UNET Froude Power= 10
UNET Time Slicing=0,0, 5
UNET Junction Losses=0
Instantaneous Interval=1HOUR
Write IC File= 0
Write IC File at Sim End=0
Echo Input=False
Echo Parameters=False
Echo Output=False
Write Detailed= 0
WQ AD Non Conservative
WQ ULTIMATE=-1
WQ Max Comp Step=1HOUR
WQ Output Interval=15MIN
WQ Output Selected Increments= 0
WQ Output face flow=0
WQ Output face velocity=0
WQ Output face area=0
WQ Output face dispersion=0
WQ Output cell volume=0
WQ Output cell surface area=0
WQ Output cell continuity=0
WQ Output cumulative cell continuity=0
WQ Output face conc=0
WQ Output face dconc_dx=0
WQ Output face courant=0
WQ Output face peclet=0
WQ Output face adv mass=0
WQ Output face disp mass=0
WQ Output cell mass=0
WQ Output cell source sink temp=0
WQ Output cell source sink nsm=0
WQ Output MaxMinRange=-1
WQ Daily Max Min Mean=-1
WQ Daily Range=0
WQ Daily Time=0
WQ Create Restart=0
WQ Fixed Restart=0
WQ System Summary=0
WQ Use Fixed Temperature=0
Sorting and Armoring Iterations= 10
XS Update Threshold= 0.02
Hydraulics Update Threshold= 0.02
Energy Slope Method= 1
Volume Change Method= 0
XS Weighting Method= 0
Number of US Weighted Cross Sections= 1
Number of DS Weighted Cross Sections= 1
Upstream XS Weight=0.25
Main XS Weight=0.5
Downstream XS Weight=0.25
Number of DS XS's Weighted with US Boundary= 1
Upstream Boundary Weight= 1
Weight of XSs Associated with US Boundary= 0
Number of US XS's Weighted with DS Boundary= 1
Downstream Boundary Weight= 0.5
Weight of XSs Associated with DS Boundary= 0.5
Sediment Output Level= 4
Mass or Volume Output= 0
Output Increment Type= 1
Profile and TS Output Increment= 10
XS Output Flag= 0
XS Output Increment= 10
Disregard all LS=0
Disregard all Conn=0
Disregard all Breaches=0
Disregard all Pumps=0

--- Walnut27.f01 (steady flow) ---

Flow Title=Multiple
Number of Profiles=7
Profile Names=10-year,25-year,50-year,1pct_min,100-year,1pct_plu,500-year
River Rch & RM= Walnut27,Reach-1,13176
     417     551     659     392     782    1560    1103
River Rch & RM= Walnut27,Reach-1,10835
     549     734     884     529    1055    2104    1505
River Rch & RM= Walnut27,Reach-1,8132
     622     838    1014     609    1216    2426    1752
River Rch & RM= Walnut27,Reach-1,6253
     716     965    1168     700    1397    2788    2006
River Rch & RM= Walnut27,Reach-1,3631
     799    1083    1315     791    1579    3150    2284
Boundary for River Rch & Prof#=Walnut27,Reach-1,1
Up Type=0
Dn Type=3
Dn Slope=0.008
Boundary for River Rch & Prof#=Walnut27,Reach-1,2
Up Type=0
Dn Type=3
Dn Slope=0.008
Boundary for River Rch & Prof#=Walnut27,Reach-1,3
Up Type=0
Dn Type=3
Dn Slope=0.008
Boundary for River Rch & Prof#=Walnut27,Reach-1,4
Up Type=0
Dn Type=3
Dn Slope=0.008
Boundary for River Rch & Prof#=Walnut27,Reach-1,5
Up Type=0
Dn Type=3
Dn Slope=0.008
Boundary for River Rch & Prof#=Walnut27,Reach-1,6
Up Type=0
Dn Type=3
Dn Slope=0.008
Boundary for River Rch & Prof#=Walnut27,Reach-1,7
Up Type=0
Dn Type=3
Dn Slope=0.008

--- Walnut27.g01 (geometry) ---

Geom Title=Existing Conditions
Program Version=4.10

River Reach=Walnut27        ,Reach-1
Reach XY= 30
        2742526.        6758061.       2742425.8      6757536.08
      2742525.93      6757140.97      2742474.03      6756672.97
      2742270.56      6756266.25      2741932.98      6756167.14
      2741967.95      6756057.69      2741783.87      6755714.21
       2741975.1       6755545.1      2741923.75      6754966.93
      2741686.95      6754771.43      2741723.02      6754619.34
      2741462.76      6754247.28        2741226.        6754111.
      2741426.24      6753436.05      2741277.05      6753200.57
      2741275.95      6752680.97      2741409.77      6752628.26
        2741426.        6752511.      2741206.53      6752140.46
      2740730.77      6751855.42       2740773.5      6751719.16
      2740579.08      6751609.33      2740627.37      6751514.07
      2740749.73       6751538.7      2740824.21      6751367.11
      2740381.85      6750763.29      2739879.55       6749759.7
      2739434.28      6748364.22        2739326.        6747661.

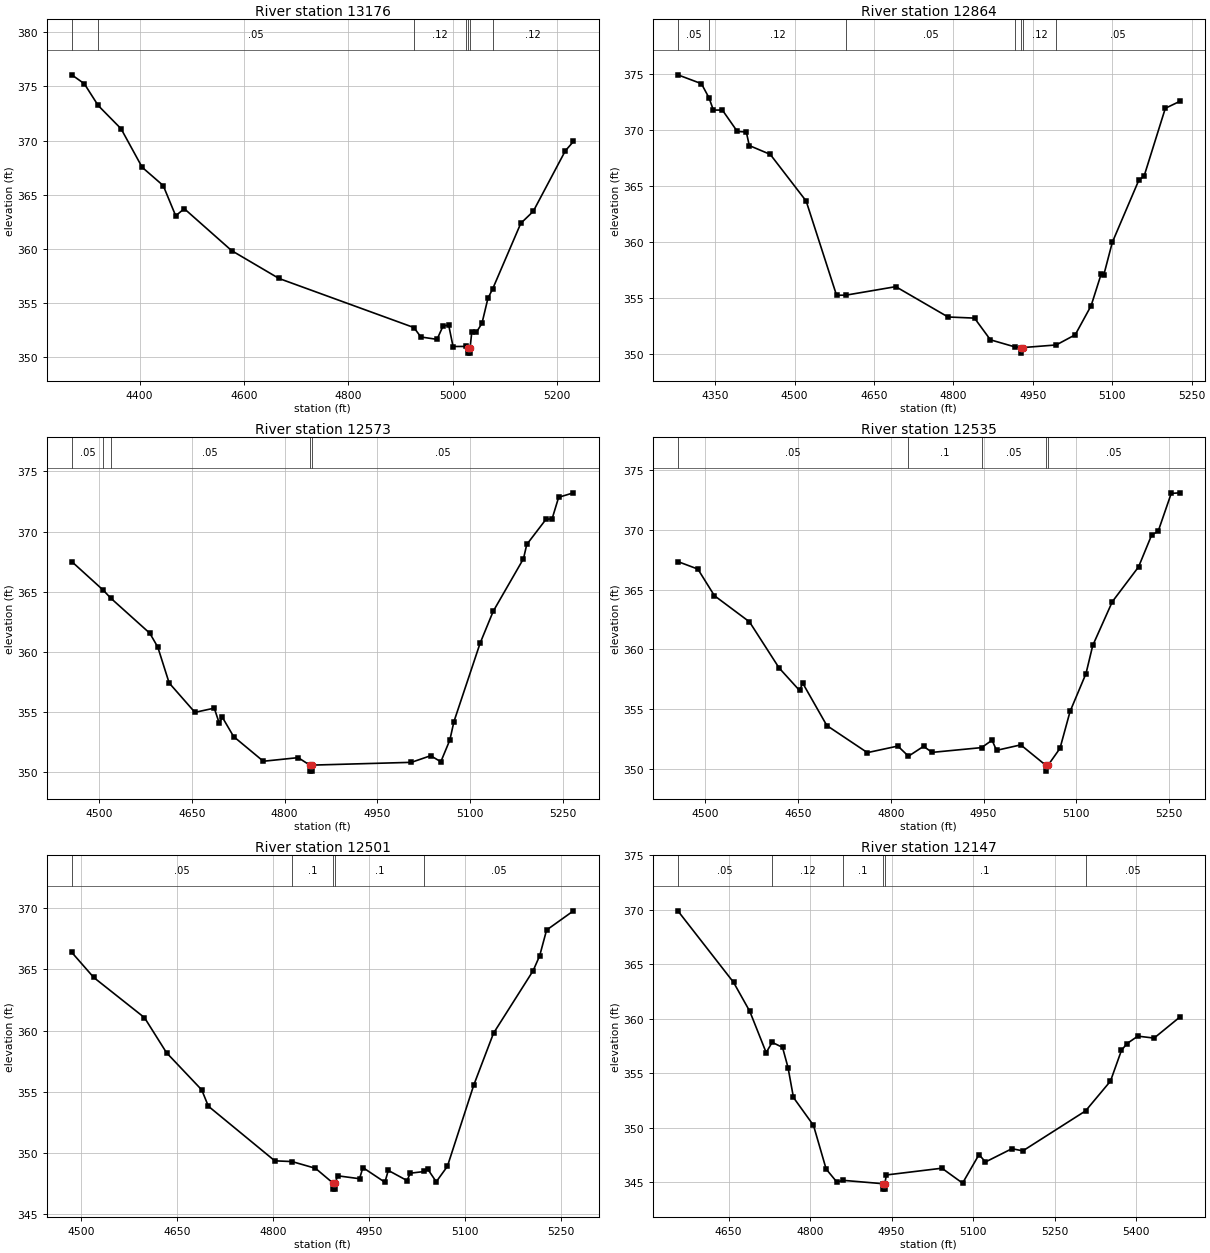
Type RM Length L Ch R = 1 ,13176   ,312,312,312
BEGIN DESCRIPTION:
Walnut27 28.0
END DESCRIPTION:
XS GIS Cut Line= 3
      2743219.78      6757931.17      2742551.68      6758015.74
      2742281.06      6758112.99
#Sta/Elev= 30
  4270.2  376.07  4294.2  375.25  4320.8  373.24  4364.7  371.09    4405  367.54
  4445.4  365.85  4469.3  363.06  4485.7  363.72  4576.4  359.85  4667.1  357.28
  4925.5  352.75  4938.9  351.88  4969.8  351.66  4981.5   352.9  4992.2  352.97
  5000.5     351  5025.8  351.01  5029.2  350.89  5029.5  350.39    5033  350.39
  5033.2  350.89  5036.5  352.38  5045.3  352.32  5055.9  353.14  5067.3  355.44
  5076.6  356.34  5130.3  362.37  5154.1  363.47  5215.6  369.06  5231.2  369.92
#Mann= 7 ,-1 , 0
  4270.2     .12       0  4320.8     .05       0  4925.5     .12       0
  5025.8     .05       0  5029.2     .07       0  5033.2     .05       0
  5076.6     .12       0
Bank Sta=5029.2,5033.2
XS Rating Curve= 0 ,0
Exp/Cntr=0.3,0.1

Type RM Length L Ch R = 1 ,12864   ,291,291,291
BEGIN DESCRIPTION:
Walnut27 27.0
END DESCRIPTION:
XS GIS Cut Line= 3
      2743145.77      6757518.91      2742691.21      6757738.79
      2742249.16      6757719.84
#Sta/Elev= 30
  4279.7  374.97  4324.2  374.18  4338.6  372.91  4346.8  371.82  4363.8  371.82
    4392  369.91    4409  369.86  4414.6  368.65  4454.2  367.86    4522  363.69
  4579.4  355.27    4597  355.28  4691.2  356.04  4789.9  353.33  4839.9  353.23
  4869.9  351.29  4915.9  350.66    4928   350.6  4928.2   350.1    4932   350.6
  4994.2  350.83  5030.1  351.74  5060.1  354.34  5079.2  357.19  5084.2  357.12
  5100.1     360  5150.2  365.56  5160.2  365.93  5200.2  371.98  5227.1  372.59
#Mann= 7 ,-1 , 0
  4279.7     .05       0  4338.6     .12       0    4597     .05       0
  4915.9     .12       0    4928     .04       0    4932     .12       0
  4994.2     .05       0
Bank Sta=4928,4932
XS Rating Curve= 0 ,0
Exp/Cntr=0.3,0.1

Type RM Length L Ch R = 1 ,12573   ,38,38,38
BEGIN DESCRIPTION:
Walnut27 26.2
END DESCRIPTION:
XS GIS Cut Line= 3
      2742946.98      6757296.95      2742458.66      6757442.81
       2742173.3      6757542.16
#Sta/Elev= 30
  4455.6  367.51  4506.7  365.13  4518.6  364.48  4581.9  361.56  4594.8  360.41
  4613.2  357.43  4654.9  354.99  4686.2  355.34  4694.1  354.11  4699.4  354.57
  4717.5  352.98  4765.6  350.93  4821.9  351.23  4840.8  350.61    4841  350.11
  4844.5  350.11  4844.8  350.61  5005.2  350.84  5036.3  351.39  5052.8  350.89
  5067.4   352.7  5073.9  354.21  5116.3  360.73  5137.5  363.38  5186.5  367.75
  5191.8  368.93  5222.9  371.02  5232.8  371.06  5243.4  372.85  5267.4  373.22
#Mann= 5 ,-1 , 0
  4455.6     .05       0  4506.7     .12       0  4518.6     .05       0
  4840.8     .04       0  4844.8     .05       0
Bank Sta=4840.8,4844.8
XS Rating Curve= 0 ,0
Exp/Cntr=0.3,0.1

Type RM Length L Ch R = 1 ,12535   ,34,34,34
BEGIN DESCRIPTION:
Walnut27 26.0
END DESCRIPTION:
XS GIS Cut Line= 3
      2742947.06      6757258.88      2742458.66      6757404.76
      2742173.28      6757504.12
#Sta/Elev= 30
  4455.3  367.35  4487.7  366.72  4514.5  364.49  4571.2   362.3  4619.1  358.44
  4652.2  356.55  4657.4  357.16  4696.4  353.61    4762  351.34  4811.3  351.89
  4828.5  351.04    4853  351.87  4866.6  351.36  4946.7  351.76  4963.8  352.38
    4971  351.53  5010.2  351.99  5050.5  350.29  5050.8  349.79  5054.5  350.29
  5073.7   351.7    5090  354.79  5115.8  357.97  5126.7  360.32  5158.4  363.99
  5200.8   366.9    5222  369.57  5232.6  369.89  5253.7  373.06  5267.2  373.11
#Mann= 5 ,-1 , 0
  4455.3     .05       0  4828.5      .1       0  4946.7     .05       0
  5050.5     .04       0  5054.5     .05       0
Bank Sta=5050.5,5054.5
XS Rating Curve= 0 ,0
Exp/Cntr=0.3,0.1

Type RM Length L Ch R = 1 ,12501   ,354,354,354
BEGIN DESCRIPTION:
Walnut27 25.8
END DESCRIPTION:
XS GIS Cut Line= 3
       2742921.6      6757246.22      2742391.01      6757392.08
      2742164.77      6757447.05
#Sta/Elev= 30
    4486  366.38  4520.3  364.33  4599.5  361.05    4634  358.18  4688.9  355.15
  4699.2  353.82  4802.9  349.36  4829.8   349.3  4866.4  348.75  4893.6  347.55
  4893.9  347.05  4897.4  347.05  4897.6  347.55  4900.8  348.14  4935.2   347.9
  4940.4  348.81  4974.8  347.61    4980  348.58  5009.3  347.75  5014.4  348.35
  5036.4  348.49  5041.4   348.7  5054.9  347.65  5072.3  348.91  5113.5  355.55
  5144.3  359.78  5206.1  364.88  5216.4  366.11  5227.1   368.2  5269.1  369.77
#Mann= 5 ,-1 , 0
    4486     .05       0  4829.8      .1       0  4893.6     .07       0
  4897.6      .1       0  5036.4     .05       0
Bank Sta=4893.6,4897.6
XS Rating Curve= 0 ,0
Exp/Cntr=0.3,0.1

Type RM Length L Ch R = 1 ,12147   ,366,366,366
BEGIN DESCRIPTION:
Walnut27 25.0
END DESCRIPTION:
XS GIS Cut Line= 3
      2742968.14      6757026.34        2742526.        6757061.
       2742049.8      6757121.31
#Sta/Elev= 30
  4556.6  369.92  4659.1  363.36  4689.1  360.69  4719.2  356.91  4730.2  357.85
  4749.3  357.39  4759.4  355.54  4769.4  352.79  4806.3  350.23  4829.6  346.22
  4849.6  345.01    4860  345.19  4933.5  344.88  4933.8  344.38  4937.3  344.38
  4937.5  344.88  4940.5  345.68  5042.7   346.3  5080.7  344.93    5111  347.55
  5122.8  346.87  5171.5  348.09  5191.6  347.89  5307.1  351.56  5352.9  354.29
  5373.1  357.11  5383.1  357.73  5403.3  358.42  5433.2  358.24  5480.1  360.15
#Mann= 6 ,-1 , 0
  4556.6     .05       0  4730.2     .12       0    4860      .1       0
  4933.5     .07       0  4937.5      .1       0  5307.1     .05       0
Bank Sta=4933.5,4937.5
XS Rating Curve= 0 ,0
Exp/Cntr=0.3,0.1

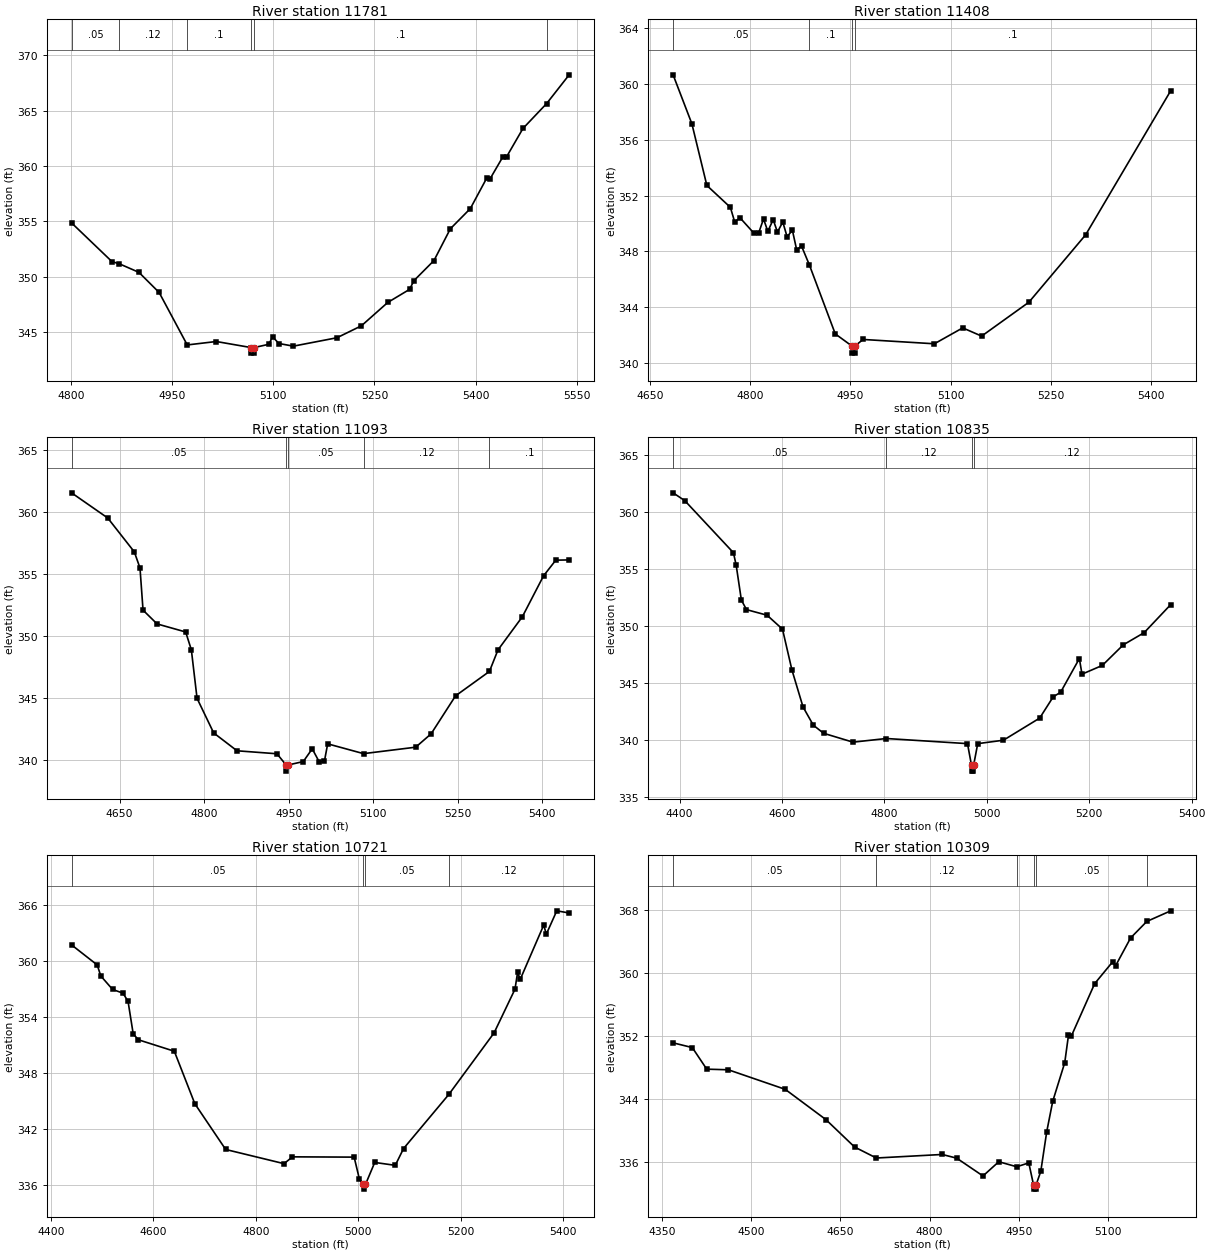
Type RM Length L Ch R = 1 ,11781   ,373,373,373
BEGIN DESCRIPTION:
Walnut27 24.0
END DESCRIPTION:
XS GIS Cut Line= 3
        2742676.        6756711.        2742476.        6756711.
      2741976.01      6756910.99
#Sta/Elev= 30
  4800.5  354.85  4860.5  351.35  4871.5  351.15  4900.5  350.38  4930.5  348.56
  4972.2  343.82  5015.3  344.13  5067.2  343.58  5067.4  343.08  5070.9  343.08
  5071.2  343.58  5093.4  343.88  5098.8  344.56  5108.2  343.95  5129.7  343.71
  5194.4  344.47  5230.7  345.55  5269.8  347.66  5302.1  348.84  5308.8  349.64
  5338.4  351.45  5362.7  354.32  5392.3  356.14  5416.5  358.88  5421.9  358.86
  5440.7  360.83  5446.1  360.82  5470.4  363.38  5505.5  365.63    5539  368.23
#Mann= 6 ,-1 , 0
  4800.5     .05       0  4871.5     .12       0  4972.2      .1       0
  5067.2     .07       0  5071.2      .1       0  5505.5     .05       0
Bank Sta=5067.2,5071.2
XS Rating Curve= 0 ,0
Exp/Cntr=0.3,0.1

Type RM Length L Ch R = 1 ,11408   ,315,315,315
BEGIN DESCRIPTION:
Walnut27 23.0
END DESCRIPTION:
XS GIS Cut Line= 3
      2742526.03      6756160.96        2742326.        6756411.
      2742025.98      6756711.02
#Sta/Elev= 30
  4684.9  360.66    4713  357.15  4735.4  352.73  4770.6  351.16    4777  350.12
    4785  350.41  4805.8  349.31    4813  349.34  4820.2  350.33  4826.6  349.44
  4834.6  350.28    4841  349.39    4849  350.11  4855.4  349.06  4863.4  349.51
  4869.8  348.11    4877  348.39  4888.8  347.03  4927.5  342.09  4952.7  341.21
  4952.9  340.71  4956.4  340.71  4956.7  341.21  4969.1  341.69  5075.8  341.38
  5118.2  342.52  5146.5  341.93  5217.2  344.36  5302.1  349.19  5429.4  359.52
#Mann= 4 ,-1 , 0
  4684.9     .05       0  4888.8      .1       0  4952.7     .07       0
  4956.7      .1       0
Bank Sta=4952.7,4956.7
XS Rating Curve= 0 ,0
Exp/Cntr=0.3,0.1

Type RM Length L Ch R = 1 ,11093   ,258,258,258
BEGIN DESCRIPTION:
Walnut27 22.0
END DESCRIPTION:
XS GIS Cut Line= 3
      2742535.92      6756116.31      2742152.12      6756176.47
      2741909.47       6756606.9
#Sta/Elev= 30
  4564.9  361.57  4629.1  359.54  4676.2  356.81  4686.3  355.51  4691.7  352.11
  4716.6     351  4767.3  350.35  4777.4  348.91  4787.5     345    4817  342.21
  4858.4  340.77  4929.2  340.53  4945.4  339.63  4945.6  339.13  4949.4  339.63
  4975.9   339.9  4991.8  340.93  5004.5  339.85  5013.5  339.96  5019.2  341.33
  5082.8  340.54  5175.3  341.06  5202.7  342.14    5246   345.2  5306.1  347.17
  5321.2   348.9  5364.5  351.58  5402.1  354.88  5423.8  356.14  5447.5  356.16
#Mann= 5 ,-1 , 0
  4564.9     .05       0  4945.4     .03       0  4949.4     .05       0
  5082.8     .12       0  5306.1      .1       0
Bank Sta=4945.4,4949.4
XS Rating Curve= 0 ,0
Exp/Cntr=0.3,0.1

Type RM Length L Ch R = 1 ,10835   ,114,114,114
BEGIN DESCRIPTION:
Walnut27 21.5
END DESCRIPTION:
XS GIS Cut Line= 3
      2742538.79      6756106.07       2741860.5      6756163.71
      2741575.09      6756220.79
#Sta/Elev= 30
  4387.3  361.67  4410.2  360.98  4505.1  356.42  4510.5  355.32  4520.6  352.27
  4530.6  351.43  4570.8  350.94  4600.9  349.72  4619.3  346.15    4641   342.9
  4661.1   341.3  4681.1  340.59  4738.6  339.81  4803.8  340.13  4962.2  339.68
  4970.1  337.77  4970.3  337.27  4973.8  337.27  4974.1  337.77  4982.2  339.68
  5032.4  339.98  5103.2  341.92  5129.7  343.79    5144  344.18  5180.7  347.14
  5185.8  345.77  5225.6  346.54  5266.4  348.34  5307.2  349.41  5359.1  351.87
#Mann= 4 ,-1 , 0
  4387.3     .05       0  4803.8     .12       0  4970.1     .07       0
  4974.1     .12       0
Bank Sta=4970.1,4974.1
XS Rating Curve= 0 ,0
Exp/Cntr=0.3,0.1

Type RM Length L Ch R = 1 ,10721   ,412,412,412
BEGIN DESCRIPTION:
Walnut27 21.0
END DESCRIPTION:
XS GIS Cut Line= 3
      2742525.95        6756011.      2741847.69      6756068.65
      2741562.25      6756125.73
#Sta/Elev= 30
  4440.1  361.72  4490.2  359.57  4497.2  358.39  4520.3  356.94  4540.4  356.55
  4550.4  355.68  4560.5  352.19  4570.5  351.55  4640.8  350.32  4680.9  344.69
  4741.1  339.79    4855  338.27  4871.6     339    4992  338.97  5002.1  336.65
  5010.1  336.04  5010.4  335.54  5014.1  336.04  5032.2   338.4  5072.3  338.09
  5088.5  339.89  5176.9  345.69  5265.3  352.29  5306.1  356.97  5311.2  358.78
  5316.3  358.02  5362.2  363.84  5367.3  362.87  5387.7  365.37  5411.9  365.14
#Mann= 4 ,-1 , 0
  4440.1     .05       0  5010.1     .03       0  5014.1     .05       0
  5176.9     .12       0
Bank Sta=5010.1,5014.1
XS Rating Curve= 0 ,0
Exp/Cntr=0.3,0.1

Type RM Length L Ch R = 1 ,10309   ,359,359,359
BEGIN DESCRIPTION:
Walnut27 20.0
END DESCRIPTION:
XS GIS Cut Line= 3
      2742407.94      6755804.39      2741839.23      6755717.71
      2741579.06      6755684.14
#Sta/Elev= 30
  4368.4  351.13  4400.7  350.53    4425  347.79  4461.4  347.71  4557.1  345.23
  4625.7  341.38  4673.8  337.91  4710.5  336.51  4821.4  336.96  4845.8  336.49
    4890  334.23  4916.6  336.04  4946.8   335.4  4967.1  335.89  4975.2  333.06
  4975.4  332.56  4978.9  332.56  4979.2  333.06  4987.3  334.82  4997.3  339.85
  5007.4  343.71  5027.6  348.61  5033.9   352.1  5038.9  352.02    5078  358.65
  5108.2  361.41  5113.3  360.93  5138.5  364.45  5165.7  366.54    5206  367.89
#Mann= 6 ,-1 , 0
  4368.4     .05       0  4710.5     .12       0  4946.8     .05       0
  4975.2     .03       0  4979.2     .05       0  5165.7     .12       0
Bank Sta=4975.2,4979.2
XS Rating Curve= 0 ,0
Exp/Cntr=0.3,0.1

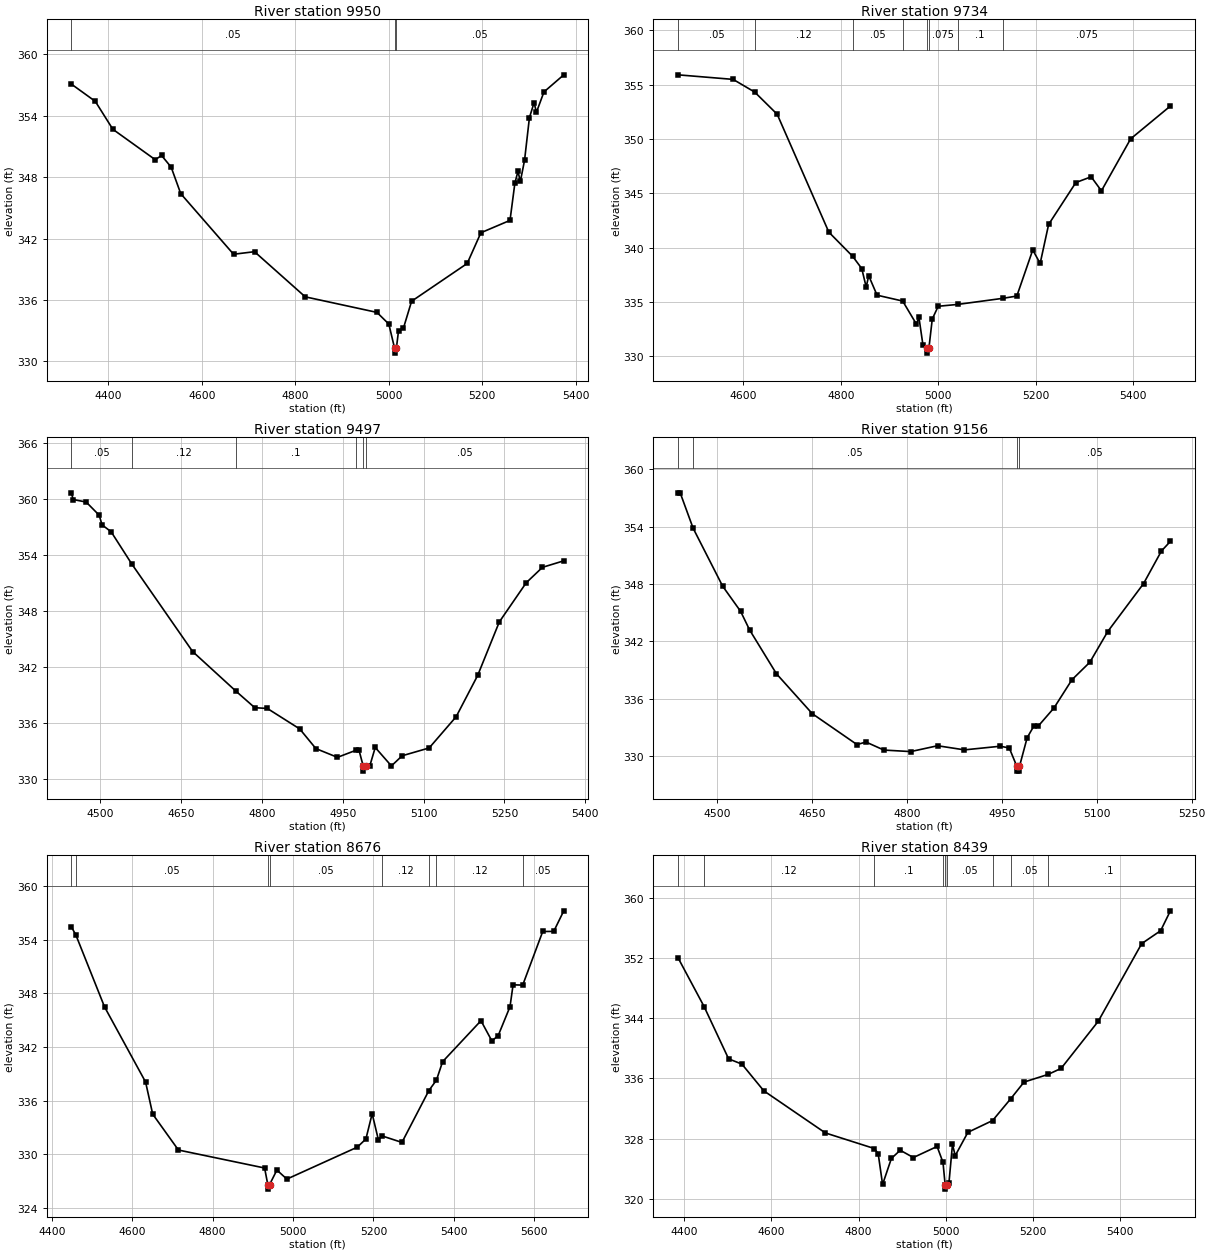
Type RM Length L Ch R = 1 ,9950    ,216,216,216
BEGIN DESCRIPTION:
Walnut27 19.0
END DESCRIPTION:
XS GIS Cut Line= 3
      2742634.11      6755626.79      2742331.82      6755557.03
      2741615.14      6755360.42
#Sta/Elev= 30
  4320.9   357.1  4372.2  355.41  4409.8  352.68  4500.4  349.71    4514  350.12
  4534.5  348.98    4555  346.39    4668  340.47  4712.8  340.72  4821.3  336.31
  4974.7  334.79  5000.1  333.65  5012.3  331.31  5012.6  330.81  5016.3  331.31
  5020.8  332.98  5031.2  333.23  5048.8  335.88  5167.7  339.57    5197  342.57
  5259.3  343.78  5269.7  347.42  5276.3  348.57  5281.4  347.58  5290.4  349.65
  5300.8  353.81  5310.7  355.27  5315.9  354.35  5331.9  356.33  5374.3     358
#Mann= 3 ,-1 , 0
  4320.9     .05       0  5012.3     .03       0  5016.3     .05       0
Bank Sta=5012.3,5016.3
XS Rating Curve= 0 ,0
Exp/Cntr=0.3,0.1

Type RM Length L Ch R = 1 ,9734    ,237,237,237
BEGIN DESCRIPTION:
Walnut27 18.5
END DESCRIPTION:
XS GIS Cut Line= 3
      2742498.84      6755277.97      2742190.17      6755309.68
      2741520.53      6755102.67
#Sta/Elev= 30
  4465.7  355.91  4579.1  355.49  4623.5  354.32  4669.6  352.28  4775.6  341.44
  4824.4  339.22  4843.2  338.09  4852.3  336.39  4857.5  337.43  4874.6  335.64
  4927.2   335.1  4955.4  332.98  4960.6   333.6  4968.8  331.07  4977.2  330.81
  4977.5  330.31  4981.2  330.81    4988  333.45  5000.2  334.62  5040.1  334.79
  5132.8  335.35  5161.6  335.56  5194.3   339.8  5209.5  338.56  5226.9  342.15
  5282.8     346  5314.2  346.53  5335.3  345.24  5395.3  350.02  5476.9  353.04
#Mann= 8 ,-1 , 0
  4465.7     .05       0  4623.5     .12       0  4824.4     .05       0
  4927.2    .075       0  4977.2     .07       0  4981.2    .075       0
  5040.1      .1       0  5132.8    .075       0
Bank Sta=4977.2,4981.2
XS Rating Curve= 0 ,0
Exp/Cntr=0.3,0.1

Type RM Length L Ch R = 1 ,9497    ,341,341,341
BEGIN DESCRIPTION:
Walnut27 18.0
END DESCRIPTION:
XS GIS Cut Line= 3
      2742454.47      6754884.73      2742137.32      6755013.71
      2741566.47      6755036.97
#Sta/Elev= 30
  4446.3  360.69  4449.9  359.97  4473.9   359.7    4498  358.29  4503.4  357.25
  4520.2  356.51  4558.4  353.06  4671.4  343.65  4751.3  339.42  4786.7  337.62
    4810  337.54  4870.1  335.34  4900.1  333.23  4940.1  332.29  4973.6  333.03
  4980.2  333.03  4988.1  331.31  4988.4  330.81  4992.3  331.31  5000.2  331.39
  5010.2  333.35  5040.2  331.37  5060.2  332.46  5110.3   333.3  5160.3  336.65
  5200.3  341.09  5240.4  346.83  5290.4  351.04  5320.4  352.69    5360  353.39
#Mann= 6 ,-1 , 0
  4446.3     .05       0  4558.4     .12       0  4751.3      .1       0
  4973.6     .05       0  4988.1     .03       0  4992.3     .05       0
Bank Sta=4988.1,4992.3
XS Rating Curve= 0 ,0
Exp/Cntr=0.3,0.1

Type RM Length L Ch R = 1 ,9156    ,480,480,480
BEGIN DESCRIPTION:
Walnut27 17.0
END DESCRIPTION:
XS GIS Cut Line= 3
      2742126.01      6754410.99        2741726.        6754811.
      2741576.03      6754960.97
#Sta/Elev= 30
  4438.5  357.52  4442.1  357.52  4462.5  353.83  4509.2  347.77  4537.5  345.15
  4551.7  343.21  4594.1  338.63  4650.7  334.46  4721.4  331.23  4735.5   331.5
  4763.8  330.66  4806.2   330.5  4848.6  331.11  4891.1  330.68  4947.6  331.06
  4961.8  330.88  4973.8  328.96  4974.1  328.46  4977.7  328.46    4978  328.96
  4990.1  331.95  5000.7  333.17  5007.7  333.17  5032.5  335.06  5060.8     338
  5089.1  339.83  5117.3  343.03  5173.9  348.04  5202.2  351.45  5216.3  352.45
#Mann= 4 ,-1 , 0
  4438.5      .1       0  4462.5     .05       0  4973.8     .05       0
    4978     .05       0
Bank Sta=4973.8,4978
XS Rating Curve= 0 ,0
Exp/Cntr=0.3,0.1

Type RM Length L Ch R = 1 ,8676    ,237,237,237
BEGIN DESCRIPTION:
Walnut27 16.0
END DESCRIPTION:
XS GIS Cut Line= 3
       2742097.1      6754324.52      2741585.54      6754430.22
      2740980.95      6754789.59
#Sta/Elev= 30
  4448.1  355.44  4459.4  354.53  4530.9  346.48    4633  338.09  4650.7   334.5
  4714.7  330.49  4929.2  328.48  4937.2  326.62  4937.6  326.12  4941.5  326.62
  4959.8  328.25  4984.6  327.24  5159.9  330.81  5181.3  331.72  5196.9  334.55
  5212.5  331.61  5221.3  332.07    5271  331.34  5338.1  337.14  5356.9   338.3
  5372.2  340.36  5467.7  344.94  5494.9  342.68  5510.5  343.27    5540  346.51
  5547.6  348.95  5571.6  348.92  5621.4  354.91  5648.8  354.92  5673.8  357.22
#Mann= 8 ,-1 , 0
  4448.1      .1       0  4459.4     .05       0  4937.2     .05       0
  4941.5     .05       0  5221.3     .12       0  5338.1      .1       0
  5356.9     .12       0  5571.6     .05       0
Bank Sta=4937.2,4941.5
XS Rating Curve= 0 ,0
Exp/Cntr=0.3,0.1

Type RM Length L Ch R = 1 ,8439    ,307,307,307
BEGIN DESCRIPTION:
Walnut27 15.0
END DESCRIPTION:
XS GIS Cut Line= 3
      2742061.23      6754294.92      2741494.63      6754218.81
      2741052.81      6754559.16
#Sta/Elev= 30
  4385.5  352.07  4445.5  345.56  4501.8   338.6  4532.3   337.9  4582.5  334.35
  4723.7  328.75  4835.8  326.68  4844.8     326  4854.9   321.9  4875.1  325.36
  4895.3  326.45  4925.5  325.48  4979.9  326.95  4993.4  324.84  4998.5  321.78
  4998.9  321.28  5002.8  321.78    5007  322.06  5015.2  327.22  5021.5  325.73
  5050.5  328.83  5107.2   330.4  5149.1  333.32  5179.2  335.51  5234.4  336.53
  5264.3  337.33  5349.5   343.6  5449.1  353.92  5492.6  355.64  5514.9  358.28
#Mann= 9 ,-1 , 0
  4385.5     .05       0  4445.5     .12       0  4835.8      .1       0
  4993.4     .05       0  4998.5     .05       0  5002.8     .05       0
  5107.2     .12       0  5149.1     .05       0  5234.4      .1       0
Bank Sta=4998.5,5002.8
XS Rating Curve= 0 ,0
Exp/Cntr=0.3,0.1

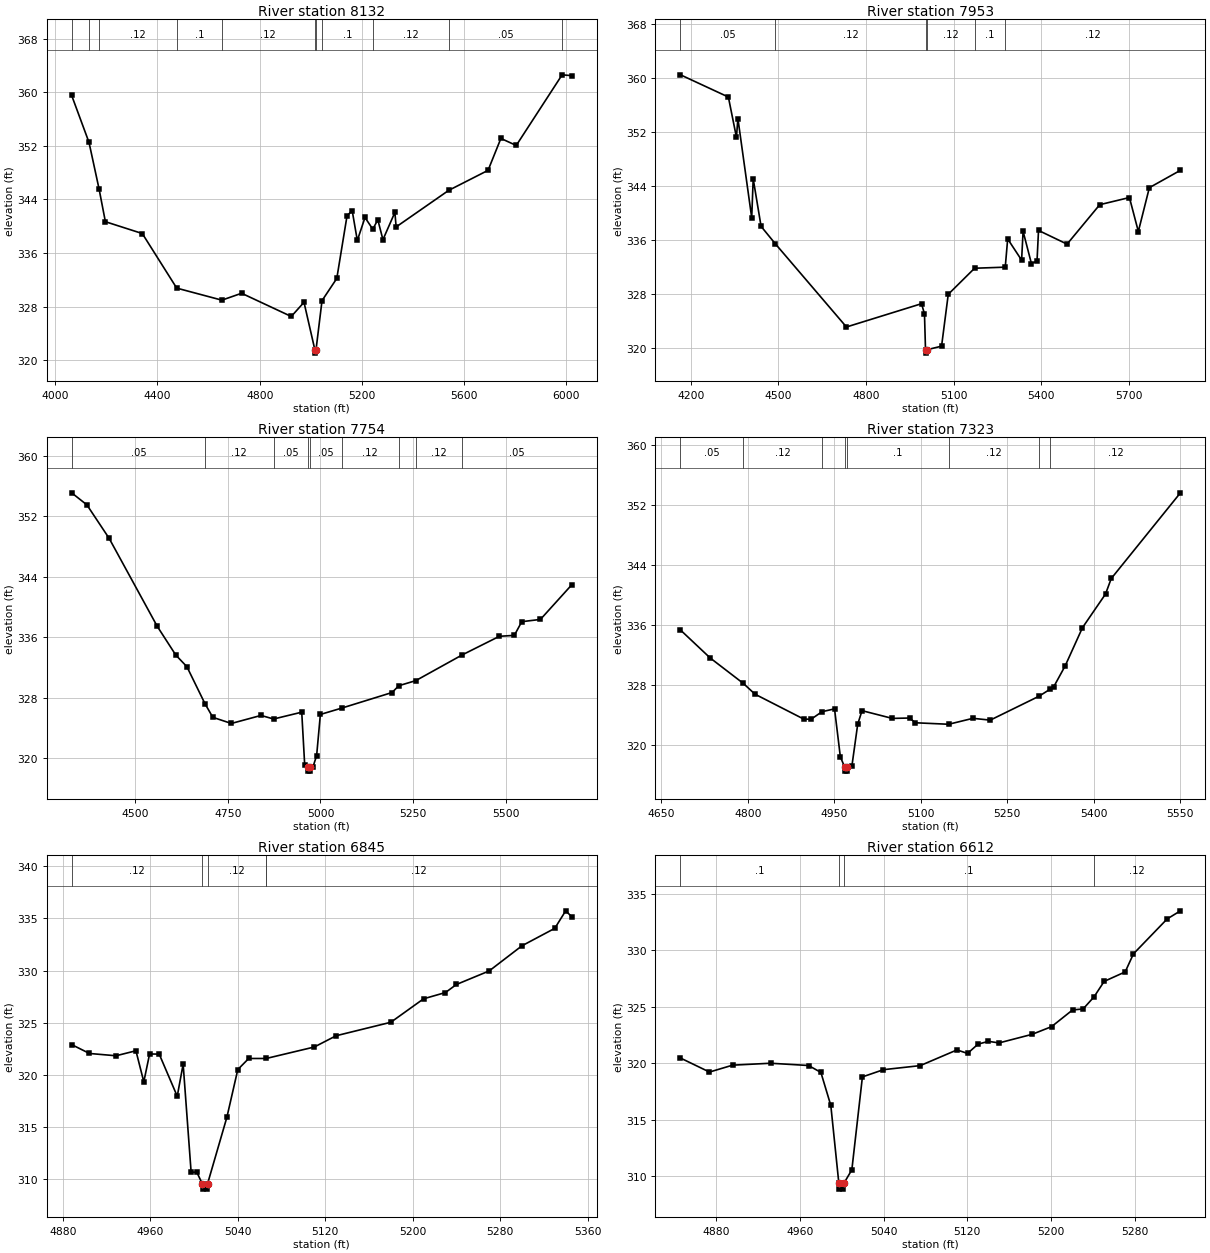
Type RM Length L Ch R = 1 ,8132    ,179,179,179
BEGIN DESCRIPTION:
Walnut27 14.4
END DESCRIPTION:
XS GIS Cut Line= 3
      2742141.59      6754292.81      2741156.37      6754085.62
      2740210.16      6754013.81
#Sta/Elev= 30
  4064.3  359.56  4132.2  352.53  4171.6  345.56  4196.2  340.68  4340.6  338.91
  4475.3  330.75  4651.9  328.95  4729.1  329.98  4923.4  326.51  4973.2  328.63
  5015.7  321.53  5016.1  321.03  5020.2  321.53  5043.7  328.88  5101.5   332.2
  5141.6  341.57  5161.7  342.34  5181.8  337.87  5211.8  341.31  5242.3  339.56
    5262  340.97    5282  337.99  5328.7  342.07  5333.7   339.9  5539.5  345.37
  5693.2  348.36  5743.4  353.13  5803.5  352.08  5982.9  362.64    6020  362.52
#Mann= 11 ,-1 , 0
  4064.3      .1       0  4132.2     .05       0  4171.6     .12       0
  4475.3      .1       0  4651.9     .12       0  5015.7     .07       0
  5020.2     .12       0  5043.7      .1       0  5242.3     .12       0
  5539.5     .05       0  5982.9     .12       0
Bank Sta=5015.7,5020.2
XS Rating Curve= 0 ,0
Exp/Cntr=0.3,0.1

Type RM Length L Ch R = 1 ,7953    ,199,199,199
BEGIN DESCRIPTION:
Walnut27 14.2
END DESCRIPTION:
XS GIS Cut Line= 3
      2742097.18      6754091.96      2741403.72      6753960.88
      2740414.31      6753776.96
#Sta/Elev= 30
  4164.5   360.4  4328.5  357.11  4356.1  351.16  4361.1  353.93  4408.4  339.24
  4413.5     345  4440.5  337.96  4489.1  335.39  4732.8  323.06    4990  326.51
  5000.1  324.99  5003.6  319.69    5004  319.19  5008.1  319.69  5058.6  320.22
  5081.5   327.9  5171.7  331.76  5276.7  331.92    5285   336.1  5332.7  332.96
  5337.8  337.23  5366.3  332.46  5385.5  332.82  5390.6  337.36  5488.4  335.33
  5600.3  341.17    5702  342.23  5732.5   337.2  5770.2  343.69  5876.6  346.26
#Mann= 6 ,-1 , 0
  4164.5     .05       0  4489.1     .12       0  5003.6     .07       0
  5008.1     .12       0  5171.7      .1       0  5276.7     .12       0
Bank Sta=5003.6,5008.1
XS Rating Curve= 0 ,0
Exp/Cntr=0.3,0.1

Type RM Length L Ch R = 1 ,7754    ,431,431,431
BEGIN DESCRIPTION:
Walnut27 14.0
END DESCRIPTION:
XS GIS Cut Line= 3
      2741947.05      6753749.47      2741314.93      6753743.13
      2740602.48      6753658.57
#Sta/Elev= 30
  4328.3  355.08  4369.4  353.49  4429.4  349.07  4559.4  337.43  4609.4  333.64
  4639.4   332.1  4688.2  327.21  4709.4  325.41  4759.4   324.6  4839.4  325.66
  4873.6  325.19  4949.4  326.09  4957.4  319.11  4967.1   318.8  4967.6   318.3
  4971.3   318.3  4971.7   318.8  4979.5  318.83  4989.6  320.34  4999.7  325.79
  5057.4  326.63  5193.3  328.69  5211.5  329.59  5257.3  330.26  5382.6  333.66
    5483  336.12  5523.3  336.24  5543.4  338.05  5593.8  338.35  5677.9   342.9
#Mann= 9 ,-1 , 0
  4328.3     .05       0  4688.2     .12       0  4873.6     .05       0
  4967.1     .05       0  4971.7     .05       0  5057.4     .12       0
  5211.5     .05       0  5257.3     .12       0  5382.6     .05       0
Bank Sta=4967.1,4971.7
XS Rating Curve= 0 ,0
Exp/Cntr=0.3,0.1

Type RM Length L Ch R = 1 ,7323    ,478,478,478
BEGIN DESCRIPTION:
Walnut27 13.0
END DESCRIPTION:
XS GIS Cut Line= 4
      2741736.24      6753305.92      2741483.19      6753366.15
        2741426.        6753361.      2740876.04        6753361.
#Sta/Elev= 30
  4683.1  335.35  4734.7  331.63    4792  328.26  4812.4  326.82  4896.7  323.52
  4909.5  323.48  4928.7  324.49  4950.4  324.87  4960.5  318.49  4968.2  317.09
  4968.7  316.59  4972.4  316.59  4972.8  317.09  4980.6   317.3  4990.6  322.82
  4998.1  324.63  5050.6   323.6  5080.6  323.65  5090.6  323.02  5148.4  322.82
  5190.6  323.61  5220.6  323.37    5305  326.54  5325.1  327.51  5330.6  327.78
  5350.6  330.58  5380.6  335.66  5420.6  340.13  5430.6   342.2  5550.6  353.59
#Mann= 8 ,-1 , 0
  4683.1     .05       0    4792     .12       0  4928.7      .1       0
  4968.2     .07       0  4972.8      .1       0  5148.4     .12       0
    5305      .1       0  5325.1     .12       0
Bank Sta=4968.2,4972.8
XS Rating Curve= 0 ,0
Exp/Cntr=0.3,0.1

Type RM Length L Ch R = 1 ,6845    ,233,233,233
BEGIN DESCRIPTION:
Walnut27 12.0
END DESCRIPTION:
XS GIS Cut Line= 3
      2741381.32      6752999.05        2741276.        6752961.
      2740930.58      6752963.02
#Sta/Elev= 30
    4888   322.9  4904.3  322.05  4928.6  321.83  4946.8  322.31    4954  319.33
  4959.3     322  4968.1  321.99  4984.6  317.95    4990  321.03  4997.3  310.67
  5002.5  310.67  5007.6  309.55  5008.1  309.05  5011.8  309.05  5012.3  309.55
    5030  315.93    5040  320.51    5050  321.57    5066  321.57    5110  322.67
    5130  323.75    5180  325.04    5210  327.29    5230  327.89    5240  328.66
    5270  329.96    5300  332.37    5330  334.04    5340  335.72  5345.4  335.17
#Mann= 5 ,-1 , 0
    4888     .12       0  5007.6     .07       0  5012.3     .12       0
    5066      .1       0    5066     .12       0
Bank Sta=5007.6,5012.3
XS Rating Curve= 0 ,0
Exp/Cntr=0.3,0.1

Type RM Length L Ch R = 1 ,6612    ,229,229,229
BEGIN DESCRIPTION:
Walnut27 11.4
END DESCRIPTION:
XS GIS Cut Line= 3
      2741407.15      6752799.37      2741300.02      6752726.34
      2740953.41      6752760.07
#Sta/Elev= 30
  4845.8  320.46  4873.5  319.22  4895.6  319.83  4931.9     320  4968.2   319.8
    4980  319.19  4989.5  316.26  4997.2  309.35  4997.7  308.85  5001.4  308.85
  5001.9  309.35  5009.6  310.56  5019.7  318.79  5039.8  319.43    5075  319.79
  5110.1  321.18  5120.2  320.87  5130.2  321.69  5140.2  321.94  5150.3   321.8
  5181.9  322.56  5200.5  323.24  5220.6  324.72  5230.7  324.81  5241.2  325.89
  5250.8  327.25  5270.9  328.09  5278.8  329.69    5311  332.78  5323.7   333.5
#Mann= 4 ,-1 , 0
  4845.8      .1       0  4997.2     .07       0  5001.9      .1       0
  5241.2     .12       0
Bank Sta=4997.2,5001.9
XS Rating Curve= 0 ,0
Exp/Cntr=0.3,0.1

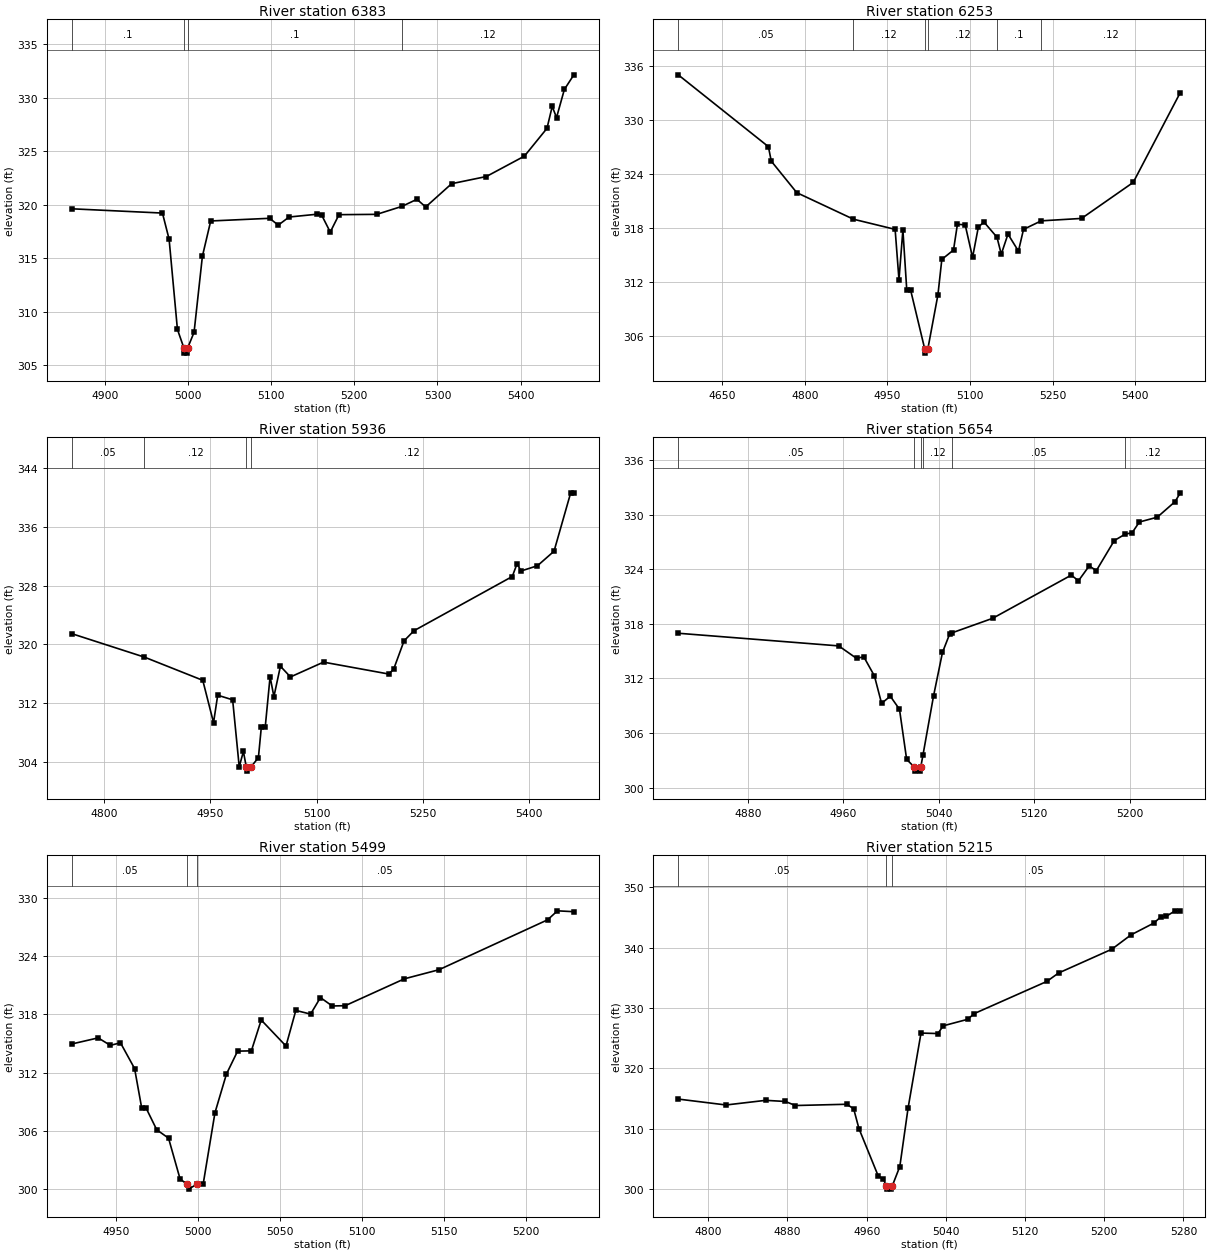
Type RM Length L Ch R = 1 ,6383    ,130,130,130
BEGIN DESCRIPTION:
Walnut27 11.2
END DESCRIPTION:
XS GIS Cut Line= 4
      2741508.83      6752701.39      2741457.07      6752608.96
      2741342.94      6752605.19      2740975.05      6752713.01
#Sta/Elev= 30
  4860.4  319.62  4969.4  319.22  4977.4  316.77  4987.4  308.33  4995.1  306.61
  4995.6  306.11  4999.3  306.11  4999.8  306.61  5007.4  308.06  5017.4  315.17
  5027.4  318.48  5098.2  318.73  5108.6  318.09  5121.6  318.85    5155  319.11
  5160.7  319.04  5171.1  317.44  5181.6  319.07    5227   319.1  5257.4  319.85
  5275.3  320.51  5285.8  319.79    5317  321.97  5358.7  322.64  5404.5  324.55
  5431.6  327.15  5437.9   329.2  5443.1  328.16  5452.5  330.79  5463.9  332.16
#Mann= 4 ,-1 , 0
  4860.4      .1       0  4995.1     .07       0  4999.8      .1       0
  5257.4     .12       0
Bank Sta=4995.1,4999.8
XS Rating Curve= 0 ,0
Exp/Cntr=0.3,0.1

Type RM Length L Ch R = 1 ,6253    ,317,317,317
BEGIN DESCRIPTION:
Walnut27 11.0
END DESCRIPTION:
XS GIS Cut Line= 4
      2741791.73      6752344.59      2741487.51      6752404.11
      2741331.84      6752557.12      2740963.98      6752664.94
#Sta/Elev= 30
  4570.2  335.07  4733.9  327.07  4739.1  325.46  4785.4  321.95  4888.4  318.99
    4964  317.86    4971  312.25  4978.1   317.8  4985.1  311.13  4992.2  311.08
  5017.6  304.58  5018.5  304.08  5023.5  304.58  5041.7  310.57  5048.8  314.52
    5070  315.56  5077.1  318.43  5091.2  318.36  5104.6  314.74    5115  318.09
  5125.1  318.69  5148.9  316.99  5156.7   315.1  5168.9  317.33  5187.9  315.44
  5197.1  317.86  5229.3  318.81  5302.5  319.08  5396.3  323.09  5481.8   333.1
#Mann= 6 ,-1 , 0
  4570.2     .05       0  4888.4     .12       0  5017.6     .07       0
  5023.5     .12       0  5148.9      .1       0  5229.3     .12       0
Bank Sta=5017.6,5023.5
XS Rating Curve= 0 ,0
Exp/Cntr=0.3,0.1

Type RM Length L Ch R = 1 ,5936    ,282,282,282
BEGIN DESCRIPTION:
Walnut27 10.0
END DESCRIPTION:
XS GIS Cut Line= 3
      2741436.01      6752125.49      2741210.51      6752270.45
      2740806.32      6752447.65
#Sta/Elev= 30
  4754.2  321.44  4856.9  318.24  4939.3  315.08  4954.5  309.31  4960.4  313.05
  4981.5  312.42  4990.8  303.29  4996.7  305.38  5000.9   303.2  5001.9   302.7
  5006.8   303.2  5017.9  304.54    5022  308.67  5027.5  308.67  5034.4  315.57
  5039.8  312.86    5049     317  5063.2  315.54  5109.9  317.56  5201.9  315.94
  5208.9  316.57  5223.7  320.46  5237.7  321.84  5376.6  329.23  5383.4  330.98
  5388.9  329.98  5412.2   330.7  5435.6  332.68    5459  340.59  5463.6  340.64
#Mann= 4 ,-1 , 0
  4754.2     .05       0  4856.9     .12       0  5000.9     .07       0
  5006.8     .12       0
Bank Sta=5000.9,5006.8
XS Rating Curve= 0 ,0
Exp/Cntr=0.3,0.1

Type RM Length L Ch R = 1 ,5654    ,155,155,155
BEGIN DESCRIPTION:
Walnut27 9.4
END DESCRIPTION:
XS GIS Cut Line= 3
      2741222.22      6751959.99      2741179.76      6751990.73
      2740874.63      6752196.59
#Sta/Elev= 30
  4821.8  316.97  4956.2  315.58  4971.1  314.21  4977.2  314.38  4986.1  312.28
  4992.1  309.26  4999.4  310.05  5007.1  308.61  5013.1   303.1  5019.1  302.31
  5020.1  301.81  5024.1  301.81    5025  302.31  5026.8   303.6  5035.6  310.06
  5043.1  314.86  5049.1  316.88  5051.4  317.03  5085.1  318.61    5151  323.36
    5157  322.74    5166  324.37    5172  323.86    5187  327.16  5195.9  327.85
    5202  328.03    5208   329.2    5223  329.73  5237.9  331.44  5242.3  332.41
#Mann= 6 ,-1 , 0
  4821.8     .05       0  5019.1     .05       0    5025     .05       0
  5026.8     .12       0  5051.4     .05       0  5195.9     .12       0
Bank Sta=5019.1,5025
XS Rating Curve= 0 ,0
Exp/Cntr=0.3,0.1

Type RM Length L Ch R = 1 ,5499    ,284,284,284
BEGIN DESCRIPTION:
Walnut27 9.0
END DESCRIPTION:
XS GIS Cut Line= 4
      2741039.17      6751911.65      2741004.02      6751936.55
      2740961.55      6751980.48       2740793.1      6752091.81
#Sta/Elev= 30
  4923.2  314.95  4939.3  315.58  4946.7  314.81  4952.9  315.07  4961.5  312.41
  4965.8  308.36  4968.4  308.36    4975  306.08  4982.2  305.21  4989.2  301.01
  4993.4  300.44  4994.4  299.94  4999.4  300.44  5003.3  300.45  5010.5  307.84
  5017.5  311.84  5024.3  314.21  5032.7  314.24  5038.7  317.43  5053.8  314.74
  5059.8  318.42  5068.8  318.04  5074.8  319.75    5082  318.88  5089.9  318.91
    5126  321.69  5147.1  322.63  5213.3  327.79  5219.3  328.72  5229.3  328.63
#Mann= 3 ,-1 , 0
  4923.2     .05       0  4993.4     .05       0  4999.4     .05       0
Bank Sta=4993.4,4999.4
XS Rating Curve= 0 ,0
Exp/Cntr=0.3,0.1

Type RM Length L Ch R = 1 ,5215    ,287,287,287
BEGIN DESCRIPTION:
Walnut27 8.5
END DESCRIPTION:
XS GIS Cut Line= 3
      2740954.27      6751826.71      2740814.79      6751822.15
      2740471.08      6751952.34
#Sta/Elev= 30
  4769.7  314.89    4818  313.91    4858  314.68    4878  314.49    4888  313.82
    4940  314.03  4946.9  313.27  4952.2     310  4971.7  302.13    4977   301.6
  4979.8  300.45  4980.8  299.95  4984.8  299.95  4985.8  300.45  4993.5   303.7
  5001.8  313.35  5014.9  325.84    5032  325.76  5037.3  327.04  5062.2  328.13
  5068.4  329.05  5141.9   334.4  5153.9  335.81  5207.6  339.75    5227  342.13
  5250.1  344.09  5257.2  345.13  5262.5   345.2  5271.5  346.12  5276.8  346.12
#Mann= 3 ,-1 , 0
  4769.7     .05       0  4979.8     .05       0  4985.8     .05       0
Bank Sta=4979.8,4985.8
XS Rating Curve= 0 ,0
Exp/Cntr=0.3,0.1