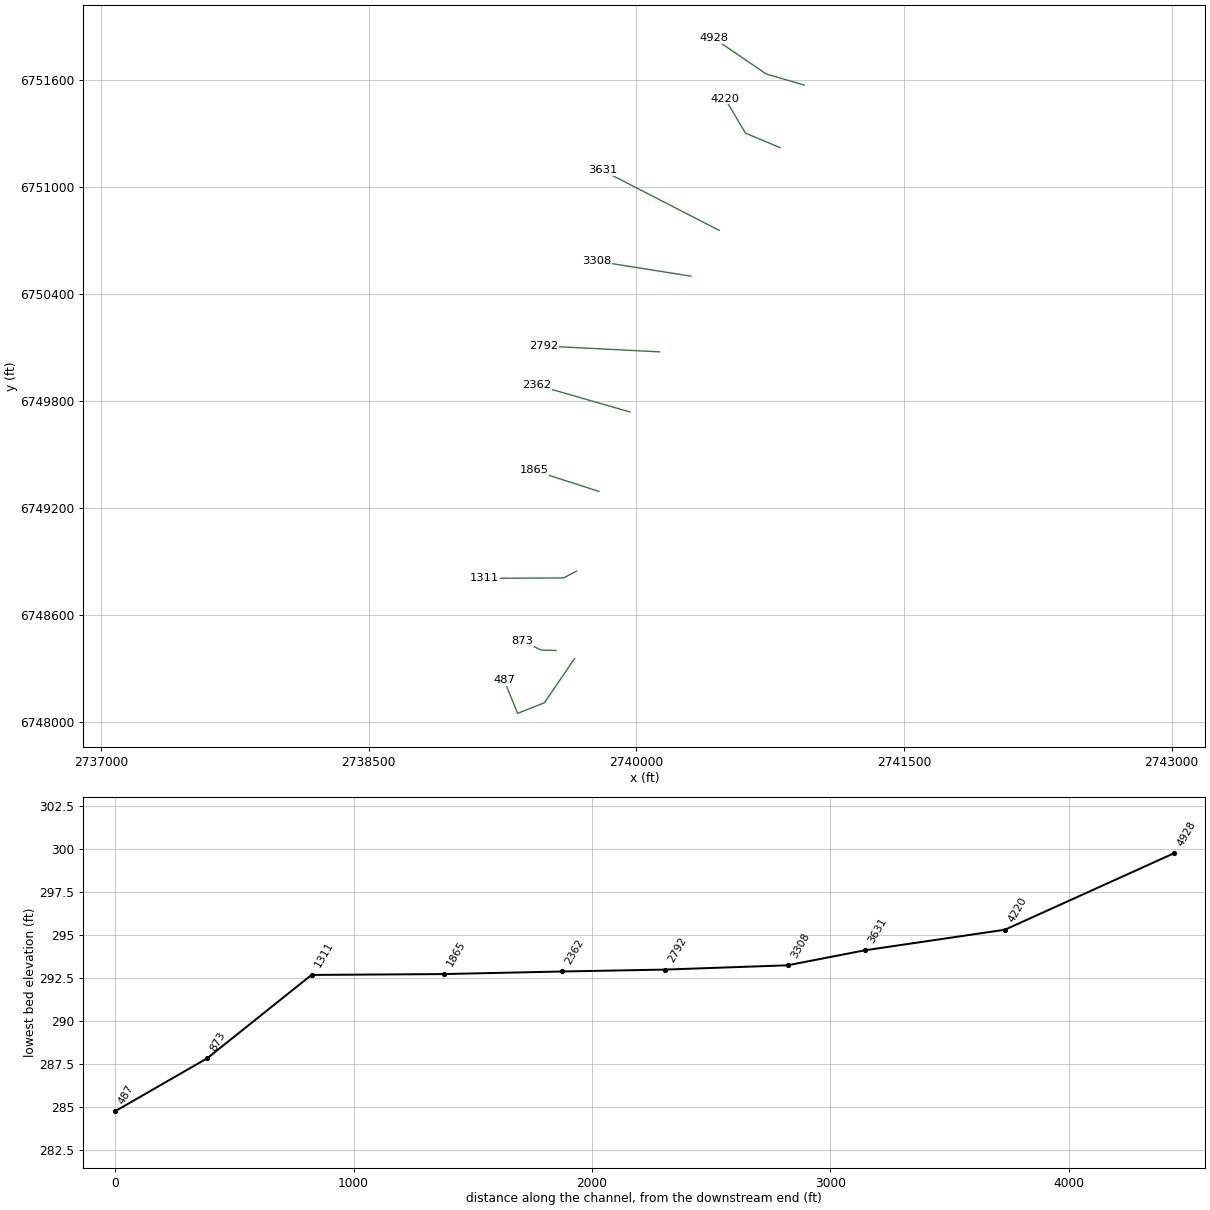
HEC-RAS study Walnut27.prj: Walnut27 Base Level Engineering

--- Walnut27.g01 (geometry) --- (continued)

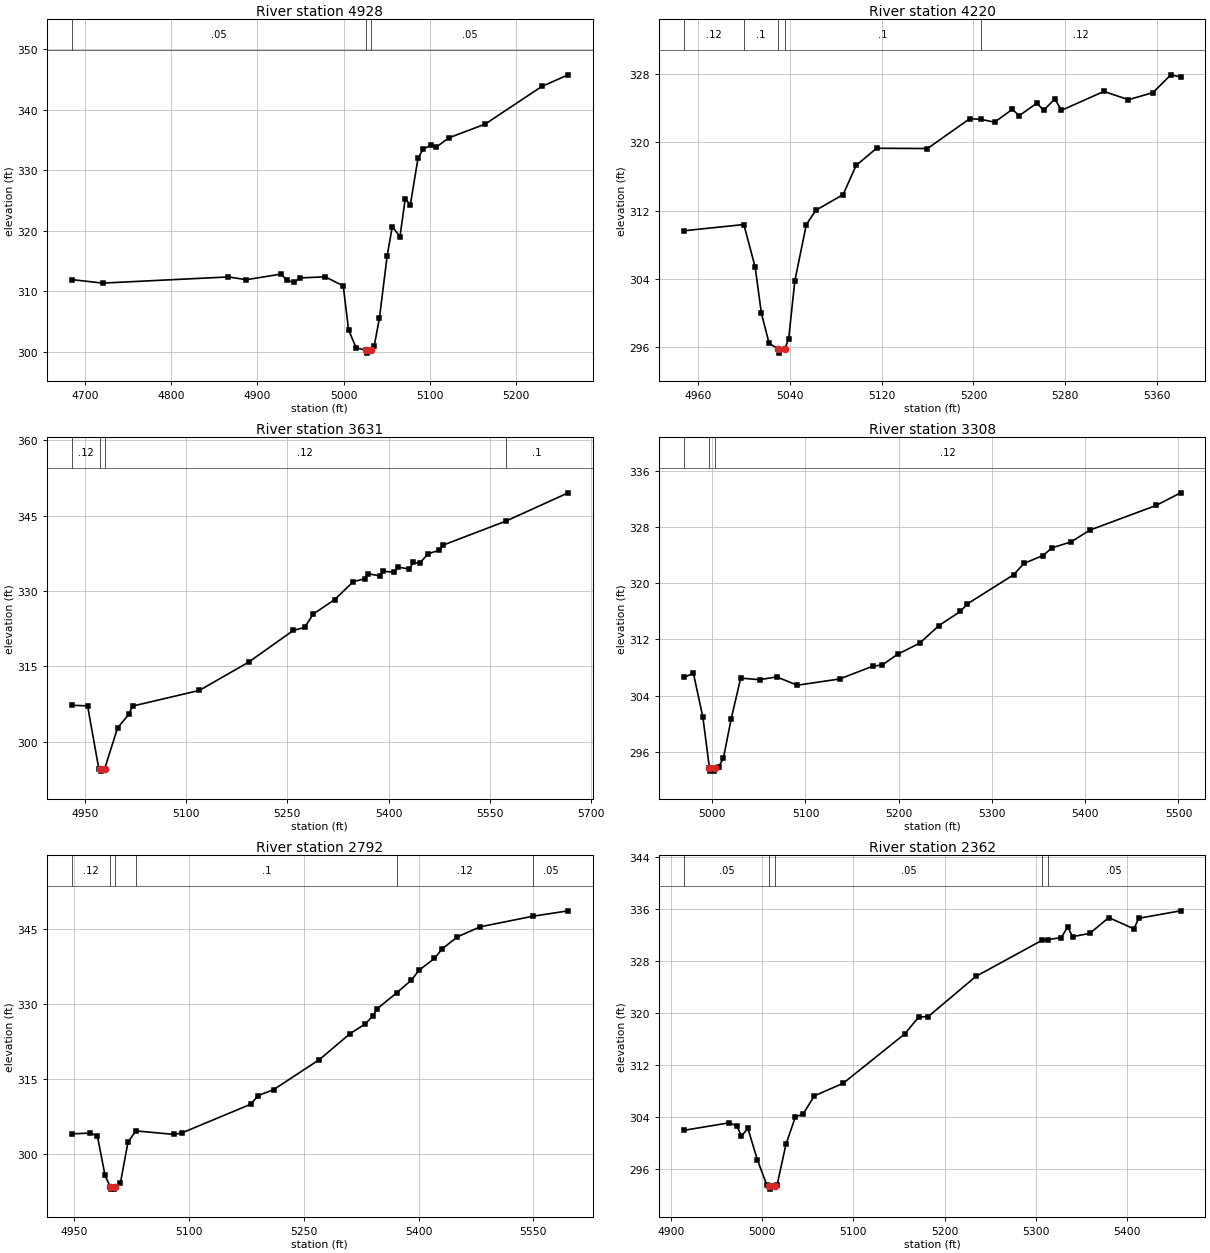
Type RM Length L Ch R = 1 ,4928    ,708,708,708
BEGIN DESCRIPTION:
Walnut27 8.0
END DESCRIPTION:
XS GIS Cut Line= 3
      2740940.79      6751570.71      2740727.81      6751632.83
      2740434.62      6751832.53
#Sta/Elev= 30
  4684.1  311.93  4720.3  311.35  4866.2  312.37    4887  311.91  4927.8  312.85
  4933.9  311.79  4942.8  311.48  4948.8   312.2  4978.7  312.39  4999.6  310.88
  5005.7  303.63  5014.6  300.63  5026.1  300.27  5027.1  299.77  5032.1  300.27
  5035.6  301.02  5041.6  305.56  5050.5  315.81  5056.5   320.7  5065.4  319.01
  5071.5  325.25  5077.5  324.32  5086.4  332.02  5092.5  333.52  5101.3  334.16
  5107.4  333.82  5122.3  335.38  5164.3  337.64  5230.1  343.87  5260.7  345.79
#Mann= 3 ,-1 , 0
  4684.1     .05       0  5026.1     .05       0  5032.1     .05       0
Bank Sta=5026.1,5032.1
XS Rating Curve= 0 ,0
Exp/Cntr=0.3,0.1

Type RM Length L Ch R = 1 ,4220    ,589,589,589
BEGIN DESCRIPTION:
Walnut27 7.0
END DESCRIPTION:
XS GIS Cut Line= 3
      2740804.47      6751220.27      2740611.66      6751301.31
       2740497.1      6751493.98
#Sta/Elev= 30
  4947.4  309.64  4999.7  310.37  5009.6  305.37    5015  299.99  5021.7  296.49
  5029.5  295.83  5030.5  295.33  5035.5  295.83  5038.8  297.03  5044.2   303.8
  5054.2  310.37  5062.5  312.04  5086.3  313.87  5097.6  317.28  5115.5  319.29
  5159.9  319.26  5196.9  322.76    5207  322.66  5218.4  322.34    5234  323.85
  5239.8  323.09  5255.4  324.57  5261.2  323.73    5271  325.06  5276.8  323.73
  5313.8  325.94  5335.2  324.97  5356.6   325.8  5372.2  327.88  5380.7  327.63
#Mann= 5 ,-1 , 0
  4947.4     .12       0  4999.7      .1       0  5029.5     .07       0
  5035.5      .1       0    5207     .12       0
Bank Sta=5029.5,5035.5
XS Rating Curve= 0 ,0
Exp/Cntr=0.3,0.1

Type RM Length L Ch R = 1 ,3631    ,323,323,323
BEGIN DESCRIPTION:
Walnut27 6.0
END DESCRIPTION:
XS GIS Cut Line= 2
      2740464.35       6750756.2       2739810.3      6751092.61
#Sta/Elev= 30
  4930.5  307.24  4954.3  307.13  4970.9  294.64  4973.3  294.63  4974.4  294.13
  4979.7  294.63  4998.7  302.73  5015.2  305.42  5020.9  307.08  5119.8   310.2
  5192.7  315.82  5259.2  322.16  5275.7  322.73  5288.5  325.41  5320.1  328.27
  5347.9  331.87  5364.5  332.41  5370.1  333.42  5386.6  333.02  5392.3  333.91
  5408.8  333.75  5414.4  334.74    5431  334.37  5436.6  335.69  5445.9  335.51
  5458.8  337.43  5475.3  338.09    5481  339.14  5573.6   343.9    5666  349.54
#Mann= 4 ,-1 , 0
  4930.5     .12       0  4973.3     .07       0  4979.7     .12       0
  5573.6      .1       0
Bank Sta=4973.3,4979.7
XS Rating Curve= 0 ,0
Exp/Cntr=0.3,0.1

Type RM Length L Ch R = 1 ,3308    ,516,516,516
BEGIN DESCRIPTION:
Walnut27 5.0
END DESCRIPTION:
XS GIS Cut Line= 2
      2740306.11      6750499.87      2739779.99      6750583.33
#Sta/Elev= 30
  4969.6   306.6  4979.8  307.17    4990  300.89  4996.9  293.76  4997.9  293.26
  5002.2  293.26  5003.3  293.76  5006.9  293.86    5012  295.13  5020.3  300.69
  5030.5  306.49  5050.7  306.27  5069.2  306.66  5091.2  305.48  5136.6  306.37
  5172.2  308.19  5182.3  308.36  5198.9  309.89  5222.8  311.49  5243.1  313.97
  5266.2  315.98  5273.5  317.04  5323.4  321.21  5334.2   322.8  5354.5  323.92
  5364.6  325.03  5384.8  325.87  5405.1  327.55    5476  331.05  5502.3  332.85
#Mann= 3 ,-1 , 0
  4969.6     .12       0  4996.9     .07       0  5003.3     .12       0
Bank Sta=4996.9,5003.3
XS Rating Curve= 0 ,0
Exp/Cntr=0.3,0.1

Type RM Length L Ch R = 1 ,2792    ,430,430,430
BEGIN DESCRIPTION:
Walnut27 4.0
END DESCRIPTION:
XS GIS Cut Line= 2
      2740129.73      6750075.78      2739481.46       6750108.6
#Sta/Elev= 30
  4946.4  304.06  4970.2  304.21  4980.2  303.68  4990.2  295.76    4997  293.51
    4998  293.01  5002.4  293.01  5003.5  293.51  5010.2  294.14  5020.2  302.37
  5030.4  304.65  5080.3  303.95  5090.3  304.22  5180.4  309.97  5190.4  311.71
  5210.5   312.9  5270.5  318.92  5310.6  324.12  5330.6  326.06  5340.6  327.71
    5346  329.08  5371.8  332.31  5390.7  334.81  5400.7  336.79  5420.7  339.12
  5430.8  341.03  5450.8  343.46  5480.8  345.46  5549.4  347.57  5595.5  348.65
#Mann= 6 ,-1 , 0
  4946.4     .12       0    4997     .07       0  5003.5     .12       0
  5030.4      .1       0  5371.8     .12       0  5549.4     .05       0
Bank Sta=4997,5003.5
XS Rating Curve= 0 ,0
Exp/Cntr=0.3,0.1

Type RM Length L Ch R = 1 ,2362    ,497,497,497
BEGIN DESCRIPTION:
Walnut27 3.0
END DESCRIPTION:
XS GIS Cut Line= 2
      2739963.39      6749739.06      2739440.35      6749889.69
#Sta/Elev= 30
  4914.3  301.96  4963.6  303.11  4972.2  302.68  4977.4  301.07  4984.4  302.26
  4994.8  297.43  5005.2   293.5  5007.8   293.4  5008.8   292.9  5014.3   293.4
  5016.3  293.46  5026.1  299.78  5036.5  304.05  5044.7  304.43  5057.3  307.28
  5088.8   309.2  5156.2   316.8  5171.7  319.42  5182.1  319.49  5234.2  325.67
  5306.5  331.22  5313.2  331.34  5327.8  331.66  5334.9  333.27  5340.2   331.8
  5359.1   332.3  5379.9  334.74  5407.5     333  5412.7  334.63  5458.6  335.78
#Mann= 5 ,-1 , 0
  4914.3     .05       0  5007.8     .04       0  5014.3     .05       0
  5306.5     .12       0  5313.2     .05       0
Bank Sta=5007.8,5014.3
XS Rating Curve= 0 ,0
Exp/Cntr=0.3,0.1

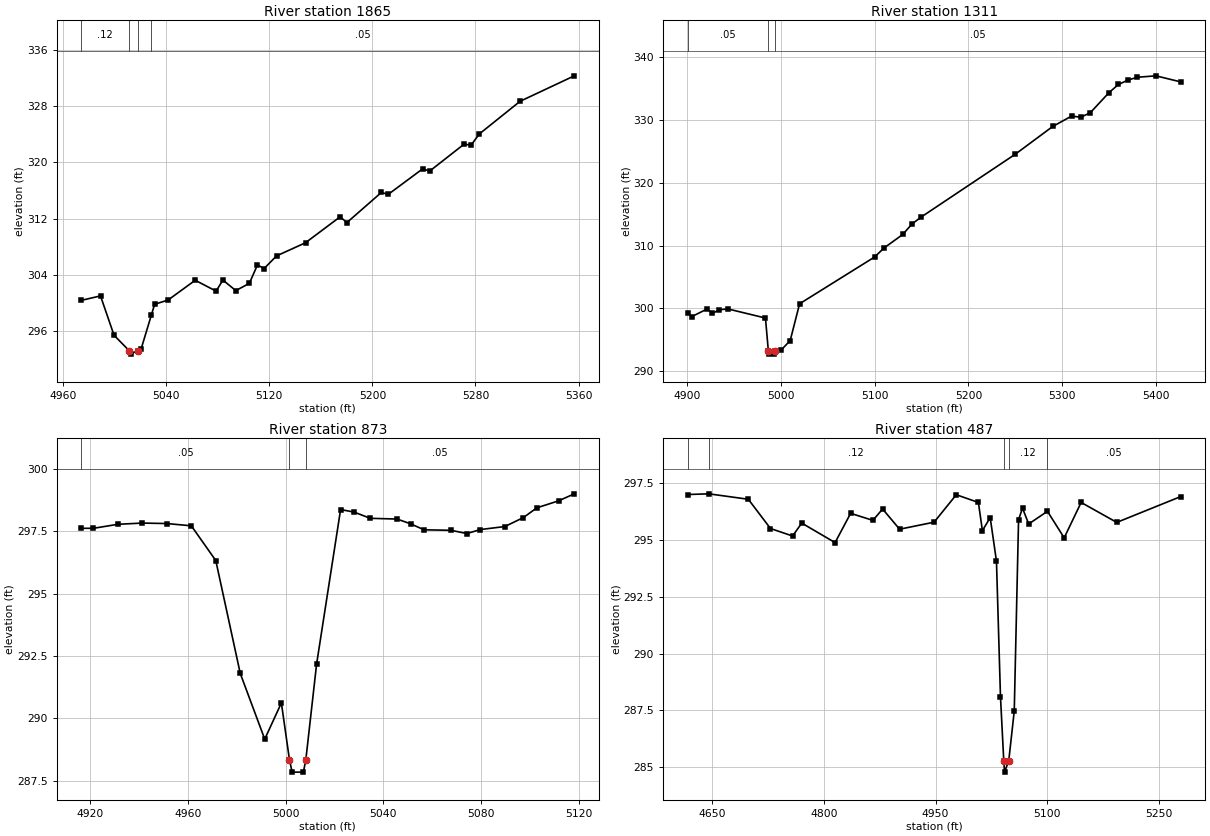
Type RM Length L Ch R = 1 ,1865    ,554,554,554
BEGIN DESCRIPTION:
Walnut27 2.0
END DESCRIPTION:
XS GIS Cut Line= 2
      2739790.08      6749293.86      2739425.97      6749411.01
#Sta/Elev= 30
  4974.2  300.39    4989  301.02  4999.5  295.43  5011.2  293.25  5012.3  292.75
  5017.9  293.25  5020.5  293.47  5028.5  298.32    5031  299.83  5041.4  300.43
  5062.5  303.24  5078.7   301.7    5084  303.27    5094  301.77  5104.5   302.8
  5110.8  305.42    5116  304.91  5125.6   306.7  5148.1  308.57    5175  312.26
  5180.2  311.43    5207  315.72  5212.3  315.44  5239.1  319.08  5244.4  318.74
  5271.2  322.58  5276.5  322.42  5283.1  324.04  5314.6  328.66  5356.7  332.28
#Mann= 4 ,-1 , 0
  4974.2     .12       0  5011.2     .07       0  5017.9     .12       0
  5028.5     .05       0
Bank Sta=5011.2,5017.9
XS Rating Curve= 0 ,0
Exp/Cntr=0.3,0.1

Type RM Length L Ch R = 1 ,1311    ,438,438,438
BEGIN DESCRIPTION:
Walnut27 1.0
END DESCRIPTION:
XS GIS Cut Line= 3
      2739665.51      6748847.59      2739592.41      6748808.88
      2739149.53      6748806.53
#Sta/Elev= 30
  4900.9  299.23  4905.1  298.68  4921.5   299.9  4927.1  299.18  4934.3  299.77
  4943.5   299.9  4983.6  298.45  4986.7   293.2  4987.7   292.7  4992.3   292.7
  4993.4   293.2    5000  293.29    5010  294.87    5020  300.72    5100  308.17
    5110   309.6    5130  311.76    5140  313.45    5150  314.57    5250  324.54
    5290  328.97    5310  330.61    5320  330.44    5330  331.15    5350  334.36
    5360  335.65    5370  336.34    5380   336.8    5400  337.03  5426.5  336.06
#Mann= 3 ,-1 , 0
  4900.9     .05       0  4986.7     .04       0  4993.4     .05       0
Bank Sta=4986.7,4993.4
XS Rating Curve= 0 ,0
Exp/Cntr=0.3,0.1

Type RM Length L Ch R = 1 ,873     ,386,386,386
BEGIN DESCRIPTION:
Walnut27 0.7
END DESCRIPTION:
XS GIS Cut Line= 3
      2739550.87      6748402.06      2739467.51      6748404.83
      2739360.14      6748453.77
#Sta/Elev= 29
  4916.6  297.61  4921.5  297.61  4931.5  297.77  4941.5  297.82  4951.5   297.8
  4961.5  297.71  4971.5  296.32  4981.5   291.8  4991.5  289.17  4998.3  290.62
  5001.6  288.35  5002.7  287.85  5007.3  287.85  5008.3  288.35  5012.7  292.18
  5022.5  298.36    5028  298.26  5034.6  298.01  5045.6  297.98  5051.1  297.79
  5056.6  297.55  5067.6  297.53  5074.1   297.4  5079.6  297.56  5089.6  297.68
  5097.2  298.04  5102.7  298.43  5111.6  298.71    5118  298.99
#Mann= 3 ,-1 , 0
  4916.6     .05       0  5001.6     .04       0  5008.3     .05       0
Bank Sta=5001.6,5008.3
XS Rating Curve= 0 ,0
Exp/Cntr=0.3,0.1

Type RM Length L Ch R = 1 ,487     ,0,0,0
BEGIN DESCRIPTION:
Walnut27 0.5
END DESCRIPTION:
XS GIS Cut Line= 4
      2739653.87      6748357.24      2739485.08      6748109.67
      2739334.91       6748049.9      2739258.49      6748235.95
#Sta/Elev= 30
  4617.1  297.01  4645.2  297.04  4698.3   296.8  4728.1  295.51  4757.8  295.18
  4770.1  295.75  4814.9  294.89  4835.8  296.18  4865.7  295.87  4878.8  296.37
  4901.6  295.48    4948  295.79  4977.8     297  5007.5  296.66  5012.9  295.42
  5023.4  295.99  5031.8  294.07  5037.2  288.09  5041.6  285.27  5042.6  284.77
  5048.3  285.27  5055.7  287.46  5061.5   295.9  5066.8  296.41  5075.1  295.71
  5100.3  296.27  5122.8   295.1  5145.6  296.66  5193.5  295.78  5279.5  296.92
#Mann= 5 ,-1 , 0
  4617.1     .05       0  4645.2     .12       0  5041.6     .07       0
  5048.3     .12       0  5100.3     .05       0
Bank Sta=5041.6,5048.3
XS Rating Curve= 0 ,0
Exp/Cntr=0.3,0.1

Chan Stop Cuts=-1
Use User Specified Reach Order=0
Composite Channel Slope=5