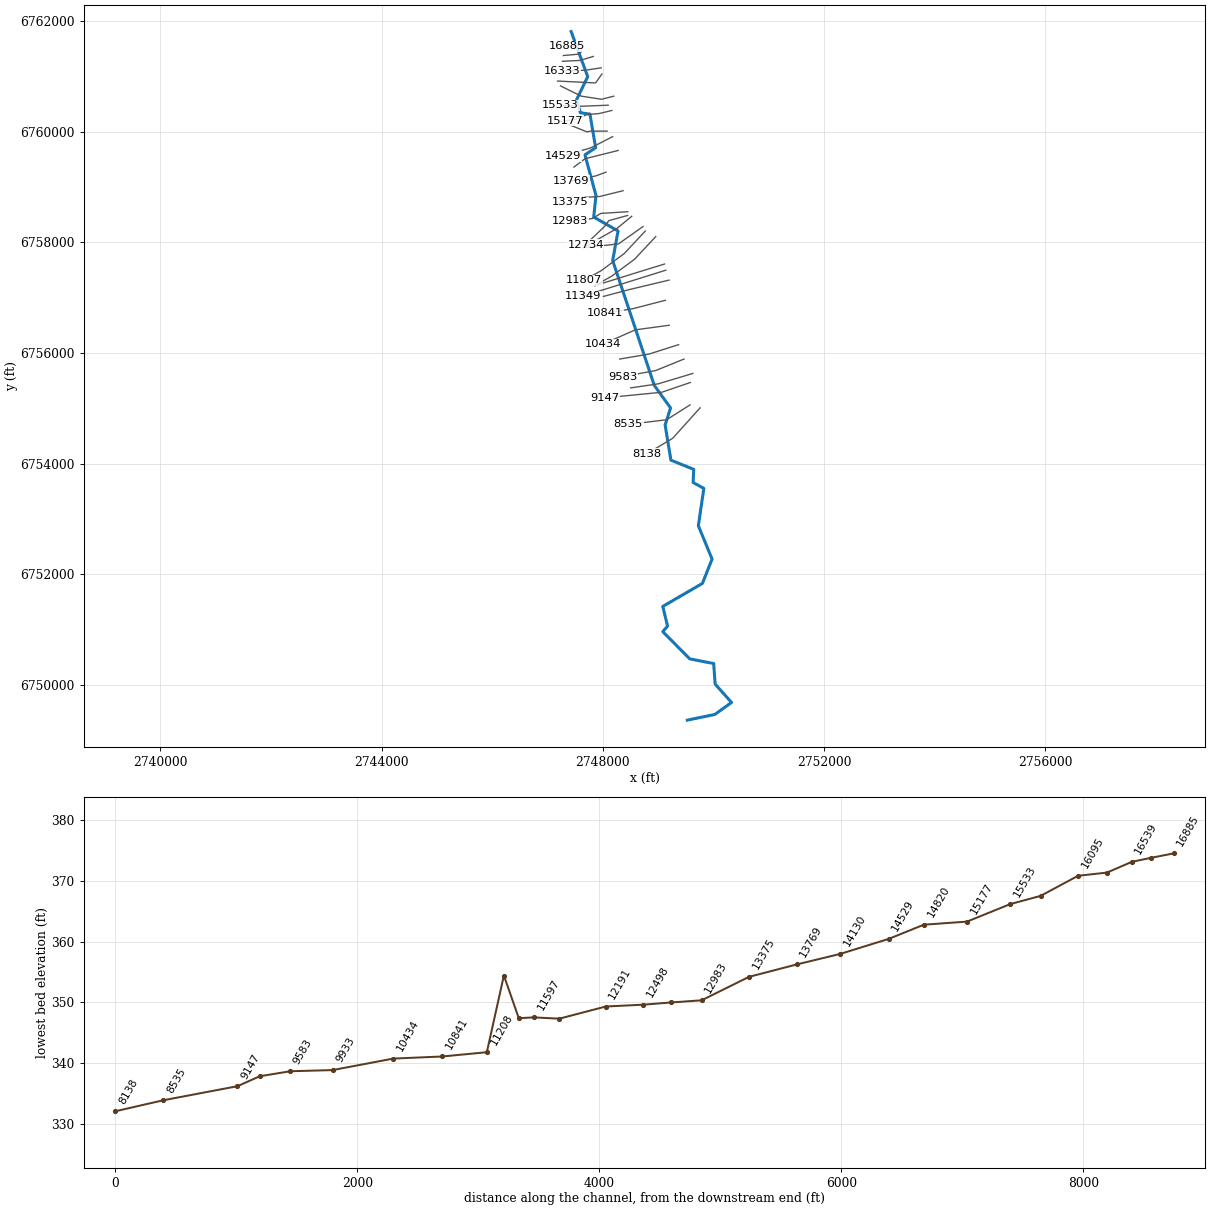
--- Walnut3.prj (project) ---

Proj Title=Walnut3 Base Level Engineering
Current Plan=p01
Default Exp/Contr=0.3,0.1
English Units
Geom File=g01
Flow File=f01
Plan File=p01
Y Axis Title=Elevation
X Axis Title(PF)=Main Channel Distance
X Axis Title(XS)=Station
BEGIN DESCRIPTION:
Walnut3
END DESCRIPTION:
DSS Export Rating Curves= 0
DSS Export Rating Curve Sorted= 0
DSS Export Volume Flow Curves= 0
DXF OffsetX= 0
DXF OffsetY= 0
DXF ScaleX= 1
DXF ScaleY= 10

--- Walnut3.p01 (plan) ---

Plan Title=Multiple Run
Program Version=4.10
Short Identifier=Multiple
Geom File=g01
Flow File=f01
Subcritical Flow
K Sum by GR= 0
Std Step Tol= 0.01
Critical Tol= 0.01
Num of Std Step Trials= 20
Max Error Tol= 0.3
Flow Tol Ratio= 0.001
Split Flow NTrial= 30
Split Flow Tol= 0.02
Split Flow Ratio= 0.02
Log Output Level= 0
Friction Slope Method= 1
Unsteady Friction Slope Method= 2
Unsteady Bridges Friction Slope Method= 1
Parabolic Critical Depth
Global Vel Dist= 1 , 1 , 1
Global Log Level= 0
CheckData=True
Encroach Param=-1 ,0,0, 0
BEGIN DESCRIPTION:
Multiple Run
END DESCRIPTION:
Computation Interval=1HOUR
Output Interval=1HOUR
Run HTab= 0
Run UNet= 0
Run PostProcess= 0
Run WQNet= 0
UNET Theta= 1
UNET Theta Warmup= 1
UNET ZTol= 0.02
UNET ZSATol= 0.05
UNET MxIter= 20
UNET MaxInSteps= 0
UNET DtIC= 0
UNET DtMin= 0
UNET MaxCRTS= 20
UNET WFStab= 2
UNET SFStab= 1
UNET WFX= 1
UNET SFX= 1
UNET DSS MLevel= 4
UNET DZMax Abort= 100
UNET Convert EG Bridges= 0
UNET Use Existing IB Tables=-1
UNET Froude Reduction=False
UNET Froude Limit= 1
UNET Froude Power= 10
UNET Time Slicing=0,0, 5
UNET Junction Losses=0
Instantaneous Interval=1HOUR
Write IC File= 0
Write IC File at Sim End=0
Echo Input=False
Echo Parameters=False
Echo Output=False
Write Detailed= 0
WQ AD Non Conservative
WQ ULTIMATE=-1
WQ Max Comp Step=1HOUR
WQ Output Interval=15MIN
WQ Output Selected Increments= 0
WQ Output face flow=0
WQ Output face velocity=0
WQ Output face area=0
WQ Output face dispersion=0
WQ Output cell volume=0
WQ Output cell surface area=0
WQ Output cell continuity=0
WQ Output cumulative cell continuity=0
WQ Output face conc=0
WQ Output face dconc_dx=0
WQ Output face courant=0
WQ Output face peclet=0
WQ Output face adv mass=0
WQ Output face disp mass=0
WQ Output cell mass=0
WQ Output cell source sink temp=0
WQ Output cell source sink nsm=0
WQ Output MaxMinRange=-1
WQ Daily Max Min Mean=-1
WQ Daily Range=0
WQ Daily Time=0
WQ Create Restart=0
WQ Fixed Restart=0
WQ System Summary=0
WQ Use Fixed Temperature=0
Sorting and Armoring Iterations= 10
XS Update Threshold= 0.02
Hydraulics Update Threshold= 0.02
Energy Slope Method= 1
Volume Change Method= 0
XS Weighting Method= 0
Number of US Weighted Cross Sections= 1
Number of DS Weighted Cross Sections= 1
Upstream XS Weight=0.25
Main XS Weight=0.5
Downstream XS Weight=0.25
Number of DS XS's Weighted with US Boundary= 1
Upstream Boundary Weight= 1
Weight of XSs Associated with US Boundary= 0
Number of US XS's Weighted with DS Boundary= 1
Downstream Boundary Weight= 0.5
Weight of XSs Associated with DS Boundary= 0.5
Sediment Output Level= 4
Mass or Volume Output= 0
Output Increment Type= 1
Profile and TS Output Increment= 10
XS Output Flag= 0
XS Output Increment= 10
Disregard all LS=0
Disregard all Conn=0
Disregard all Breaches=0
Disregard all Pumps=0

--- Walnut3.f01 (steady flow) ---

Flow Title=Multiple
Number of Profiles=7
Profile Names=10-year,25-year,50-year,1pct_min,100-year,1pct_plu,500-year
River Rch & RM= Walnut3,Reach-1,16885
     287     371     437     257     512    1022     703
River Rch & RM= Walnut3,Reach-1,15785
     390     509     602     354     707    1411     976
River Rch & RM= Walnut3,Reach-1,12983
     654     882    1068     642    1281    2555    1846
River Rch & RM= Walnut3,Reach-1,7897
     650     864    1035     614    1225    2445    1722
River Rch & RM= Walnut3,Reach-1,1553
    1152    1593    1960    1194    2383    4755    3535
Boundary for River Rch & Prof#=Walnut3,Reach-1,1
Up Type=0
Dn Type=3
Dn Slope=0.005
Boundary for River Rch & Prof#=Walnut3,Reach-1,2
Up Type=0
Dn Type=3
Dn Slope=0.005
Boundary for River Rch & Prof#=Walnut3,Reach-1,3
Up Type=0
Dn Type=3
Dn Slope=0.005
Boundary for River Rch & Prof#=Walnut3,Reach-1,4
Up Type=0
Dn Type=3
Dn Slope=0.005
Boundary for River Rch & Prof#=Walnut3,Reach-1,5
Up Type=0
Dn Type=3
Dn Slope=0.005
Boundary for River Rch & Prof#=Walnut3,Reach-1,6
Up Type=0
Dn Type=3
Dn Slope=0.005
Boundary for River Rch & Prof#=Walnut3,Reach-1,7
Up Type=0
Dn Type=3
Dn Slope=0.005

--- Walnut3.g01 (geometry) ---

Geom Title=Existing Conditions
Program Version=4.10

River Reach=Walnut3         ,Reach-1
Reach XY= 30
        2747426.        6761811.      2747725.48      6760995.78
       2747525.6      6760581.13      2747592.22      6760343.44
      2747766.83      6760318.04      2747868.71      6759710.89
      2747675.54      6759581.31      2747875.61      6758845.84
      2747833.79      6758457.58      2748274.47      6758205.17
      2748176.77       6757671.7      2748929.62       6755412.5
      2749224.04      6755005.11       2749125.5      6754700.83
      2749229.43      6754062.22      2749642.78      6753895.31
      2749631.28      6753658.29      2749825.14      6753550.69
      2749725.97      6752876.35      2749974.52      6752272.99
      2749799.63      6751833.87      2749083.36      6751417.38
      2749168.89      6751060.99      2749083.12        6750961.
      2749569.94      6750469.14      2750003.35      6750385.03
      2750029.49      6750012.44      2750326.27      6749680.94
       2750024.5      6749464.46        2749526.        6749361.

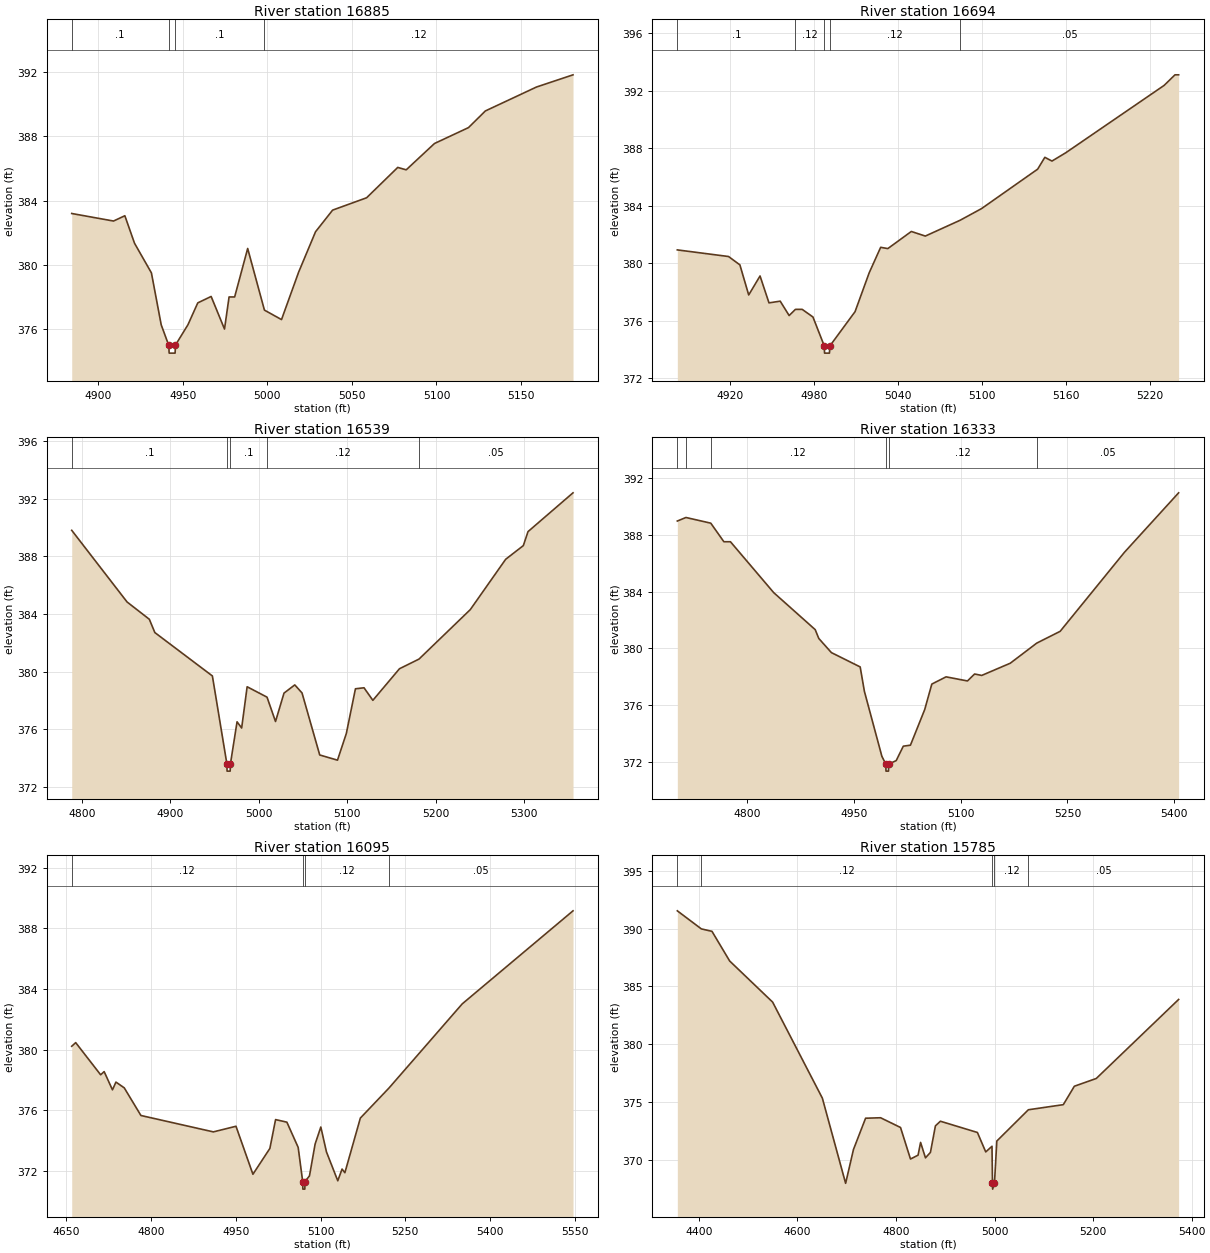
Type RM Length L Ch R = 1 ,16885   ,191,191,191
BEGIN DESCRIPTION:
Walnut3 35.0
END DESCRIPTION:
XS GIS Cut Line= 3
      2747637.42      6761612.08      2747556.32      6761565.36
      2747354.47      6761546.85
#Sta/Elev= 30
  4884.4   383.2  4909.1  382.73  4915.8  383.06  4921.5  381.35  4931.5   379.5
  4937.3  376.26  4941.7     375    4942   374.5  4945.5   374.5  4945.7     375
  4953.1  376.27  4958.9  377.63  4966.8  378.03  4974.7     376  4977.4     378
  4980.7     378  4988.4  381.02  4998.3  377.18  5008.4  376.59  5018.5  379.54
  5028.5  382.06  5038.6  383.41  5058.7  384.18  5077.1  386.07  5082.1  385.92
  5098.8  387.56  5118.9  388.55  5128.9  389.59  5159.1  391.08  5180.7  391.84
#Mann= 4 ,-1 , 0
  4884.4      .1       0  4941.7     .07       0  4945.7      .1       0
  4998.3     .12       0
Bank Sta=4941.7,4945.7
XS Rating Curve= 0 ,0
Exp/Cntr=0.3,0.1

Type RM Length L Ch R = 1 ,16694   ,155,155,155
BEGIN DESCRIPTION:
Walnut3 34.0
END DESCRIPTION:
XS GIS Cut Line= 3
      2747624.18      6761455.19      2747556.32      6761401.43
      2747285.74      6761377.64
#Sta/Elev= 30
  4882.2  380.93  4918.8  380.47  4926.9  379.89  4933.2   377.8  4941.3  379.12
  4947.7  377.25  4955.7  377.37  4962.1  376.37  4966.6   376.8  4971.4   376.8
  4979.1  376.27  4987.2  374.26  4987.4  373.76  4990.9  373.76  4991.2  374.26
  5009.2  376.64  5019.3  379.34  5027.5  381.11  5032.6  381.02  5049.4  382.21
  5059.4  381.89  5084.3  382.99  5099.6   383.8  5139.7  386.54  5144.8  387.36
  5149.9   387.1  5159.8  387.68  5230.1  392.36  5237.8  393.09  5240.4  393.09
#Mann= 5 ,-1 , 0
  4882.2      .1       0  4966.6     .12       0  4987.2     .07       0
  4991.2     .12       0  5084.3     .05       0
Bank Sta=4987.2,4991.2
XS Rating Curve= 0 ,0
Exp/Cntr=0.3,0.1

Type RM Length L Ch R = 1 ,16539   ,206,206,206
BEGIN DESCRIPTION:
Walnut3 33.0
END DESCRIPTION:
XS GIS Cut Line= 3
      2747825.98      6761360.99      2747587.35      6761289.35
       2747269.9      6761273.48
#Sta/Elev= 30
  4788.5  389.81  4851.1  384.84  4876.3  383.64  4882.5  382.72  4947.6  379.71
    4964  373.61  4964.2  373.11  4967.7  373.11    4968  373.61  4975.5  376.53
  4980.7   376.1  4986.9  378.96  5009.4  378.24    5019  376.55  5028.6  378.52
  5040.8  379.09    5049  378.53    5069  374.23  5089.1  373.87  5099.1  375.72
  5109.4  378.82  5119.1  378.89  5129.1  378.02  5159.2  380.21  5181.3  380.88
  5239.3  384.31  5279.3   387.8  5299.3  388.75  5304.6  389.72  5355.5  392.41
#Mann= 5 ,-1 , 0
  4788.5      .1       0    4964     .07       0    4968      .1       0
  5009.4     .12       0  5181.3     .05       0
Bank Sta=4964,4968
XS Rating Curve= 0 ,0
Exp/Cntr=0.3,0.1

Type RM Length L Ch R = 1 ,16333   ,238,238,238
BEGIN DESCRIPTION:
Walnut3 32.0
END DESCRIPTION:
XS GIS Cut Line= 3
      2747969.68      6761155.09        2747676.        6761111.
      2747269.91      6761100.51
#Sta/Elev= 30
  4702.7  388.98  4714.8  389.23  4749.6  388.83    4768  387.52  4777.2  387.52
  4837.9  383.93  4896.1  381.32  4901.1   380.7  4918.8   379.7  4959.2  378.69
  4965.1  376.97  4989.6  372.39  4995.1  371.84  4995.4  371.34  4998.9  371.34
  4999.1  371.84  5009.7  372.08  5019.7   373.1  5029.7  373.17  5049.7  375.68
  5059.7  377.48  5079.7  377.99  5109.7   377.7  5119.7  378.19  5129.7  378.09
  5169.7  378.95  5206.9  380.37  5239.7   381.2  5329.8  386.77  5405.9  390.97
#Mann= 6 ,-1 , 0
  4702.7     .12       0  4714.8      .1       0  4749.6     .12       0
  4995.1     .07       0  4999.1     .12       0  5206.9     .05       0
Bank Sta=4995.1,4999.1
XS Rating Curve= 0 ,0
Exp/Cntr=0.3,0.1

Type RM Length L Ch R = 1 ,16095   ,310,310,310
BEGIN DESCRIPTION:
Walnut3 31.0
END DESCRIPTION:
XS GIS Cut Line= 3
      2747983.28       6761044.2      2747867.25      6760882.02
        2747180.      6760916.16
#Sta/Elev= 30
  4659.4  380.23  4666.4  380.47  4710.6  378.35  4716.8  378.56  4731.5  377.36
  4737.7  377.87  4752.4  377.49  4781.9  375.67  4910.1  374.59  4950.2  374.96
  4980.2   371.8  5010.2   373.5  5020.3   375.4  5040.3  375.23  5060.3  373.57
  5068.3  371.32  5068.6  370.82  5072.1  370.82  5072.3  371.32  5080.3  371.69
  5090.3  373.79  5100.4  374.91  5110.4  373.27  5130.4  371.37    5138  372.14
    5143   371.9  5170.4   375.5  5221.1  377.48  5350.7  383.02  5546.9  389.15
#Mann= 4 ,-1 , 0
  4659.4     .12       0  5068.3     .07       0  5072.3     .12       0
  5221.1     .05       0
Bank Sta=5068.3,5072.3
XS Rating Curve= 0 ,0
Exp/Cntr=0.3,0.1

Type RM Length L Ch R = 1 ,15785   ,252,252,252
BEGIN DESCRIPTION:
Walnut3 30.0
END DESCRIPTION:
XS GIS Cut Line= 4
      2748196.29      6760642.49      2747975.16      6760586.59
      2747610.11      6760643.09      2747233.34      6760828.05
#Sta/Elev= 30
  4356.4  391.53  4405.1  389.97  4426.7  389.76  4462.6   387.2  4549.8  383.65
  4650.7  375.36  4697.9  368.01  4713.8  370.93  4738.4  373.63  4768.8  373.67
  4809.3  372.83  4829.5  370.11  4844.9  370.44    4850  371.54  4859.9  370.21
    4870  370.68  4880.1  372.97  4890.2  373.37  4965.3   372.4  4982.2  370.72
  4994.9  371.21  4995.9  368.01  4996.2  367.51  4999.9  368.01  5004.7  371.66
  5068.7  374.36  5139.6   374.8    5162  376.39  5206.5  377.06  5373.6  383.88
#Mann= 5 ,-1 , 0
  4356.4     .05       0  4405.1     .12       0  4995.9     .07       0
  4999.9     .12       0  5068.7     .05       0
Bank Sta=4995.9,4999.9
XS Rating Curve= 0 ,0
Exp/Cntr=0.3,0.1

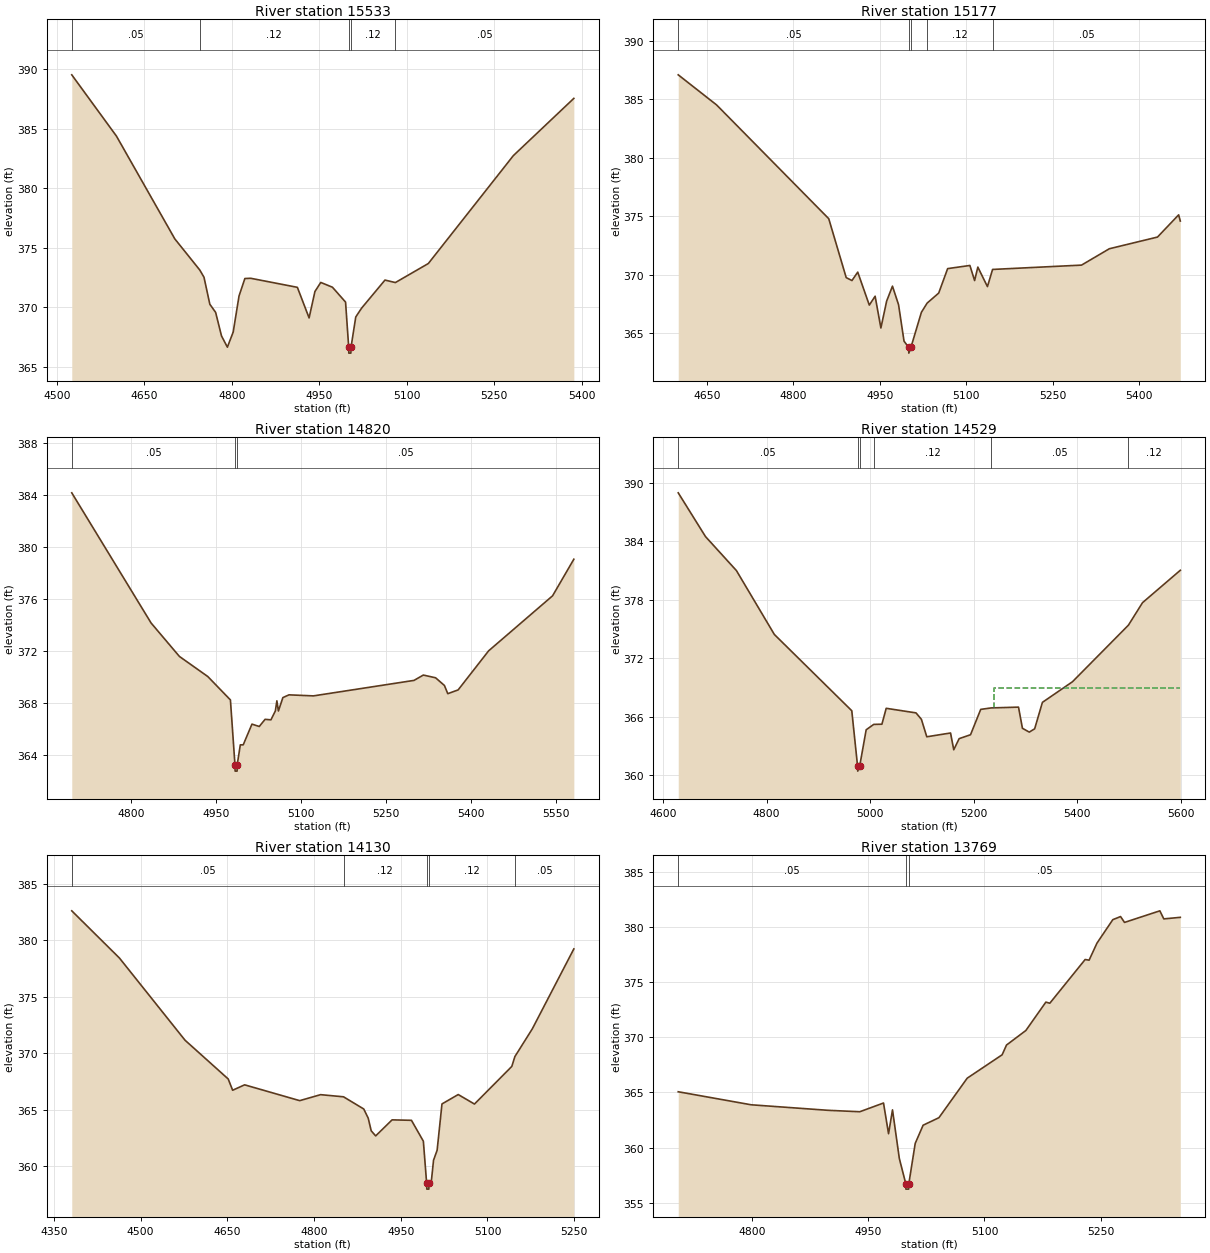
Type RM Length L Ch R = 1 ,15533   ,356,356,356
BEGIN DESCRIPTION:
Walnut3 29.0
END DESCRIPTION:
XS GIS Cut Line= 3
      2748095.55      6760479.37        2747626.        6760461.
      2747235.35      6760474.59
#Sta/Elev= 30
  4525.7  389.54  4602.3  384.39  4702.4  375.75  4745.1  373.14  4752.4  372.53
  4762.4  370.26  4772.4  369.57  4782.4   367.6  4792.5  366.65  4802.5  367.93
  4812.5  370.96  4822.5  372.42  4832.5  372.44  4912.5  371.68  4932.6  369.11
  4942.6  371.33  4952.6  372.09  4972.6  371.69  4995.1  370.44  5000.5  366.65
  5000.7  366.15  5004.2  366.15  5004.5  366.65  5012.6  369.19  5022.6  369.93
  5062.7  372.29  5080.5  372.08    5137  373.68  5282.8  382.75  5386.5  387.56
#Mann= 5 ,-1 , 0
  4525.7     .05       0  4745.1     .12       0  5000.5     .07       0
  5004.5     .12       0  5080.5     .05       0
Bank Sta=5000.5,5004.5
XS Rating Curve= 0 ,0
Exp/Cntr=0.3,0.1

Type RM Length L Ch R = 1 ,15177   ,357,357,357
BEGIN DESCRIPTION:
Walnut3 28.0
END DESCRIPTION:
XS GIS Cut Line= 5
       2748160.8      6760383.68      2747935.51      6760329.06
       2747700.2      6760307.97      2747558.68      6760236.96
      2747316.98       6760195.7
#Sta/Elev= 30
  4600.2  387.09  4666.9  384.51  4861.5  374.78  4891.8  369.74  4901.8  369.49
  4911.8  370.21  4931.9  367.39    4942  368.15    4952  365.43    4962  367.73
  4972.1  369.01  4982.7  367.42  4992.2   364.3  5000.2  363.78  5000.5  363.28
  5004.2  363.78  5022.3  366.77  5032.3  367.56  5052.4  368.42  5067.9  370.51
  5106.5  370.78  5114.7  369.49  5120.3  370.64    5137  368.97  5145.9  370.44
  5300.3  370.81  5348.6  372.21  5432.2  373.21  5468.9  375.11  5471.8  374.58
#Mann= 5 ,-1 , 0
  4600.2     .05       0  5000.2     .04       0  5004.2     .05       0
  5032.3     .12       0  5145.9     .05       0
Bank Sta=5000.2,5004.2
XS Rating Curve= 0 ,0
Exp/Cntr=0.3,0.1

Type RM Length L Ch R = 1 ,14820   ,291,291,291
BEGIN DESCRIPTION:
Walnut3 27.0
END DESCRIPTION:
XS GIS Cut Line= 4
      2748076.01        6760011.        2747776.        6760011.
      2747715.79      6759995.95      2747229.56      6760191.36
#Sta/Elev= 30
  4695.8  384.15  4835.8  374.15  4885.8  371.58  4935.8  370.04  4975.8  368.24
  4983.8  363.27  4984.1  362.77  4987.6  362.77  4987.8  363.27  4993.3  364.79
  4998.4  364.79  5013.8  366.38  5026.7   366.2    5037  366.75  5047.3  366.71
  5055.1  367.39  5057.8  368.17  5060.5  367.39  5068.4  368.42  5079.2  368.63
  5122.3  368.55  5299.8  369.74  5316.3  370.15  5337.9  369.94  5353.5  369.35
  5359.4  368.72  5377.7  369.01  5431.5  372.01  5544.4  376.24  5581.9  379.05
#Mann= 3 ,-1 , 0
  4695.8     .05       0  4983.8     .04       0  4987.8     .05       0
Bank Sta=4983.8,4987.8
XS Rating Curve= 0 ,0
Exp/Cntr=0.3,0.1

Type RM Length L Ch R = 1 ,14529   ,399,399,399
BEGIN DESCRIPTION:
Walnut3 26.0
END DESCRIPTION:
XS GIS Cut Line= 3
      2748175.96      6759910.98      2747785.32      6759710.11
      2747275.96      6759560.99
#Sta/Elev= 30
  4629.3  388.96  4681.9  384.48  4741.7  380.99    4815  374.44  4964.6  366.62
  4975.8  360.93  4976.1  360.43  4979.8  360.93  4992.4  364.67    5007  365.22
  5022.8  365.24  5031.1  366.87  5088.7   366.4  5099.1  365.74  5109.5  363.95
  5155.4  364.34  5161.6  362.62    5172  363.76    5194  364.16  5213.7  366.76
    5234  366.91  5286.7  366.99  5294.3  364.82  5307.5  364.43  5317.9  364.77
  5332.9  367.48  5390.9  369.59    5499  375.39  5526.3   377.7  5599.3  381.02
#Mann= 6 ,-1 , 0
  4629.3     .05       0  4975.8     .04       0  4979.8     .05       0
    5007     .12       0    5234     .05       0    5499     .12       0
#XS Ineff= 2 , 0
       0                    5240       0     369
Permanent Ineff=
       F       F
Bank Sta=4975.8,4979.8
XS Rating Curve= 0 ,0
Exp/Cntr=0.3,0.1

Type RM Length L Ch R = 1 ,14130   ,361,361,361
BEGIN DESCRIPTION:
Walnut3 25.0
END DESCRIPTION:
XS GIS Cut Line= 3
      2748276.04      6759661.01        2747676.        6759511.
        2747476.        6759361.
#Sta/Elev= 30
  4380.9   382.6  4463.4  378.42  4576.8  371.15  4651.5  367.72  4659.2  366.72
  4679.9   367.2  4775.2   365.8  4811.3  366.33    4851  366.14    4886  365.06
  4893.7  364.25  4898.9  363.13  4906.6  362.68    4935   364.1  4968.5  364.06
  4989.1  362.21  4994.8  358.47  4995.1  357.97  4998.6  357.97  4998.8  358.47
  5002.5  358.47  5006.7  360.53  5012.9  361.41  5021.3  365.51  5049.4  366.34
  5077.5   365.5  5142.1  368.83  5147.4   369.7  5177.5  372.15  5249.4  379.23
#Mann= 5 ,-1 , 0
  4380.9     .05       0    4851     .12       0  4994.8     .07       0
  4998.8     .12       0  5147.4     .05       0
Bank Sta=4994.8,4998.8
XS Rating Curve= 0 ,0
Exp/Cntr=0.3,0.1

Type RM Length L Ch R = 1 ,13769   ,394,394,394
BEGIN DESCRIPTION:
Walnut3 24.0
END DESCRIPTION:
XS GIS Cut Line= 3
      2748057.58      6759268.87      2747869.52      6759200.38
      2747430.63       6759111.7
#Sta/Elev= 30
  4704.8  365.05  4798.9  363.87    4898  363.37  4939.1  363.24  4969.7  364.03
  4976.2  361.25  4981.3  363.41  4990.1  359.01  4998.4  356.73  4998.6  356.23
  5002.1  356.23  5002.4  356.73  5010.6  360.37  5020.8  362.02  5041.2   362.7
  5077.7  366.28  5122.8   368.4  5128.4  369.28  5153.4   370.6  5179.2  373.17
  5184.3  373.07  5229.9  377.03    5235  376.97  5245.2  378.52  5265.6  380.64
  5275.6  380.92  5280.7  380.39  5326.3  381.44  5331.4  380.71  5352.7  380.85
#Mann= 3 ,-1 , 0
  4704.8     .05       0  4998.4     .04       0  5002.4     .05       0
Bank Sta=4998.4,5002.4
XS Rating Curve= 0 ,0
Exp/Cntr=0.3,0.1

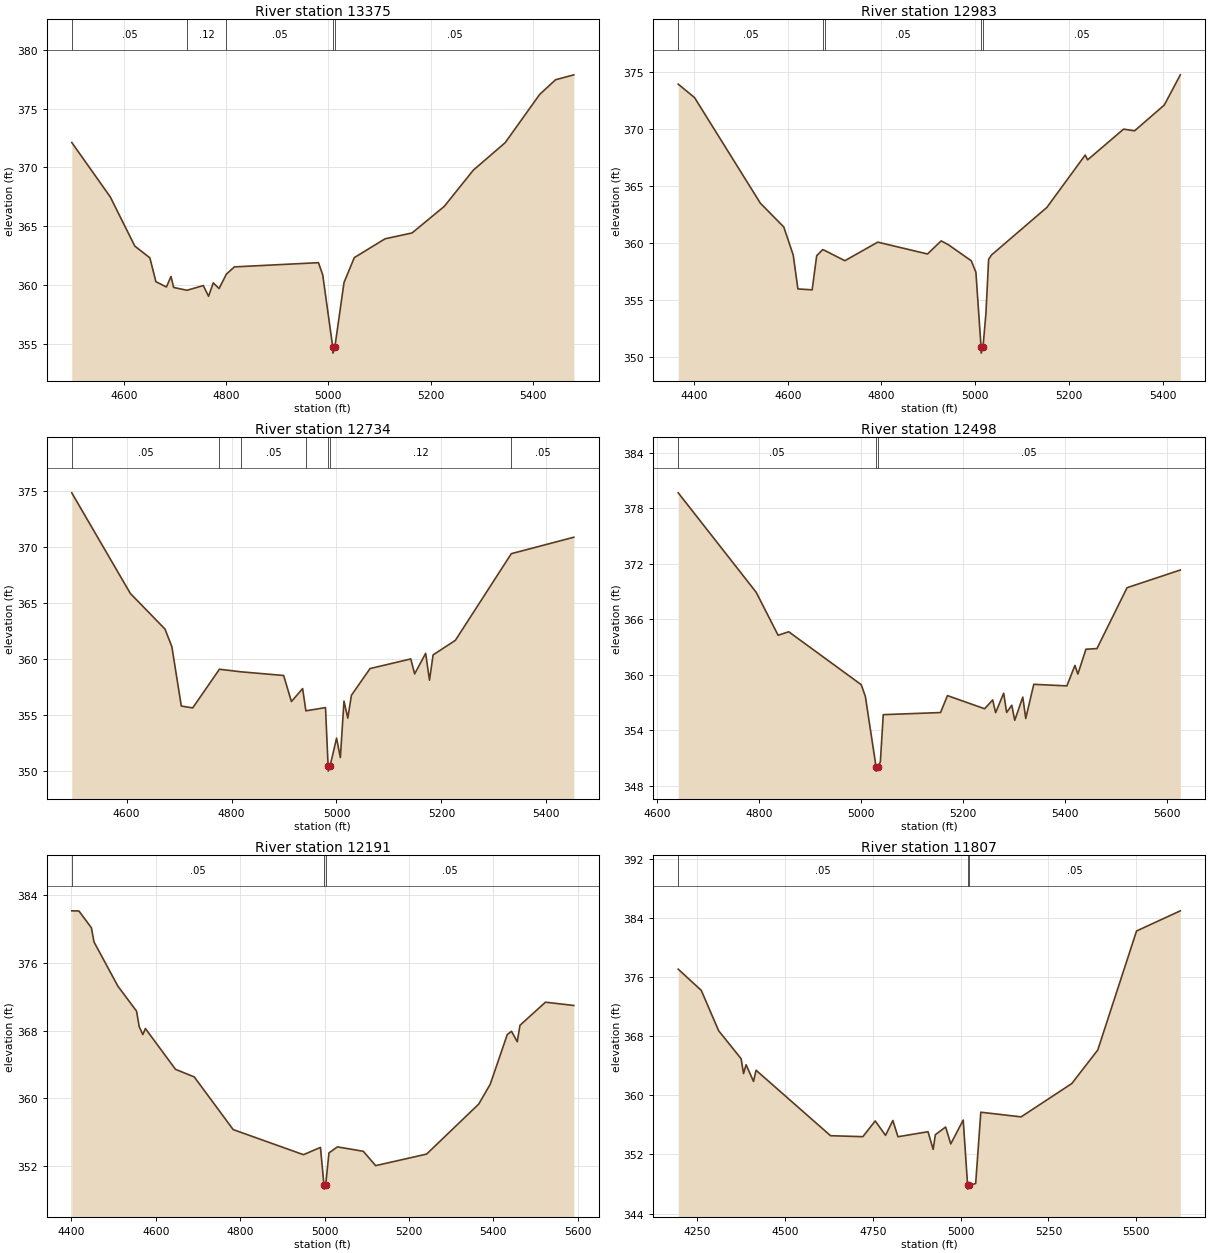
Type RM Length L Ch R = 1 ,13375   ,392,392,392
BEGIN DESCRIPTION:
Walnut3 23.0
END DESCRIPTION:
XS GIS Cut Line= 4
      2748365.72      6758933.78      2747947.49      6758829.73
      2747673.82      6758813.54      2747412.12      6758722.51
#Sta/Elev= 30
  4497.9  372.12  4573.2  367.49  4621.3   363.3  4650.7   362.3  4662.5  360.27
  4683.1  359.82    4692  360.72  4697.2  359.78  4723.3  359.54  4755.2  359.94
  4765.5  359.03  4774.7  360.17  4786.1  359.69  4800.3  360.91    4816  361.53
  4980.5  361.89  4988.8  360.86  5008.5  354.69  5008.8  354.19  5012.5  354.69
  5030.5   360.2  5050.6  362.32  5110.7  363.92  5163.6  364.42  5226.6  366.68
  5283.5  369.77  5345.7   372.1  5413.2  376.21  5444.3  377.46  5480.1  377.88
#Mann= 5 ,-1 , 0
  4497.9     .05       0  4723.3     .12       0  4800.3     .05       0
  5008.5     .04       0  5012.5     .05       0
Bank Sta=5008.5,5012.5
XS Rating Curve= 0 ,0
Exp/Cntr=0.3,0.1

Type RM Length L Ch R = 1 ,12983   ,249,249,249
BEGIN DESCRIPTION:
Walnut3 22.0
END DESCRIPTION:
XS GIS Cut Line= 4
      2748450.77      6758553.57      2747963.51      6758523.05
       2747806.1      6758429.77       2747409.1      6758381.65
#Sta/Elev= 30
  4366.5  373.96  4401.3  372.78  4541.6  363.51  4591.7  361.41  4611.8  358.95
  4621.8  355.97  4652.2  355.89  4661.9  358.89  4674.6  359.42  4679.5  359.34
    4722  358.45  4792.1  360.08  4898.3  359.04  4927.4  360.19    4943  359.85
  4991.7  358.44  5001.5  357.44  5012.6  350.83  5012.8  350.33  5016.6  350.83
  5022.9  353.81  5028.7  358.57  5034.8  358.95  5152.9  363.13  5234.7  367.73
  5239.8  367.31  5316.6  370.01    5340  369.86  5403.5  372.13  5437.6  374.78
#Mann= 5 ,-1 , 0
  4366.5     .05       0  4674.6     .12       0  4679.5     .05       0
  5012.6     .04       0  5016.6     .05       0
Bank Sta=5012.6,5016.6
XS Rating Curve= 0 ,0
Exp/Cntr=0.3,0.1

Type RM Length L Ch R = 1 ,12734   ,236,236,236
BEGIN DESCRIPTION:
Walnut3 21.0
END DESCRIPTION:
XS GIS Cut Line= 4
      2748447.33      6758485.87      2748107.18      6758392.51
      2748040.19      6758296.99      2747687.46      6757960.19
#Sta/Elev= 30
  4495.4  374.86    4607  365.87  4673.1  362.68  4686.2  361.11  4704.2   355.8
  4725.9  355.63  4776.9  359.09  4817.5  358.86  4899.3  358.53  4914.1   356.2
  4935.5  357.36  4941.7  355.37  4979.1  355.66    4984  350.48  4984.3  349.98
    4988  350.48  5000.2  352.93  5007.4  351.19  5014.3  356.24  5021.6  354.72
  5028.5  356.76    5064  359.15  5141.7  360.01    5149  358.67    5170  360.51
  5177.3  358.11  5184.2  360.37  5226.6  361.67  5333.3  369.42  5452.5  370.89
#Mann= 7 ,-1 , 0
  4495.4     .05       0  4776.9     .12       0  4817.5     .05       0
  4941.7     .12       0    4984     .07       0    4988     .12       0
  5333.3     .05       0
Bank Sta=4984,4988
XS Rating Curve= 0 ,0
Exp/Cntr=0.3,0.1

Type RM Length L Ch R = 1 ,12498   ,307,307,307
BEGIN DESCRIPTION:
Walnut3 20.5
END DESCRIPTION:
XS GIS Cut Line= 3
      2748521.86      6758470.86      2748253.47      6758250.83
      2747698.96        6757935.
#Sta/Elev= 30
    4641  379.68    4794  368.93    4837  364.29  4857.8  364.67  5000.1  358.95
  5008.2  357.68  5029.1  350.11  5029.4  349.61  5033.2  350.11  5037.6   350.6
  5043.3  355.71  5155.7  355.94  5169.3  357.77  5242.2  356.35    5258   357.3
  5263.8  355.93  5279.6  358.03  5285.4  355.95  5295.5  356.73  5301.3   355.1
  5317.1  357.61  5322.9   355.3  5338.7  358.99  5403.6  358.82  5419.4  361.03
  5425.2   360.1    5441  362.78  5462.6  362.85  5521.7  369.43  5626.2  371.34
#Mann= 3 ,-1 , 0
    4641     .05       0  5029.1     .05       0  5033.2     .05       0
Bank Sta=5029.1,5033.2
XS Rating Curve= 0 ,0
Exp/Cntr=0.3,0.1

Type RM Length L Ch R = 1 ,12191   ,384,384,384
BEGIN DESCRIPTION:
Walnut3 20.0
END DESCRIPTION:
XS GIS Cut Line= 3
      2748725.14      6758285.62       2748281.4      6757971.58
      2747639.16      6757901.23
#Sta/Elev= 30
    4401  382.12    4418   382.1  4447.5  380.12  4453.7  378.45  4510.3  373.24
  4554.6  370.29  4560.7  368.47  4569.4  367.53  4575.5  368.24  4646.9  363.43
  4691.2  362.54  4783.5  356.33  4950.1  353.37  4990.3  354.23  4998.6  349.81
  4998.9  349.31  5002.7  349.81  5010.4  353.58  5030.5  354.29  5091.8  353.77
  5121.1  352.08  5241.8  353.44  5365.4  359.34  5392.7  361.69  5432.9  367.53
    5443  367.92  5456.6  366.69  5463.1  368.63  5523.5  371.35  5590.7  370.96
#Mann= 3 ,-1 , 0
    4401     .05       0  4998.6     .03       0  5002.7     .05       0
Bank Sta=4998.6,5002.7
XS Rating Curve= 0 ,0
Exp/Cntr=0.3,0.1

Type RM Length L Ch R = 1 ,11807   ,210,210,210
BEGIN DESCRIPTION:
Walnut3 19.3
END DESCRIPTION:
XS GIS Cut Line= 4
      2748766.08      6758203.68      2748387.86      6757798.51
      2747971.92      6757489.16      2747660.55      6757316.43
#Sta/Elev= 30
  4196.6  377.08  4262.2  374.21  4311.6  368.75  4375.6  364.96  4382.4  362.95
  4389.7  364.15  4410.8  361.89  4418.1   363.4  4630.1  354.54  4721.9  354.41
  4757.2  356.54  4786.5  354.59  4807.3   356.6  4821.9   354.4  4907.4  355.08
    4922  352.69  4928.3  354.68  4957.5  355.72  4972.1  353.43  5007.5  356.66
  5020.1  347.81  5020.4  347.31  5024.3  347.81    5043  348.07  5057.6  357.72
  5172.3  357.09  5316.5   361.6  5390.4  366.14  5500.8  382.25  5625.3  384.98
#Mann= 3 ,-1 , 0
  4196.6     .05       0  5020.1     .03       0  5024.3     .05       0
Bank Sta=5020.1,5024.3
XS Rating Curve= 0 ,0
Exp/Cntr=0.3,0.1

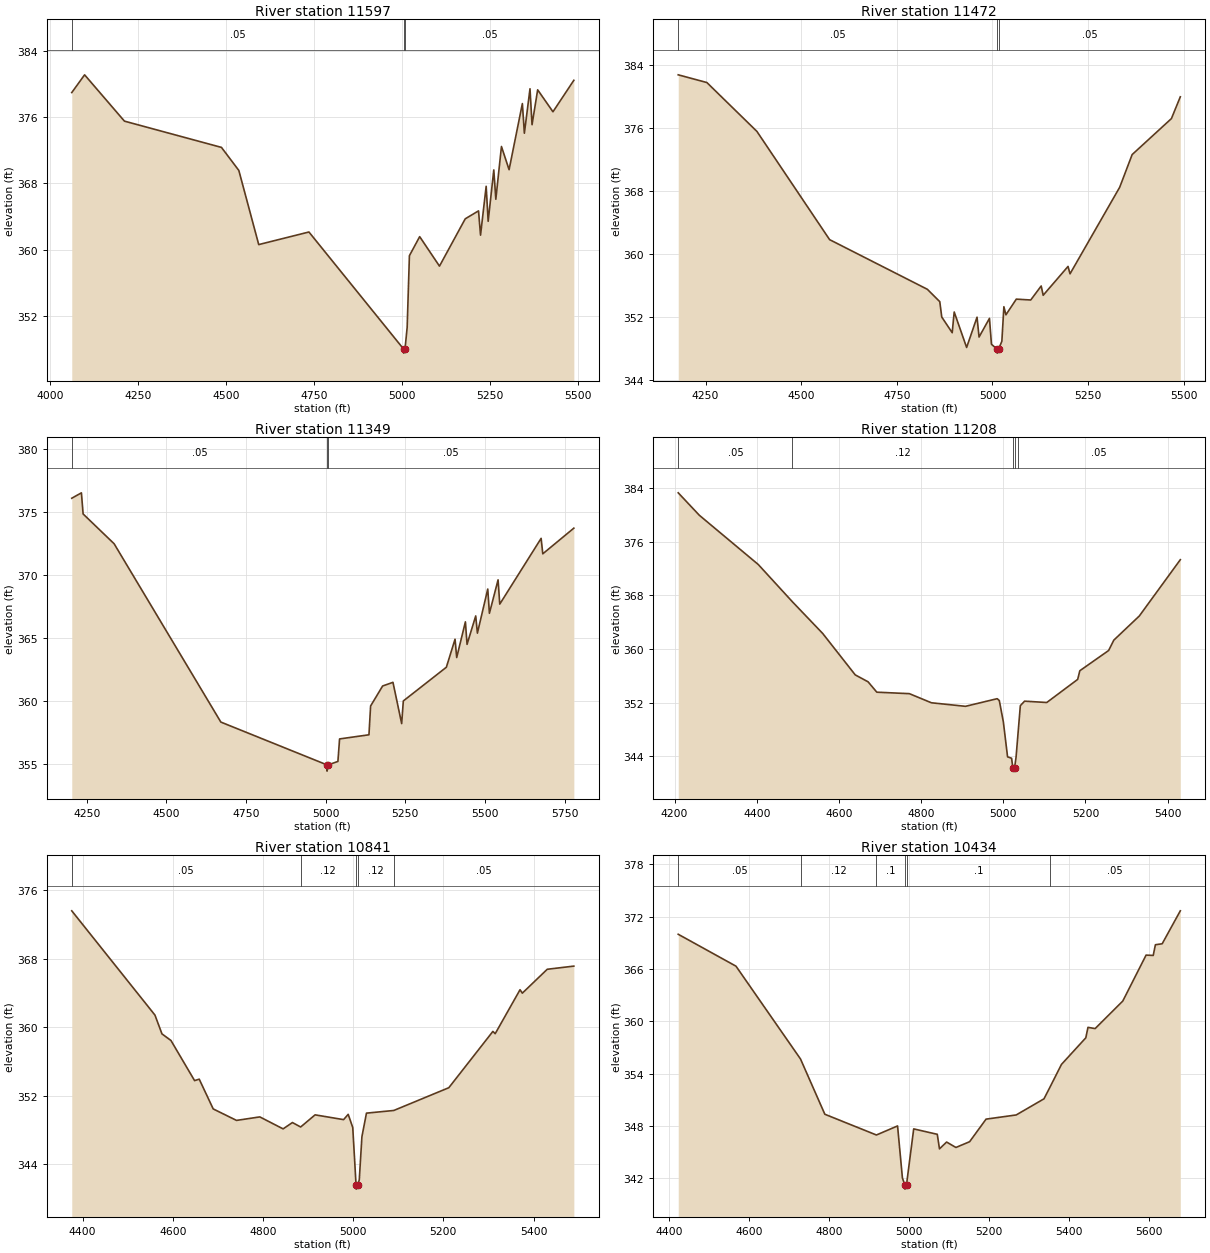
Type RM Length L Ch R = 1 ,11597   ,125,125,125
BEGIN DESCRIPTION:
Walnut3 19.0
END DESCRIPTION:
XS GIS Cut Line= 4
        2748955.       6758103.6      2748576.73      6757698.38
      2748160.79      6757389.04        2747850.      6757216.63
#Sta/Elev= 30
  4060.9  378.97  4097.4  381.11  4210.7  375.52  4486.7  372.35  4536.1  369.57
  4592.7  360.62  4735.5  362.14  5004.6  348.02  5004.9  347.52  5008.8  348.02
  5014.9  350.63  5021.3  359.28  5050.5  361.58  5106.8  358.02  5180.1  363.73
  5217.9  364.69  5223.6  361.76  5239.6  367.66  5245.3  363.43  5261.3  369.63
  5267.1  366.09  5283.1  372.46  5304.8  369.66  5342.6  377.64  5348.3  374.06
  5364.3  379.43  5370.1  375.09  5386.1   379.3  5429.6  376.65    5489  380.45
#Mann= 3 ,-1 , 0
  4060.9     .05       0  5004.6     .05       0  5008.8     .05       0
Bank Sta=5004.6,5008.8
XS Rating Curve= 0 ,0
Exp/Cntr=0.3,0.1

Type RM Length L Ch R = 1 ,11472   ,123,123,123
BEGIN DESCRIPTION:
Walnut3 18.4
END DESCRIPTION:
XS GIS Cut Line= 3
      2749114.25      6757607.49       2748588.6      6757445.93
      2747860.73      6757218.47
#Sta/Elev= 30
  4178.6   382.7  4253.5  381.72  4384.3  375.52  4574.3  361.79  4829.8  355.49
  4862.3  353.92  4867.5  351.97  4894.8  349.98    4900  352.61  4932.5  348.11
  4959.7  351.95    4965  349.43  4992.2   351.8  4997.4  348.52    5012  347.89
  5012.4  347.39  5016.2  347.89  5024.6   348.9  5029.9  353.28  5035.2  352.25
  5062.4  354.24  5100.1  354.13  5127.4  355.91  5132.6  354.73  5197.6  358.39
  5202.8  357.45  5332.7  368.44  5365.2  372.58  5467.9  377.15  5491.1  379.91
#Mann= 3 ,-1 , 0
  4178.6     .05       0    5012     .05       0  5016.2     .05       0
Bank Sta=5012,5016.2
XS Rating Curve= 0 ,0
Exp/Cntr=0.3,0.1

Type RM Length L Ch R = 1 ,11349   ,141,141,141
BEGIN DESCRIPTION:
Walnut3 18.2
END DESCRIPTION:
XS GIS Cut Line= 3
        2749137.      6757495.99      2748358.77      6757252.51
      2747632.43      6757025.53
#Sta/Elev= 30
  4202.6  376.11  4232.9  376.54  4238.2  374.86  4335.6  372.49  4670.7  358.31
  5003.6  354.91    5004  354.41  5007.9  354.91  5038.2  355.18  5043.5  356.97
  5135.7   357.3  5140.9  359.59  5178.6  361.18  5211.1  361.47  5238.4  358.19
  5243.6  359.99  5378.7  362.67    5406   364.9  5411.2  363.44  5438.5  366.28
  5443.7  364.49  5470.9  366.75  5476.2  365.38  5508.7  368.89  5513.9  366.96
  5541.1  369.62  5546.4  367.69  5676.3  372.92  5681.5  371.69    5779  373.73
#Mann= 3 ,-1 , 0
  4202.6     .05       0  5003.6     .05       0  5007.9     .05       0
Bank Sta=5003.6,5007.9
XS Rating Curve= 0 ,0
Exp/Cntr=0.3,0.1

Type RM Length L Ch R = 1 ,11208   ,367,367,367
BEGIN DESCRIPTION:
Walnut3 18.0
END DESCRIPTION:
XS GIS Cut Line= 3
      2749195.57      6757316.83      2748480.25      6757146.68
      2748009.54      6757022.08
#Sta/Elev= 30
  4208.9  383.32  4260.3  379.97  4403.8  372.62    4487  367.05  4560.6  362.33
  4639.8  356.15    4671  355.12  4692.3  353.57  4771.5  353.35  4825.2  351.99
  4908.2  351.46  4985.3   352.6  4990.5  352.32  5000.3  349.15  5010.6  343.92
  5020.4  343.71  5023.4  342.29  5023.8  341.79  5027.7  342.29  5031.3  343.89
  5036.5  347.73  5041.7  351.56    5052  352.23    5106  352.03  5181.3  355.48
  5186.5  356.77  5256.6  359.79  5269.3  361.34  5331.3  364.94  5431.1  373.34
#Mann= 5 ,-1 , 0
  4208.9     .05       0    4487     .12       0  5023.4     .07       0
  5027.7     .12       0  5036.5     .05       0
Bank Sta=5023.4,5027.7
XS Rating Curve= 0 ,0
Exp/Cntr=0.3,0.1

Type RM Length L Ch R = 1 ,10841   ,407,407,407
BEGIN DESCRIPTION:
Walnut3 17.0
END DESCRIPTION:
XS GIS Cut Line= 3
      2749129.59      6756952.24      2748553.17      6756802.93
      2748042.74      6756716.12
#Sta/Elev= 30
  4376.1  373.61  4560.5  361.43  4576.1  359.23    4596  358.46  4648.4  353.77
  4658.7  353.94  4689.7  350.46  4741.4  349.12    4793  349.53  4844.7  348.13
  4865.3  348.87  4883.6  348.35  4915.6  349.77  4978.8  349.21    4989  349.83
  4999.1  348.29  5006.4  341.59  5006.7  341.09  5010.7  341.59  5013.6   342.2
  5019.4  347.21  5029.5  349.97  5090.1  350.28  5212.1  352.94  5309.8  359.52
  5314.9  359.25    5370  364.39  5375.1  363.99  5430.3  366.78  5489.3  367.15
#Mann= 5 ,-1 , 0
  4376.1     .05       0  4883.6     .12       0  5006.4     .07       0
  5010.7     .12       0  5090.1     .05       0
Bank Sta=5006.4,5010.7
XS Rating Curve= 0 ,0
Exp/Cntr=0.3,0.1

Type RM Length L Ch R = 1 ,10434   ,501,501,501
BEGIN DESCRIPTION:
Walnut3 16.0
END DESCRIPTION:
XS GIS Cut Line= 3
      2749198.99      6756500.84      2748584.42      6756417.51
      2748004.59      6756160.58
#Sta/Elev= 30
  4423.2  369.98  4567.5  366.32  4728.7  355.67  4789.5  349.33  4918.4  346.95
  4971.2  347.99  4983.3  342.02  4989.2  341.24  4989.5  340.74  4993.5  341.24
  5011.5  347.65  5070.4  347.03  5075.9  345.36  5093.7  346.14    5117  345.52
  5151.2  346.18  5192.3  348.77  5267.6  349.25    5337   351.1  5352.2  352.46
  5380.7  355.05  5441.5   358.1  5446.9   359.3  5464.8  359.16  5533.9  362.32
  5592.1  367.59  5609.9  367.55  5615.4  368.78  5632.3  368.89  5677.6  372.67
#Mann= 6 ,-1 , 0
  4423.2     .05       0  4728.7     .12       0  4918.4      .1       0
  4989.2     .07       0  4993.5      .1       0  5352.2     .05       0
Bank Sta=4989.2,4993.5
XS Rating Curve= 0 ,0
Exp/Cntr=0.3,0.1

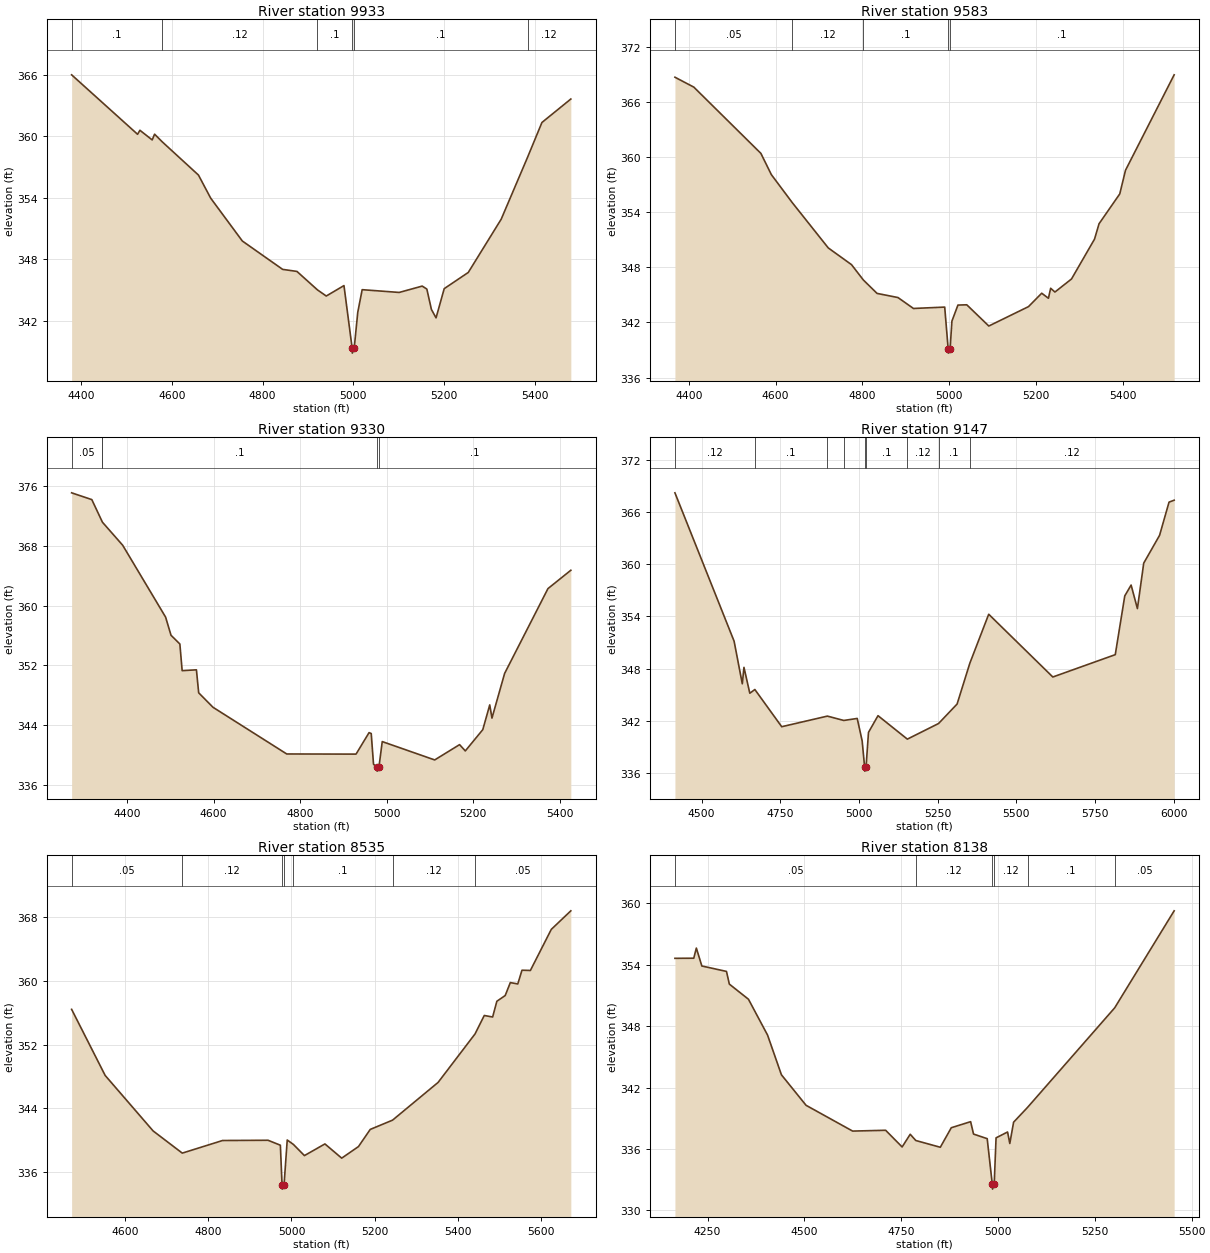
Type RM Length L Ch R = 1 ,9933    ,350,350,350
BEGIN DESCRIPTION:
Walnut3 15.0
END DESCRIPTION:
XS GIS Cut Line= 3
      2749369.13      6756150.15      2748834.42      6755980.01
      2748303.16      6755889.73
#Sta/Elev= 30
  4379.4     366  4524.7   360.2  4529.9  360.59  4556.9  359.65  4562.2  360.21
  4578.9  359.47  4658.9  356.22  4685.8  353.97  4755.5  349.79  4844.4  347.02
  4875.9  346.82  4921.1  345.02  4940.5  344.42  4979.5  345.44  4997.5  339.35
  4997.9  338.85  5002.1  339.35  5009.9  342.83  5019.6  345.04  5101.2  344.77
  5151.9  345.39  5162.1   345.1  5172.2  343.11  5182.4  342.29  5200.4  345.14
  5253.4  346.72    5326  351.92    5384  357.95  5415.7  361.35  5479.4  363.64
#Mann= 6 ,-1 , 0
  4379.4      .1       0  4578.9     .12       0  4921.1      .1       0
  4997.5     .07       0  5002.1      .1       0    5384     .12       0
Bank Sta=4997.5,5002.1
XS Rating Curve= 0 ,0
Exp/Cntr=0.3,0.1

Type RM Length L Ch R = 1 ,9583    ,253,253,253
BEGIN DESCRIPTION:
Walnut3 14.0
END DESCRIPTION:
XS GIS Cut Line= 3
      2749466.41      6755889.75      2748952.48       6755681.4
      2748365.63      6755573.75
#Sta/Elev= 30
  4367.8  368.69  4411.4  367.61    4566   360.4  4590.1  358.09  4638.7  355.02
  4721.4  350.11    4775  348.29  4802.3  346.62  4833.9  345.16  4882.1  344.71
  4917.8  343.52  4989.9  343.67  4997.8  339.16  4998.3  338.66  5002.4  339.16
  5006.5  342.14  5020.4  343.89  5040.8  343.92  5091.6  341.61  5183.1  343.72
  5213.6  345.18  5229.1  344.63  5234.2  345.72  5244.1  345.31  5282.3  346.73
  5335.4  351.07  5345.8  352.74  5393.6  355.99  5406.8  358.56    5519  368.95
#Mann= 5 ,-1 , 0
  4367.8     .05       0  4638.7     .12       0  4802.3      .1       0
  4997.8     .07       0  5002.4      .1       0
Bank Sta=4997.8,5002.4
XS Rating Curve= 0 ,0
Exp/Cntr=0.3,0.1

Type RM Length L Ch R = 1 ,9330    ,183,183,183
BEGIN DESCRIPTION:
Walnut3 14.3
END DESCRIPTION:
XS GIS Cut Line= 3
      2749626.13      6755629.33      2749001.09      6755441.82
      2748504.57       6755368.9
#Sta/Elev= 30
  4271.7  375.14  4318.4  374.23  4342.8  371.22    4343   371.2  4389.8  368.11
    4489  358.48  4501.5  356.05    4522  354.87  4527.3   351.3  4560.3  351.41
  4565.5  348.33  4598.6  346.39  4769.1  340.13  4929.4  340.11  4959.5  342.99
  4964.5  342.87  4969.8  338.76  4977.6  338.33  4978.1  337.83  4982.3  338.33
    4990  341.79  5111.3  339.33  5168.8  341.38  5182.1  340.54  5222.5  343.39
  5238.6  346.71  5243.7  344.94    5273  350.93  5373.2   362.3  5426.1  364.76
#Mann= 5 ,-1 , 0
  4271.7     .05       0  4342.8     .12       0    4343      .1       0
  4977.6     .07       0  4982.3      .1       0
Bank Sta=4977.6,4982.3
XS Rating Curve= 0 ,0
Exp/Cntr=0.3,0.1

Type RM Length L Ch R = 1 ,9147    ,612,612,612
BEGIN DESCRIPTION:
Walnut3 13.0
END DESCRIPTION:
XS GIS Cut Line= 3
      2749580.94      6755466.12      2749063.59      6755289.04
      2748029.89      6755188.45
#Sta/Elev= 30
  4415.5  368.22  4603.4  351.15  4629.4  346.25  4634.7  348.14  4653.3  345.16
  4669.3  345.59  4754.6  341.31  4899.7  342.53  4951.7  342.03  4994.4  342.26
  5010.1  339.67  5017.8   336.7  5018.3   336.2  5022.5   336.7  5030.2  340.66
  5060.4  342.58  5153.6  339.88  5252.8  341.68  5311.6  343.92    5352  348.61
    5412  354.25  5615.6  347.03  5813.9   349.6  5844.1  356.36  5864.2  357.61
  5884.2   354.9  5904.3  360.13  5954.6  363.33  5984.7  367.15  6000.9  367.37
#Mann= 9 ,-1 , 0
  4415.5     .12       0  4669.3      .1       0  4899.7     .12       0
  4951.7      .1       0  5017.8     .07       0  5022.5      .1       0
  5153.6     .12       0  5252.8      .1       0    5352     .12       0
Bank Sta=5017.8,5022.5
XS Rating Curve= 0 ,0
Exp/Cntr=0.3,0.1

Type RM Length L Ch R = 1 ,8535    ,397,397,397
BEGIN DESCRIPTION:
Walnut3 12.0
END DESCRIPTION:
XS GIS Cut Line= 3
      2749576.04      6755061.02      2749152.35      6754792.51
      2748459.48      6754708.07
#Sta/Elev= 30
  4471.7  356.41  4552.3  348.13  4667.5  341.18  4737.6   338.4  4834.4  339.98
  4943.7  340.01  4973.3  339.39  4977.4  334.39  4977.9  333.89  4982.1  334.39
  4989.8  340.04  5004.6  339.49  5031.1  338.09  5080.4  339.55  5120.7  337.77
    5161  339.22  5189.3  341.37  5242.9  342.53  5352.4  347.26  5441.1  353.33
  5463.3  355.64  5483.4  355.45  5493.5  357.42  5513.6  358.14  5525.9  359.76
  5543.8  359.59  5553.9  361.31  5574.1  361.28  5624.4  366.43  5671.3  368.75
#Mann= 7 ,-1 , 0
  4471.7     .05       0  4737.6     .12       0  4977.4     .07       0
  4982.1     .12       0  5004.6      .1       0  5242.9     .12       0
  5441.1     .05       0
Bank Sta=4977.4,4982.1
XS Rating Curve= 0 ,0
Exp/Cntr=0.3,0.1

Type RM Length L Ch R = 1 ,8138    ,241,241,241
BEGIN DESCRIPTION:
Walnut3 11.0
END DESCRIPTION:
XS GIS Cut Line= 3
      2749757.81      6755007.35      2749260.85      6754456.14
      2748791.01      6754175.96
#Sta/Elev= 30
  4165.6  354.63  4214.2  354.64  4220.9  355.63  4235.1  353.88  4298.7  353.35
  4306.1  352.11  4355.5  350.63  4404.8  347.13  4440.6  343.25  4504.2  340.27
  4624.5  337.75  4709.7  337.83  4752.3   336.2  4773.2  337.44  4787.6  336.83
  4850.9  336.17  4879.3  338.08  4929.2  338.67  4936.7  337.46    4972  337.01
  4985.1  332.58  4985.8  332.08  4990.1  332.58  4994.9  337.09  5024.6  337.66
  5030.4  336.54  5040.2  338.62  5076.1  340.06  5301.2  349.79  5454.8  359.27
#Mann= 6 ,-1 , 0
  4165.6     .05       0  4787.6     .12       0  4985.1     .07       0
  4990.1     .12       0  5076.1      .1       0  5301.2     .05       0
Bank Sta=4985.1,4990.1
XS Rating Curve= 0 ,0
Exp/Cntr=0.3,0.1