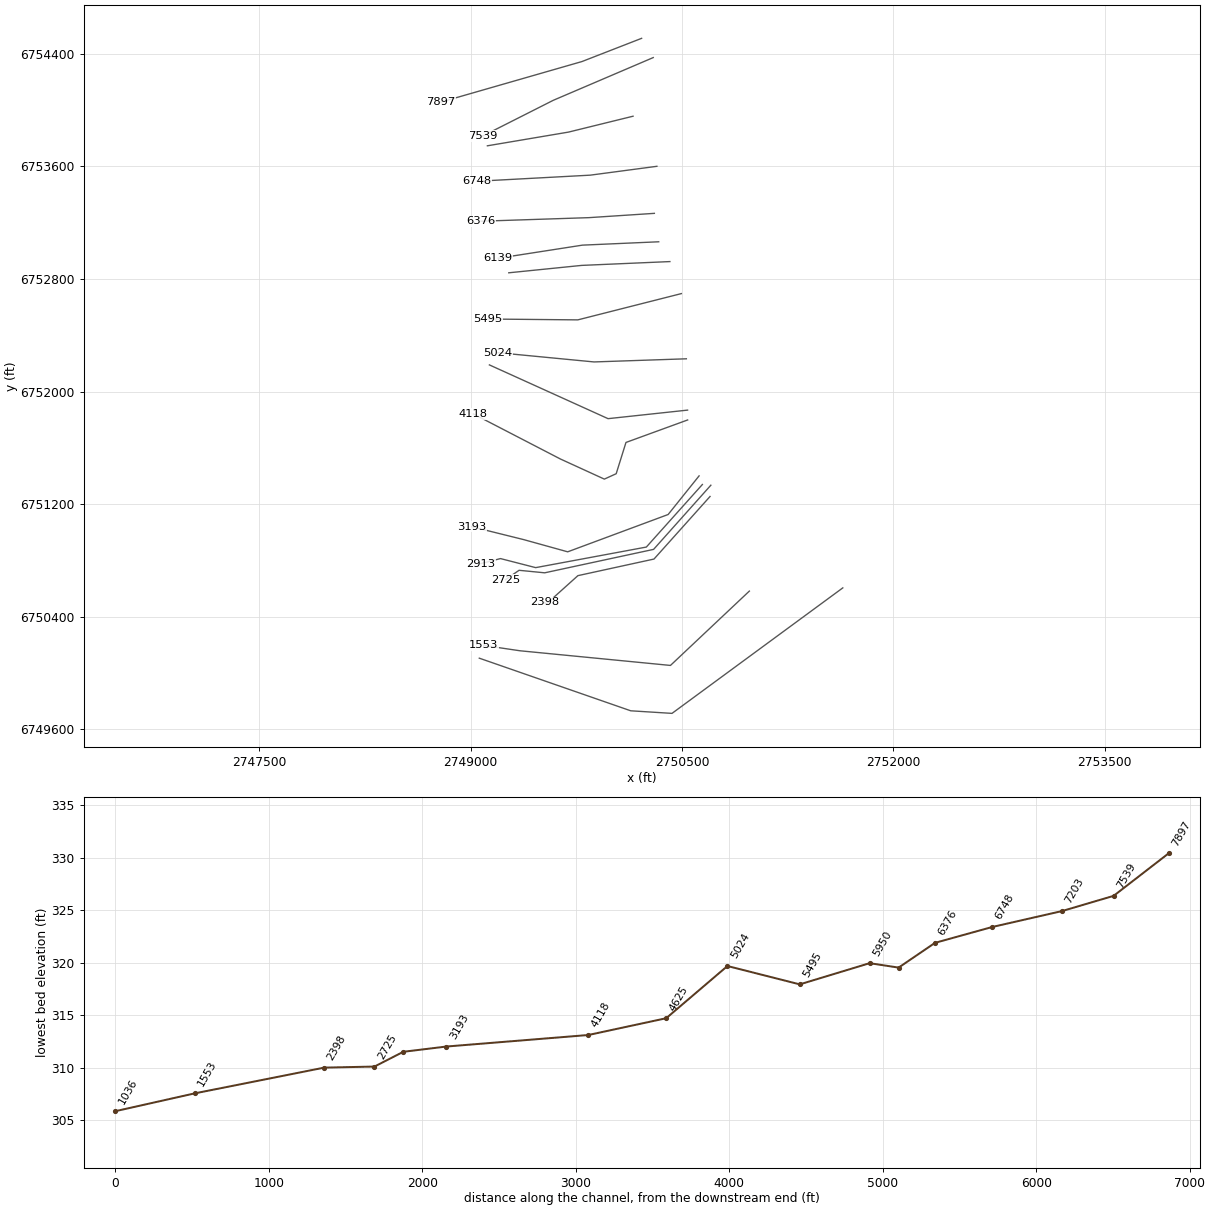
HEC-RAS study Walnut3.prj: Walnut3 Base Level Engineering

--- Walnut3.g01 (geometry) --- (continued)

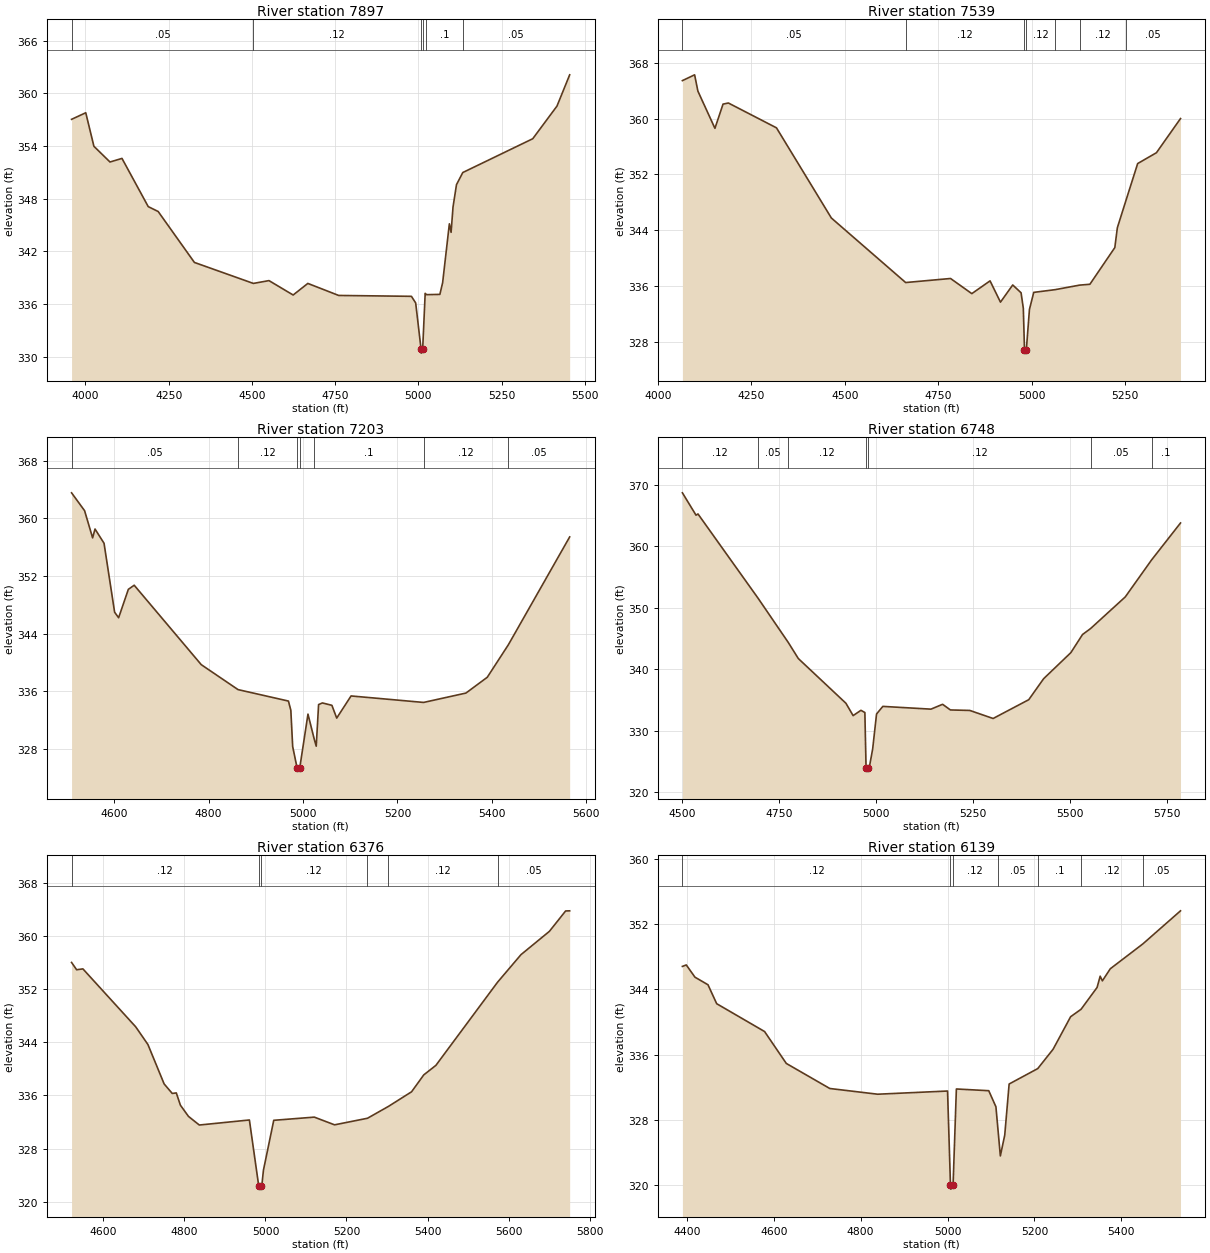
Type RM Length L Ch R = 1 ,7897    ,358,358,358
BEGIN DESCRIPTION:
Walnut3 10.4
END DESCRIPTION:
XS GIS Cut Line= 3
      2750213.53      6754510.39      2749790.37      6754345.46
      2748789.39       6754057.3
#Sta/Elev= 30
  3958.5  357.05  4001.1   357.8  4025.6  353.98  4073.9  352.19  4109.9   352.6
  4188.7  347.11  4218.6  346.55  4327.4  340.75  4504.4  338.36  4551.3  338.68
  4623.9  337.04    4668  338.36  4760.6  336.99  4979.1  336.89  4991.9  336.13
  5007.9  330.92  5008.5  330.42  5012.9  330.92  5020.4  337.23  5024.3  337.08
  5064.5  337.11  5072.8  338.44    5093  345.15  5098.2  344.18    5104  347.06
  5114.4  349.61  5133.3  350.99  5343.4  354.84  5416.2  358.56  5454.3  362.12
#Mann= 6 ,-1 , 0
  3958.5     .05       0  4504.4     .12       0  5007.9     .07       0
  5012.9     .12       0  5024.3      .1       0  5133.3     .05       0
Bank Sta=5007.9,5012.9
XS Rating Curve= 0 ,0
Exp/Cntr=0.3,0.1

Type RM Length L Ch R = 1 ,7539    ,336,336,336
BEGIN DESCRIPTION:
Walnut3 10.0
END DESCRIPTION:
XS GIS Cut Line= 3
      2750296.04      6754373.69      2749586.37      6754069.86
      2749085.16        6753816.
#Sta/Elev= 30
    4065  365.44  4097.7  366.27  4106.5  363.93  4152.1   358.6  4173.8  362.07
  4188.1  362.23  4316.9  358.67  4463.9  345.74  4662.8  336.49    4783  337.07
    4840   334.9  4888.8  336.73  4916.7  333.68  4949.5  336.14  4971.9  335.02
  4977.9  332.79    4981  326.87  4981.6  326.37    4986  326.87  4994.3  332.64
  5005.8  335.08  5063.2  335.47  5128.5  336.12  5156.1  336.24  5222.9   341.5
  5229.7  344.35  5251.9  348.12  5284.1  353.55  5334.3   355.1  5398.8     360
#Mann= 7 ,-1 , 0
    4065     .05       0  4662.8     .12       0    4981     .07       0
    4986     .12       0  5063.2      .1       0  5128.5     .12       0
  5251.9     .05       0
Bank Sta=4981,4986
XS Rating Curve= 0 ,0
Exp/Cntr=0.3,0.1

Type RM Length L Ch R = 1 ,7203    ,455,455,455
BEGIN DESCRIPTION:
Walnut3 9.0
END DESCRIPTION:
XS GIS Cut Line= 3
      2750152.82      6753957.02      2749694.88      6753844.16
       2749119.3      6753746.79
#Sta/Elev= 30
  4509.6  363.53  4537.2  361.05  4554.2  357.28  4559.3  358.51  4578.4  356.53
  4600.8  346.97  4609.3   346.2  4629.9  350.14  4642.3  350.71  4784.4  339.69
  4862.3  336.23  4969.1  334.64  4974.2  333.36  4978.1  328.33  4987.3  325.42
  4988.2  324.92  4993.2  325.42  5010.5  332.83  5024.2  329.25    5028  328.38
    5033  334.15    5041  334.38  5061.2  334.05  5071.4  332.28  5101.8  335.35
  5255.5  334.45  5345.2  335.75  5390.4  337.94  5435.1  342.45    5565  357.41
#Mann= 7 ,-1 , 0
  4509.6     .05       0  4862.3     .12       0  4987.3     .07       0
  4993.2     .12       0  5024.2      .1       0  5255.5     .12       0
  5435.1     .05       0
Bank Sta=4987.3,4993.2
XS Rating Curve= 0 ,0
Exp/Cntr=0.3,0.1

Type RM Length L Ch R = 1 ,6748    ,372,372,372
BEGIN DESCRIPTION:
Walnut3 8.0
END DESCRIPTION:
XS GIS Cut Line= 3
       2750322.1      6753601.11      2749848.96      6753538.17
      2749043.83      6753494.77
#Sta/Elev= 30
  4500.2  368.71  4535.3  365.07  4540.3  365.27  4695.3  351.54  4772.8  344.37
  4798.9  341.73  4921.6  334.45  4940.1  332.44  4960.3   333.3  4970.4  332.94
  4973.5   323.9  4974.5   323.4  4979.5   323.9  4981.5   323.9  4990.5  327.01
  5000.5   332.7  5016.7  333.94  5140.7  333.49  5170.7  334.28  5190.8  333.36
  5240.8  333.28  5300.9  331.97  5392.7  335.03  5431.1  338.45  5501.2  342.69
  5531.3  345.64  5552.2  346.62  5641.4  351.76  5709.2  357.78  5783.8   363.8
#Mann= 7 ,-1 , 0
  4500.2     .12       0  4695.3     .05       0  4772.8     .12       0
  4973.5     .07       0  4979.5     .12       0  5552.2     .05       0
  5709.2      .1       0
Bank Sta=4973.5,4979.5
XS Rating Curve= 0 ,0
Exp/Cntr=0.3,0.1

Type RM Length L Ch R = 1 ,6376    ,237,237,237
BEGIN DESCRIPTION:
Walnut3 7.0
END DESCRIPTION:
XS GIS Cut Line= 3
      2750303.99      6753266.78       2749839.2      6753236.25
        2749076.        6753211.
#Sta/Elev= 30
  4521.5  356.05    4534  354.95  4549.5  355.08  4679.8  346.35  4709.9  343.69
    4750  337.74    4770  336.31    4780  336.39  4790.1  334.54  4810.1  332.85
  4836.8  331.55  4960.4  332.31  4983.4  322.39  4984.4  321.89  4989.4  322.39
    4991  322.39  4995.1  324.75  5020.5  332.26  5120.6  332.74  5170.6  331.58
  5251.9  332.57  5303.7  334.36  5360.7  336.56  5390.7   339.1  5420.7  340.54
    5573  353.08  5630.8  357.23  5700.9  360.74  5740.9  363.81  5750.9  363.83
#Mann= 6 ,-1 , 0
  4521.5     .12       0  4983.4     .07       0  4989.4     .12       0
  5251.9     .05       0  5303.7     .12       0    5573     .05       0
Bank Sta=4983.4,4989.4
XS Rating Curve= 0 ,0
Exp/Cntr=0.3,0.1

Type RM Length L Ch R = 1 ,6139    ,189,189,189
BEGIN DESCRIPTION:
Walnut3 6.5
END DESCRIPTION:
XS GIS Cut Line= 3
      2750334.87      6753064.75      2749793.74      6753040.92
       2749196.3      6752947.87
#Sta/Elev= 30
  4389.9  346.82  4398.8     347  4418.8   345.5  4448.8  344.57  4468.8  342.25
    4579  338.84    4629  334.93  4729.1  331.86  4839.2  331.16  5000.1  331.55
  5006.8  320.03  5007.8  319.53  5012.8  320.03  5020.4   331.8  5094.9  331.59
  5111.4  329.62  5115.1  327.44  5121.6   323.6  5131.7  326.15  5141.8  332.41
  5207.7   334.3    5243  336.67  5283.4  340.66  5307.4  341.57  5344.2  344.24
  5351.3  345.62  5356.4  345.05  5374.6  346.53  5449.6  349.58  5536.2  353.63
#Mann= 7 ,-1 , 0
  4389.9     .12       0  5006.8     .07       0  5012.8     .12       0
  5115.1     .05       0  5207.7      .1       0  5307.4     .12       0
  5449.6     .05       0
Bank Sta=5006.8,5012.8
XS Rating Curve= 0 ,0
Exp/Cntr=0.3,0.1

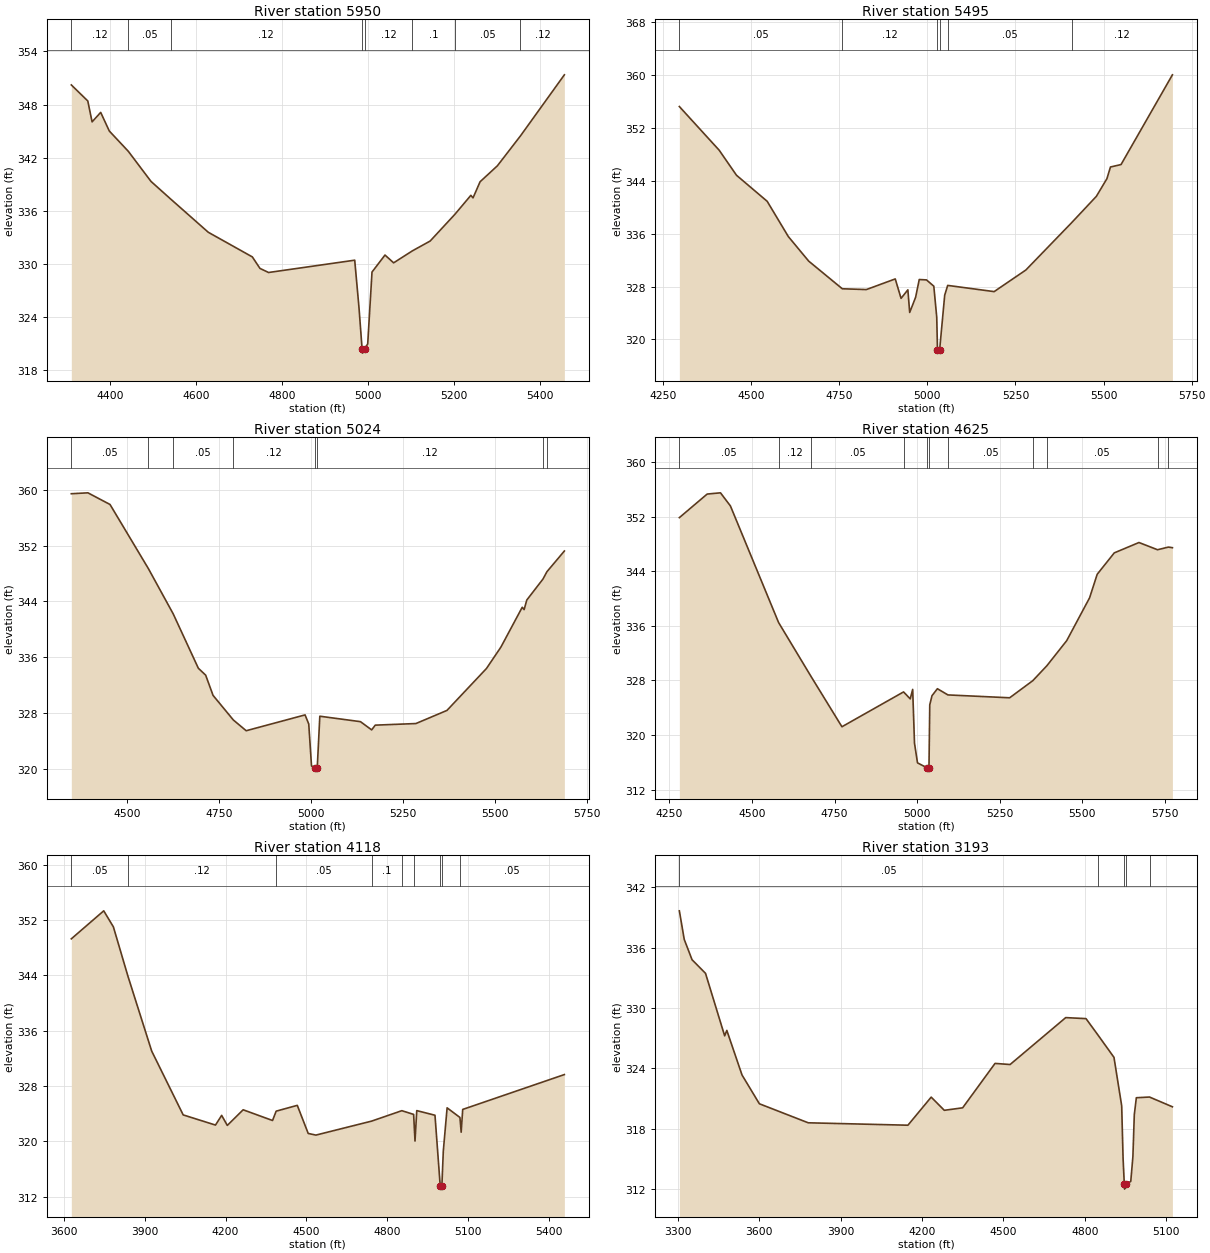
Type RM Length L Ch R = 1 ,5950    ,455,455,455
BEGIN DESCRIPTION:
Walnut3 6.0
END DESCRIPTION:
XS GIS Cut Line= 3
      2750414.24      6752924.11      2749788.31      6752896.97
        2749271.      6752844.39
#Sta/Elev= 30
  4310.5  350.22  4348.8  348.41  4358.8  346.05  4378.8  347.12  4398.8  345.02
    4443  342.73  4495.8  339.33  4541.3  337.35    4629  333.59  4731.4  330.81
  4749.2  329.51  4769.2  329.05  4969.5  330.44  4979.5  325.05  4986.6  320.45
  4987.6  319.95  4992.7  320.45  4999.7  320.99  5009.7   329.1  5039.9  331.02
    5060  330.14  5103.5  331.49  5144.9   332.6  5202.7  335.63  5239.6  337.76
  5244.6  337.47    5261  339.29  5301.2  341.09  5354.8  344.46    5457  351.36
#Mann= 8 ,-1 , 0
  4310.5     .12       0    4443     .05       0  4541.3     .12       0
  4986.6     .07       0  4992.7     .12       0  5103.5      .1       0
  5202.7     .05       0  5354.8     .12       0
Bank Sta=4986.6,4992.7
XS Rating Curve= 0 ,0
Exp/Cntr=0.3,0.1

Type RM Length L Ch R = 1 ,5495    ,471,471,471
BEGIN DESCRIPTION:
Walnut3 5.0
END DESCRIPTION:
XS GIS Cut Line= 3
      2750495.53      6752696.58      2749760.89      6752509.91
       2749120.3      6752515.92
#Sta/Elev= 30
  4296.8  355.25  4409.8  348.64  4458.9  344.85  4545.9  340.91  4605.8  335.58
  4663.6  331.86    4759  327.67  4827.3  327.55  4909.2  329.16  4925.7  326.22
    4945  327.51  4950.2  324.09    4967  326.39  4977.3  329.07  4997.9  329.01
  5018.6  328.06  5026.9  323.37    5029  318.43    5030  317.93  5035.1  318.43
  5049.5  326.71    5058  328.18  5189.7  327.24  5279.7  330.51  5410.6  337.73
  5479.7  341.66  5509.7  344.34  5519.7   346.1  5549.7  346.47  5695.4  360.05
#Mann= 6 ,-1 , 0
  4296.8     .05       0    4759     .12       0    5029     .07       0
  5035.1     .12       0    5058     .05       0  5410.6     .12       0
Bank Sta=5029,5035.1
XS Rating Curve= 0 ,0
Exp/Cntr=0.3,0.1

Type RM Length L Ch R = 1 ,5024    ,399,399,399
BEGIN DESCRIPTION:
Walnut3 4.0
END DESCRIPTION:
XS GIS Cut Line= 3
       2750531.1      6752233.31        2749876.        6752211.
      2749194.24      6752276.71
#Sta/Elev= 30
  4348.7  359.44  4393.8  359.57  4453.9   357.9  4558.3   348.7  4625.7  342.22
    4694  334.43    4714  333.43    4734  330.54  4789.2  327.01  4824.1  325.47
  4984.2  327.74  4994.2  326.43  5001.7  320.42  5011.1  320.18  5012.2  319.68
  5017.3  320.18  5024.3  327.55  5134.8  326.77  5165.2  325.59    5175  326.27
  5285.5   326.5  5369.9  328.38  5477.3  334.39  5516.5  337.45  5574.6  343.17
  5579.7  342.83  5586.9   344.2  5630.8   347.2  5641.8  348.27  5689.1  351.23
#Mann= 8 ,-1 , 0
  4348.7     .05       0  4558.3     .12       0  4625.7     .05       0
  4789.2     .12       0  5011.1     .07       0  5017.3     .12       0
  5630.8      .1       0  5641.8     .12       0
Bank Sta=5011.1,5017.3
XS Rating Curve= 0 ,0
Exp/Cntr=0.3,0.1

Type RM Length L Ch R = 1 ,4625    ,507,507,507
BEGIN DESCRIPTION:
Walnut3 3.0
END DESCRIPTION:
XS GIS Cut Line= 3
      2750539.75      6751868.72       2749975.5      6751807.96
      2749133.49       6752189.9
#Sta/Elev= 30
  4280.2  351.89  4364.4  355.35  4404.7  355.53  4434.8   353.6  4580.5   336.5
  4679.7  328.51  4772.2  321.21  4958.7  326.32  4978.9   325.3  4986.3  326.69
  4991.8   318.8  5000.9  315.91  5029.4   315.2  5030.4   314.7  5035.6   315.2
    5038  324.43  5044.8  325.77  5061.1  326.79    5093  325.88  5279.8  325.46
  5349.8  327.97  5392.2  330.15  5452.4  333.84  5521.6  340.12  5544.7  343.58
  5596.4  346.72  5671.1  348.24  5727.3  347.18  5760.2  347.57  5772.3  347.48
#Mann= 11 ,-1 , 0
  4280.2     .05       0  4580.5     .12       0  4679.7     .05       0
  4958.7     .12       0  5029.4     .07       0  5035.6     .12       0
    5093     .05       0  5349.8     .12       0  5392.2     .05       0
  5727.3      .1       0  5760.2     .12       0
Bank Sta=5029.4,5035.6
XS Rating Curve= 0 ,0
Exp/Cntr=0.3,0.1

Type RM Length L Ch R = 1 ,4118    ,925,925,925
BEGIN DESCRIPTION:
Walnut3 2.5
END DESCRIPTION:
XS GIS Cut Line= 6
      2750540.08      6751798.66       2750102.6      6751638.95
      2750033.16      6751416.72      2749949.01      6751378.44
      2749636.96       6751521.5      2749019.76      6751841.53
#Sta/Elev= 30
  3627.5  349.28  3747.8  353.33  3783.6  351.01  3837.6  343.88  3925.7  333.06
  4042.6  323.83  4162.4  322.36  4185.4  323.76  4206.3  322.31  4265.1  324.57
  4374.2  323.02  4387.6  324.37    4466  325.21  4506.5  321.15    4535  320.91
  4741.7  322.93    4854  324.44  4897.7   323.9  4902.8  320.05  4909.3  324.45
  4976.9  323.78  4996.3   313.6  4997.3   313.1  5002.5   313.6  5007.8  318.61
  5021.9  324.85  5069.5  323.46  5074.1  321.33  5079.8  324.62    5457  329.66
#Mann= 9 ,-1 , 0
  3627.5     .05       0  3837.6     .12       0  4387.6     .05       0
  4741.7      .1       0    4854     .12       0  4897.7      .1       0
  4996.3     .07       0  5002.5      .1       0  5069.5     .05       0
Bank Sta=4996.3,5002.5
XS Rating Curve= 0 ,0
Exp/Cntr=0.3,0.1

Type RM Length L Ch R = 1 ,3193    ,280,280,280
BEGIN DESCRIPTION:
Walnut3 2.0
END DESCRIPTION:
XS GIS Cut Line= 5
      2750621.26      6751401.31      2750401.75      6751126.92
      2749689.04      6750861.78      2749376.54      6750948.58
      2749007.04      6751040.46
#Sta/Elev= 30
  3305.6  339.65  3323.6  336.81  3352.4  334.79    3402  333.44  3472.5  327.23
  3480.5  327.77  3536.5  323.34  3600.5  320.48  3780.5  318.59  4147.9  318.35
  4233.6  321.14    4282  319.83  4349.6  320.08  4468.9  324.49  4524.4  324.38
  4729.4  329.04  4804.1  328.94  4849.3  327.27  4907.2  325.09  4935.6  320.28
  4940.7  315.08  4945.2   312.5  4946.3     312  4951.5   312.5    4969  312.76
  4976.9  315.22  4982.1   319.4  4989.6  321.08  5038.1  321.15  5122.5  320.18
#Mann= 5 ,-1 , 0
  3305.6     .05       0  4849.3     .12       0  4945.2     .05       0
  4951.5     .12       0  5038.1     .05       0
Bank Sta=4945.2,4951.5
XS Rating Curve= 0 ,0
Exp/Cntr=0.3,0.1

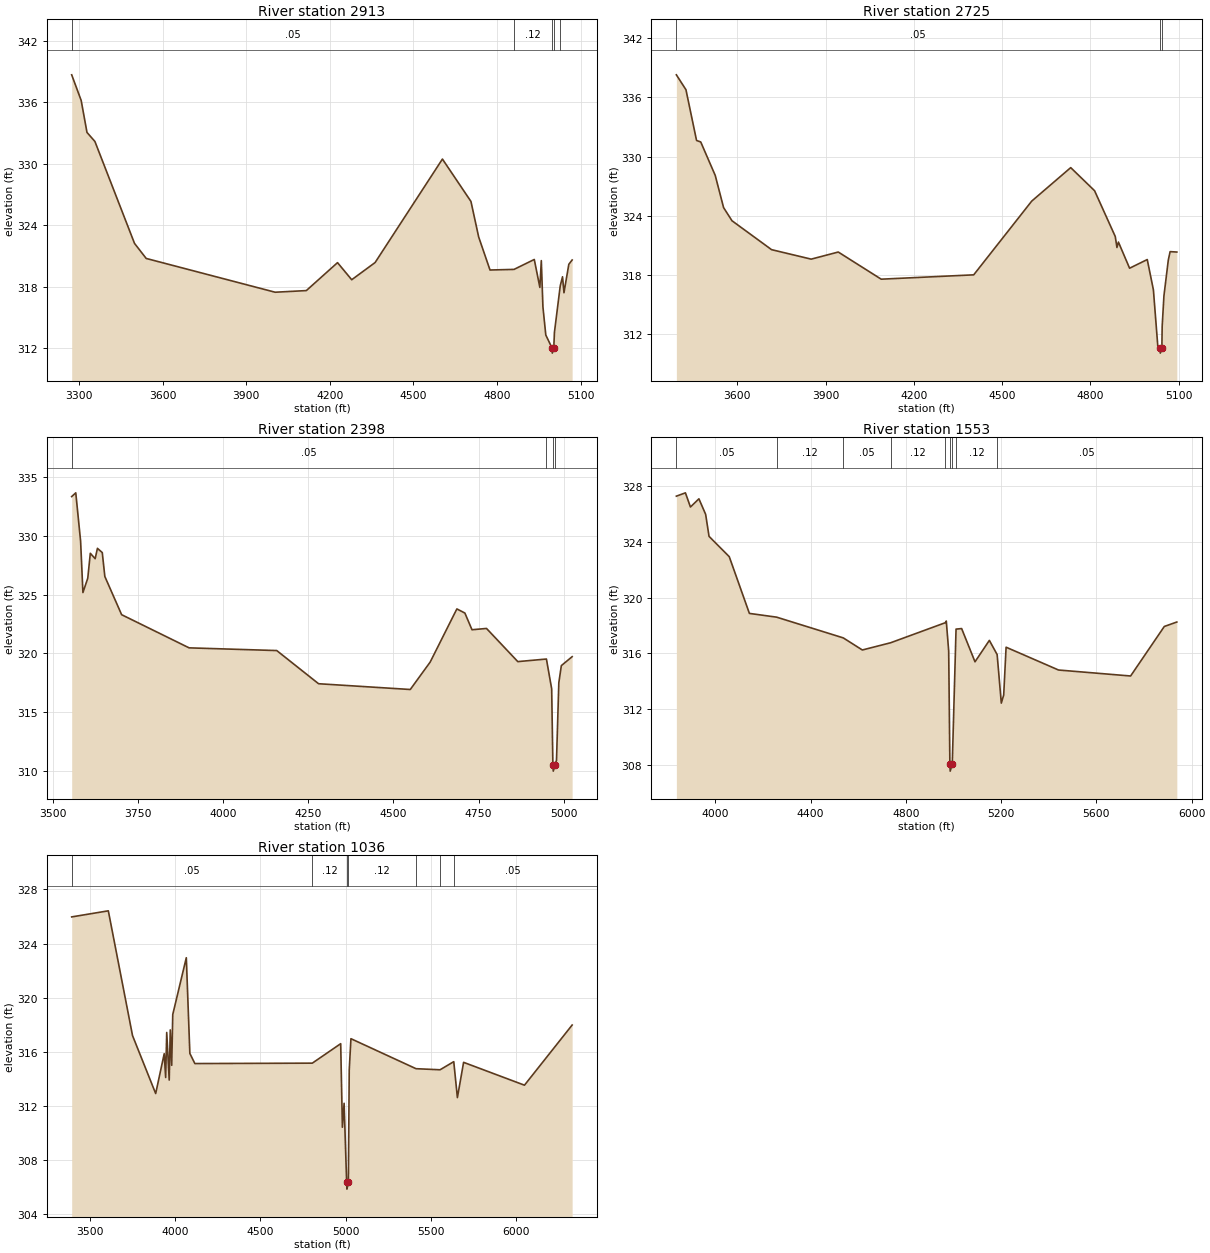
Type RM Length L Ch R = 1 ,2913    ,188,188,188
BEGIN DESCRIPTION:
Walnut3 1.8
END DESCRIPTION:
XS GIS Cut Line= 5
      2750644.74      6751340.16      2750247.13       6750895.6
      2749461.88       6750749.4       2749212.2      6750813.73
      2749074.52      6750778.18
#Sta/Elev= 30
  3273.9  338.69  3307.9  336.19  3328.8  333.06  3357.2  332.18  3499.3  322.22
  3541.2  320.75  4003.7  317.45  4115.6  317.61  4227.5  320.34  4278.4  318.67
  4362.3  320.35  4603.8  330.46  4706.1  326.32  4733.8  322.85  4774.5  319.62
  4860.6  319.68  4933.3  320.65  4953.3  317.92  4958.5  320.54  4964.3  316.02
  4974.6  313.27  4996.9     312  4997.9   311.5  5003.2     312  5005.6  313.53
  5026.4  318.07  5034.6  318.96  5039.8   317.4  5057.2  320.18  5069.1   320.6
#Mann= 5 ,-1 , 0
  3273.9     .05       0  4860.6     .12       0  4996.9     .05       0
  5003.2     .12       0  5026.4     .05       0
Bank Sta=4996.9,5003.2
XS Rating Curve= 0 ,0
Exp/Cntr=0.3,0.1

Type RM Length L Ch R = 1 ,2725    ,327,327,327
BEGIN DESCRIPTION:
Walnut3 1.7
END DESCRIPTION:
XS GIS Cut Line= 5
      2750704.91      6751335.18      2750298.65      6750879.17
       2749525.8      6750712.59      2749344.07      6750730.49
      2749247.96      6750663.82
#Sta/Elev= 30
  3393.1  338.28  3425.7  336.77  3461.7  331.63  3475.9  331.48  3525.2  328.09
  3553.6  324.83  3582.1   323.5  3716.7  320.57  3851.3  319.61  3943.3  320.33
  4089.3  317.58  4403.7  318.02  4600.9  325.49  4733.4  328.88  4814.5  326.54
  4884.8   321.9  4890.5  320.79  4895.5  321.34  4933.5  318.69  4993.5  319.57
  5014.4   316.5  5029.3  310.82  5036.9  310.59  5037.9  310.09  5043.2  310.59
  5044.2   312.8  5050.2  315.89  5065.1  319.53  5071.2  320.37    5094  320.33
#Mann= 3 ,-1 , 0
  3393.1     .05       0  5036.9     .07       0  5043.2     .05       0
Bank Sta=5036.9,5043.2
XS Rating Curve= 0 ,0
Exp/Cntr=0.3,0.1

Type RM Length L Ch R = 1 ,2398    ,845,845,845
BEGIN DESCRIPTION:
Walnut3 1.5
END DESCRIPTION:
XS GIS Cut Line= 5
      2750699.02      6751254.98      2750301.36      6750810.37
      2749761.51      6750692.47      2749537.31      6750490.69
      2749522.97      6750502.38
#Sta/Elev= 30
  3555.3  333.33  3567.3  333.65  3581.5  329.53  3588.3  325.17  3602.5  326.39
    3610  328.51  3624.2  328.05  3630.9  328.93  3645.1  328.57  3652.6  326.54
  3701.9  323.29    3900  320.47  4157.3  320.24  4280.1  317.42  4549.3  316.93
  4607.7  319.26  4686.1  323.78  4709.6  323.43  4730.5  322.01  4773.1  322.12
    4865   319.3    4949  319.52  4964.4  316.99    4968  310.49  4969.1  309.99
  4974.3  310.49  4978.6  310.92  4985.4   317.5  4992.8  318.96  5024.5  319.72
#Mann= 4 ,-1 , 0
  3555.3     .05       0    4949     .12       0    4968     .05       0
  4974.3     .05       0
Bank Sta=4968,4974.3
XS Rating Curve= 0 ,0
Exp/Cntr=0.3,0.1

Type RM Length L Ch R = 1 ,1553    ,517,517,517
BEGIN DESCRIPTION:
Walnut3 1.0
END DESCRIPTION:
XS GIS Cut Line= 4
      2750977.99      6750582.74      2750418.21      6750054.49
       2749350.5      6750158.65      2749093.96      6750196.71
#Sta/Elev= 30
    3836   327.3    3874  327.54  3895.1  326.52  3930.7  327.11    3959  325.99
  3973.2  324.41  4058.1  322.95  4142.7  318.87  4257.2   318.6  4536.9  317.11
  4617.1  316.24  4735.9  316.76  4965.3   318.2  4969.6  318.32  4979.7  316.16
  4984.7  308.03  4986.1  307.53  4994.7  308.03  5010.6  317.74  5034.1  317.78
  5090.2  315.39  5150.5  316.93  5183.2  315.91  5200.7  312.42  5210.7     313
  5220.8  316.44    5441   314.8  5743.7  314.37  5885.2  317.93  5937.8  318.25
#Mann= 9 ,-1 , 0
    3836     .05       0  4257.2     .12       0  4536.9     .05       0
  4735.9     .12       0  4965.3      .1       0  4984.7     .07       0
  4994.7      .1       0  5010.6     .12       0  5183.2     .05       0
Bank Sta=4984.7,4994.7
XS Rating Curve= 0 ,0
Exp/Cntr=0.3,0.1

Type RM Length L Ch R = 1 ,1036    ,0,0,0
BEGIN DESCRIPTION:
Walnut3 0.5
END DESCRIPTION:
XS GIS Cut Line= 4
      2751641.08      6750605.59      2750429.19      6749713.82
      2750136.51      6749732.11      2749061.88      6750105.99
#Sta/Elev= 30
  3392.8  325.97  3607.7  326.42  3749.7  317.19  3885.5   312.9  3935.6  315.85
    3944  314.09  3950.3  317.42  3964.9   313.9  3971.1  317.61  3979.5  314.99
  3985.7  318.75  4065.2  322.95    4086  315.87  4115.3  315.12  4804.3  315.15
  4970.8  316.59  4980.8  310.41  4990.8  312.18  5005.8  306.33  5007.2  305.83
  5015.8  306.33  5020.9  314.64  5030.9  316.96  5412.7  314.74  5553.7  314.66
  5634.1  315.26  5655.4   312.6  5691.8  315.21  6048.9  313.52  6328.5  317.97
#Mann= 7 ,-1 , 0
  3392.8     .05       0  4804.3     .12       0  5005.8     .07       0
  5015.8     .12       0  5412.7      .1       0  5553.7     .12       0
  5634.1     .05       0
Bank Sta=5005.8,5015.8
XS Rating Curve= 0 ,0
Exp/Cntr=0.3,0.1

Chan Stop Cuts=-1
Use User Specified Reach Order=0
Composite Channel Slope=5