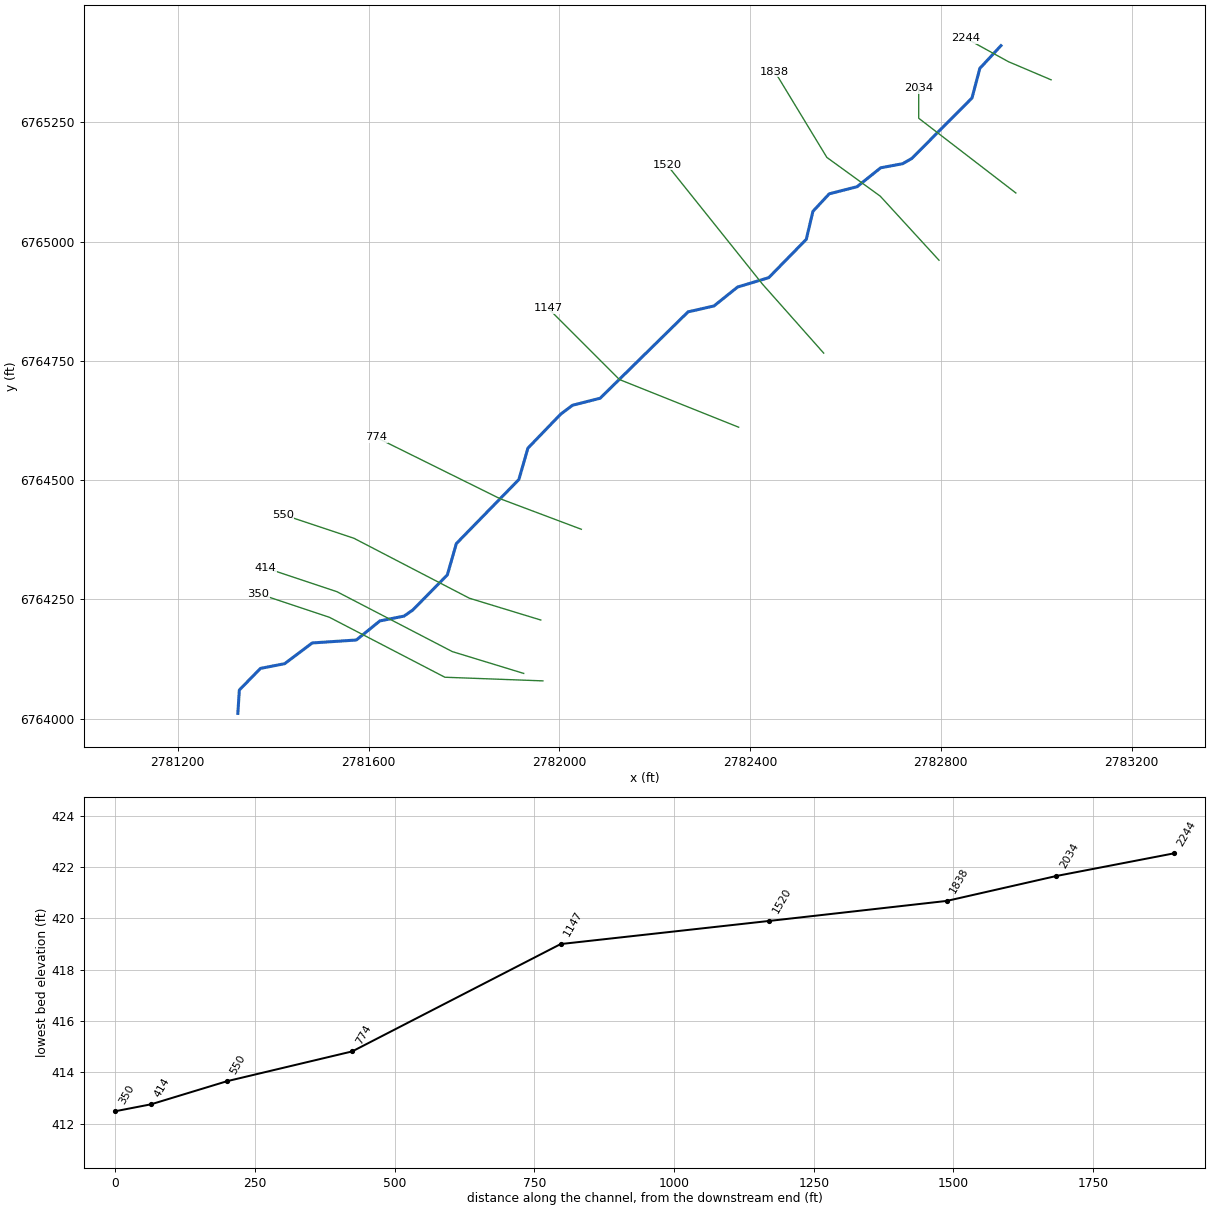
--- Walnut30.prj (project) ---

Proj Title=Walnut30 Base Level Engineering
Current Plan=p01
Default Exp/Contr=0.3,0.1
English Units
Geom File=g01
Flow File=f01
Plan File=p01
Y Axis Title=Elevation
X Axis Title(PF)=Main Channel Distance
X Axis Title(XS)=Station
BEGIN DESCRIPTION:
Walnut30
END DESCRIPTION:
DSS Export Rating Curves= 0
DSS Export Rating Curve Sorted= 0
DSS Export Volume Flow Curves= 0
DXF OffsetX= 0
DXF OffsetY= 0
DXF ScaleX= 1
DXF ScaleY= 10

--- Walnut30.p01 (plan) ---

Plan Title=Multiple Run
Program Version=4.10
Short Identifier=Multiple
Geom File=g01
Flow File=f01
Subcritical Flow
K Sum by GR= 0
Std Step Tol= 0.01
Critical Tol= 0.01
Num of Std Step Trials= 20
Max Error Tol= 0.3
Flow Tol Ratio= 0.001
Split Flow NTrial= 30
Split Flow Tol= 0.02
Split Flow Ratio= 0.02
Log Output Level= 0
Friction Slope Method= 1
Unsteady Friction Slope Method= 2
Unsteady Bridges Friction Slope Method= 1
Parabolic Critical Depth
Global Vel Dist= 1 , 1 , 1
Global Log Level= 0
CheckData=True
Encroach Param=-1 ,0,0, 0
BEGIN DESCRIPTION:
Multiple Run
END DESCRIPTION:
Computation Interval=1HOUR
Output Interval=1HOUR
Run HTab= 0
Run UNet= 0
Run PostProcess= 0
Run WQNet= 0
UNET Theta= 1
UNET Theta Warmup= 1
UNET ZTol= 0.02
UNET ZSATol= 0.05
UNET MxIter= 20
UNET MaxInSteps= 0
UNET DtIC= 0
UNET DtMin= 0
UNET MaxCRTS= 20
UNET WFStab= 2
UNET SFStab= 1
UNET WFX= 1
UNET SFX= 1
UNET DSS MLevel= 4
UNET DZMax Abort= 100
UNET Convert EG Bridges= 0
UNET Use Existing IB Tables=-1
UNET Froude Reduction=False
UNET Froude Limit= 1
UNET Froude Power= 10
UNET Time Slicing=0,0, 5
UNET Junction Losses=0
Instantaneous Interval=1HOUR
Write IC File= 0
Write IC File at Sim End=0
Echo Input=False
Echo Parameters=False
Echo Output=False
Write Detailed= 0
WQ AD Non Conservative
WQ ULTIMATE=-1
WQ Max Comp Step=1HOUR
WQ Output Interval=15MIN
WQ Output Selected Increments= 0
WQ Output face flow=0
WQ Output face velocity=0
WQ Output face area=0
WQ Output face dispersion=0
WQ Output cell volume=0
WQ Output cell surface area=0
WQ Output cell continuity=0
WQ Output cumulative cell continuity=0
WQ Output face conc=0
WQ Output face dconc_dx=0
WQ Output face courant=0
WQ Output face peclet=0
WQ Output face adv mass=0
WQ Output face disp mass=0
WQ Output cell mass=0
WQ Output cell source sink temp=0
WQ Output cell source sink nsm=0
WQ Output MaxMinRange=-1
WQ Daily Max Min Mean=-1
WQ Daily Range=0
WQ Daily Time=0
WQ Create Restart=0
WQ Fixed Restart=0
WQ System Summary=0
WQ Use Fixed Temperature=0
Sorting and Armoring Iterations= 10
XS Update Threshold= 0.02
Hydraulics Update Threshold= 0.02
Energy Slope Method= 1
Volume Change Method= 0
XS Weighting Method= 0
Number of US Weighted Cross Sections= 1
Number of DS Weighted Cross Sections= 1
Upstream XS Weight=0.25
Main XS Weight=0.5
Downstream XS Weight=0.25
Number of DS XS's Weighted with US Boundary= 1
Upstream Boundary Weight= 1
Weight of XSs Associated with US Boundary= 0
Number of US XS's Weighted with DS Boundary= 1
Downstream Boundary Weight= 0.5
Weight of XSs Associated with DS Boundary= 0.5
Sediment Output Level= 4
Mass or Volume Output= 0
Output Increment Type= 1
Profile and TS Output Increment= 10
XS Output Flag= 0
XS Output Increment= 10
Disregard all LS=0
Disregard all Conn=0
Disregard all Breaches=0
Disregard all Pumps=0

--- Walnut30.f01 (steady flow) ---

Flow Title=Multiple
Number of Profiles=7
Profile Names=10-year,25-year,50-year,1pct_min,100-year,1pct_plu,500-year
River Rch & RM= Walnut30,Reach-1,2244
     484     649     783     471     939    1874    1352
Boundary for River Rch & Prof#=Walnut30,Reach-1,1
Up Type=0
Dn Type=3
Dn Slope=0.005
Boundary for River Rch & Prof#=Walnut30,Reach-1,2
Up Type=0
Dn Type=3
Dn Slope=0.005
Boundary for River Rch & Prof#=Walnut30,Reach-1,3
Up Type=0
Dn Type=3
Dn Slope=0.005
Boundary for River Rch & Prof#=Walnut30,Reach-1,4
Up Type=0
Dn Type=3
Dn Slope=0.005
Boundary for River Rch & Prof#=Walnut30,Reach-1,5
Up Type=0
Dn Type=3
Dn Slope=0.005
Boundary for River Rch & Prof#=Walnut30,Reach-1,6
Up Type=0
Dn Type=3
Dn Slope=0.005
Boundary for River Rch & Prof#=Walnut30,Reach-1,7
Up Type=0
Dn Type=3
Dn Slope=0.005

--- Walnut30.g01 (geometry) ---

Geom Title=Existing Conditions
Program Version=4.10

River Reach=Walnut30        ,Reach-1
Reach XY= 30
        2782926.        6765411.      2782881.71      6765363.35
       2782865.3      6765301.29      2782739.22      6765174.62
      2782719.97       6765163.5      2782673.81       6765154.9
      2782624.24       6765115.2        2782566.      6765100.37
      2782531.75      6765063.54      2782517.84      6765004.95
      2782439.24      6764924.61      2782373.81       6764904.9
      2782324.26      6764865.19      2782269.94      6764852.86
      2782085.68      6764671.78      2782027.64      6764657.03
      2782002.49      6764638.01      2781934.15      6764567.07
      2781915.22      6764501.32      2781784.16      6764367.05
      2781765.23       6764301.3      2781692.71      6764227.63
      2781674.38      6764214.94      2781623.83      6764204.86
      2781574.42      6764164.83      2781481.96      6764158.67
      2781424.24       6764115.2      2781373.48      6764105.32
      2781329.14      6764059.97        2781326.        6764011.

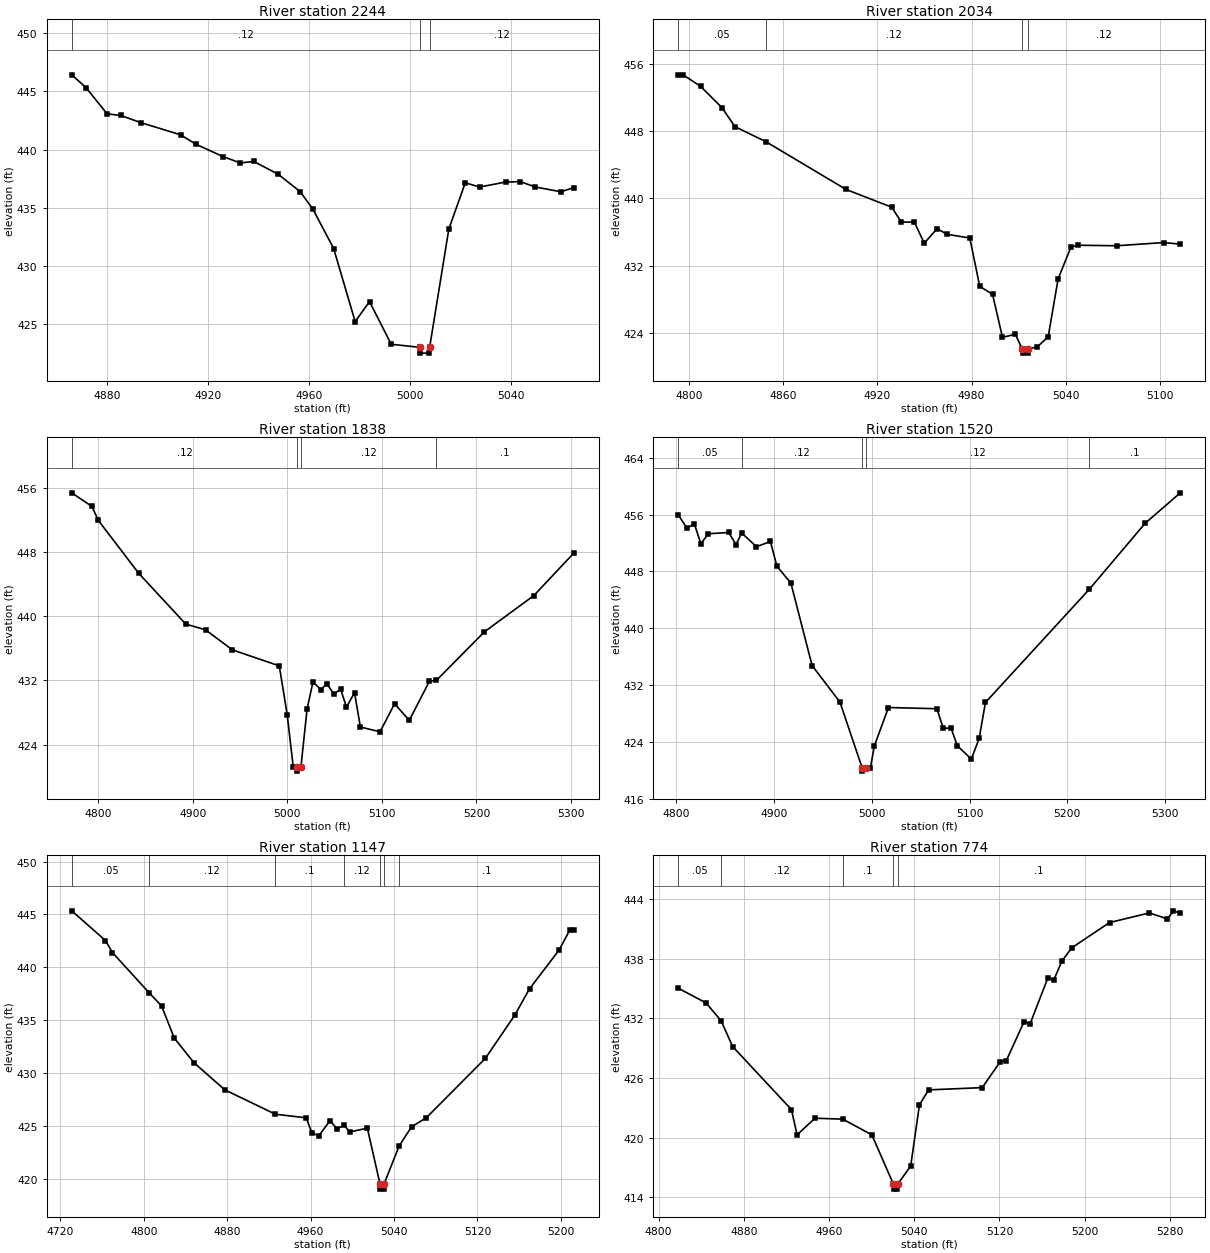
Type RM Length L Ch R = 1 ,2244    ,210,210,210
BEGIN DESCRIPTION:
Walnut30 5.0
END DESCRIPTION:
XS GIS Cut Line= 3
      2783031.16      6765339.38      2782941.59      6765377.44
      2782852.67      6765426.35
#Sta/Elev= 29
    4866  446.42  4871.6  445.33    4880  443.07  4885.4  442.93  4893.3  442.32
  4909.1  441.27  4915.1  440.47  4925.9   439.4  4932.7  438.86  4938.1  438.98
  4947.7  437.89  4956.4   436.4  4961.5  434.88  4969.7  431.51  4978.2  425.24
  4983.9  426.95  4992.5  423.29  5003.7  423.03    5004  422.53  5007.5  422.53
  5007.7  423.03  5015.3  433.18  5021.8  437.15  5027.5  436.79  5037.9  437.22
  5043.6  437.25  5049.6  436.79  5059.7  436.38  5064.8  436.74
#Mann= 3 ,-1 , 0
    4866     .12       0  5003.7     .07       0  5007.7     .12       0
Bank Sta=5003.7,5007.7
XS Rating Curve= 0 ,0
Exp/Cntr=0.3,0.1

Type RM Length L Ch R = 1 ,2034    ,196,196,196
BEGIN DESCRIPTION:
Walnut30 4.5
END DESCRIPTION:
XS GIS Cut Line= 3
      2782957.23      6765102.14      2782753.56       6765258.8
      2782753.56      6765321.45
#Sta/Elev= 30
  4793.3  454.67  4796.4  454.67  4807.5  453.31  4821.2  450.76  4829.4  448.52
    4849  446.75  4900.1  441.07  4929.1  438.97  4935.4  437.19  4943.6   437.2
  4949.9  434.69  4958.1  436.42  4964.4  435.75  4978.9  435.31  4985.2  429.59
  4993.4  428.61  4999.7  423.52  5007.9  423.89  5012.2  422.15  5012.5  421.65
    5016  421.65  5016.2  422.15  5021.9   422.4  5028.8  423.59  5035.1  430.45
  5043.3  434.24    5048  434.45  5072.4  434.39  5102.4  434.77  5112.9  434.58
#Mann= 4 ,-1 , 0
  4793.3     .05       0    4849     .12       0  5012.2     .07       0
  5016.2     .12       0
Bank Sta=5012.2,5016.2
XS Rating Curve= 0 ,0
Exp/Cntr=0.3,0.1

Type RM Length L Ch R = 1 ,1838    ,318,318,318
BEGIN DESCRIPTION:
Walnut30 4.0
END DESCRIPTION:
XS GIS Cut Line= 4
       2782796.1      6764961.08      2782672.97       6765095.4
      2782560.96       6765176.7      2782451.77      6765356.64
#Sta/Elev= 30
  4771.9   455.4  4793.2   453.7    4800  451.96  4842.5  445.39  4892.5  439.02
  4913.4  438.31  4941.8  435.81  4991.4  433.81  4999.8  427.71  5006.1  421.25
  5010.3  421.18  5010.5  420.68  5014.3  421.18  5020.8  428.43    5027  431.79
  5035.5  430.86  5041.7  431.58  5049.2   430.3  5056.3   430.9  5062.5  428.66
    5071  430.48  5077.2  426.18    5098  425.59  5113.4  429.09  5128.9  427.01
  5150.2  431.88  5157.7  432.01  5208.4  438.06  5260.7  442.58    5303  447.89
#Mann= 4 ,-1 , 0
  4771.9     .12       0  5010.3     .07       0  5014.3     .12       0
  5157.7      .1       0
Bank Sta=5010.3,5014.3
XS Rating Curve= 0 ,0
Exp/Cntr=0.3,0.1

Type RM Length L Ch R = 1 ,1520    ,373,373,373
BEGIN DESCRIPTION:
Walnut30 3.0
END DESCRIPTION:
XS GIS Cut Line= 3
      2782554.32      6764766.36        2782426.        6764911.
      2782226.01      6765160.99
#Sta/Elev= 30
  4802.1  455.97    4811  454.08  4818.6  454.67  4825.3  451.89  4832.8   453.3
  4853.7  453.48  4861.2  451.78    4867  453.42  4882.1  451.47  4896.4  452.22
    4903  448.73  4917.3  446.37    4939  434.76  4967.5  429.61  4990.1   420.4
  4990.4   419.9  4994.1   420.4  4998.7   420.4  5002.7  423.46  5017.1  428.85
  5066.7  428.68  5073.1  425.93  5081.1  425.96  5087.5  423.48  5101.9  421.59
  5109.9  424.53  5116.3  429.56  5222.6   445.5  5279.6  454.77  5315.6  459.06
#Mann= 5 ,-1 , 0
  4802.1     .05       0    4867     .12       0  4990.1     .07       0
  4994.1     .12       0  5222.6      .1       0
Bank Sta=4990.1,4994.1
XS Rating Curve= 0 ,0
Exp/Cntr=0.3,0.1

Type RM Length L Ch R = 1 ,1147    ,373,373,373
BEGIN DESCRIPTION:
Walnut30 2.0
END DESCRIPTION:
XS GIS Cut Line= 3
      2782375.98      6764611.01        2782126.        6764711.
      2781975.98      6764861.02
#Sta/Elev= 30
    4731  445.34  4763.3  442.53    4770  441.39  4805.2  437.58  4817.1  436.34
  4829.3  433.29  4848.1  430.97  4877.7   428.4  4926.2  426.09  4955.8  425.75
  4961.2  424.33  4967.9  424.05  4978.7  425.49  4985.4  424.69  4992.1  425.05
  4997.5  424.41  5014.4  424.77  5026.5   419.5  5026.8     419  5030.3     419
  5030.5   419.5  5044.9  423.09  5056.8   424.9    5071  425.76  5127.5  431.37
  5155.8  435.47  5169.9  437.96  5198.2  441.62  5208.8  443.57  5212.4  443.57
#Mann= 7 ,-1 , 0
    4731     .05       0  4805.2     .12       0  4926.2      .1       0
  4992.1     .12       0  5026.5     .07       0  5030.5     .12       0
  5044.9      .1       0
Bank Sta=5026.5,5030.5
XS Rating Curve= 0 ,0
Exp/Cntr=0.3,0.1

Type RM Length L Ch R = 1 ,774     ,224,224,224
BEGIN DESCRIPTION:
Walnut30 1.0
END DESCRIPTION:
XS GIS Cut Line= 3
      2782046.19        6764397.        2781876.        6764461.
       2781616.4      6764589.52
#Sta/Elev= 30
  4818.4  435.03  4844.6  433.54  4858.6  431.76  4869.5  429.16  4924.7  422.82
    4930  420.28  4946.8  421.95  4972.9  421.86  5000.2  420.28  5020.5  415.32
  5020.8  414.82  5024.3  414.82  5024.5  415.32  5036.7  417.14  5044.9  423.29
  5053.5   424.8  5103.9  425.03  5120.8  427.64  5126.4  427.72  5143.2  431.67
  5148.8  431.43  5165.6  436.09  5171.2  435.88  5178.8  437.78  5188.1   439.1
  5223.4  441.63  5260.9   442.6  5277.8  441.99  5283.4  442.81  5289.9  442.55
#Mann= 5 ,-1 , 0
  4818.4     .05       0  4858.6     .12       0  4972.9      .1       0
  5020.5     .06       0  5024.5      .1       0
Bank Sta=5020.5,5024.5
XS Rating Curve= 0 ,0
Exp/Cntr=0.3,0.1

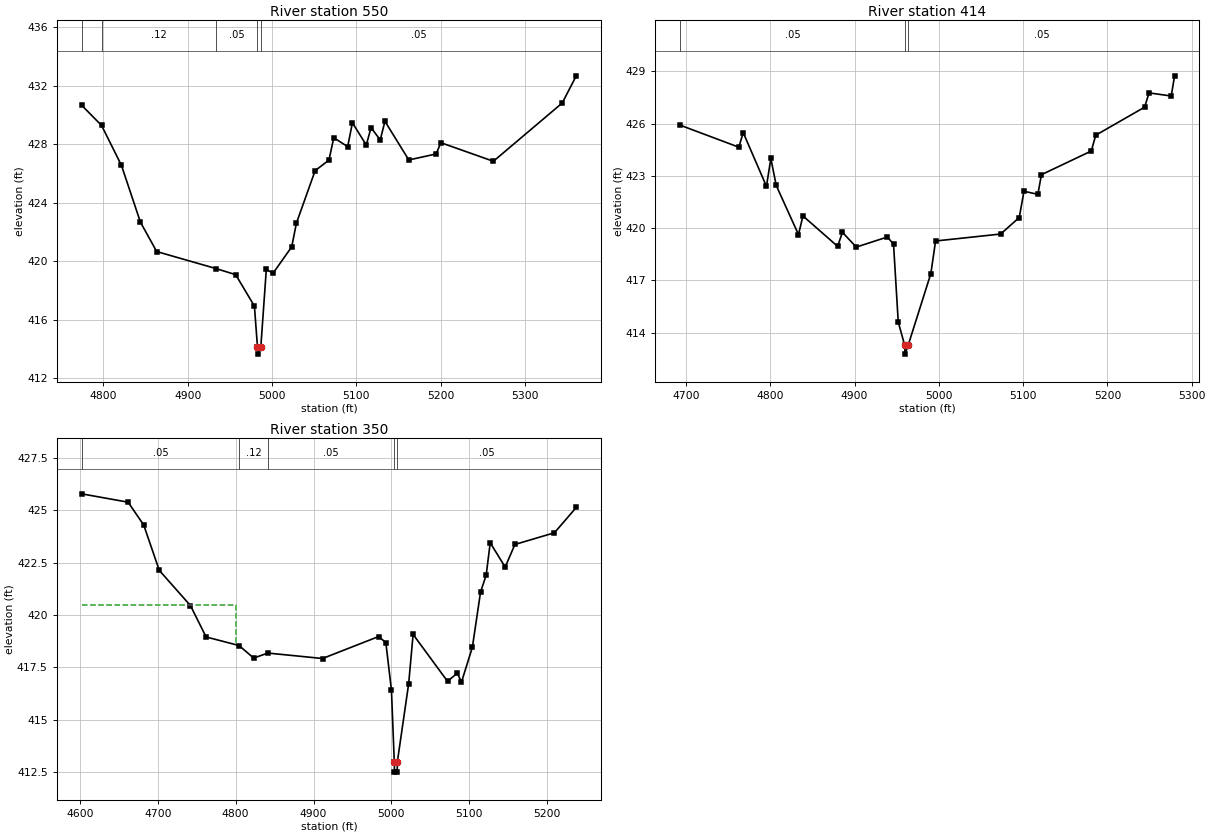
Type RM Length L Ch R = 1 ,550     ,136,136,136
BEGIN DESCRIPTION:
Walnut30 0.6
END DESCRIPTION:
XS GIS Cut Line= 4
      2781961.16      6764206.73      2781811.56      6764252.41
      2781569.33      6764378.18      2781420.15       6764427.9
#Sta/Elev= 30
  4774.2  430.67  4797.8  429.29  4821.4  426.56  4843.9  422.68  4863.2  420.67
  4933.4  419.51  4956.9  419.09  4979.1  416.94  4982.7  414.16  4982.9  413.66
  4986.7  414.16  4993.2  419.45  5001.2  419.19  5023.3  420.99  5028.9  422.61
  5051.1   426.2  5067.5  426.92  5073.2  428.45  5089.7  427.84  5095.3  429.47
  5111.8  427.95  5117.4  429.14  5128.3   428.3  5133.9  429.57  5162.2  426.93
  5194.6  427.34  5200.2  428.11  5262.5  426.84  5344.1  430.82  5360.8  432.68
#Mann= 5 ,-1 , 0
  4774.2     .05       0  4797.8     .12       0  4933.4     .05       0
  4982.7     .06       0  4986.7     .05       0
Bank Sta=4982.7,4986.7
XS Rating Curve= 0 ,0
Exp/Cntr=0.3,0.1

Type RM Length L Ch R = 1 ,414     ,64,64,64
BEGIN DESCRIPTION:
Walnut30 0.4
END DESCRIPTION:
XS GIS Cut Line= 4
      2781925.31      6764094.81      2781775.74      6764140.49
      2781533.52      6764266.25      2781383.93      6764316.12
#Sta/Elev= 30
  4692.7  425.92  4762.6  424.65  4767.8  425.49  4795.4   422.4  4800.6     424
    4807  422.45  4833.4  419.63  4838.7   420.7  4879.9  418.95  4885.5  419.76
    4902  418.91  4938.9  419.49  4946.2  419.08  4951.8   414.6  4959.5  413.26
  4959.7  412.76  4963.5  413.26  4990.5  417.39  4996.1  419.26  5073.3  419.66
  5095.4  420.61    5101  422.12  5117.5  421.94  5121.7  423.07  5180.9  424.43
  5186.2  425.34  5244.2  426.95  5249.4  427.77  5275.8  427.59  5279.7  428.75
#Mann= 3 ,-1 , 0
  4692.7     .05       0  4959.5     .05       0  4963.5     .05       0
Bank Sta=4959.5,4963.5
XS Rating Curve= 0 ,0
Exp/Cntr=0.3,0.1

Type RM Length L Ch R = 1 ,350     ,0,0,0
BEGIN DESCRIPTION:
Walnut30 0.2
END DESCRIPTION:
XS GIS Cut Line= 4
      2781965.65      6764079.14      2781760.07      6764086.77
      2781517.85      6764212.53      2781369.43        6764262.
#Sta/Elev= 30
  4602.3  425.79    4662  425.39    4682   424.3    4702  422.13    4742  420.45
  4762.1  418.95  4804.4  418.54  4823.2  417.94  4841.3  418.18  4911.6  417.92
  4983.6  418.97  4992.9  418.68  5000.1   416.4  5003.7  412.99    5004  412.49
  5007.5  412.49  5007.7  412.99  5022.2  416.72  5027.9  419.07  5072.1  416.83
  5084.6  417.22    5090  416.79    5104  418.46  5114.5   421.1  5121.7   421.9
  5126.9  423.45  5146.1  422.29  5158.6  423.37  5209.4  423.93  5237.4  425.14
#Mann= 5 ,-1 , 0
  4602.3     .05       0  4804.4     .12       0  4841.3     .05       0
  5003.7     .05       0  5007.7     .05       0
#XS Ineff= 2 , 0
       0    4800   420.5               0
Permanent Ineff=
       F       F
Bank Sta=5003.7,5007.7
XS Rating Curve= 0 ,0
Exp/Cntr=0.3,0.1

Chan Stop Cuts=-1
Use User Specified Reach Order=0
Composite Channel Slope=5