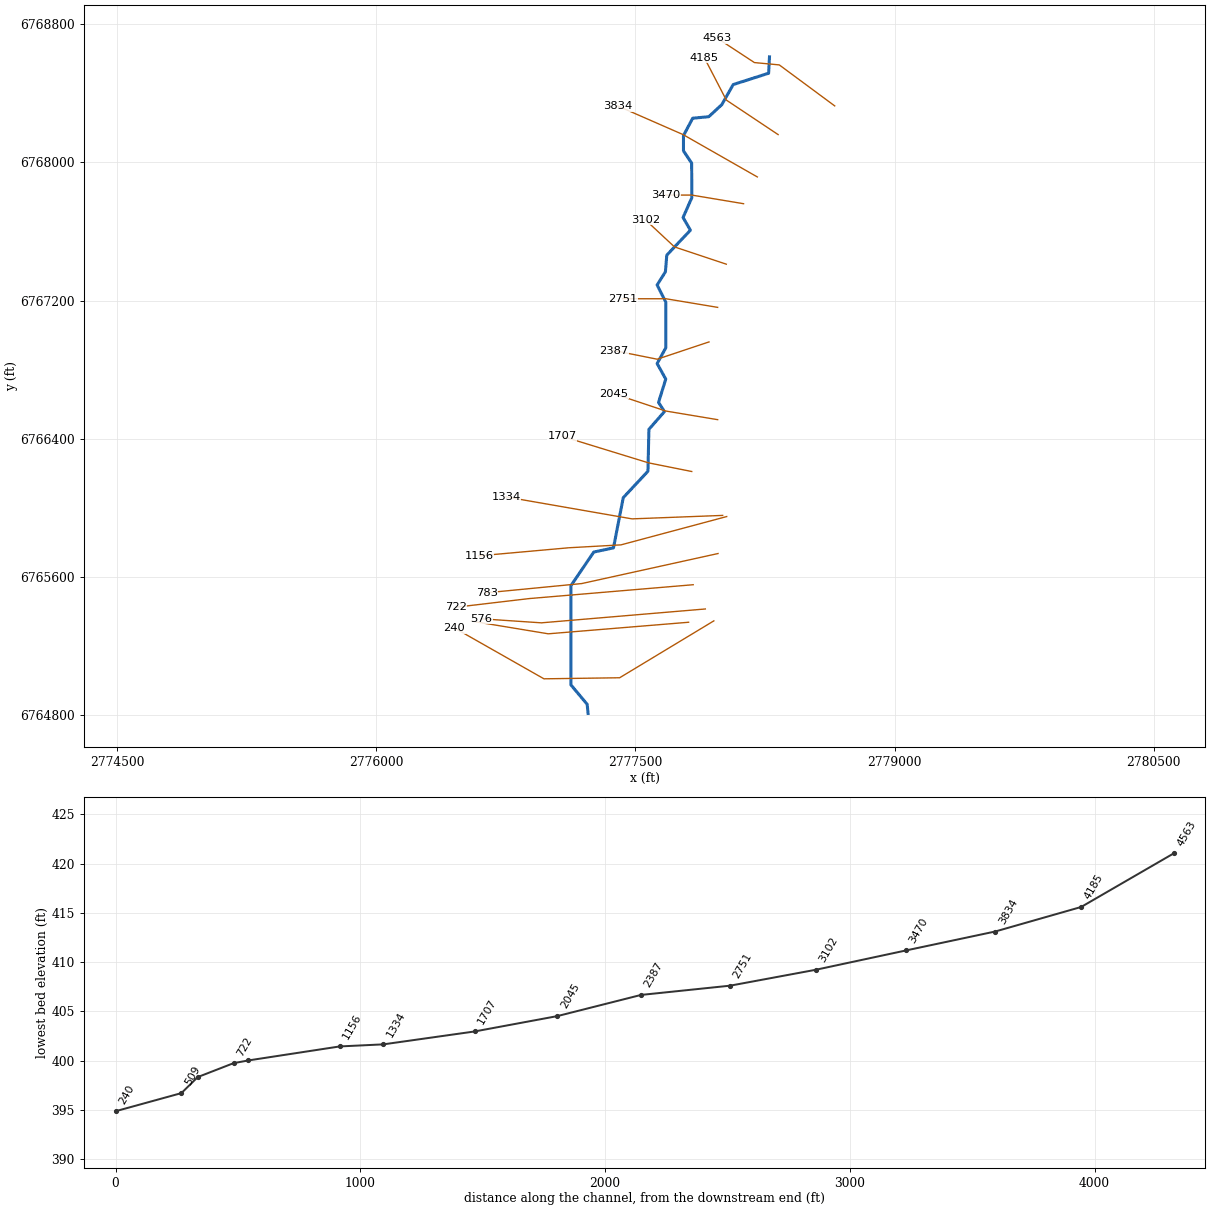
--- Walnut31.prj (project) ---

Proj Title=Walnut31 Base Level Engineering
Current Plan=p01
Default Exp/Contr=0.3,0.1
English Units
Geom File=g01
Flow File=f01
Plan File=p01
Y Axis Title=Elevation
X Axis Title(PF)=Main Channel Distance
X Axis Title(XS)=Station
BEGIN DESCRIPTION:
Walnut31
END DESCRIPTION:
DSS Export Rating Curves= 0
DSS Export Rating Curve Sorted= 0
DSS Export Volume Flow Curves= 0
DXF OffsetX= 0
DXF OffsetY= 0
DXF ScaleX= 1
DXF ScaleY= 10

--- Walnut31.p01 (plan) ---

Plan Title=Multiple Run
Program Version=4.10
Short Identifier=Multiple
Geom File=g01
Flow File=f01
Subcritical Flow
K Sum by GR= 0
Std Step Tol= 0.01
Critical Tol= 0.01
Num of Std Step Trials= 20
Max Error Tol= 0.3
Flow Tol Ratio= 0.001
Split Flow NTrial= 30
Split Flow Tol= 0.02
Split Flow Ratio= 0.02
Log Output Level= 0
Friction Slope Method= 1
Unsteady Friction Slope Method= 2
Unsteady Bridges Friction Slope Method= 1
Parabolic Critical Depth
Global Vel Dist= 1 , 1 , 1
Global Log Level= 0
CheckData=True
Encroach Param=-1 ,0,0, 0
BEGIN DESCRIPTION:
Multiple Run
END DESCRIPTION:
Computation Interval=1HOUR
Output Interval=1HOUR
Run HTab= 0
Run UNet= 0
Run PostProcess= 0
Run WQNet= 0
UNET Theta= 1
UNET Theta Warmup= 1
UNET ZTol= 0.02
UNET ZSATol= 0.05
UNET MxIter= 20
UNET MaxInSteps= 0
UNET DtIC= 0
UNET DtMin= 0
UNET MaxCRTS= 20
UNET WFStab= 2
UNET SFStab= 1
UNET WFX= 1
UNET SFX= 1
UNET DSS MLevel= 4
UNET DZMax Abort= 100
UNET Convert EG Bridges= 0
UNET Use Existing IB Tables=-1
UNET Froude Reduction=False
UNET Froude Limit= 1
UNET Froude Power= 10
UNET Time Slicing=0,0, 5
UNET Junction Losses=0
Instantaneous Interval=1HOUR
Write IC File= 0
Write IC File at Sim End=0
Echo Input=False
Echo Parameters=False
Echo Output=False
Write Detailed= 0
WQ AD Non Conservative
WQ ULTIMATE=-1
WQ Max Comp Step=1HOUR
WQ Output Interval=15MIN
WQ Output Selected Increments= 0
WQ Output face flow=0
WQ Output face velocity=0
WQ Output face area=0
WQ Output face dispersion=0
WQ Output cell volume=0
WQ Output cell surface area=0
WQ Output cell continuity=0
WQ Output cumulative cell continuity=0
WQ Output face conc=0
WQ Output face dconc_dx=0
WQ Output face courant=0
WQ Output face peclet=0
WQ Output face adv mass=0
WQ Output face disp mass=0
WQ Output cell mass=0
WQ Output cell source sink temp=0
WQ Output cell source sink nsm=0
WQ Output MaxMinRange=-1
WQ Daily Max Min Mean=-1
WQ Daily Range=0
WQ Daily Time=0
WQ Create Restart=0
WQ Fixed Restart=0
WQ System Summary=0
WQ Use Fixed Temperature=0
Sorting and Armoring Iterations= 10
XS Update Threshold= 0.02
Hydraulics Update Threshold= 0.02
Energy Slope Method= 1
Volume Change Method= 0
XS Weighting Method= 0
Number of US Weighted Cross Sections= 1
Number of DS Weighted Cross Sections= 1
Upstream XS Weight=0.25
Main XS Weight=0.5
Downstream XS Weight=0.25
Number of DS XS's Weighted with US Boundary= 1
Upstream Boundary Weight= 1
Weight of XSs Associated with US Boundary= 0
Number of US XS's Weighted with DS Boundary= 1
Downstream Boundary Weight= 0.5
Weight of XSs Associated with DS Boundary= 0.5
Sediment Output Level= 4
Mass or Volume Output= 0
Output Increment Type= 1
Profile and TS Output Increment= 10
XS Output Flag= 0
XS Output Increment= 10
Disregard all LS=0
Disregard all Conn=0
Disregard all Breaches=0
Disregard all Pumps=0

--- Walnut31.f01 (steady flow) ---

Flow Title=Multiple
Number of Profiles=7
Profile Names=10-year,25-year,50-year,1pct_min,100-year,1pct_plu,500-year
River Rch & RM= Walnut31,Reach-1,4563
     584     795     971     590    1177    2348    1732
River Rch & RM= Walnut31,Reach-1,2751
     703     965    1184     722    1441    2876    2139
Boundary for River Rch & Prof#=Walnut31,Reach-1,1
Up Type=0
Dn Type=3
Dn Slope=0.005
Boundary for River Rch & Prof#=Walnut31,Reach-1,2
Up Type=0
Dn Type=3
Dn Slope=0.005
Boundary for River Rch & Prof#=Walnut31,Reach-1,3
Up Type=0
Dn Type=3
Dn Slope=0.005
Boundary for River Rch & Prof#=Walnut31,Reach-1,4
Up Type=0
Dn Type=3
Dn Slope=0.005
Boundary for River Rch & Prof#=Walnut31,Reach-1,5
Up Type=0
Dn Type=3
Dn Slope=0.005
Boundary for River Rch & Prof#=Walnut31,Reach-1,6
Up Type=0
Dn Type=3
Dn Slope=0.005
Boundary for River Rch & Prof#=Walnut31,Reach-1,7
Up Type=0
Dn Type=3
Dn Slope=0.005

--- Walnut31.g01 (geometry) ---

Geom Title=Existing Conditions

River Reach=Walnut31,Reach-1
Reach XY= 30
      2778276.00      6768611.00      2778271.02      6768516.27
      2778065.90      6768450.61      2777999.73      6768334.12
      2777924.44      6768264.64      2777831.44      6768255.75
      2777778.13      6768155.06      2777778.17      6768066.98
      2777825.48      6767995.78      2777826.42      6767795.82
      2777775.83      6767681.13      2777818.18      6767607.59
      2777681.52      6767463.43      2777673.62      6767366.97
      2777625.72      6767290.82      2777675.91      6767190.97
      2777675.46      6766926.21      2777625.60      6766836.00
      2777675.60      6766745.73      2777633.81      6766610.90
      2777667.99      6766557.67      2777578.07      6766455.15
      2777572.46      6766212.46      2777429.54      6766059.53
      2777372.97      6765769.01      2777258.90      6765744.69
      2777127.05      6765550.56      2777126.38      6764976.16
      2777220.67      6764863.51      2777226.00      6764811.00

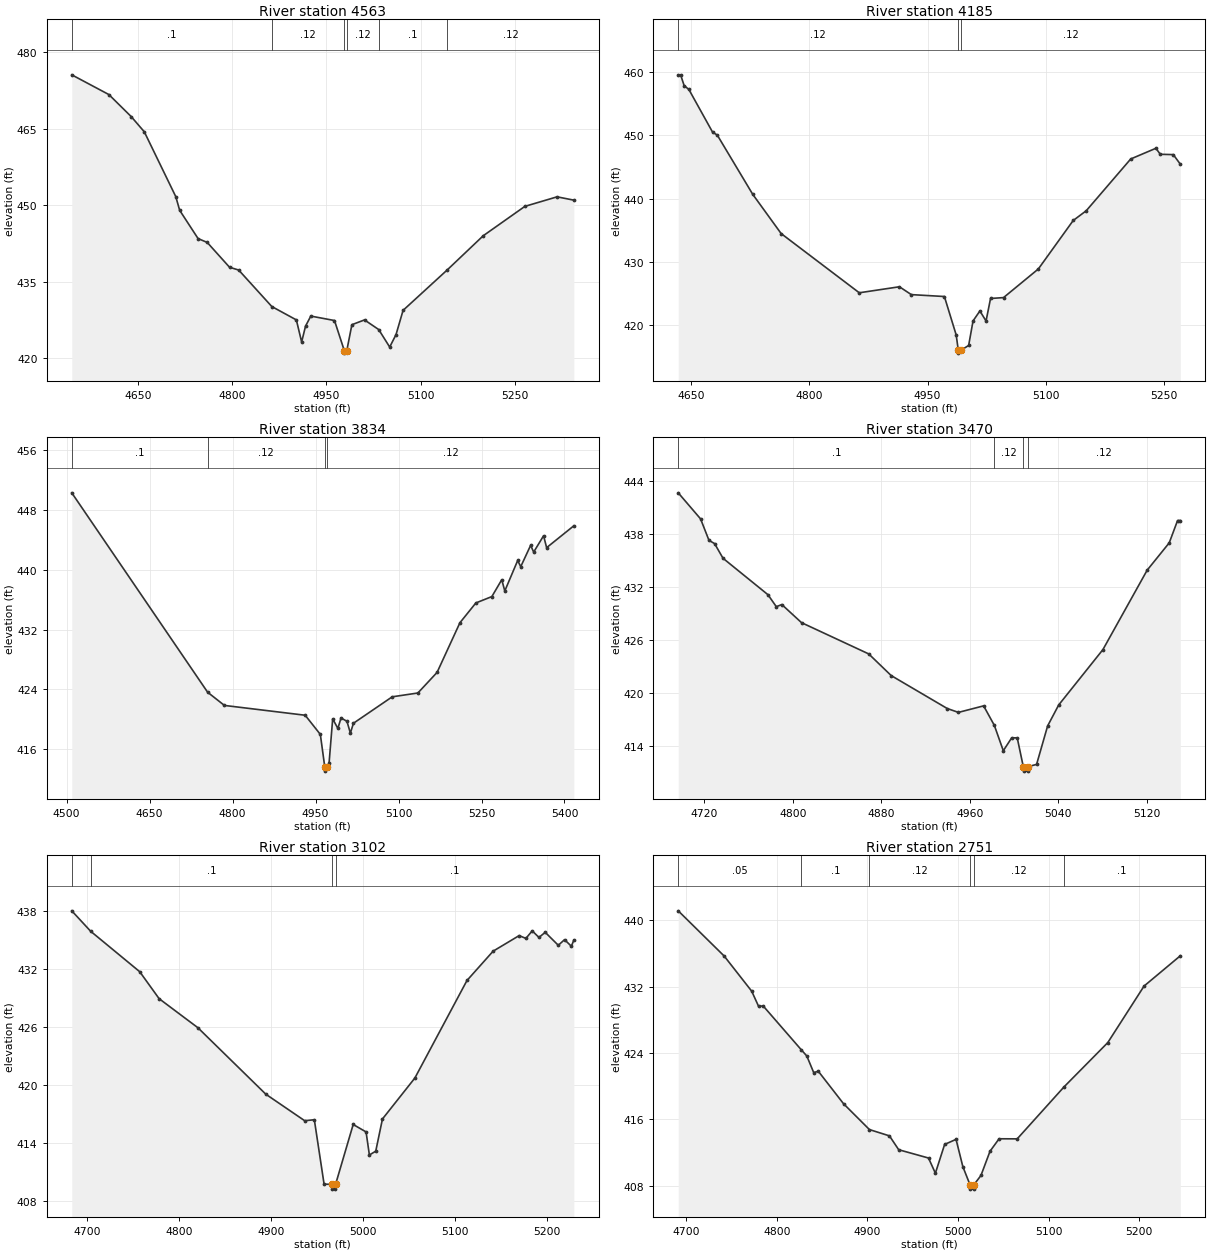
Type RM Length L Ch R = 1,4563,378,378,378
BEGIN DESCRIPTION:
Walnut31 11.0
END DESCRIPTION:
XS GIS Cut Line= 4
      2778653.55      6768327.11      2778332.63      6768564.46
      2778188.88      6768577.83      2777974.95      6768718.22
#Sta/Elev= 30
  4544.7  475.57  4603.8  471.70  4639.3  467.39  4660.2  464.40  4710.3  451.70
  4716.5  449.02  4745.8  443.48  4760.4  442.72  4795.9  437.86  4810.5  437.31
  4863.2  430.16  4902.3  427.54  4910.7  423.21  4916.9  426.32  4925.3  428.29
  4963.0  427.42  4978.6  421.53  4978.9  421.03  4982.6  421.53  4990.7  426.60
  5010.8  427.54  5033.4  425.65  5050.9  422.22  5061.0  424.67  5072.2  429.41
  5142.2  437.30  5199.8  444.03  5266.1  449.79  5317.4  451.66  5344.1  451.01
#Mann=6,-1,0
  4544.7     0.1       0  4863.2    0.12       0  4978.6    0.07       0
  4982.6    0.12       0  5033.4     0.1       0  5142.2    0.12       0
Bank Sta=4978.6,4982.6
Exp/Cntr=0.3,0.1

Type RM Length L Ch R = 1,4185,351,351,351
BEGIN DESCRIPTION:
Walnut31 10.0
END DESCRIPTION:
XS GIS Cut Line= 3
      2778326.00      6768161.00      2778026.00      6768361.00
      2777898.52      6768606.97
#Sta/Elev= 30
  4633.4  459.54  4636.4  459.54  4640.9  457.84  4646.9  457.23  4677.0  450.49
  4683.0  450.02  4728.0  440.67  4764.1  434.47  4863.3  425.12  4914.3  426.07
  4929.4  424.83  4971.4  424.53  4986.4  418.45  4989.0  416.09  4989.2  415.59
  4993.0  416.09  5002.2  416.80  5007.8  420.68  5016.5  422.25  5024.3  420.66
  5030.0  424.22  5046.5  424.36  5090.7  428.88  5135.0  436.54  5151.5  438.07
  5208.0  446.25  5240.0  447.94  5245.6  446.99  5262.1  446.94  5271.0  445.43
#Mann=3,-1,0
  4633.4    0.12       0  4989.0    0.07       0  4993.0    0.12       0
Bank Sta=4989,4993
Exp/Cntr=0.3,0.1

Type RM Length L Ch R = 1,3834,364,364,364
BEGIN DESCRIPTION:
Walnut31 9.0
END DESCRIPTION:
XS GIS Cut Line= 3
      2778205.63      6767915.88      2777776.00      6768161.00
      2777397.79      6768326.57
#Sta/Elev= 30
  4509.4  450.25  4755.0  423.63  4785.3  421.87  4931.3  420.56  4958.7  418.00
  4966.8  413.60  4967.0  413.10  4970.8  413.60  4974.5  414.19  4981.0  420.08
  4990.4  418.80  4996.1  420.20  5006.8  419.75  5013.0  418.17  5018.5  419.49
  5088.6  423.02  5135.0  423.53  5169.7  426.28  5211.0  432.91  5239.8  435.55
  5268.7  436.40  5286.6  438.65  5292.1  437.15  5315.4  441.22  5320.9  440.39
  5338.8  443.24  5344.3  442.34  5362.2  444.52  5367.7  442.93  5416.9  445.85
#Mann=4,-1,0
  4509.4     0.1       0  4755.0    0.12       0  4966.8    0.07       0
  4970.8    0.12       0
Bank Sta=4966.8,4970.8
Exp/Cntr=0.3,0.1

Type RM Length L Ch R = 1,3470,368,368,368
BEGIN DESCRIPTION:
Walnut31 8.0
END DESCRIPTION:
XS GIS Cut Line= 3
      2778125.97      6767761.01      2777826.00      6767811.00
      2777676.01      6767811.00
#Sta/Elev= 30
  4696.3  442.69  4716.5  439.74  4724.1  437.31  4729.2  436.94  4736.8  435.28
  4777.4  431.16  4785.0  429.80  4790.0  430.04  4807.8  427.99  4868.6  424.45
  4888.9  422.00  4939.6  418.27  4949.7  417.83  4972.5  418.57  4982.2  416.36
  4990.3  413.49  4997.9  414.95  5002.9  414.95  5008.4  411.68  5008.7  411.18
  5012.2  411.18  5012.4  411.68  5020.4  411.94  5030.4  416.30  5040.4  418.67
  5080.4  424.94  5120.4  433.93  5140.4  437.03  5147.9  439.55  5150.4  439.55
#Mann=4,-1,0
  4696.3     0.1       0  4982.2    0.12       0  5008.4    0.07       0
  5012.4    0.12       0
Bank Sta=5008.4,5012.4
Exp/Cntr=0.3,0.1

Type RM Length L Ch R = 1,3102,351,351,351
BEGIN DESCRIPTION:
Walnut31 7.0
END DESCRIPTION:
XS GIS Cut Line= 3
      2778026.01      6767411.00      2777726.00      6767511.00
      2777558.38      6767667.27
#Sta/Elev= 30
  4683.5  437.98  4704.0  435.87  4757.3  431.69  4778.4  428.90  4820.5  425.90
  4894.3  419.03  4936.5  416.29  4947.0  416.39  4957.6  409.73  4966.1  409.72
  4966.4  409.22  4969.9  409.22  4970.1  409.72  4989.2  415.90  5003.2  415.13
  5006.8  412.75  5013.7  413.14  5021.0  416.47  5056.2  420.70  5112.8  430.78
  5141.2  433.81  5169.5  435.42  5176.8  435.13  5183.7  435.91  5191.0  435.23
  5197.8  435.76  5212.0  434.42  5218.8  435.00  5226.2  434.32  5228.9  434.96
#Mann=4,-1,0
  4683.5    0.05       0  4704.0     0.1       0  4966.1    0.07       0
  4970.1     0.1       0
Bank Sta=4966.1,4970.1
Exp/Cntr=0.3,0.1

Type RM Length L Ch R = 1,2751,364,364,364
BEGIN DESCRIPTION:
Walnut31 6.0
END DESCRIPTION:
XS GIS Cut Line= 3
      2777975.97      6767161.01      2777676.00      6767211.00
      2777426.00      6767211.00
#Sta/Elev= 30
  4691.3  441.15  4742.0  435.70  4772.4  431.46  4780.0  429.63  4785.0  429.69
  4827.0  424.41  4833.2  423.65  4840.8  421.65  4845.9  421.81  4873.7  417.90
  4902.3  414.78  4924.4  414.02  4934.6  412.35  4967.5  411.35  4975.1  409.52
  4985.3  412.99  4997.9  413.60  5005.4  410.31  5013.4  408.10  5013.7  407.60
  5017.2  407.60  5017.4  408.10  5025.4  409.25  5035.4  412.17  5045.4  413.67
  5065.4  413.66  5117.2  419.94  5165.4  425.27  5205.4  432.08  5245.4  435.73
#Mann=6,-1,0
  4691.3    0.05       0  4827.0     0.1       0  4902.3    0.12       0
  5013.4    0.07       0  5017.4    0.12       0  5117.2     0.1       0
Bank Sta=5013.4,5017.4
Exp/Cntr=0.3,0.1

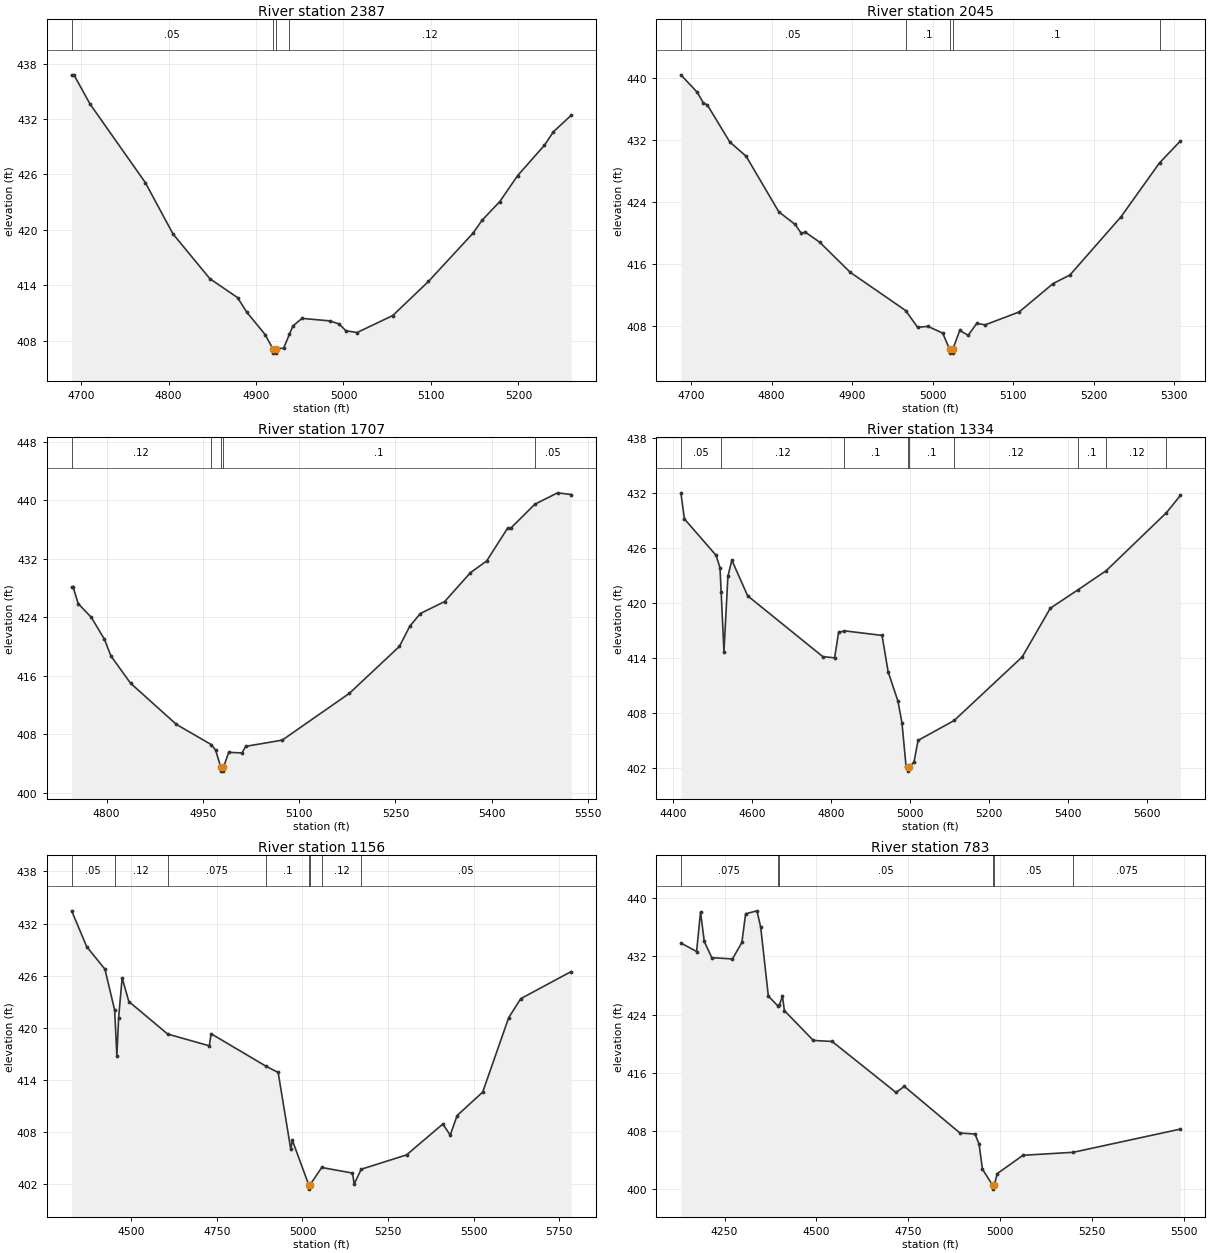
Type RM Length L Ch R = 1,2387,342,342,342
BEGIN DESCRIPTION:
Walnut31 5.0
END DESCRIPTION:
XS GIS Cut Line= 3
      2777925.99      6766961.00      2777626.00      6766861.00
      2777375.97      6766911.01
#Sta/Elev= 30
  4689.2  436.78  4691.8  436.78  4710.3  433.61  4773.5  425.11  4805.1  419.56
  4847.3  414.71  4878.9  412.67  4889.5  411.09  4910.5  408.66  4919.1  407.16
  4919.3  406.66  4922.8  406.66  4923.1  407.16  4931.6  407.19  4938.2  408.70
  4942.2  409.61  4952.7  410.42  4984.3  410.15  4994.9  409.82  5002.8  409.08
  5015.6  408.89  5056.4  410.73  5097.2  414.42  5148.2  419.65  5158.4  421.03
  5178.8  423.07  5199.2  425.88  5229.8  429.16  5240.0  430.61  5260.4  432.40
#Mann=4,-1,0
  4689.2    0.05       0  4919.1    0.07       0  4923.1    0.05       0
  4938.2    0.12       0
Bank Sta=4919.1,4923.1
Exp/Cntr=0.3,0.1

Type RM Length L Ch R = 1,2045,338,338,338
BEGIN DESCRIPTION:
Walnut31 4.0
END DESCRIPTION:
XS GIS Cut Line= 3
      2777975.99      6766511.00      2777676.00      6766561.00
      2777375.96      6766661.01
#Sta/Elev= 30
  4687.4  440.41  4707.7  438.16  4715.3  436.79  4720.3  436.52  4748.2  431.74
  4768.5  429.90  4809.0  422.74  4829.3  421.11  4836.9  419.97  4842.0  420.11
  4859.7  418.83  4897.8  414.93  4966.6  410.00  4981.4  407.84  4994.2  407.96
  5012.6  407.09  5021.1  405.01  5021.4  404.51  5024.9  404.51  5025.1  405.01
  5033.7  407.43  5044.2  406.81  5054.8  408.34  5065.3  408.16  5107.5  409.82
  5149.6  413.48  5170.7  414.60  5234.0  422.10  5281.8  429.05  5307.8  431.88
#Mann=5,-1,0
  4687.4    0.05       0  4966.6     0.1       0  5021.1    0.07       0
  5025.1     0.1       0  5281.8    0.12       0
Bank Sta=5021.1,5025.1
Exp/Cntr=0.3,0.1

Type RM Length L Ch R = 1,1707,373,373,373
BEGIN DESCRIPTION:
Walnut31 3.0
END DESCRIPTION:
XS GIS Cut Line= 3
      2777825.99      6766211.00      2777576.00      6766261.00
      2777075.67      6766414.86
#Sta/Elev= 30
  4745.5  428.07  4748.0  428.07  4755.7  425.85  4776.1  423.98  4796.5  421.00
  4806.7  418.70  4837.3  414.97  4908.7  409.34  4962.8  406.59  4969.8  405.83
  4978.0  403.45  4978.3  402.95  4981.8  402.95  4982.0  403.45  4990.2  405.52
  5010.9  405.44  5016.8  406.34  5073.7  407.19  5178.3  413.59  5256.2  420.00
  5272.5  422.78  5288.9  424.50  5326.8  426.14  5366.6  430.06  5392.2  431.69
  5424.9  436.18  5430.2  436.21  5467.1  439.43  5502.6  441.00  5523.9  440.77
#Mann=5,-1,0
  4745.5    0.12       0  4962.8     0.1       0  4978.0    0.07       0
  4982.0     0.1       0  5467.1    0.05       0
Bank Sta=4978,4982
Exp/Cntr=0.3,0.1

Type RM Length L Ch R = 1,1334,178,178,178
BEGIN DESCRIPTION:
Walnut31 2.0
END DESCRIPTION:
XS GIS Cut Line= 3
      2778004.99      6765956.87      2777480.15      6765936.82
      2776751.37      6766063.85
#Sta/Elev= 30
  4420.2  432.01  4429.2  429.16  4509.3  425.19  4519.3  423.83  4522.2  421.18
  4529.3  414.68  4539.3  422.91  4549.3  424.66  4589.3  420.77  4779.5  414.14
  4809.5  414.00  4819.5  416.77  4834.5  416.95  4929.6  416.45  4945.0  412.49
  4969.9  409.27  4980.1  406.90  4990.2  402.25  4995.1  402.14  4995.4  401.64
  4999.1  402.14  5010.5  402.62  5020.7  404.99  5112.4  407.17  5284.6  414.11
  5355.7  419.42  5425.5  421.42  5497.4  423.52  5649.9  429.85  5685.2  431.73
#Mann=9,-1,0
  4420.2    0.05       0  4522.2    0.12       0  4834.5     0.1       0
  4995.1    0.07       0  4999.1     0.1       0  5112.4    0.12       0
  5425.5     0.1       0  5497.4    0.12       0  5649.9    0.05       0
Bank Sta=4995.1,4999.1
Exp/Cntr=0.3,0.1

Type RM Length L Ch R = 1,1156,373,373,373
BEGIN DESCRIPTION:
Walnut31 1.0
END DESCRIPTION:
XS GIS Cut Line= 4
      2778028.38      6765950.18      2777416.63      6765786.38
      2777115.75      6765769.66      2776594.19      6765722.86
#Sta/Elev= 30
  4326.1  433.47  4370.0  429.35  4423.3  426.75  4451.6  422.05  4458.1  416.79
  4463.3  421.18  4473.5  425.76  4493.0  423.03  4606.5  419.28  4728.0  417.93
  4733.2  419.32  4894.8  415.55  4929.0  414.86  4965.6  406.06  4970.6  407.03
  5018.1  401.93  5018.4  401.43  5022.1  401.93  5056.1  403.92  5145.9  403.28
  5150.9  402.03  5171.4  403.72  5303.7  405.37  5409.8  408.93  5431.2  407.64
  5451.3  409.90  5526.0  412.60  5601.9  421.17  5637.2  423.36  5784.4  426.48
#Mann=8,-1,0
  4326.1    0.05       0  4451.6    0.12       0  4606.5   0.075       0
  4894.8     0.1       0  5018.1    0.07       0  5022.1     0.1       0
  5056.1    0.12       0  5171.4    0.05       0
Bank Sta=5018.1,5022.1
Exp/Cntr=0.3,0.1

Type RM Length L Ch R = 1,783,61,61,61
BEGIN DESCRIPTION:
Walnut31 0.5
END DESCRIPTION:
XS GIS Cut Line= 3
      2777978.21      6765736.22      2777189.30      6765562.39
      2776639.32      6765509.06
#Sta/Elev= 30
  4131.1  433.83  4173.9  432.66  4184.6  438.09  4194.8  434.04  4215.3  431.81
  4271.6  431.64  4297.2  433.91  4307.4  437.84  4338.2  438.25  4348.4  436.03
  4369.3  426.53  4394.5  425.22  4398.8  425.27  4407.8  426.49  4413.0  424.54
  4491.8  420.44  4543.0  420.30  4717.0  413.29  4739.5  414.13  4891.1  407.72
  4932.1  407.58  4943.1  406.21  4952.3  402.76  4980.4  400.51  4980.7  400.01
  4984.4  400.51  4992.5  402.14  5062.8  404.66  5199.4  405.07  5491.5  408.26
#Mann=6,-1,0
  4131.1   0.075       0  4394.5    0.12       0  4398.8    0.05       0
  4980.4    0.05       0  4984.4    0.05       0  5199.4   0.075       0
Bank Sta=4980.4,4984.4
Exp/Cntr=0.3,0.1

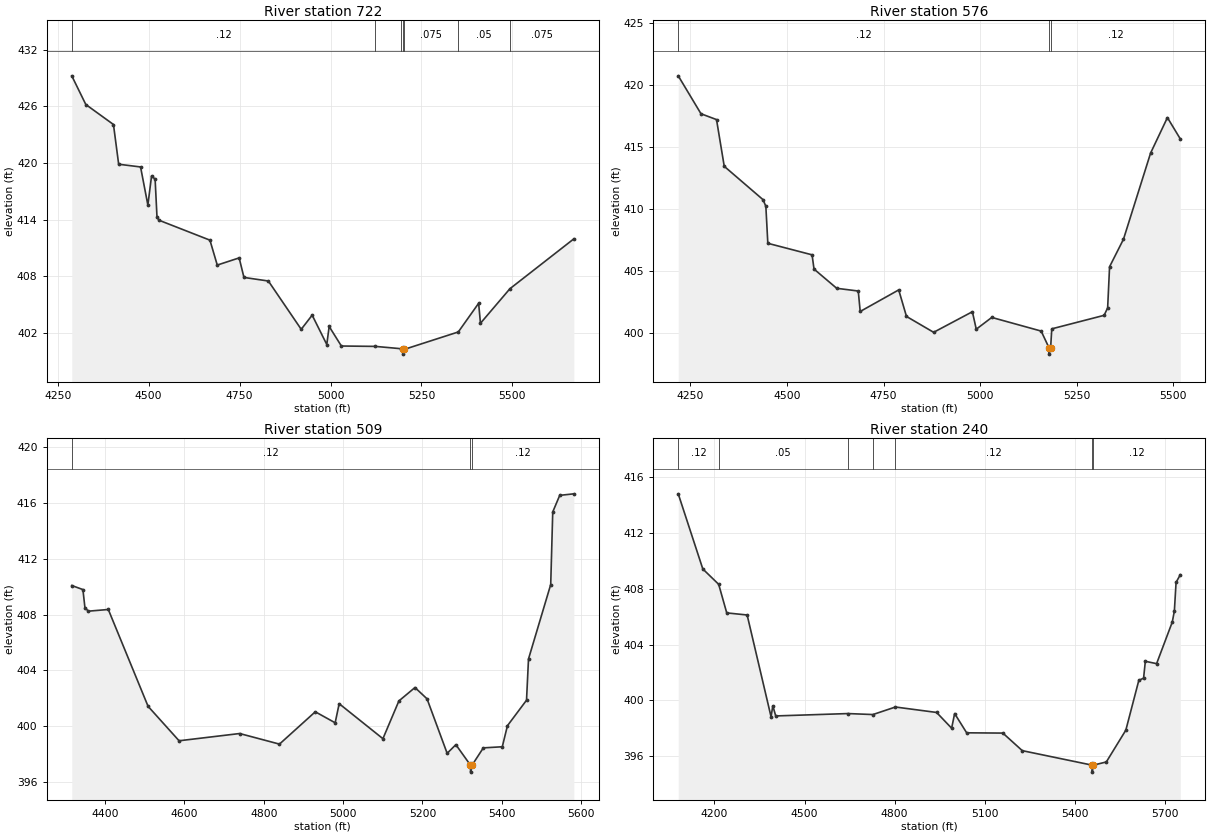
Type RM Length L Ch R = 1,722,146,146,146
BEGIN DESCRIPTION:
Walnut31 0.4
END DESCRIPTION:
XS GIS Cut Line= 3
      2777834.47      6765555.70      2776885.08      6765475.47
      2776460.71      6765425.35
#Sta/Elev= 30
  4288.7  429.23  4327.3  426.19  4403.3  424.07  4417.6  419.86  4477.8  419.57
  4497.9  415.53  4508.0  418.61  4517.8  418.28  4522.9  414.30  4528.0  413.93
  4668.5  411.81  4688.6  409.17  4748.8  409.93  4762.0  407.86  4829.1  407.48
  4919.4  402.36  4949.5  403.86  4989.7  400.75  4996.2  402.66  5029.8  400.59
  5123.1  400.55  5195.0  400.30  5198.4  400.23  5198.7  399.73  5202.4  400.23
  5351.2  402.08  5407.1  405.12  5412.1  403.00  5493.0  406.66  5668.8  411.95
#Mann=7,-1,0
  4288.7    0.12       0  5123.1    0.05       0  5195.0   0.075       0
  5198.4    0.07       0  5202.4   0.075       0  5351.2    0.05       0
  5493.0   0.075       0
Bank Sta=5198.4,5202.4
Exp/Cntr=0.3,0.1

Type RM Length L Ch R = 1,576,67,67,67
BEGIN DESCRIPTION:
Walnut31 0.2
END DESCRIPTION:
XS GIS Cut Line= 3
      2777904.70      6765415.30      2776955.29      6765335.07
      2776609.27      6765358.36
#Sta/Elev= 30
  4218.5  420.77  4277.4  417.71  4317.6  417.24  4337.6  413.47  4438.0  410.78
  4445.3  410.24  4450.4  407.26  4564.9  406.33  4570.0  405.18  4628.7  403.63
  4684.5  403.41  4689.5  401.76  4789.2  403.50  4809.3  401.36  4879.6  400.08
  4979.9  401.74  4989.9  400.33  5030.1  401.28  5157.9  400.18  5178.4  398.82
  5178.7  398.32  5182.4  398.82  5185.4  400.36  5320.9  401.45  5330.0  402.05
  5335.0  405.37  5371.0  407.59  5441.2  414.54  5484.7  417.40  5518.1  415.68
#Mann=3,-1,0
  4218.5    0.12       0  5178.4    0.07       0  5182.4    0.12       0
Bank Sta=5178.4,5182.4
Exp/Cntr=0.3,0.1

Type RM Length L Ch R = 1,509,269,269,269
BEGIN DESCRIPTION:
Walnut31 0.1
END DESCRIPTION:
XS GIS Cut Line= 3
      2777807.79      6765338.41      2776995.40      6765271.55
      2776550.87      6765345.08
#Sta/Elev= 30
  4315.9  410.08  4344.0  409.79  4349.1  408.49  4357.8  408.24  4408.0  408.36
  4508.3  401.41  4586.4  398.94  4739.1  399.46  4839.5  398.70  4929.8  401.02
  4979.9  400.23  4990.0  401.60  5100.3  399.09  5140.6  401.80  5181.1  402.76
  5211.5  401.95  5262.2  398.04  5284.2  398.66  5321.0  397.19  5321.3  396.69
  5325.0  397.19  5353.4  398.43  5401.2  398.51  5414.2  400.02  5462.3  401.85
  5467.3  404.81  5523.3  410.15  5528.4  415.36  5546.0  416.55  5581.6  416.66
#Mann=3,-1,0
  4315.9    0.12       0  5321.0    0.07       0  5325.0    0.12       0
Bank Sta=5321,5325
Exp/Cntr=0.3,0.1

Type RM Length L Ch R = 1,240,0,0,0
BEGIN DESCRIPTION:
Walnut31 0.05
END DESCRIPTION:
XS GIS Cut Line= 4
      2777954.04      6765346.51      2777408.70      6765017.17
      2776970.57      6765011.04      2776452.73      6765305.19
#Sta/Elev= 30
  4079.8  414.81  4161.6  409.42  4214.4  408.32  4241.2  406.27  4309.1  406.12
  4388.7  398.82  4394.5  399.61  4404.2  398.88  4644.4  399.05  4727.6  398.98
  4802.6  399.52  4939.6  399.13  4989.6  398.00  4999.6  399.05  5039.6  397.67
  5160.1  397.65  5224.7  396.39  5457.3  395.35  5457.6  394.85  5461.3  395.35
  5504.4  395.58  5569.3  397.86  5612.5  401.43  5628.4  401.59  5634.2  402.80
  5671.7  402.63  5723.8  405.61  5730.8  406.40  5736.5  408.46  5750.6  409.01
#Mann=7,-1,0
  4079.8    0.12       0  4214.4    0.05       0  4644.4   0.075       0
  4727.6    0.05       0  4802.6    0.12       0  5457.3    0.07       0
  5461.3    0.12       0
Bank Sta=5457.3,5461.3
Exp/Cntr=0.3,0.1

Chan Stop Cuts=-1