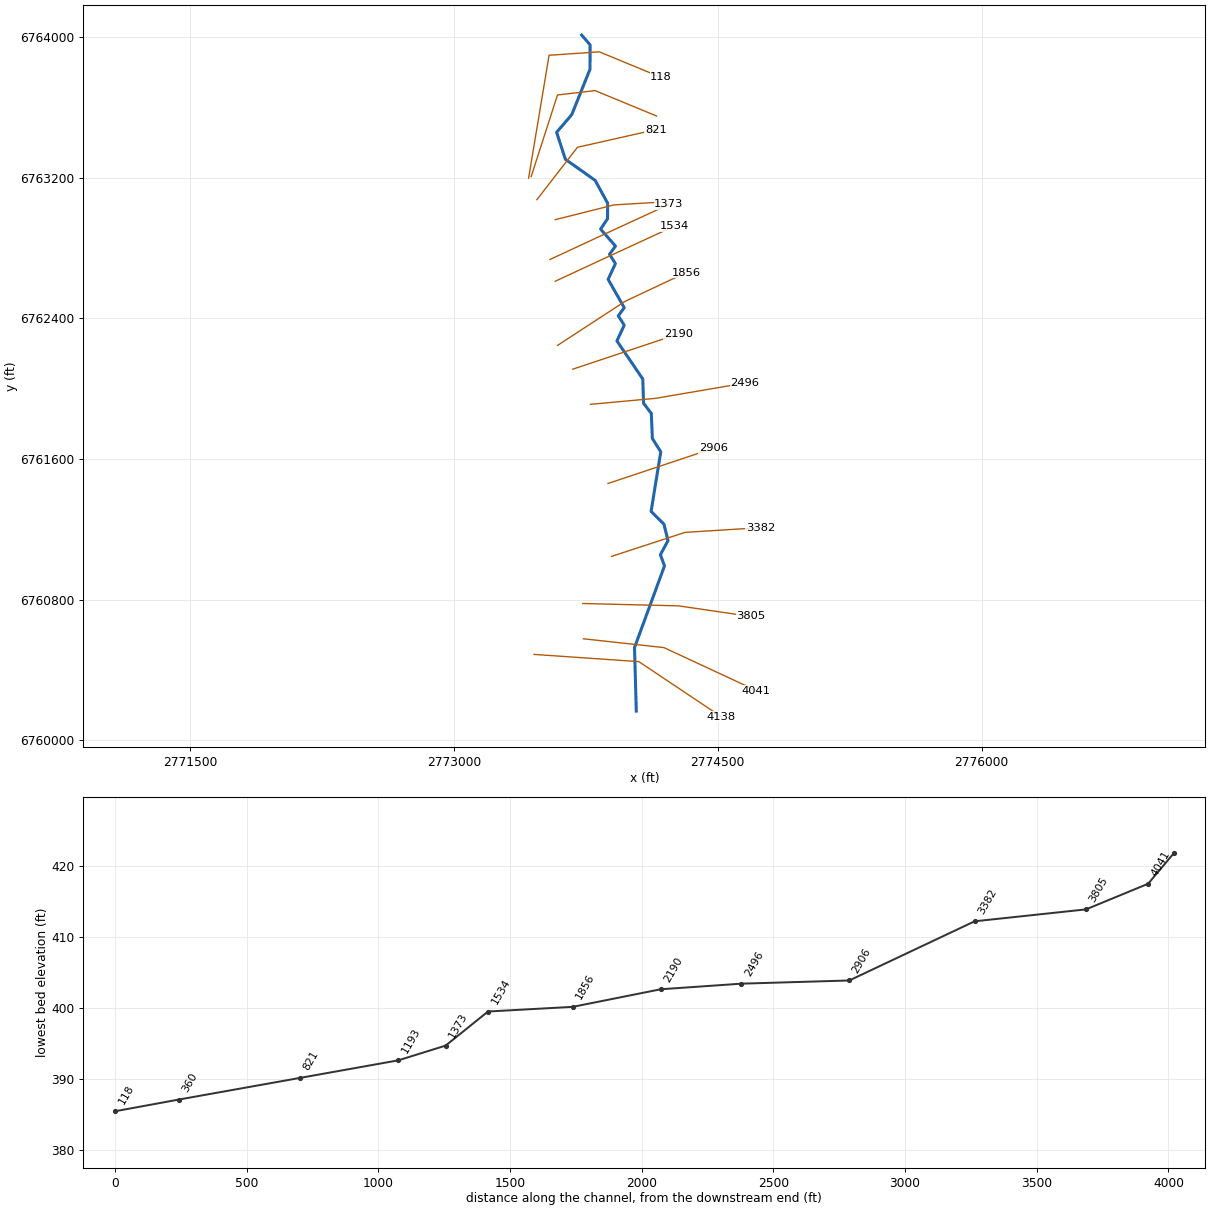
--- Walnut34.prj (project) ---

Proj Title=Walnut34 Base Level Engineering
Current Plan=p01
Default Exp/Contr=0.3,0.1
English Units
Geom File=g01
Flow File=f01
Plan File=p01
Y Axis Title=Elevation
X Axis Title(PF)=Main Channel Distance
X Axis Title(XS)=Station
BEGIN DESCRIPTION:
Walnut34
END DESCRIPTION:
DSS Export Rating Curves= 0
DSS Export Rating Curve Sorted= 0
DSS Export Volume Flow Curves= 0
DXF OffsetX= 0
DXF OffsetY= 0
DXF ScaleX= 1
DXF ScaleY= 10

--- Walnut34.p01 (plan) ---

Plan Title=Multiple Run
Program Version=4.10
Short Identifier=Multiple
Geom File=g01
Flow File=f01
Subcritical Flow
K Sum by GR= 0
Std Step Tol= 0.01
Critical Tol= 0.01
Num of Std Step Trials= 20
Max Error Tol= 0.3
Flow Tol Ratio= 0.001
Split Flow NTrial= 30
Split Flow Tol= 0.02
Split Flow Ratio= 0.02
Log Output Level= 0
Friction Slope Method= 1
Unsteady Friction Slope Method= 2
Unsteady Bridges Friction Slope Method= 1
Parabolic Critical Depth
Global Vel Dist= 1 , 1 , 1
Global Log Level= 0
CheckData=True
Encroach Param=-1 ,0,0, 0
BEGIN DESCRIPTION:
Multiple Run
END DESCRIPTION:
Computation Interval=1HOUR
Output Interval=1HOUR
Run HTab= 0
Run UNet= 0
Run PostProcess= 0
Run WQNet= 0
UNET Theta= 1
UNET Theta Warmup= 1
UNET ZTol= 0.02
UNET ZSATol= 0.05
UNET MxIter= 20
UNET MaxInSteps= 0
UNET DtIC= 0
UNET DtMin= 0
UNET MaxCRTS= 20
UNET WFStab= 2
UNET SFStab= 1
UNET WFX= 1
UNET SFX= 1
UNET DSS MLevel= 4
UNET DZMax Abort= 100
UNET Convert EG Bridges= 0
UNET Use Existing IB Tables=-1
UNET Froude Reduction=False
UNET Froude Limit= 1
UNET Froude Power= 10
UNET Time Slicing=0,0, 5
UNET Junction Losses=0
Instantaneous Interval=1HOUR
Write IC File= 0
Write IC File at Sim End=0
Echo Input=False
Echo Parameters=False
Echo Output=False
Write Detailed= 0
WQ AD Non Conservative
WQ ULTIMATE=-1
WQ Max Comp Step=1HOUR
WQ Output Interval=15MIN
WQ Output Selected Increments= 0
WQ Output face flow=0
WQ Output face velocity=0
WQ Output face area=0
WQ Output face dispersion=0
WQ Output cell volume=0
WQ Output cell surface area=0
WQ Output cell continuity=0
WQ Output cumulative cell continuity=0
WQ Output face conc=0
WQ Output face dconc_dx=0
WQ Output face courant=0
WQ Output face peclet=0
WQ Output face adv mass=0
WQ Output face disp mass=0
WQ Output cell mass=0
WQ Output cell source sink temp=0
WQ Output cell source sink nsm=0
WQ Output MaxMinRange=-1
WQ Daily Max Min Mean=-1
WQ Daily Range=0
WQ Daily Time=0
WQ Create Restart=0
WQ Fixed Restart=0
WQ System Summary=0
WQ Use Fixed Temperature=0
Sorting and Armoring Iterations= 10
XS Update Threshold= 0.02
Hydraulics Update Threshold= 0.02
Energy Slope Method= 1
Volume Change Method= 0
XS Weighting Method= 0
Number of US Weighted Cross Sections= 1
Number of DS Weighted Cross Sections= 1
Upstream XS Weight=0.25
Main XS Weight=0.5
Downstream XS Weight=0.25
Number of DS XS's Weighted with US Boundary= 1
Upstream Boundary Weight= 1
Weight of XSs Associated with US Boundary= 0
Number of US XS's Weighted with DS Boundary= 1
Downstream Boundary Weight= 0.5
Weight of XSs Associated with DS Boundary= 0.5
Sediment Output Level= 4
Mass or Volume Output= 0
Output Increment Type= 1
Profile and TS Output Increment= 10
XS Output Flag= 0
XS Output Increment= 10
Disregard all LS=0
Disregard all Conn=0
Disregard all Breaches=0
Disregard all Pumps=0

--- Walnut34.f01 (steady flow) ---

Flow Title=Multiple
Number of Profiles=7
Profile Names=10-year,25-year,50-year,1pct_min,100-year,1pct_plu,500-year
River Rch & RM= Walnut34,Reach-1,4138
     671     923    1134     693    1384    2761    2062
Boundary for River Rch & Prof#=Walnut34,Reach-1,1
Up Type=0
Dn Type=3
Dn Slope=0.005
Boundary for River Rch & Prof#=Walnut34,Reach-1,2
Up Type=0
Dn Type=3
Dn Slope=0.005
Boundary for River Rch & Prof#=Walnut34,Reach-1,3
Up Type=0
Dn Type=3
Dn Slope=0.005
Boundary for River Rch & Prof#=Walnut34,Reach-1,4
Up Type=0
Dn Type=3
Dn Slope=0.005
Boundary for River Rch & Prof#=Walnut34,Reach-1,5
Up Type=0
Dn Type=3
Dn Slope=0.005
Boundary for River Rch & Prof#=Walnut34,Reach-1,6
Up Type=0
Dn Type=3
Dn Slope=0.005
Boundary for River Rch & Prof#=Walnut34,Reach-1,7
Up Type=0
Dn Type=3
Dn Slope=0.005

--- Walnut34.g01 (geometry) ---

Geom Title=Existing Conditions

River Reach=Walnut34,Reach-1
Reach XY= 30
      2774036.80      6760166.70      2774026.77      6760527.75
      2774197.26      6760992.43      2774173.86      6761055.95
      2774217.32      6761136.18      2774193.92      6761229.79
      2774121.03      6761302.26      2774175.95      6761640.96
      2774128.27      6761716.94      2774122.21      6761859.43
      2774078.27      6761916.94      2774073.75      6762055.07
      2773926.65      6762271.64      2773968.19      6762361.09
      2773934.55      6762414.33      2773968.25      6762460.91
      2773876.80      6762621.70      2773918.19      6762711.09
      2773884.56      6762764.34      2773918.44      6762811.00
      2773833.83      6762907.58      2773873.63      6762966.89
      2773873.85      6763055.03      2773803.01      6763184.52
      2773633.74      6763304.55      2773583.88      6763457.78
      2773670.14      6763558.70      2773773.75      6763816.94
      2773774.12      6763955.21      2773726.00      6764011.00

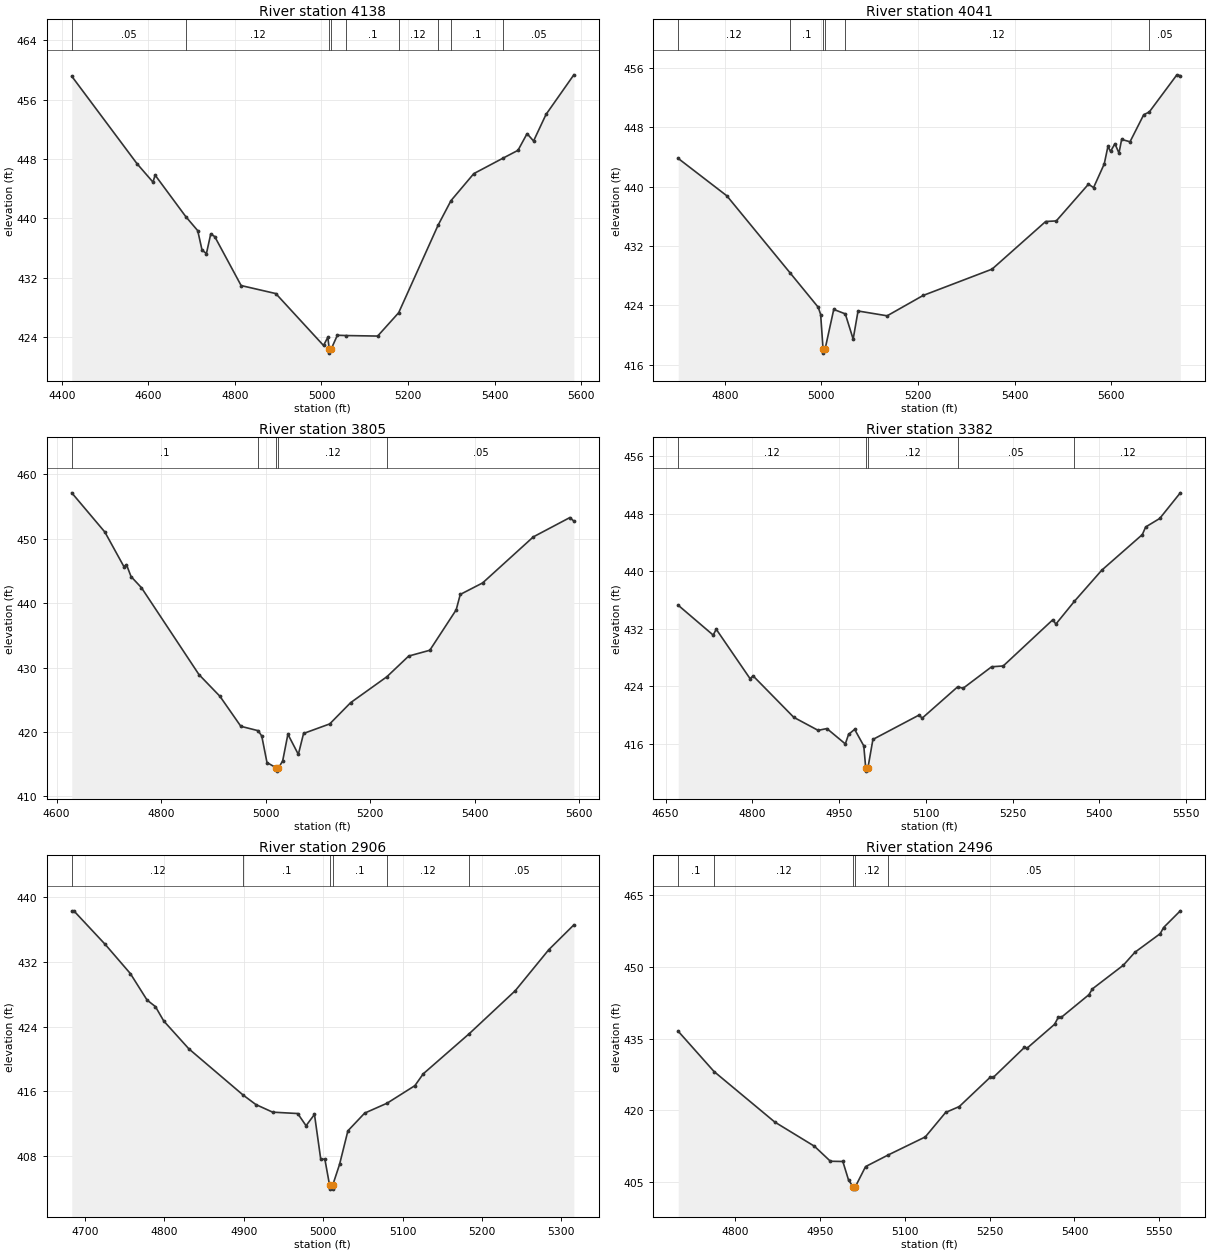
Type RM Length L Ch R = 1,4138,97,97,97
BEGIN DESCRIPTION:
Walnut34 11.0
END DESCRIPTION:
XS GIS Cut Line= 3
      2773455.57      6760489.03      2774051.52      6760447.93
      2774519.46      6760134.99
#Sta/Elev= 30
  4423.0  459.16  4573.8  447.37  4610.6  444.89  4615.6  445.83  4686.4  440.24
  4714.1  438.34  4724.1  435.71  4734.2  435.26  4744.2  437.91  4753.4  437.54
  4814.4  430.94  4894.5  429.86  5004.8  422.86  5014.8  423.97  5018.1  422.33
  5018.4  421.83  5022.1  422.33  5036.8  424.24  5057.5  424.20  5129.9  424.13
  5178.5  427.28  5269.5  439.07  5299.4  442.39  5352.1  446.03  5420.4  448.14
  5454.2  449.17  5475.2  451.42  5490.2  450.43  5519.0  454.01  5583.3  459.35
#Mann=9,-1,0
  4423.0    0.05       0  4686.4    0.12       0  5018.1    0.07       0
  5022.1    0.12       0  5057.5     0.1       0  5178.5    0.12       0
  5269.5    0.05       0  5299.4     0.1       0  5420.4    0.05       0
Bank Sta=5018.1,5022.1
Exp/Cntr=0.3,0.1

Type RM Length L Ch R = 1,4041,236,236,236
BEGIN DESCRIPTION:
Walnut34 10.0
END DESCRIPTION:
XS GIS Cut Line= 3
      2773735.92      6760577.89      2774193.92      6760527.75
      2774718.82      6760283.69
#Sta/Elev= 30
  4703.6  443.79  4804.3  438.75  4935.4  428.35  4993.5  423.73  4998.5  422.75
  5003.5  418.05  5003.7  417.55  5007.5  418.05  5025.6  423.44  5049.5  422.84
  5065.8  419.44  5075.9  423.23  5136.2  422.58  5210.6  425.32  5353.4  428.87
  5464.4  435.29  5486.4  435.37  5553.0  440.32  5563.6  439.86  5585.7  443.05
  5593.3  445.40  5598.8  444.74  5607.8  445.78  5616.2  444.51  5621.7  446.35
  5639.1  446.04  5667.5  449.69  5678.8  450.04  5736.1  455.06  5743.2  454.95
#Mann=6,-1,0
  4703.6    0.12       0  4935.4     0.1       0  5003.5    0.07       0
  5007.5     0.1       0  5049.5    0.12       0  5678.8    0.05       0
Bank Sta=5003.5,5007.5
Exp/Cntr=0.3,0.1

Type RM Length L Ch R = 1,3805,423,423,423
BEGIN DESCRIPTION:
Walnut34 9.0
END DESCRIPTION:
XS GIS Cut Line= 3
      2773732.63      6760778.48      2774277.50      6760765.11
      2774688.68      6760704.93
#Sta/Elev= 30
  4629.0  457.15  4692.4  451.05  4728.7  445.70  4733.7  445.99  4742.4  444.15
  4762.4  442.41  4872.4  428.92  4912.5  425.55  4952.5  420.89  4985.6  420.21
  4992.5  419.38  5002.5  415.26  5020.5  414.43  5020.7  413.93  5024.5  414.43
  5032.5  415.51  5042.5  419.66  5062.5  416.53  5072.5  419.78  5122.5  421.26
  5162.5  424.56  5231.9  428.59  5273.6  431.80  5314.0  432.70  5364.5  438.98
  5372.3  441.37  5415.1  443.16  5512.1  450.31  5582.0  453.31  5589.6  452.76
#Mann=5,-1,0
  4629.0     0.1       0  4985.6    0.12       0  5020.5    0.07       0
  5024.5    0.12       0  5231.9    0.05       0
Bank Sta=5020.5,5024.5
Exp/Cntr=0.3,0.1

Type RM Length L Ch R = 1,3382,476,476,476
BEGIN DESCRIPTION:
Walnut34 8.0
END DESCRIPTION:
XS GIS Cut Line= 3
      2773896.02      6761046.45      2774314.27      6761182.99
      2774741.57      6761209.69
#Sta/Elev= 30
  4671.9  435.28  4732.3  431.14  4737.6  431.95  4796.1  425.09  4801.4  425.47
  4871.7  419.72  4913.8  417.91  4928.9  418.16  4960.8  416.03  4966.4  417.35
  4976.9  418.05  4992.7  415.76  4996.0  412.75  4996.2  412.25  5000.0  412.75
  5008.5  416.65  5088.4  420.04  5093.6  419.60  5155.1  423.96  5164.4  423.75
  5213.8  426.74  5233.8  426.85  5319.7  433.28  5324.8  432.66  5357.0  435.84
  5404.2  440.15  5474.3  445.09  5480.1  446.15  5504.4  447.33  5540.0  450.89
#Mann=5,-1,0
  4671.9    0.12       0  4996.0    0.07       0  5000.0    0.12       0
  5155.1    0.05       0  5357.0    0.12       0
Bank Sta=4996,5000
Exp/Cntr=0.3,0.1

Type RM Length L Ch R = 1,2906,410,410,410
BEGIN DESCRIPTION:
Walnut34 7.0
END DESCRIPTION:
XS GIS Cut Line= 3
      2773876.02      6761461.01      2774176.00      6761561.00
      2774475.97      6761660.99
#Sta/Elev= 30
  4683.3  438.32  4685.9  438.32  4725.4  434.17  4757.1  430.56  4778.1  427.29
  4788.7  426.47  4799.2  424.69  4830.8  421.25  4899.2  415.53  4915.2  414.36
  4936.3  413.42  4967.9  413.25  4978.4  411.74  4989.0  413.14  4996.9  407.60
  5002.1  407.60  5008.0  404.40  5008.3  403.90  5011.8  403.90  5012.0  404.40
  5020.6  406.96  5031.1  411.11  5052.2  413.30  5080.5  414.53  5115.5  416.70
  5126.0  418.16  5184.0  423.13  5241.9  428.44  5284.1  433.51  5315.7  436.58
#Mann=6,-1,0
  4683.3    0.12       0  4899.2     0.1       0  5008.0    0.07       0
  5012.0     0.1       0  5080.5    0.12       0  5184.0    0.05       0
Bank Sta=5008,5012
Exp/Cntr=0.3,0.1

Type RM Length L Ch R = 1,2496,306,306,306
BEGIN DESCRIPTION:
Walnut34 6.0
END DESCRIPTION:
XS GIS Cut Line= 3
      2773776.01      6761911.00      2774147.12      6761945.20
      2774655.26      6762032.12
#Sta/Elev= 30
  4699.0  436.52  4762.3  428.09  4869.7  417.51  4940.0  412.43  4968.2  409.29
  4990.2  409.24  5000.3  405.35  5008.3  403.95  5008.6  403.45  5012.1  403.45
  5012.3  403.95  5030.4  408.17  5070.0  410.58  5136.1  414.39  5172.0  419.51
  5196.2  420.75  5251.2  426.92  5256.3  426.85  5311.3  433.12  5316.4  433.01
  5364.8  437.98  5371.4  439.46  5376.5  439.42  5425.6  444.19  5431.5  445.38
  5486.5  450.37  5506.8  453.06  5551.7  456.97  5557.5  458.24  5587.2  461.75
#Mann=5,-1,0
  4699.0     0.1       0  4762.3    0.12       0  5008.3    0.07       0
  5012.3    0.12       0  5070.0    0.05       0
Bank Sta=5008.3,5012.3
Exp/Cntr=0.3,0.1

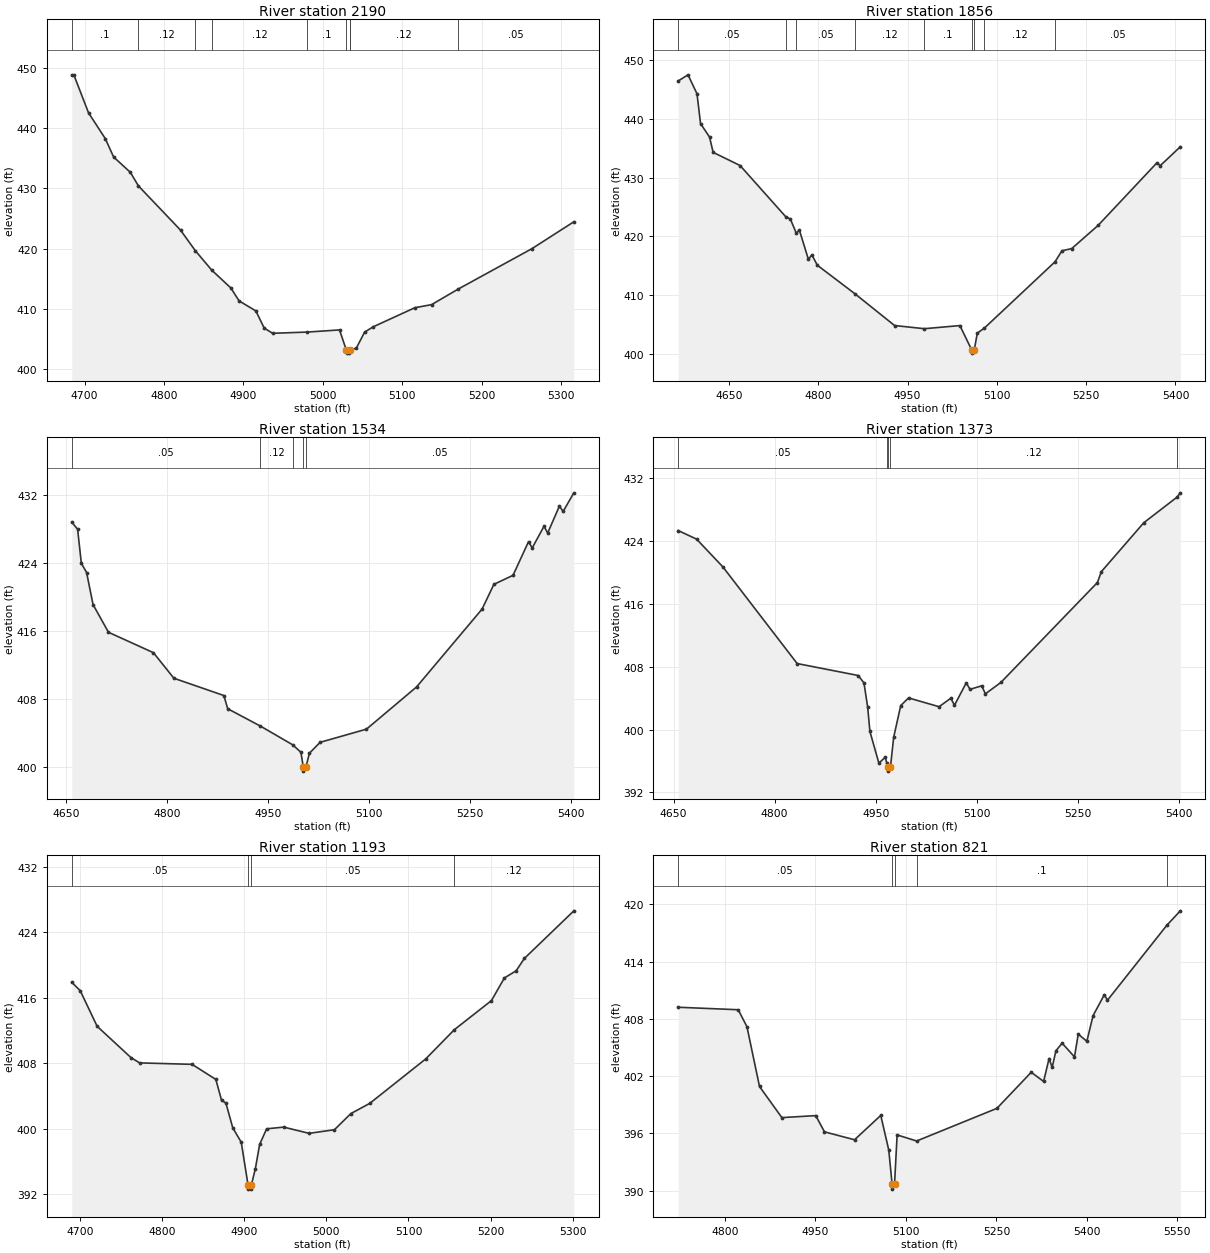
Type RM Length L Ch R = 1,2190,334,334,334
BEGIN DESCRIPTION:
Walnut34 5.0
END DESCRIPTION:
XS GIS Cut Line= 3
      2773675.99      6762111.00      2773976.00      6762211.00
      2774276.03      6762311.01
#Sta/Elev= 30
  4683.8  448.81  4686.4  448.81  4704.9  442.51  4726.0  438.24  4736.5  435.19
  4757.6  432.64  4767.7  430.40  4820.8  423.06  4839.5  419.64  4860.2  416.41
  4884.1  413.48  4894.6  411.32  4915.7  409.66  4926.2  406.82  4936.8  405.95
  4980.4  406.15  5021.1  406.51  5029.7  403.16  5029.9  402.66  5033.4  402.66
  5033.7  403.16  5034.2  403.18  5042.2  403.47  5052.7  406.14  5063.3  407.01
  5116.0  410.19  5137.1  410.70  5170.6  413.28  5263.6  419.99  5316.3  424.44
#Mann=9,-1,0
  4683.8     0.1       0  4767.7    0.12       0  4839.5    0.05       0
  4860.2    0.12       0  4980.4     0.1       0  5029.7    0.07       0
  5033.7     0.1       0  5034.2    0.12       0  5170.6    0.05       0
Bank Sta=5029.7,5033.7
Exp/Cntr=0.3,0.1

Type RM Length L Ch R = 1,1856,322,322,322
BEGIN DESCRIPTION:
Walnut34 4.0
END DESCRIPTION:
XS GIS Cut Line= 3
      2773588.79      6762246.06      2773973.28      6762496.81
      2774320.99      6762660.63
#Sta/Elev= 30
  4564.7  446.42  4581.1  447.46  4596.2  444.24  4602.2  439.17  4617.3  436.89
  4623.3  434.29  4668.6  432.05  4745.4  423.34  4753.0  422.97  4763.2  420.51
  4768.1  421.12  4783.3  416.13  4789.2  416.86  4798.4  415.11  4861.7  410.25
  4928.1  404.87  4978.1  404.33  5037.8  404.86  5057.9  400.68  5058.2  400.18
  5061.9  400.68  5067.1  403.58  5078.8  404.42  5197.6  415.69  5209.3  417.57
  5225.7  417.94  5269.9  421.87  5368.8  432.51  5374.4  432.03  5408.1  435.24
#Mann=9,-1,0
  4564.7    0.05       0  4745.4    0.12       0  4763.2    0.05       0
  4861.7    0.12       0  4978.1     0.1       0  5057.9    0.07       0
  5061.9     0.1       0  5078.8    0.12       0  5197.6    0.05       0
Bank Sta=5057.9,5061.9
Exp/Cntr=0.3,0.1

Type RM Length L Ch R = 1,1534,161,161,161
BEGIN DESCRIPTION:
Walnut34 3.0
END DESCRIPTION:
XS GIS Cut Line= 3
      2773576.01      6762611.00      2773913.10      6762767.60
      2774252.51      6762923.99
#Sta/Elev= 30
  4658.5  428.78  4667.2  427.92  4672.7  423.93  4680.5  422.85  4690.1  419.08
  4713.0  415.83  4779.8  413.43  4810.1  410.43  4884.3  408.40  4890.0  406.85
  4938.6  404.81  4986.3  402.62  4998.7  401.74  5002.2  400.02  5002.5  399.52
  5006.2  400.02  5011.3  401.62  5027.1  402.90  5096.0  404.45  5170.4  409.41
  5267.7  418.56  5285.2  421.46  5313.6  422.52  5336.6  426.47  5342.1  425.74
  5359.6  428.28  5365.1  427.49  5382.5  430.66  5388.0  430.02  5403.9  432.21
#Mann=5,-1,0
  4658.5    0.05       0  4938.6    0.12       0  4986.3    0.05       0
  5002.2    0.03       0  5006.2    0.05       0
Bank Sta=5002.2,5006.2
Exp/Cntr=0.3,0.1

Type RM Length L Ch R = 1,1373,180,180,180
BEGIN DESCRIPTION:
Walnut34 2.7
END DESCRIPTION:
XS GIS Cut Line= 3
      2773545.87      6762734.67      2773883.02      6762891.29
      2774222.47      6763047.70
#Sta/Elev= 30
  4656.9  425.30  4684.2  424.21  4723.2  420.68  4833.5  408.39  4924.2  406.87
  4932.7  405.92  4938.2  402.84  4941.5  399.76  4954.8  395.73  4964.4  396.48
  4966.6  395.70  4968.0  395.21  4968.2  394.71  4972.0  395.21  4976.8  399.02
  4987.3  403.05  4998.9  404.02  5044.2  402.90  5061.6  403.98  5067.1  403.09
  5084.6  405.94  5090.1  405.11  5107.5  405.56  5113.0  404.54  5136.0  405.99
  5279.3  418.69  5285.2  420.08  5348.1  426.29  5397.8  429.57  5402.4  430.10
#Mann=5,-1,0
  4656.9    0.05       0  4966.6    0.12       0  4968.0    0.07       0
  4972.0    0.12       0  5397.8    0.05       0
Bank Sta=4968,4972
Exp/Cntr=0.3,0.1

Type RM Length L Ch R = 1,1193,372,372,372
BEGIN DESCRIPTION:
Walnut34 2.0
END DESCRIPTION:
XS GIS Cut Line= 3
      2773576.04      6762961.01      2773909.76      6763045.07
      2774176.04      6763061.00
#Sta/Elev= 30
  4690.3  417.88  4700.6  416.85  4721.2  412.50  4762.4  408.68  4772.8  408.04
  4836.7  407.86  4865.6  406.02  4872.6  403.45  4877.8  403.15  4886.2  400.11
  4896.5  398.36  4904.8  393.13  4905.1  392.63  4908.6  392.63  4908.8  393.13
  4913.7  395.13  4918.9  398.09  4927.4  399.99  4948.1  400.20  4979.0  399.44
  5009.9  399.88  5029.9  401.85  5052.9  403.10  5120.8  408.51  5155.9  412.10
  5201.0  415.65  5216.7  418.41  5231.0  419.28  5241.0  420.79  5301.2  426.60
#Mann=4,-1,0
  4690.3    0.05       0  4904.8    0.07       0  4908.8    0.05       0
  5155.9    0.12       0
Bank Sta=4904.8,4908.8
Exp/Cntr=0.3,0.1

Type RM Length L Ch R = 1,821,461,461,461
BEGIN DESCRIPTION:
Walnut34 1.0
END DESCRIPTION:
XS GIS Cut Line= 3
      2773471.85      6763075.20      2773702.49      6763372.69
      2774147.09      6763472.98
#Sta/Elev= 30
  4722.6  409.21  4822.0  408.95  4836.5  407.17  4857.3  400.91  4894.4  397.65
  4950.5  397.86  4965.0  396.16  5014.8  395.33  5058.3  397.88  5071.6  394.24
  5077.1  390.66  5077.3  390.16  5081.1  390.66  5085.4  395.84  5117.7  395.20
  5250.8  398.62  5307.7  402.40  5328.2  401.44  5337.3  403.84  5342.4  402.91
  5348.7  404.66  5358.9  405.45  5379.4  404.01  5385.6  406.39  5399.9  405.65
  5410.2  408.33  5428.9  410.53  5434.0  409.94  5532.5  417.80  5554.8  419.31
#Mann=5,-1,0
  4722.6    0.05       0  5077.1    0.04       0  5081.1    0.05       0
  5117.7     0.1       0  5532.5    0.12       0
Bank Sta=5077.1,5081.1
Exp/Cntr=0.3,0.1

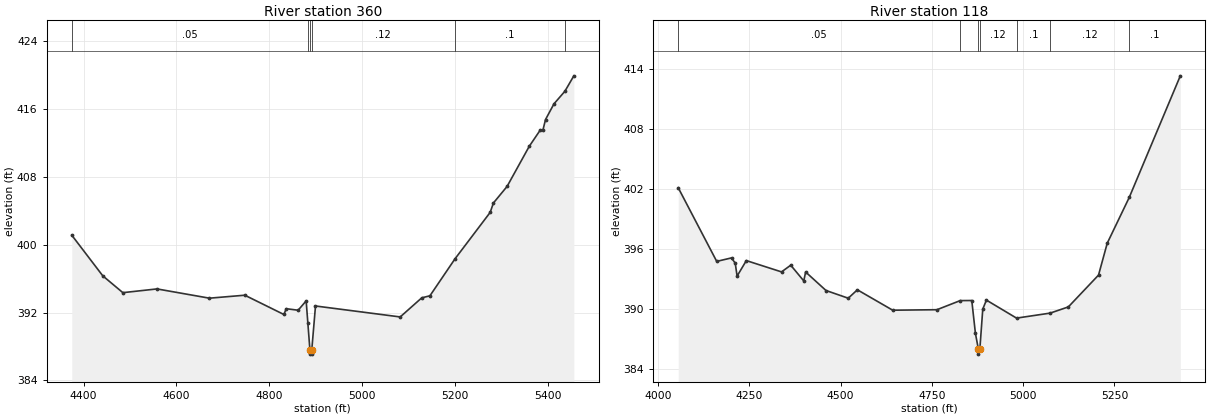
Type RM Length L Ch R = 1,360,242,242,242
BEGIN DESCRIPTION:
Walnut34 0.5
END DESCRIPTION:
XS GIS Cut Line= 4
      2773439.23      6763206.35      2773588.83      6763670.22
      2773802.63      6763694.98      2774152.42      6763550.45
#Sta/Elev= 30
  4374.5  401.11  4441.3  396.32  4484.5  394.34  4558.0  394.78  4670.9  393.69
  4747.1  394.04  4831.2  391.77  4836.4  392.45  4861.9  392.27  4879.2  393.37
  4882.9  390.73  4887.3  387.60  4887.5  387.10  4891.0  387.10  4891.3  387.60
  4899.3  392.77  5081.7  391.48  5128.1  393.73  5145.7  393.97  5199.5  398.31
  5275.5  403.80  5282.4  404.90  5311.8  406.85  5359.6  411.58  5383.5  413.51
  5388.9  413.46  5394.6  414.73  5412.8  416.58  5436.3  418.06  5455.6  419.88
#Mann=6,-1,0
  4374.5    0.05       0  4882.9    0.12       0  4887.3    0.07       0
  4891.3    0.12       0  5199.5     0.1       0  5436.3    0.12       0
Bank Sta=4887.3,4891.3
Exp/Cntr=0.3,0.1

Type RM Length L Ch R = 1,118,0,0,0
BEGIN DESCRIPTION:
Walnut34 0.3
END DESCRIPTION:
XS GIS Cut Line= 4
      2773424.55      6763197.05      2773540.81      6763895.95
      2773826.68      6763915.48      2774177.84      6763770.38
#Sta/Elev= 30
  4055.3  402.08  4160.7  394.72  4201.2  395.07  4211.4  394.54  4216.5  393.25
  4241.8  394.80  4338.2  393.67  4363.4  394.34  4399.1  392.77  4404.2  393.66
  4460.0  391.81  4520.9  391.04  4545.9  391.88  4642.7  389.84  4763.8  389.89
  4827.5  390.80  4859.2  390.81  4869.2  387.52  4877.3  385.95  4877.5  385.45
  4881.3  385.95  4889.3  389.95  4899.3  390.85  4981.8  389.05  5073.8  389.55
  5123.7  390.17  5206.3  393.35  5230.2  396.54  5290.4  401.11  5430.3  413.27
#Mann=7,-1,0
  4055.3    0.05       0  4827.5    0.12       0  4877.3    0.07       0
  4881.3    0.12       0  4981.8     0.1       0  5073.8    0.12       0
  5290.4     0.1       0
Bank Sta=4877.3,4881.3
Exp/Cntr=0.3,0.1

Chan Stop Cuts=-1