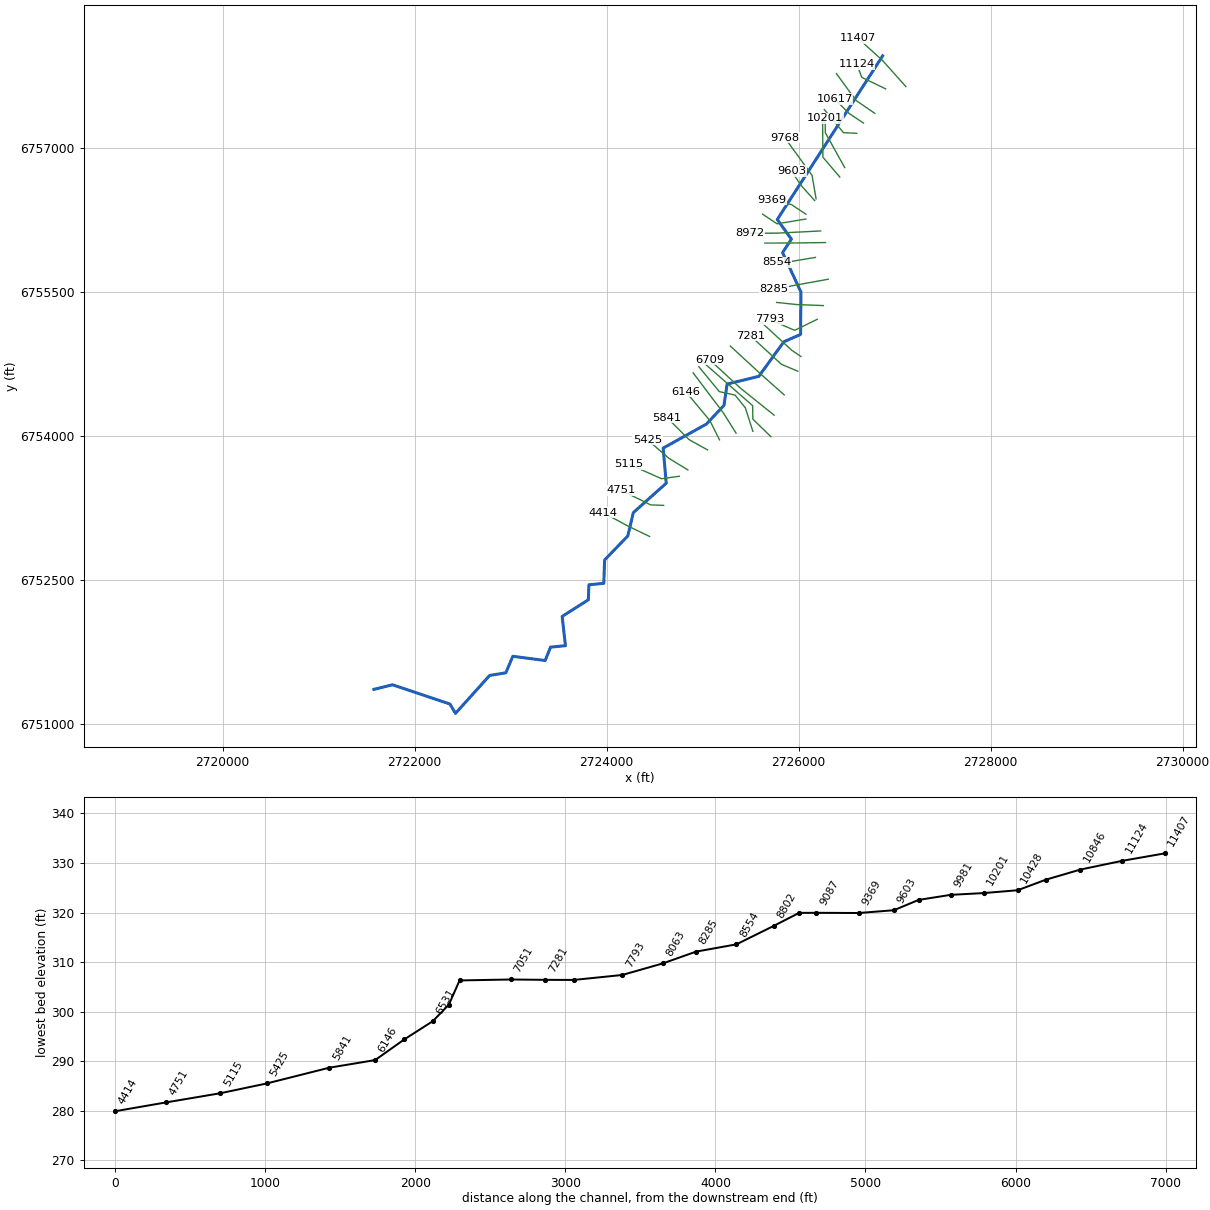
--- Walnut36.prj (project) ---

Proj Title=Walnut36 Base Level Engineering
Current Plan=p01
Default Exp/Contr=0.3,0.1
English Units
Geom File=g01
Flow File=f01
Plan File=p01
Y Axis Title=Elevation
X Axis Title(PF)=Main Channel Distance
X Axis Title(XS)=Station
BEGIN DESCRIPTION:
Walnut36
END DESCRIPTION:
DSS Export Rating Curves= 0
DSS Export Rating Curve Sorted= 0
DSS Export Volume Flow Curves= 0
DXF OffsetX= 0
DXF OffsetY= 0
DXF ScaleX= 1
DXF ScaleY= 10

--- Walnut36.p01 (plan) ---

Plan Title=Multiple Run
Program Version=4.10
Short Identifier=Multiple
Geom File=g01
Flow File=f01
Subcritical Flow
K Sum by GR= 0
Std Step Tol= 0.01
Critical Tol= 0.01
Num of Std Step Trials= 20
Max Error Tol= 0.3
Flow Tol Ratio= 0.001
Split Flow NTrial= 30
Split Flow Tol= 0.02
Split Flow Ratio= 0.02
Log Output Level= 0
Friction Slope Method= 1
Unsteady Friction Slope Method= 2
Unsteady Bridges Friction Slope Method= 1
Parabolic Critical Depth
Global Vel Dist= 1 , 1 , 1
Global Log Level= 0
CheckData=True
Encroach Param=-1 ,0,0, 0
BEGIN DESCRIPTION:
Multiple Run
END DESCRIPTION:
Computation Interval=1HOUR
Output Interval=1HOUR
Run HTab= 0
Run UNet= 0
Run PostProcess= 0
Run WQNet= 0
UNET Theta= 1
UNET Theta Warmup= 1
UNET ZTol= 0.02
UNET ZSATol= 0.05
UNET MxIter= 20
UNET MaxInSteps= 0
UNET DtIC= 0
UNET DtMin= 0
UNET MaxCRTS= 20
UNET WFStab= 2
UNET SFStab= 1
UNET WFX= 1
UNET SFX= 1
UNET DSS MLevel= 4
UNET DZMax Abort= 100
UNET Convert EG Bridges= 0
UNET Use Existing IB Tables=-1
UNET Froude Reduction=False
UNET Froude Limit= 1
UNET Froude Power= 10
UNET Time Slicing=0,0, 5
UNET Junction Losses=0
Instantaneous Interval=1HOUR
Write IC File= 0
Write IC File at Sim End=0
Echo Input=False
Echo Parameters=False
Echo Output=False
Write Detailed= 0
WQ AD Non Conservative
WQ ULTIMATE=-1
WQ Max Comp Step=1HOUR
WQ Output Interval=15MIN
WQ Output Selected Increments= 0
WQ Output face flow=0
WQ Output face velocity=0
WQ Output face area=0
WQ Output face dispersion=0
WQ Output cell volume=0
WQ Output cell surface area=0
WQ Output cell continuity=0
WQ Output cumulative cell continuity=0
WQ Output face conc=0
WQ Output face dconc_dx=0
WQ Output face courant=0
WQ Output face peclet=0
WQ Output face adv mass=0
WQ Output face disp mass=0
WQ Output cell mass=0
WQ Output cell source sink temp=0
WQ Output cell source sink nsm=0
WQ Output MaxMinRange=-1
WQ Daily Max Min Mean=-1
WQ Daily Range=0
WQ Daily Time=0
WQ Create Restart=0
WQ Fixed Restart=0
WQ System Summary=0
WQ Use Fixed Temperature=0
Sorting and Armoring Iterations= 10
XS Update Threshold= 0.02
Hydraulics Update Threshold= 0.02
Energy Slope Method= 1
Volume Change Method= 0
XS Weighting Method= 0
Number of US Weighted Cross Sections= 1
Number of DS Weighted Cross Sections= 1
Upstream XS Weight=0.25
Main XS Weight=0.5
Downstream XS Weight=0.25
Number of DS XS's Weighted with US Boundary= 1
Upstream Boundary Weight= 1
Weight of XSs Associated with US Boundary= 0
Number of US XS's Weighted with DS Boundary= 1
Downstream Boundary Weight= 0.5
Weight of XSs Associated with DS Boundary= 0.5
Sediment Output Level= 4
Mass or Volume Output= 0
Output Increment Type= 1
Profile and TS Output Increment= 10
XS Output Flag= 0
XS Output Increment= 10
Disregard all LS=0
Disregard all Conn=0
Disregard all Breaches=0
Disregard all Pumps=0

--- Walnut36.f01 (steady flow) ---

Flow Title=Multiple
Number of Profiles=7
Profile Names=10-year,25-year,50-year,1pct_min,100-year,1pct_plu,500-year
River Rch & RM= Walnut36,Reach-1,11407
     116     139     155      86     172     343     211
River Rch & RM= Walnut36,Reach-1,10846
     262     333     388     225     448     894     599
River Rch & RM= Walnut36,Reach-1,7470
     133     156     171      93     185     370     219
River Rch & RM= Walnut36,Reach-1,7051
     177     210     233     128     256     510     308
River Rch & RM= Walnut36,Reach-1,916
     313     383     432     241     480     958     594
Boundary for River Rch & Prof#=Walnut36,Reach-1,1
Up Type=0
Dn Type=3
Dn Slope=0.005
Boundary for River Rch & Prof#=Walnut36,Reach-1,2
Up Type=0
Dn Type=3
Dn Slope=0.005
Boundary for River Rch & Prof#=Walnut36,Reach-1,3
Up Type=0
Dn Type=3
Dn Slope=0.005
Boundary for River Rch & Prof#=Walnut36,Reach-1,4
Up Type=0
Dn Type=3
Dn Slope=0.005
Boundary for River Rch & Prof#=Walnut36,Reach-1,5
Up Type=0
Dn Type=3
Dn Slope=0.005
Boundary for River Rch & Prof#=Walnut36,Reach-1,6
Up Type=0
Dn Type=3
Dn Slope=0.005
Boundary for River Rch & Prof#=Walnut36,Reach-1,7
Up Type=0
Dn Type=3
Dn Slope=0.005

--- Walnut36.g01 (geometry) ---

Geom Title=Existing Conditions

River Reach=Walnut36,Reach-1
Reach XY= 30
      2726876.00      6757961.00      2725778.00      6756255.70
      2725925.36      6756051.36      2725833.30      6755911.08
      2726024.80      6755500.49      2726021.00      6755058.68
      2725845.92      6754981.86      2725586.06      6754621.95
      2725255.35      6754541.58      2725222.94      6754319.28
      2725039.62      6754124.47      2724589.64      6753874.34
      2724620.99      6753508.46      2724279.16      6753202.66
      2724220.48      6752958.57      2723979.54      6752709.54
      2723971.00      6752466.01      2723815.77      6752450.65
      2723809.85      6752293.92      2723537.10      6752121.08
      2723571.40      6751816.18      2723415.83      6751800.67
      2723360.36      6751661.42      2723023.26      6751705.66
      2722950.01      6751533.66      2722781.45      6751505.78
      2722426.00      6751111.00      2722368.07      6751208.07
      2721770.11      6751409.02      2721576.00      6751361.00

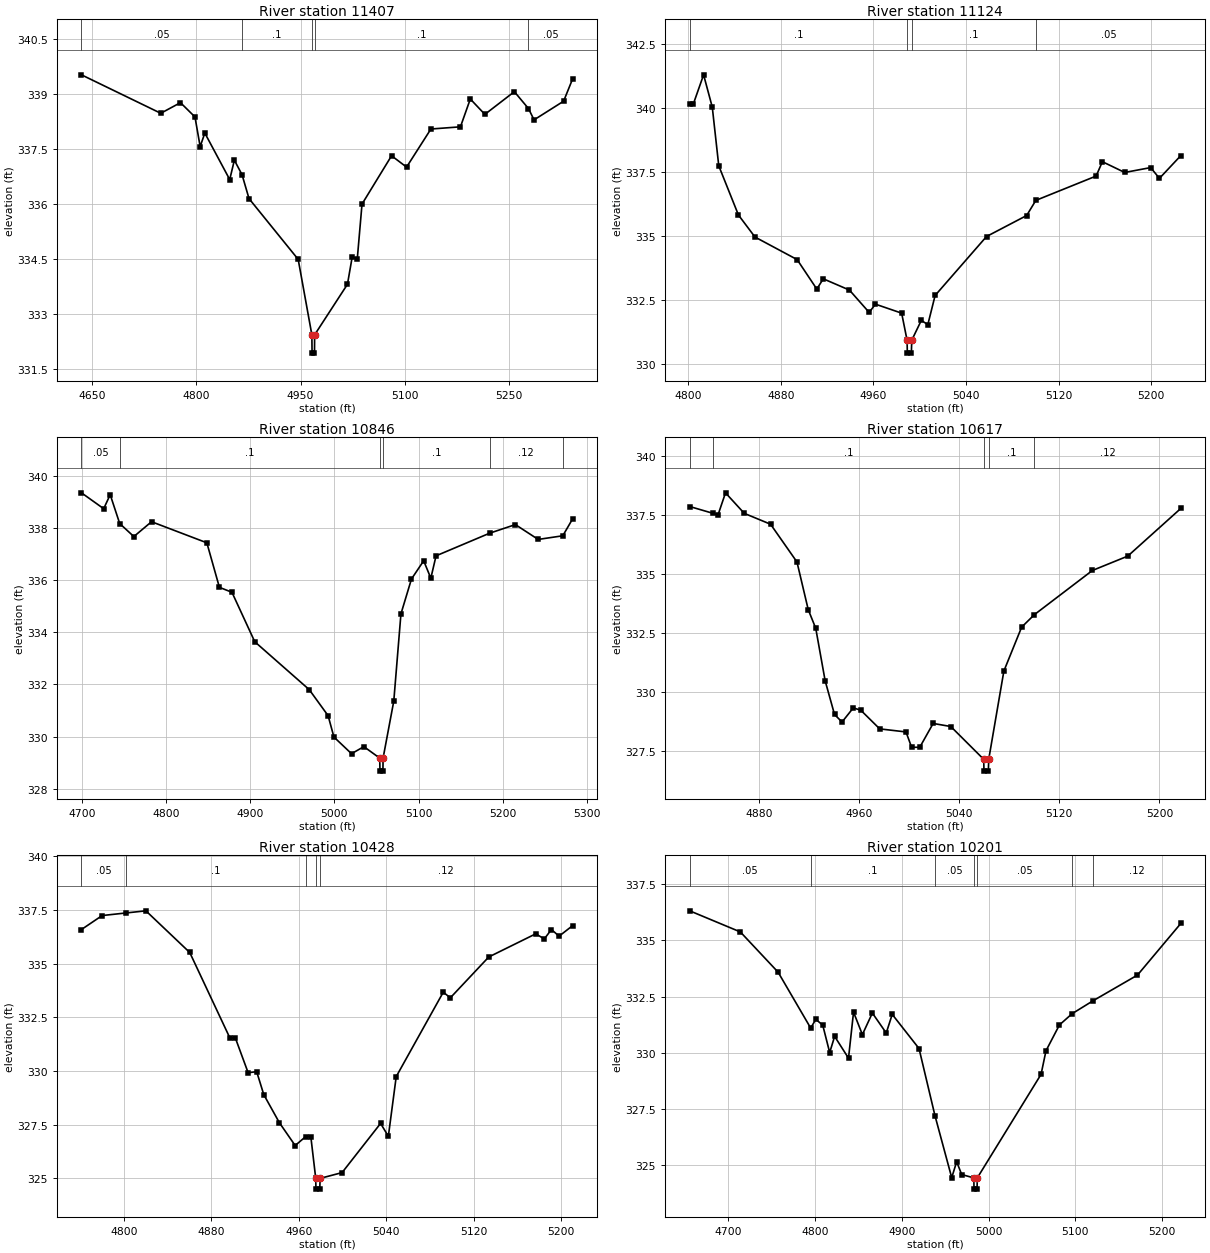
Type RM Length L Ch R = 1,11407,283,283,283
BEGIN DESCRIPTION:
Walnut36 31.0
END DESCRIPTION:
XS GIS Cut Line= 3
      2727117.29      6757640.95      2726876.00      6757911.00
      2726619.60      6758143.11
#Sta/Elev= 30
  4634.2  339.53  4748.5  338.48  4776.9  338.77  4797.8  338.38  4805.3  337.57
  4812.0  337.94  4847.9  336.67  4854.6  337.20  4865.7  336.80  4875.7  336.15
  4946.6  334.49  4966.3  332.43  4966.6  331.93  4970.1  331.93  4970.3  332.43
  5017.6  333.81  5024.4  334.55  5031.8  334.51  5038.6  336.00  5081.2  337.32
  5102.8  337.01  5137.9  338.05  5180.5  338.11  5194.7  338.87  5215.7  338.45
  5258.2  339.07  5278.5  338.61  5286.6  338.30  5329.2  338.81  5342.2  339.42
#Mann=5,-1,0
  4634.2    0.05       0  4865.7     0.1       0  4966.3    0.07       0
  4970.3     0.1       0  5278.5    0.05       0
Bank Sta=4966.3,4970.3
Exp/Cntr=0.3,0.1

Type RM Length L Ch R = 1,11124,278,278,278
BEGIN DESCRIPTION:
Walnut36 30.0
END DESCRIPTION:
XS GIS Cut Line= 3
      2726906.79      6757616.65      2726658.28      6757737.04
      2726605.13      6757875.34
#Sta/Elev= 30
  4801.3  340.16  4804.5  340.16  4813.3  341.29  4820.8  340.03  4826.4  337.74
  4843.4  335.82  4857.7  334.96  4894.1  334.08  4911.1  332.93  4916.7  333.33
  4939.3  332.89  4956.3  332.02  4961.8  332.34  4984.4  331.99  4989.1  330.93
  4989.3  330.43  4992.8  330.43  4993.1  330.93  5001.4  331.71  5007.0  331.54
  5013.3  332.68  5057.7  334.98  5092.4  335.80  5100.3  336.39  5152.4  337.34
  5157.8  337.90  5177.1  337.48  5199.5  337.67  5207.1  337.25  5225.6  338.14
#Mann=4,-1,0
  4801.3     0.1       0  4989.1    0.07       0  4993.1     0.1       0
  5100.3    0.05       0
Bank Sta=4989.1,4993.1
Exp/Cntr=0.3,0.1

Type RM Length L Ch R = 1,10846,229,229,229
BEGIN DESCRIPTION:
Walnut36 29.0
END DESCRIPTION:
XS GIS Cut Line= 3
      2726794.09      6757362.02      2726598.09      6757496.28
      2726394.38      6757775.61
#Sta/Elev= 30
  4699.7  339.36  4726.1  338.75  4733.8  339.29  4745.1  338.18  4761.9  337.68
  4782.9  338.25  4848.6  337.44  4863.5  335.73  4878.4  335.54  4905.5  333.64
  4970.2  331.80  4992.6  330.80  4999.5  329.98  5020.4  329.34  5035.1  329.61
  5053.9  329.17  5054.2  328.67  5057.7  328.67  5057.9  329.17  5070.6  331.36
  5079.1  334.71  5091.6  336.05  5106.1  336.75  5114.6  336.08  5120.8  336.94
  5184.5  337.81  5215.0  338.14  5242.1  337.57  5271.3  337.71  5283.0  338.36
#Mann=6,-1,0
  4699.7    0.05       0  4745.1     0.1       0  5053.9    0.07       0
  5057.9     0.1       0  5184.5    0.12       0  5271.3    0.05       0
Bank Sta=5053.9,5057.9
Exp/Cntr=0.3,0.1

Type RM Length L Ch R = 1,10617,189,189,189
BEGIN DESCRIPTION:
Walnut36 28.0
END DESCRIPTION:
XS GIS Cut Line= 3
      2726676.03      6757260.98      2726526.00      6757361.00
      2726376.03      6757510.97
#Sta/Elev= 30
  4824.7  337.85  4843.4  337.56  4847.3  337.49  4853.3  338.43  4868.3  337.56
  4889.3  337.10  4910.4  335.50  4919.4  333.48  4925.4  332.69  4932.9  330.47
  4940.4  329.04  4946.4  328.72  4955.4  329.32  4961.4  329.22  4976.5  328.43
  4997.5  328.30  5002.0  327.65  5008.5  327.65  5019.2  328.66  5033.3  328.53
  5059.6  327.14  5059.8  326.64  5063.3  326.64  5063.6  327.14  5075.7  330.88
  5089.9  332.74  5100.1  333.27  5146.4  335.14  5174.7  335.75  5217.1  337.77
#Mann=5,-1,0
  4824.7    0.12       0  4843.4     0.1       0  5059.6    0.07       0
  5063.6     0.1       0  5100.1    0.12       0
Bank Sta=5059.6,5063.6
Exp/Cntr=0.3,0.1

Type RM Length L Ch R = 1,10428,227,227,227
BEGIN DESCRIPTION:
Walnut36 27.5
END DESCRIPTION:
XS GIS Cut Line= 3
      2726604.83      6757153.58      2726467.67      6757160.90
      2726268.28      6757400.53
#Sta/Elev= 30
  4761.3  336.59  4780.2  337.24  4801.9  337.36  4820.2  337.46  4860.3  335.52
  4897.0  331.54  4902.0  331.54  4913.7  329.92  4921.5  329.97  4928.0  328.90
  4942.3  327.59  4956.7  326.53  4966.4  326.95  4971.0  326.95  4975.5  325.00
  4975.7  324.50  4979.2  324.50  4979.5  325.00  4999.6  325.27  5034.8  327.56
  5041.9  326.96  5049.1  329.74  5092.1  333.67  5098.6  333.41  5133.7  335.31
  5176.7  336.39  5184.5  336.15  5191.0  336.59  5198.0  336.28  5210.4  336.77
#Mann=5,-1,0
  4761.3    0.05       0  4801.9     0.1       0  4966.4    0.12       0
  4975.5    0.07       0  4979.5    0.12       0
Bank Sta=4975.5,4979.5
Exp/Cntr=0.3,0.1

Type RM Length L Ch R = 1,10201,220,220,220
BEGIN DESCRIPTION:
Walnut36 27.0
END DESCRIPTION:
XS GIS Cut Line= 3
      2726480.48      6756796.89      2726279.26      6757159.07
      2726276.00      6757311.01
#Sta/Elev= 30
  4655.4  336.32  4713.8  335.38  4757.3  333.59  4794.9  331.10  4800.8  331.49
  4808.8  331.23  4816.8  330.01  4822.5  330.73  4838.5  329.76  4844.3  331.81
  4854.5  330.81  4866.0  331.77  4882.0  330.88  4888.9  331.71  4919.8  330.19
  4938.2  327.20  4957.5  324.44  4963.2  325.15  4969.0  324.58  4983.0  324.43
  4983.2  323.93  4986.7  323.93  4987.0  324.43  5060.5  329.04  5066.2  330.09
  5081.7  331.24  5096.3  331.74  5120.2  332.31  5171.7  333.46  5221.7  335.76
#Mann=7,-1,0
  4655.4    0.05       0  4794.9     0.1       0  4938.2    0.05       0
  4983.0    0.03       0  4987.0    0.05       0  5096.3     0.1       0
  5120.2    0.12       0
Bank Sta=4983,4987
Exp/Cntr=0.3,0.1

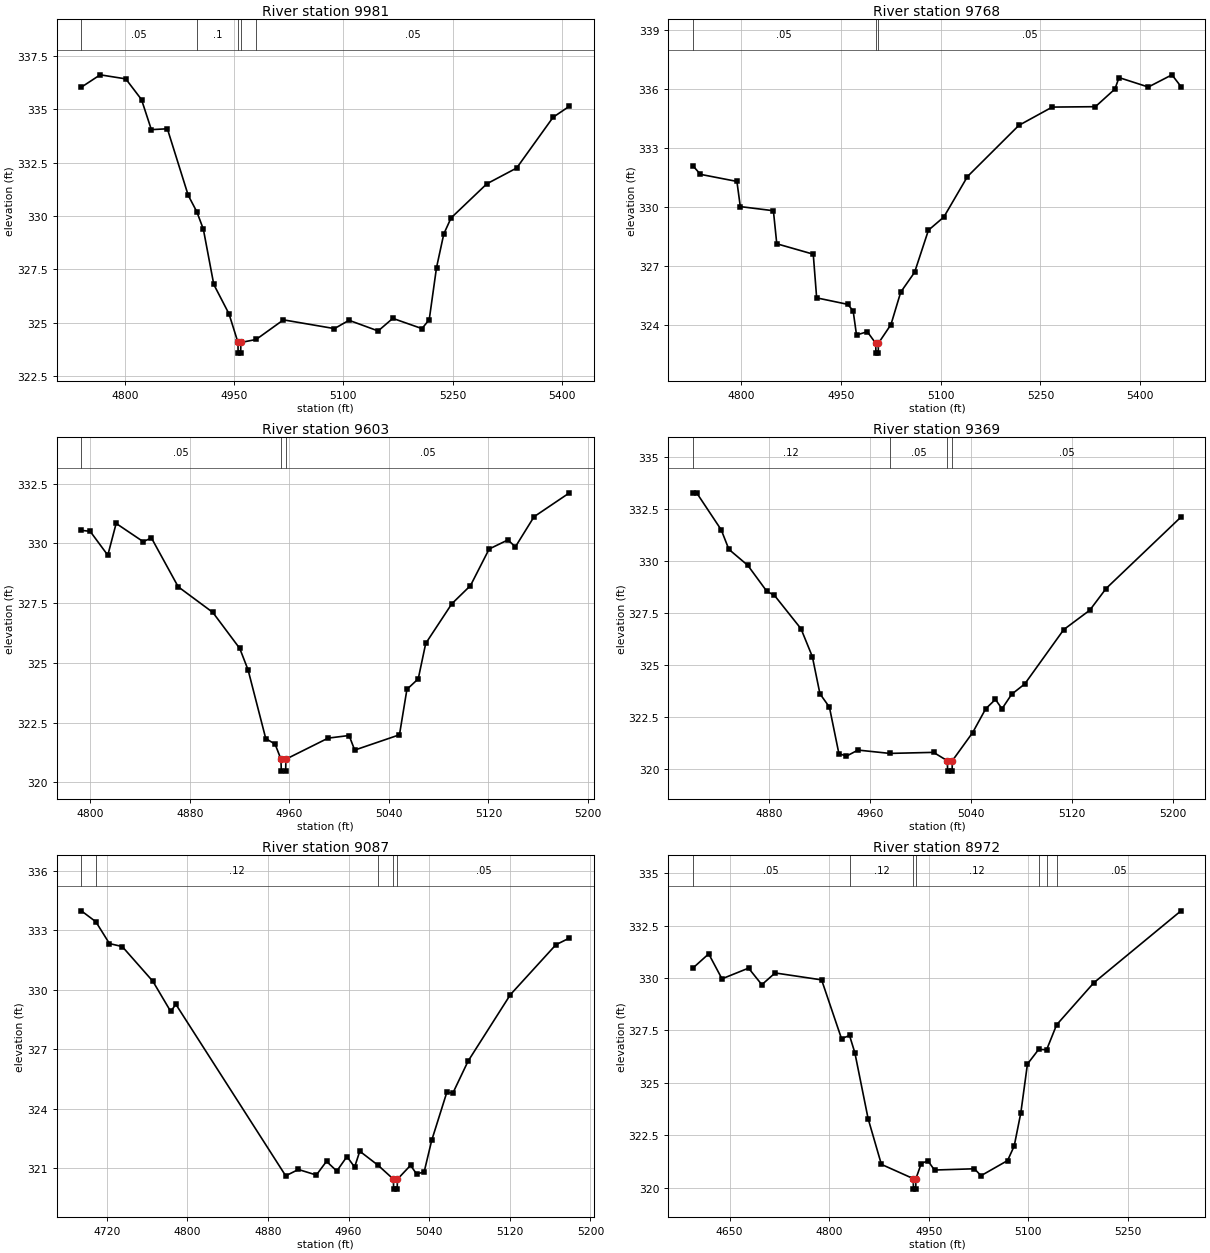
Type RM Length L Ch R = 1,9981,213,213,213
BEGIN DESCRIPTION:
Walnut36 26.0
END DESCRIPTION:
XS GIS Cut Line= 3
      2726429.28      6756698.09      2726253.66      6756904.81
      2726250.00      6757303.54
#Sta/Elev= 30
  4740.3  336.04  4766.2  336.62  4801.3  336.43  4822.9  335.46  4836.4  334.05
  4858.4  334.09  4887.0  330.97  4898.8  330.20  4907.8  329.38  4922.1  326.79
  4943.0  325.41  4955.3  324.07  4955.5  323.57  4959.0  323.57  4959.3  324.07
  4980.2  324.21  5017.7  325.13  5087.7  324.72  5107.7  325.11  5147.7  324.61
  5167.8  325.20  5207.8  324.72  5217.8  325.14  5227.8  327.58  5237.8  329.16
  5247.8  329.91  5296.9  331.51  5337.8  332.25  5387.8  334.63  5410.3  335.15
#Mann=5,-1,0
  4740.3    0.05       0  4898.8     0.1       0  4955.3    0.03       0
  4959.3     0.1       0  4980.2    0.05       0
Bank Sta=4955.3,4959.3
Exp/Cntr=0.3,0.1

Type RM Length L Ch R = 1,9768,165,165,165
BEGIN DESCRIPTION:
Walnut36 25.0
END DESCRIPTION:
XS GIS Cut Line= 3
      2726182.33      6756471.25      2726140.25      6756716.40
      2725854.91      6757109.65
#Sta/Elev= 30
  4727.0  332.08  4738.4  331.64  4793.3  331.28  4798.4  330.00  4848.2  329.79
  4853.3  328.11  4908.2  327.58  4913.3  325.36  4960.1  325.03  4968.2  324.70
  4973.3  323.47  4989.5  323.64  5002.2  323.05  5002.5  322.55  5006.0  322.55
  5006.2  323.05  5025.1  324.00  5039.8  325.65  5060.7  326.66  5081.5  328.80
  5104.7  329.47  5140.3  331.53  5217.6  334.13  5267.8  335.06  5332.8  335.08
  5362.2  335.98  5368.3  336.56  5412.4  336.08  5448.0  336.70  5461.6  336.10
#Mann=3,-1,0
  4727.0    0.05       0  5002.2    0.04       0  5006.2    0.05       0
Bank Sta=5002.2,5006.2
Exp/Cntr=0.3,0.1

Type RM Length L Ch R = 1,9603,234,234,234
BEGIN DESCRIPTION:
Walnut36 24.0
END DESCRIPTION:
XS GIS Cut Line= 3
      2726167.71      6756452.97      2726026.00      6756611.00
      2725926.02      6756760.96
#Sta/Elev= 30
  4792.7  330.54  4799.8  330.50  4814.0  329.50  4820.7  330.83  4842.4  330.07
  4849.1  330.22  4870.6  328.18  4898.4  327.11  4920.1  325.60  4926.8  324.70
  4941.0  321.83  4948.5  321.60  4953.2  320.97  4953.5  320.47  4957.0  320.47
  4957.2  320.97  4991.1  321.85  5008.0  321.96  5012.5  321.35  5048.5  321.99
  5054.5  323.89  5063.6  324.33  5069.6  325.81  5090.6  327.47  5105.6  328.23
  5120.6  329.76  5135.7  330.14  5141.7  329.85  5156.7  331.11  5185.2  332.11
#Mann=3,-1,0
  4792.7    0.05       0  4953.2    0.04       0  4957.2    0.05       0
Bank Sta=4953.2,4957.2
Exp/Cntr=0.3,0.1

Type RM Length L Ch R = 1,9369,282,282,282
BEGIN DESCRIPTION:
Walnut36 23.0
END DESCRIPTION:
XS GIS Cut Line= 3
      2726075.96      6756311.03      2725926.00      6756411.00
      2725725.99      6756461.00
#Sta/Elev= 30
  4819.8  333.26  4822.8  333.26  4842.3  331.48  4848.3  330.55  4863.3  329.78
  4878.3  328.54  4884.4  328.34  4905.4  326.74  4914.4  325.40  4920.4  323.62
  4927.9  322.98  4935.4  320.75  4941.4  320.63  4950.5  320.92  4975.7  320.76
  5010.3  320.81  5021.2  320.41  5021.5  319.91  5025.0  319.91  5025.2  320.41
  5041.3  321.76  5051.6  322.90  5059.3  323.35  5064.5  322.90  5072.2  323.60
  5082.5  324.09  5113.4  326.70  5134.0  327.63  5146.9  328.67  5206.2  332.10
#Mann=4,-1,0
  4819.8    0.12       0  4975.7    0.05       0  5021.2    0.04       0
  5025.2    0.05       0
Bank Sta=5021.2,5025.2
Exp/Cntr=0.3,0.1

Type RM Length L Ch R = 1,9087,115,115,115
BEGIN DESCRIPTION:
Walnut36 22.0
END DESCRIPTION:
XS GIS Cut Line= 3
      2726076.01      6756261.00      2725776.00      6756211.00
      2725626.02      6756310.98
#Sta/Elev= 30
  4694.8  333.97  4709.2  333.42  4722.7  332.32  4735.4  332.17  4765.8  330.42
  4783.5  328.90  4788.6  329.26  4897.6  320.62  4910.2  320.94  4928.0  320.66
  4938.1  321.35  4948.3  320.86  4958.4  321.59  4966.0  321.06  4971.1  321.86
  4989.3  321.15  5004.5  320.45  5004.7  319.95  5008.2  319.95  5008.5  320.45
  5021.5  321.15  5027.5  320.71  5035.0  320.82  5042.5  322.41  5057.5  324.83
  5063.5  324.79  5078.6  326.40  5120.6  329.75  5165.7  332.26  5179.2  332.60
#Mann=5,-1,0
  4694.8    0.05       0  4709.2    0.12       0  4989.3    0.05       0
  5004.5    0.04       0  5008.5    0.05       0
Bank Sta=5004.5,5008.5
Exp/Cntr=0.3,0.1

Type RM Length L Ch R = 1,8972,170,170,170
BEGIN DESCRIPTION:
Walnut36 21.1
END DESCRIPTION:
XS GIS Cut Line= 3
      2726229.85      6756136.55      2725772.35      6756113.43
      2725494.53      6756112.77
#Sta/Elev= 30
  4594.5  330.47  4618.4  331.15  4638.4  329.96  4678.5  330.47  4698.5  329.68
  4718.5  330.24  4788.6  329.91  4818.6  327.11  4830.7  327.26  4838.7  326.44
  4858.7  323.30  4878.7  321.12  4926.8  320.44  4927.0  319.94  4930.5  319.94
  4930.8  320.44  4938.8  321.16  4948.8  321.29  4958.8  320.85  5018.9  320.91
  5028.9  320.58  5068.9  321.30  5078.9  321.99  5088.9  323.57  5098.9  325.90
  5115.9  326.60  5127.8  326.58  5142.9  327.77  5198.9  329.77  5330.4  333.20
#Mann=7,-1,0
  4594.5    0.05       0  4830.7    0.12       0  4926.8    0.07       0
  4930.8    0.12       0  5115.9    0.05       0  5127.8    0.12       0
  5142.9    0.05       0
Bank Sta=4926.8,4930.8
Exp/Cntr=0.3,0.1

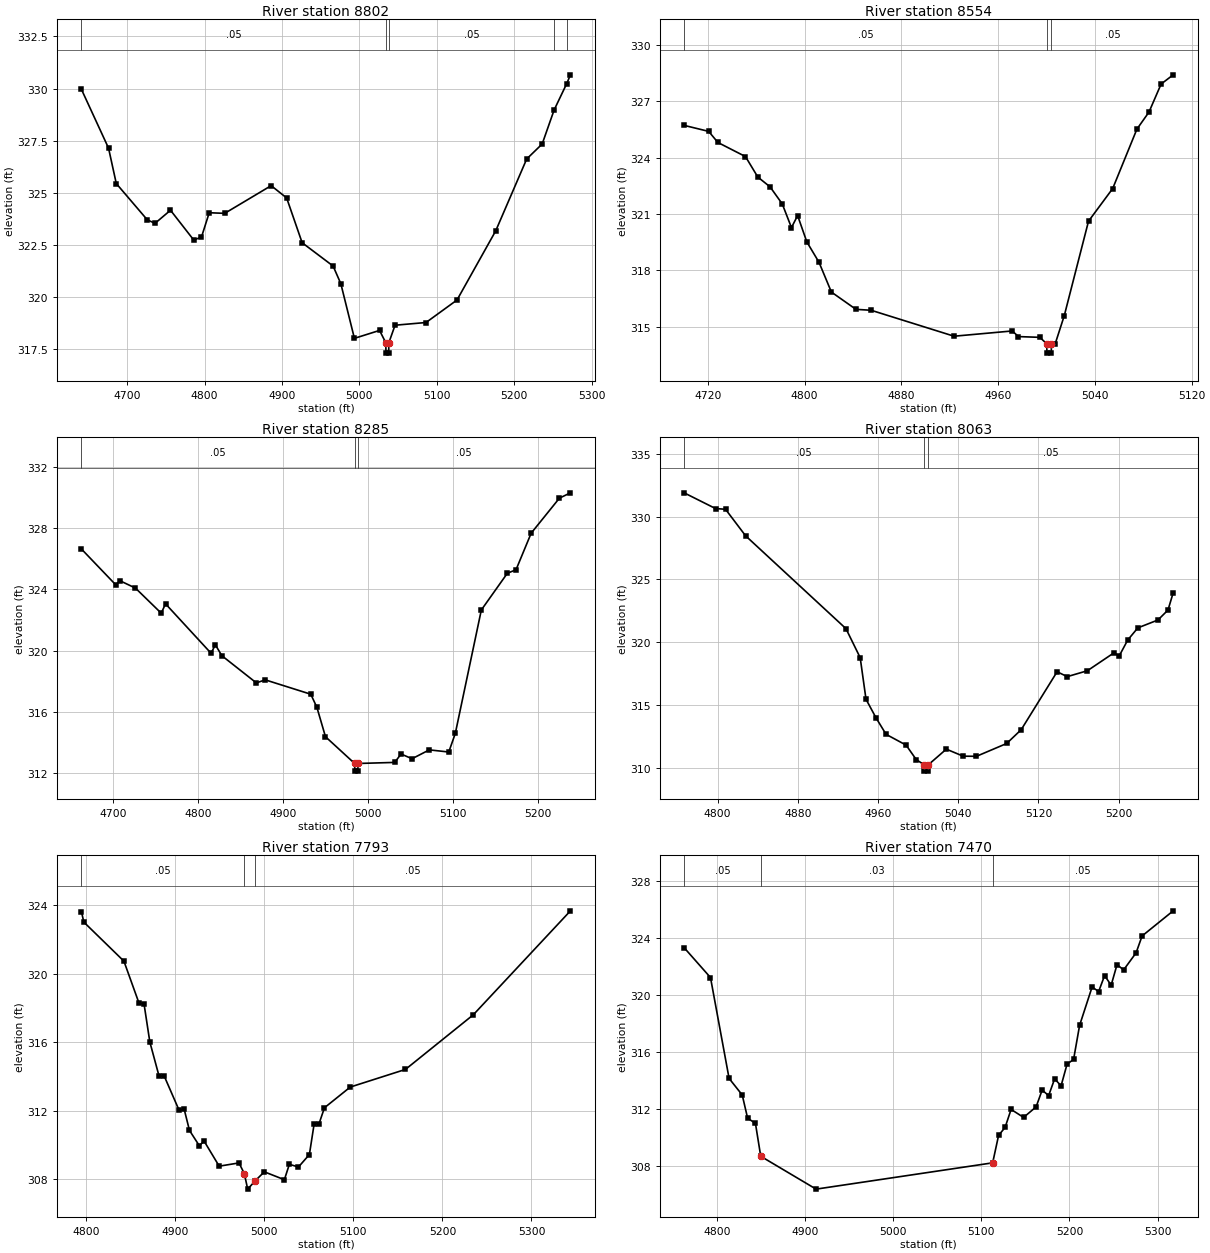
Type RM Length L Ch R = 1,8802,248,248,248
BEGIN DESCRIPTION:
Walnut36 21.0
END DESCRIPTION:
XS GIS Cut Line= 3
      2726281.11      6756015.83      2725926.00      6756011.00
      2725649.55      6756010.34
#Sta/Elev= 30
  4640.9  329.97  4676.0  327.14  4686.0  325.44  4726.0  323.70  4736.0  323.53
  4756.0  324.16  4786.0  322.73  4796.0  322.87  4806.0  324.04  4826.0  324.01
  4886.0  325.34  4906.0  324.75  4926.0  322.60  4966.0  321.48  4976.0  320.63
  4993.5  318.01  5026.0  318.39  5034.0  317.80  5034.3  317.30  5037.8  317.30
  5038.0  317.80  5046.0  318.64  5086.0  318.77  5126.0  319.85  5176.0  323.17
  5216.0  326.62  5236.0  327.34  5251.4  328.97  5267.7  330.24  5272.5  330.66
#Mann=5,-1,0
  4640.9    0.05       0  5034.0    0.04       0  5038.0    0.05       0
  5251.4    0.12       0  5267.7    0.05       0
Bank Sta=5034,5038
Exp/Cntr=0.3,0.1

Type RM Length L Ch R = 1,8554,269,269,269
BEGIN DESCRIPTION:
Walnut36 20.0
END DESCRIPTION:
XS GIS Cut Line= 3
      2726176.03      6755861.00      2725876.00      6755811.00
      2725775.97      6755811.00
#Sta/Elev= 30
  4700.5  325.71  4720.8  325.39  4728.4  324.80  4751.2  324.05  4761.4  322.96
  4771.5  322.44  4781.6  321.53  4789.2  320.27  4794.3  320.91  4801.9  319.51
  4812.0  318.42  4822.2  316.84  4842.5  315.92  4855.1  315.87  4923.6  314.49
  4971.7  314.77  4976.8  314.47  4994.5  314.43  5000.1  314.09  5000.4  313.59
  5003.9  313.59  5004.1  314.09  5007.2  314.09  5014.7  315.59  5034.7  320.61
  5054.7  322.35  5074.7  325.51  5084.7  326.42  5094.7  327.91  5104.7  328.40
#Mann=3,-1,0
  4700.5    0.05       0  5000.1    0.04       0  5004.1    0.05       0
Bank Sta=5000.1,5004.1
Exp/Cntr=0.3,0.1

Type RM Length L Ch R = 1,8285,222,222,222
BEGIN DESCRIPTION:
Walnut36 19.0
END DESCRIPTION:
XS GIS Cut Line= 3
      2726308.57      6755633.53      2725953.67      6755569.51
      2725743.27      6755527.43
#Sta/Elev= 30
  4663.1  326.65  4703.4  324.31  4708.5  324.57  4726.7  324.09  4757.0  322.45
  4762.1  323.06  4815.6  319.83  4820.7  320.38  4828.3  319.67  4868.9  317.89
  4879.3  318.09  4932.9  317.15  4940.1  316.29  4950.2  314.37  4984.5  312.62
  4984.7  312.12  4988.2  312.12  4988.5  312.62  5031.6  312.69  5039.1  313.24
  5052.0  312.93  5072.3  313.51  5095.2  313.37  5102.9  314.59  5133.5  322.66
  5164.1  325.06  5174.3  325.29  5192.1  327.68  5225.3  329.97  5238.3  330.32
#Mann=3,-1,0
  4663.1    0.05       0  4984.5    0.03       0  4988.5    0.05       0
Bank Sta=4984.5,4988.5
Exp/Cntr=0.3,0.1

Type RM Length L Ch R = 1,8063,270,270,270
BEGIN DESCRIPTION:
Walnut36 18.5
END DESCRIPTION:
XS GIS Cut Line= 3
      2726257.28      6755359.15      2725977.45      6755370.12
      2725770.86      6755392.06
#Sta/Elev= 30
  4766.6  331.89  4797.9  330.64  4807.9  330.58  4827.9  328.47  4928.0  321.08
  4942.2  318.77  4948.0  315.46  4958.0  313.98  4968.0  312.67  4988.0  311.81
  4998.1  310.66  5006.1  310.24  5006.3  309.74  5009.8  309.74  5010.1  310.24
  5028.1  311.49  5044.9  310.93  5058.2  310.92  5088.3  311.94  5102.8  313.04
  5138.6  317.65  5148.7  317.26  5168.8  317.73  5195.4  319.16  5200.5  318.90
  5209.0  320.17  5219.1  321.14  5239.2  321.77  5249.2  322.56  5254.4  323.94
#Mann=3,-1,0
  4766.6    0.05       0  5006.1    0.03       0  5010.1    0.05       0
Bank Sta=5006.1,5010.1
Exp/Cntr=0.3,0.1

Type RM Length L Ch R = 1,7793,323,323,323
BEGIN DESCRIPTION:
Walnut36 18.0
END DESCRIPTION:
XS GIS Cut Line= 3
      2726195.08      6755216.45      2725959.16      6755101.23
      2725695.79      6755214.63
#Sta/Elev= 30
  4794.5  323.62  4797.3  323.00  4842.3  320.72  4859.3  318.26  4864.9  318.22
  4871.4  316.00  4881.8  314.00  4887.4  314.03  4904.3  312.01  4909.9  312.09
  4915.9  310.84  4926.9  309.95  4932.4  310.21  4949.3  308.75  4971.5  308.94
  4977.5  308.32  4981.3  307.41  4990.0  307.91  5000.0  308.42  5022.5  307.96
  5028.1  308.86  5038.3  308.70  5050.6  309.43  5056.0  311.24  5061.5  311.24
  5067.5  312.16  5096.5  313.37  5158.5  314.40  5234.7  317.59  5343.8  323.66
#Mann=3,-1,0
  4794.5    0.05       0  4977.5    0.03       0  4990.0    0.05       0
Bank Sta=4977.5,4990
Exp/Cntr=0.3,0.1

Type RM Length L Ch R = 1,7470,189,189,189
BEGIN DESCRIPTION:
Walnut36 17.7
END DESCRIPTION:
XS GIS Cut Line= 3
      2726024.98      6754828.70      2725929.89      6754892.71
      2725606.10      6755190.89
#Sta/Elev= 30
  4762.9  323.31  4792.8  321.22  4813.9  314.16  4828.8  313.00  4834.9  311.38
  4843.8  311.01  4849.8  308.71  4912.6  306.41  5112.9  308.25  5119.6  310.17
  5127.0  310.73  5133.8  311.99  5148.0  311.43  5162.2  312.17  5169.0  313.34
  5176.4  312.96  5183.2  314.13  5190.5  313.64  5197.3  315.16  5204.7  315.49
  5211.5  317.87  5225.7  320.56  5233.1  320.24  5239.9  321.36  5247.3  320.68
  5254.0  322.13  5261.4  321.75  5275.6  322.95  5282.4  324.13  5317.7  325.89
#Mann=3,-1,0
  4762.9    0.05       0  4849.8    0.03       0  5112.9    0.05       0
Bank Sta=4849.8,5112.9
Exp/Cntr=0.3,0.1

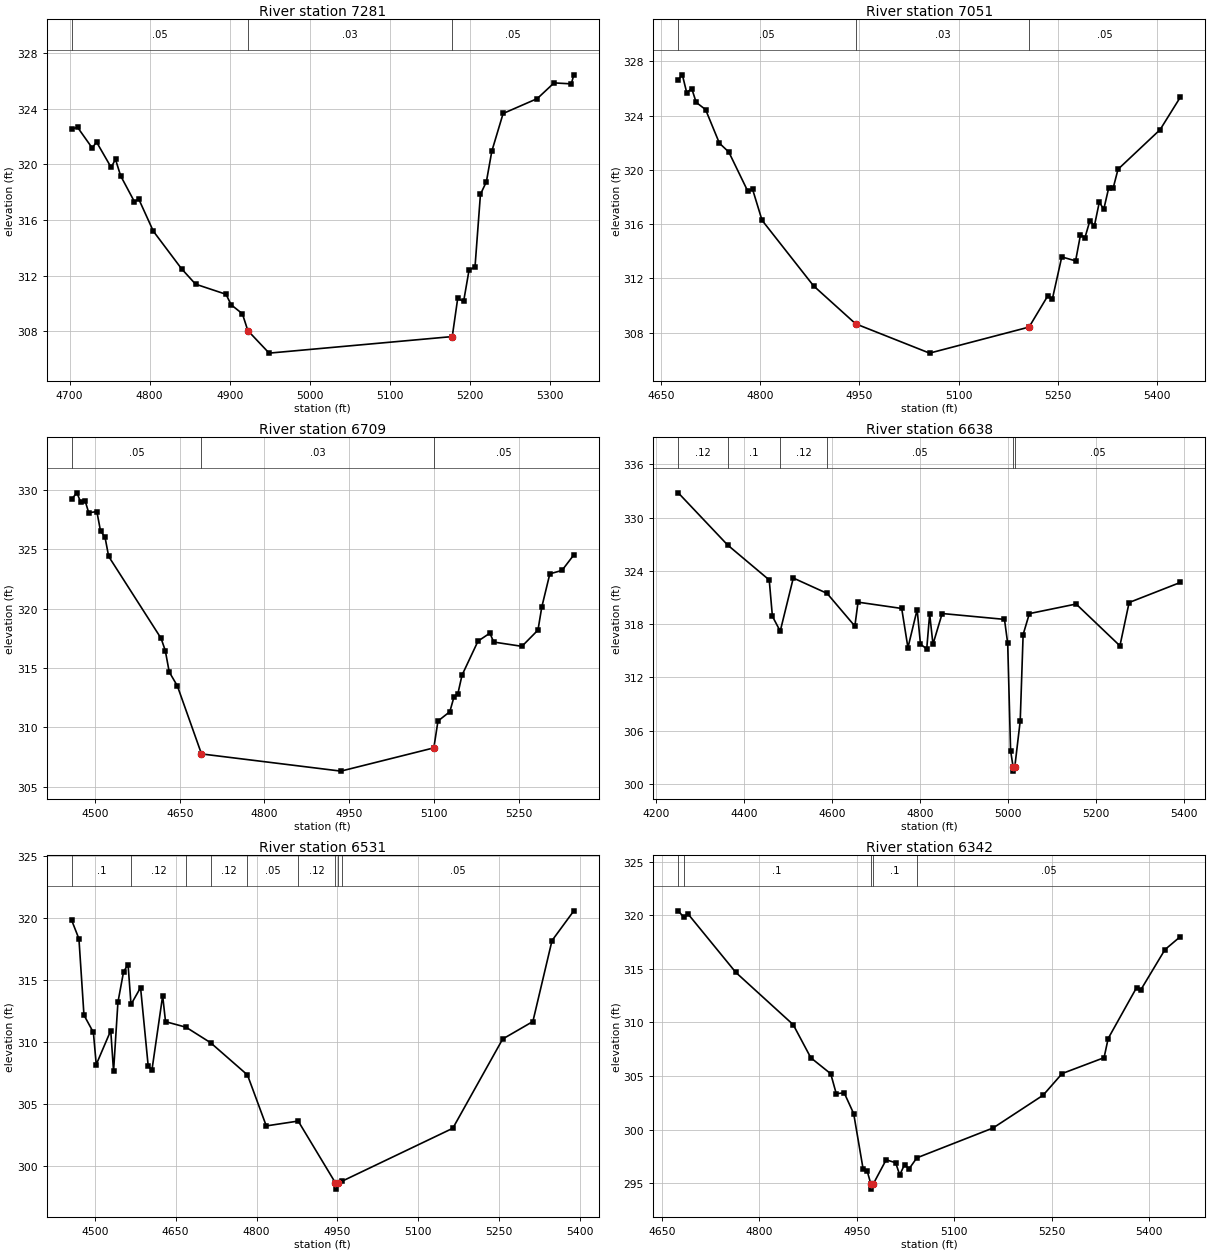
Type RM Length L Ch R = 1,7281,230,230,230
BEGIN DESCRIPTION:
Walnut36 17.4
END DESCRIPTION:
XS GIS Cut Line= 3
      2725992.10      6754675.03      2725820.14      6754748.20
      2725496.54      6755046.21
#Sta/Elev= 30
  4702.8  322.56  4710.1  322.66  4728.3  321.18  4733.7  321.61  4751.9  319.79
  4757.4  320.36  4763.8  319.18  4781.0  317.32  4786.4  317.51  4804.6  315.20
  4839.8  312.50  4857.3  311.39  4895.4  310.66  4901.7  309.91  4915.8  309.26
  4922.6  308.05  4949.2  306.43  5177.8  307.62  5184.6  310.36  5192.0  310.15
  5198.8  312.41  5206.2  312.62  5213.0  317.85  5220.4  318.75  5227.2  320.95
  5241.3  323.66  5283.9  324.73  5304.9  325.86  5326.4  325.79  5329.6  326.44
#Mann=3,-1,0
  4702.8    0.05       0  4922.6    0.03       0  5177.8    0.05       0
Bank Sta=4922.6,5177.8
Exp/Cntr=0.3,0.1

Type RM Length L Ch R = 1,7051,342,342,342
BEGIN DESCRIPTION:
Walnut36 17.2
END DESCRIPTION:
XS GIS Cut Line= 3
      2725851.27      6754428.06      2725611.61      6754640.28
      2725289.13      6754937.25
#Sta/Elev= 30
  4676.2  326.64  4682.4  327.01  4689.0  325.70  4696.6  326.00  4703.3  324.98
  4717.5  324.45  4738.4  321.97  4752.6  321.32  4781.0  318.46  4788.6  318.56
  4802.8  316.29  4880.6  311.46  4944.2  308.66  5055.9  306.50  5206.2  308.42
  5234.6  310.73  5241.4  310.49  5255.6  313.59  5276.5  313.30  5283.9  315.22
  5290.7  315.02  5298.1  316.26  5304.9  315.88  5312.3  317.62  5319.1  317.11
  5326.5  318.67  5333.3  318.67  5340.6  320.05  5404.2  322.97  5434.7  325.36
#Mann=3,-1,0
  4676.2    0.05       0  4944.2    0.03       0  5206.2    0.05       0
Bank Sta=4944.2,5206.2
Exp/Cntr=0.3,0.1

Type RM Length L Ch R = 1,6709,71,71,71
BEGIN DESCRIPTION:
Walnut36 17.0
END DESCRIPTION:
XS GIS Cut Line= 3
      2725745.12      6754217.75      2725393.94      6754499.43
      2725071.45      6754796.42
#Sta/Elev= 30
  4458.9  329.26  4468.1  329.77  4474.5  328.99  4482.5  329.10  4488.9  328.09
  4503.3  328.19  4509.8  326.55  4517.7  326.04  4524.2  324.41  4617.0  317.50
  4624.4  316.47  4631.4  314.67  4645.8  313.49  4688.5  307.76  4935.2  306.31
  5099.7  308.27  5107.0  310.53  5128.0  311.32  5135.4  312.57  5142.2  312.83
  5149.6  314.40  5177.9  317.27  5198.9  317.94  5205.7  317.19  5255.6  316.83
  5284.0  318.20  5290.8  320.15  5305.0  322.94  5326.5  323.23  5347.5  324.54
#Mann=3,-1,0
  4458.9    0.05       0  4688.5    0.03       0  5099.7    0.05       0
Bank Sta=4688.5,5099.7
Exp/Cntr=0.3,0.1

Type RM Length L Ch R = 1,6638,107,107,107
BEGIN DESCRIPTION:
Walnut36 16.8
END DESCRIPTION:
XS GIS Cut Line= 5
      2725711.55      6753993.96      2725523.63      6754176.20
      2725521.37      6754316.03      2725335.34      6754479.90
      2724965.55      6754804.53
#Sta/Elev= 30
  4250.4  332.79  4362.7  326.91  4457.3  322.97  4464.5  318.88  4482.3  317.20
  4512.0  323.19  4588.8  321.46  4652.0  317.77  4659.2  320.47  4758.5  319.76
  4772.7  315.34  4793.6  319.63  4801.2  315.74  4815.4  315.20  4822.1  319.13
  4829.6  315.73  4850.5  319.19  4992.2  318.53  4999.5  315.83  5006.1  303.75
  5011.7  301.93  5012.0  301.43  5015.7  301.93  5028.0  307.10  5034.6  316.82
  5048.8  319.18  5155.1  320.26  5254.7  315.55  5275.6  320.43  5392.0  322.69
#Mann=6,-1,0
  4250.4    0.12       0  4362.7     0.1       0  4482.3    0.12       0
  4588.8    0.05       0  5011.7    0.03       0  5015.7    0.05       0
Bank Sta=5011.7,5015.7
Exp/Cntr=0.3,0.1

Type RM Length L Ch R = 1,6531,189,189,189
BEGIN DESCRIPTION:
Walnut36 16.3
END DESCRIPTION:
XS GIS Cut Line= 5
      2725523.80      6754049.47      2725445.16      6754294.56
      2725339.06      6754426.27      2725174.44      6754462.85
      2724960.69      6754722.27
#Sta/Elev= 30
  4457.3  319.77  4470.6  318.29  4479.9  312.14  4497.4  310.74  4502.7  308.15
  4529.6  310.89  4534.8  307.60  4542.9  313.17  4553.4  315.64  4561.7  316.22
  4567.2  313.00  4584.9  314.36  4599.0  308.06  4605.9  307.67  4625.9  313.70
  4631.2  311.61  4669.3  311.16  4714.8  309.91  4783.2  307.31  4818.1  303.20
  4877.3  303.59  4946.4  298.60  4946.7  298.10  4950.4  298.60  4959.2  298.75
  5164.1  303.01  5256.6  310.21  5312.6  311.62  5348.1  318.15  5388.6  320.55
#Mann=9,-1,0
  4457.3     0.1       0  4567.2    0.12       0  4669.3    0.05       0
  4714.8    0.12       0  4783.2    0.05       0  4877.3    0.12       0
  4946.4    0.04       0  4950.4    0.12       0  4959.2    0.05       0
Bank Sta=4946.4,4950.4
Exp/Cntr=0.3,0.1

Type RM Length L Ch R = 1,6342,196,196,196
BEGIN DESCRIPTION:
Walnut36 16.0
END DESCRIPTION:
XS GIS Cut Line= 3
      2725348.23      6754031.13      2725218.34      6754237.86
      2724900.51      6754659.80
#Sta/Elev= 30
  4675.4  320.42  4683.6  319.84  4691.0  320.09  4764.0  314.67  4852.3  309.79
  4879.4  306.70  4910.0  305.21  4918.5  303.35  4930.7  303.43  4945.3  301.49
  4959.9  296.29  4966.1  296.13  4971.6  294.94  4971.8  294.44  4975.6  294.94
  4995.3  297.18  5009.9  296.90  5016.1  295.77  5023.6  296.72  5030.7  296.35
  5042.5  297.36  5159.8  300.15  5236.8  303.21  5266.0  305.23  5330.5  306.71
  5336.8  308.50  5380.5  313.25  5386.7  313.01  5424.2  316.80  5447.8  318.01
#Mann=5,-1,0
  4675.4    0.12       0  4683.6     0.1       0  4971.6    0.07       0
  4975.6     0.1       0  5042.5    0.05       0
Bank Sta=4971.6,4975.6
Exp/Cntr=0.3,0.1

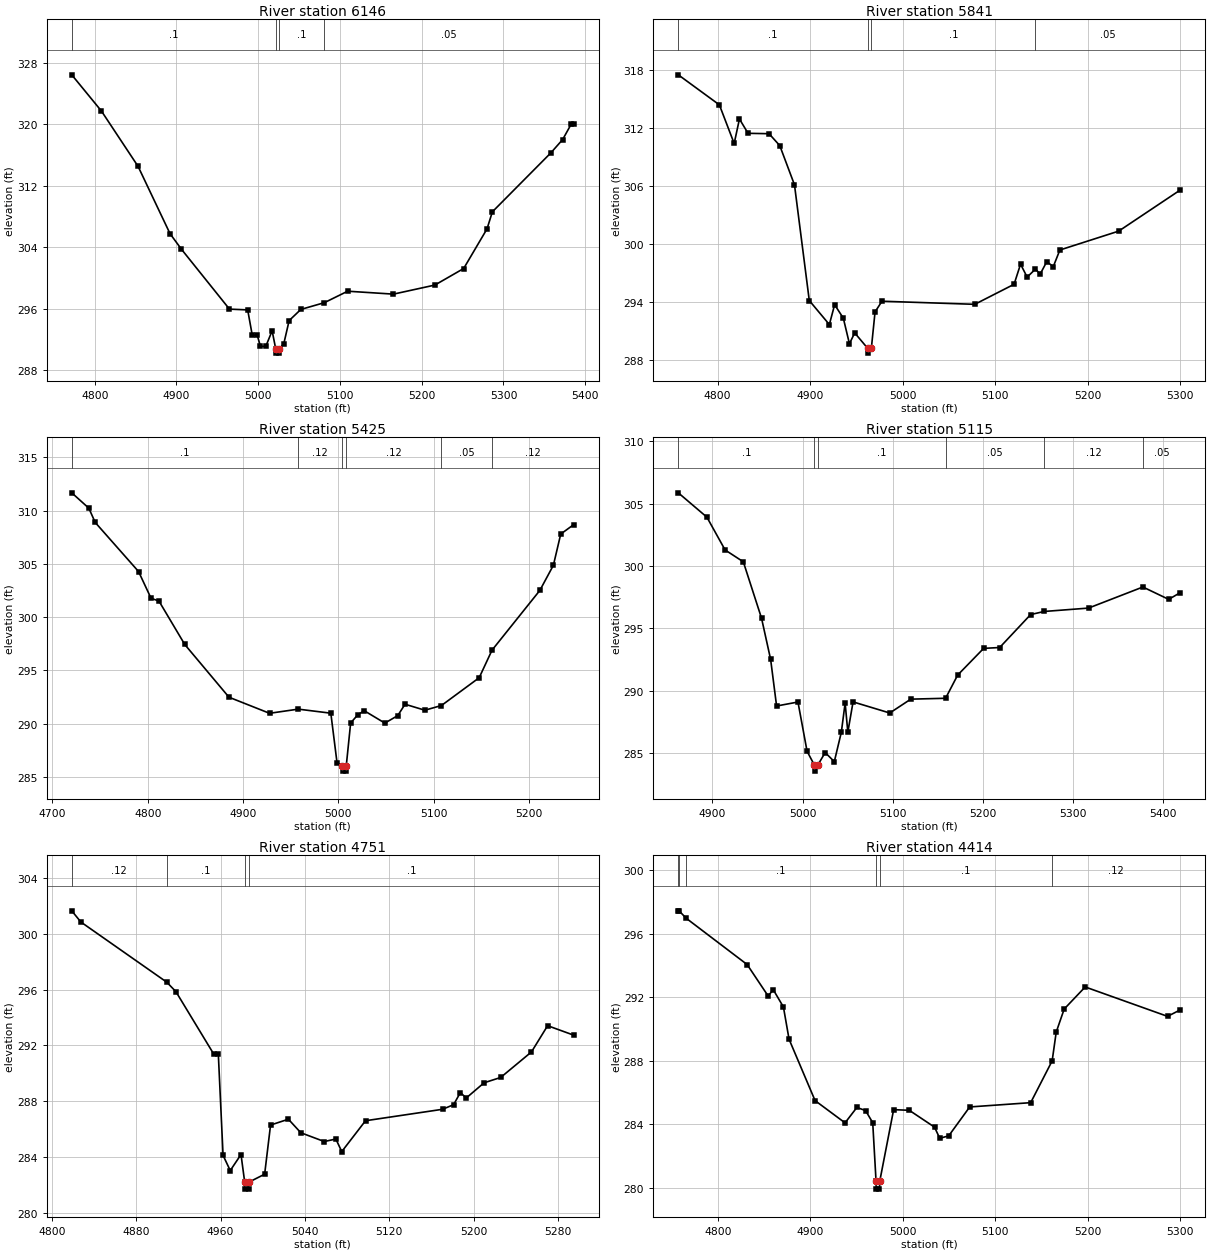
Type RM Length L Ch R = 1,6146,305,305,305
BEGIN DESCRIPTION:
Walnut36 15.0
END DESCRIPTION:
XS GIS Cut Line= 3
      2725176.00      6753961.00      2725076.00      6754161.00
      2724826.01      6754460.98
#Sta/Elev= 30
  4771.9  326.42  4808.2  321.71  4853.0  314.52  4892.1  305.77  4906.1  303.74
  4964.8  295.96  4987.1  295.86  4992.7  292.56  4998.8  292.56  5002.7  291.12
  5009.2  291.11  5017.0  293.14  5021.5  290.74  5021.7  290.24  5025.2  290.24
  5025.5  290.74  5031.3  291.48  5037.8  294.47  5052.1  295.92  5080.9  296.80
  5109.4  298.29  5165.4  297.91  5216.1  299.09  5251.3  301.24  5279.9  306.40
  5286.4  308.61  5358.0  316.28  5372.4  318.01  5382.8  320.00  5386.0  320.00
#Mann=4,-1,0
  4771.9     0.1       0  5021.5    0.07       0  5025.5     0.1       0
  5080.9    0.05       0
Bank Sta=5021.5,5025.5
Exp/Cntr=0.3,0.1

Type RM Length L Ch R = 1,5841,416,416,416
BEGIN DESCRIPTION:
Walnut36 14.0
END DESCRIPTION:
XS GIS Cut Line= 3
      2725051.86      6753855.57      2724857.99      6753963.48
      2724631.14      6754190.33
#Sta/Elev= 30
  4757.6  317.45  4802.0  314.35  4818.0  310.36  4823.7  312.89  4833.0  311.41
  4855.7  311.37  4867.3  310.14  4883.2  306.09  4899.2  294.14  4920.9  291.66
  4926.6  293.71  4936.0  292.32  4942.6  289.68  4948.3  290.80  4962.3  289.21
  4962.6  288.71  4966.3  289.21  4970.3  292.97  4977.8  294.07  5078.1  293.75
  5120.6  295.82  5127.6  297.90  5134.7  296.56  5143.7  297.39  5148.8  296.87
  5155.9  298.15  5163.0  297.65  5170.1  299.36  5233.7  301.31  5300.3  305.56
#Mann=4,-1,0
  4757.6     0.1       0  4962.3    0.07       0  4966.3     0.1       0
  5143.7    0.05       0
Bank Sta=4962.3,4966.3
Exp/Cntr=0.3,0.1

Type RM Length L Ch R = 1,5425,310,310,310
BEGIN DESCRIPTION:
Walnut36 13.0
END DESCRIPTION:
XS GIS Cut Line= 3
      2724846.98      6753647.05      2724649.46      6753767.76
      2724426.00      6753961.00
#Sta/Elev= 30
  4720.3  311.67  4738.2  310.23  4744.9  308.89  4790.4  304.28  4803.5  301.77
  4811.8  301.51  4838.9  297.43  4885.3  292.48  4927.9  290.97  4958.0  291.36
  4992.2  290.98  4998.8  286.26  5004.4  286.04  5004.7  285.54  5008.2  285.54
  5008.4  286.04  5013.0  290.06  5020.7  290.85  5027.3  291.21  5048.9  290.05
  5062.4  290.75  5070.1  291.82  5090.9  291.26  5108.3  291.70  5147.9  294.31
  5161.4  296.90  5211.6  302.51  5225.8  304.87  5233.5  307.80  5247.2  308.69
#Mann=6,-1,0
  4720.3     0.1       0  4958.0    0.12       0  5004.4    0.07       0
  5008.4    0.12       0  5108.3    0.05       0  5161.4    0.12       0
Bank Sta=5004.4,5008.4
Exp/Cntr=0.3,0.1

Type RM Length L Ch R = 1,5115,364,364,364
BEGIN DESCRIPTION:
Walnut36 12.0
END DESCRIPTION:
XS GIS Cut Line= 3
      2724757.40      6753581.18      2724572.63      6753555.57
      2724234.22      6753705.57
#Sta/Elev= 30
  4862.2  305.87  4893.9  303.92  4914.1  301.29  4934.3  300.34  4954.5  295.82
  4964.6  292.51  4971.2  288.78  4994.9  289.10  5005.0  285.15  5013.0  284.06
  5013.3  283.56  5017.0  284.06  5025.1  285.05  5035.2  284.32  5043.0  286.68
  5047.2  289.02  5050.2  286.68  5056.0  289.11  5096.7  288.22  5120.0  289.33
  5158.6  289.40  5172.0  291.26  5200.8  293.40  5218.6  293.47  5252.9  296.11
  5268.0  296.36  5317.1  296.63  5377.4  298.32  5406.0  297.33  5418.9  297.87
#Mann=6,-1,0
  4862.2     0.1       0  5013.0    0.07       0  5017.0     0.1       0
  5158.6    0.05       0  5268.0    0.12       0  5377.4    0.05       0
Bank Sta=5013,5017
Exp/Cntr=0.3,0.1

Type RM Length L Ch R = 1,4751,337,337,337
BEGIN DESCRIPTION:
Walnut36 11.0
END DESCRIPTION:
XS GIS Cut Line= 3
      2724594.60      6753277.54      2724459.23      6753283.02
      2724153.75      6753433.02
#Sta/Elev= 30
  4819.0  301.64  4827.6  300.84  4909.0  296.53  4917.7  295.85  4953.6  291.37
  4957.9  291.37  4962.4  284.12  4969.2  283.03  4979.4  284.18  4982.9  282.20
  4983.2  281.70  4986.7  281.70  4986.9  282.20  5001.8  282.77  5007.4  286.29
  5024.3  286.71  5036.1  285.74  5058.3  285.11  5069.3  285.29  5074.9  284.39
  5097.4  286.60  5170.4  287.42  5180.9  287.75  5187.3  288.62  5192.9  288.23
  5209.8  289.32  5225.5  289.70  5254.7  291.53  5270.0  293.41  5294.8  292.73
#Mann=4,-1,0
  4819.0    0.12       0  4909.0     0.1       0  4982.9    0.07       0
  4986.9     0.1       0
Bank Sta=4982.9,4986.9
Exp/Cntr=0.3,0.1

Type RM Length L Ch R = 1,4414,153,153,153
BEGIN DESCRIPTION:
Walnut36 10.0
END DESCRIPTION:
XS GIS Cut Line= 3
      2724448.28      6752953.76      2724226.00      6753061.00
      2723965.37      6753200.70
#Sta/Elev= 30
  4757.4  297.44  4758.2  297.44  4766.0  296.97  4831.8  294.06  4854.5  292.08
  4860.0  292.48  4871.0  291.39  4877.1  289.36  4905.2  285.50  4937.6  284.10
  4950.4  285.07  4959.8  284.87  4967.5  284.11  4971.1  280.43  4971.3  279.93
  4974.8  279.93  4975.1  280.43  4990.1  284.93  5007.0  284.89  5034.3  283.83
  5039.9  283.13  5049.6  283.28  5072.3  285.10  5138.2  285.37  5161.4  288.00
  5165.8  289.81  5174.4  291.26  5197.1  292.65  5286.1  290.80  5299.9  291.21
#Mann=6,-1,0
  4757.4     0.1       0  4758.2    0.12       0  4766.0     0.1       0
  4971.1    0.07       0  4975.1     0.1       0  5161.4    0.12       0
Bank Sta=4971.1,4975.1
Exp/Cntr=0.3,0.1