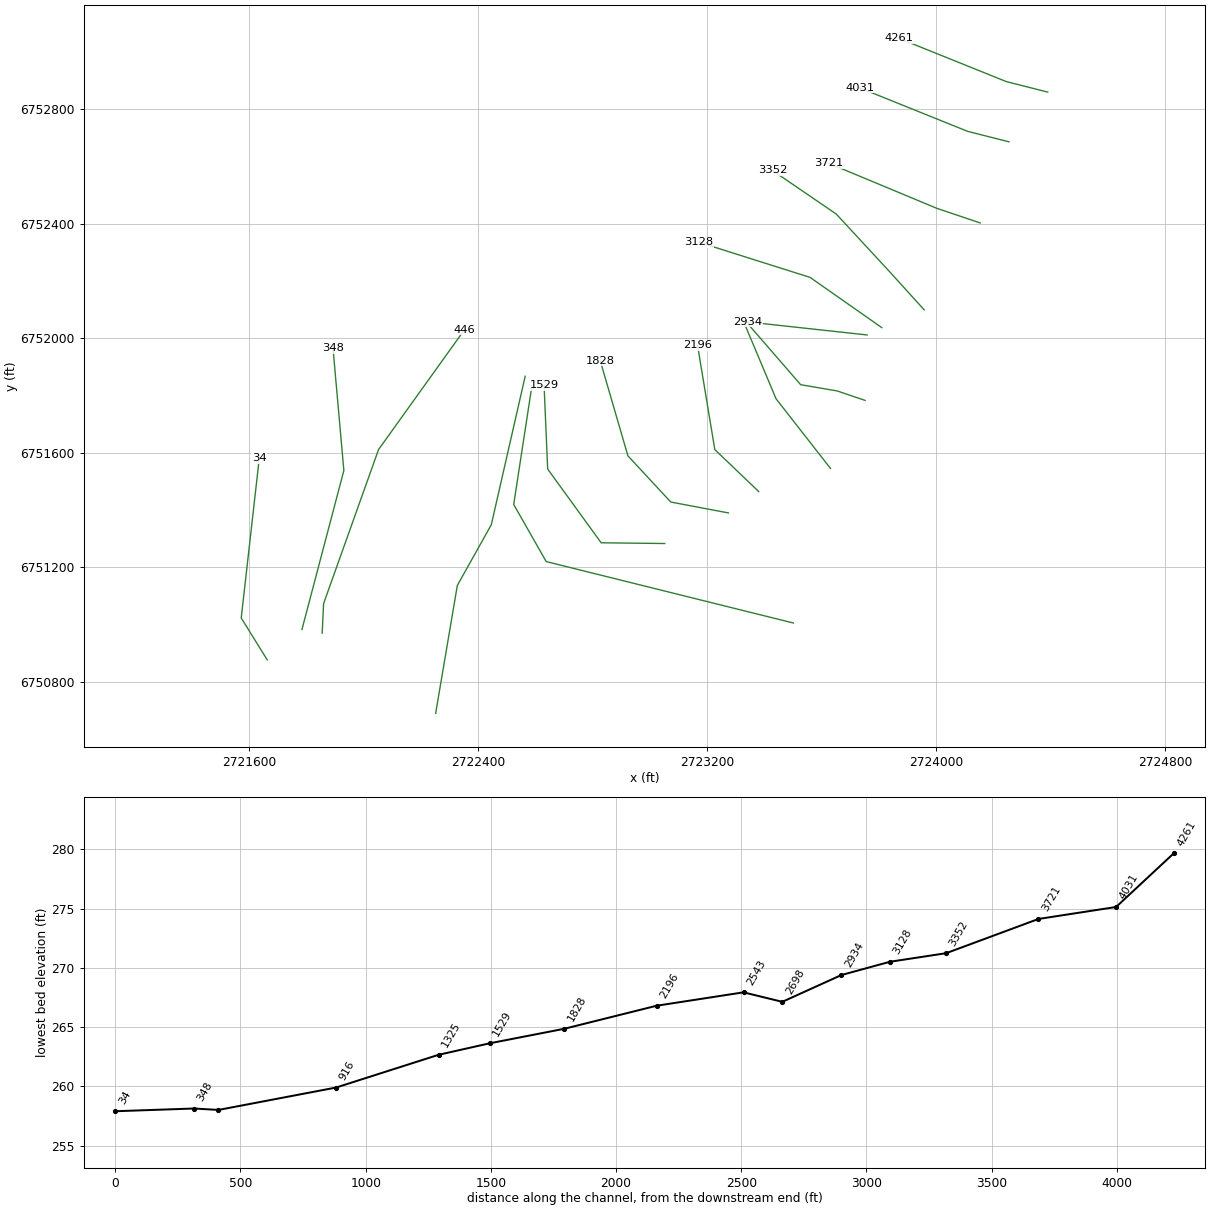
HEC-RAS study Walnut36.prj: Walnut36 Base Level Engineering

--- Walnut36.g01 (geometry) --- (continued)

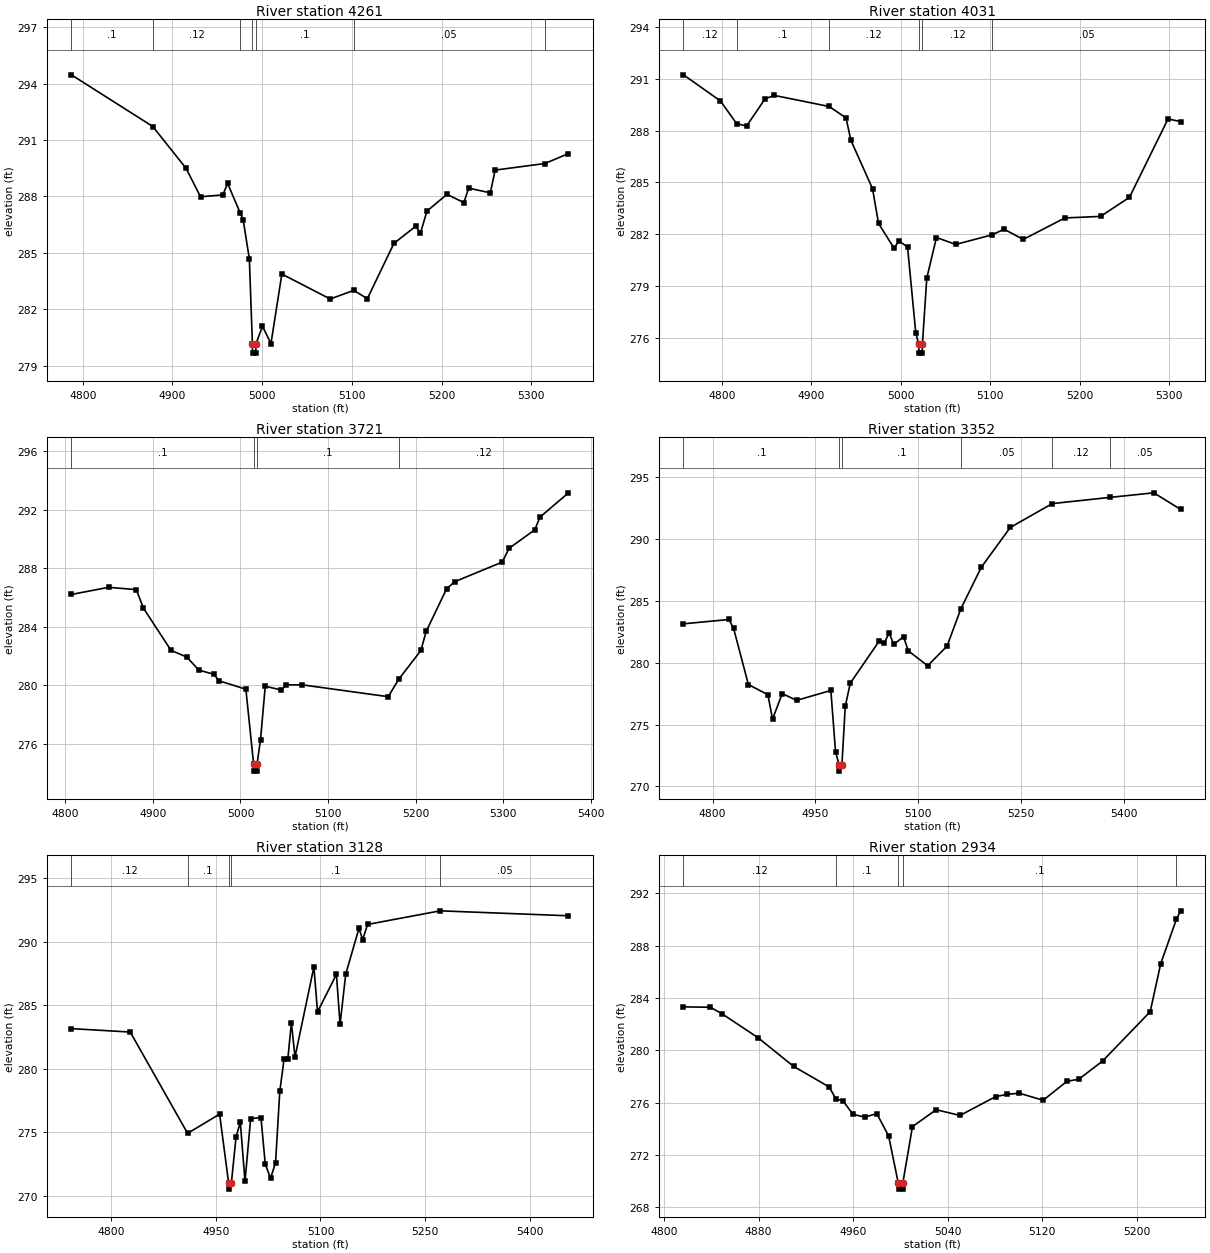
Type RM Length L Ch R = 1,4261,230,230,230
BEGIN DESCRIPTION:
Walnut36 9.5
END DESCRIPTION:
XS GIS Cut Line= 3
      2724389.75      6752860.47      2724245.21      6752897.07
      2723869.74      6753048.35
#Sta/Elev= 30
  4787.4  294.47  4878.1  291.72  4915.1  289.50  4931.3  287.98  4956.1  288.08
  4961.5  288.69  4975.4  287.13  4978.8  286.76  4985.7  284.67  4989.1  280.16
  4989.3  279.66  4992.8  279.66  4993.1  280.16  5000.3  281.09  5009.8  280.17
  5021.9  283.87  5075.8  282.54  5102.0  283.00  5117.2  282.56  5146.8  285.50
  5171.0  286.41  5176.3  286.04  5183.6  287.22  5205.9  288.11  5224.7  287.67
  5230.1  288.44  5254.2  288.19  5259.6  289.40  5315.0  289.75  5341.3  290.28
#Mann=7,-1,0
  4787.4     0.1       0  4878.1    0.12       0  4975.4     0.1       0
  4989.1    0.07       0  4993.1     0.1       0  5102.0    0.05       0
  5315.0    0.12       0
Bank Sta=4989.1,4993.1
Exp/Cntr=0.3,0.1

Type RM Length L Ch R = 1,4031,310,310,310
BEGIN DESCRIPTION:
Walnut36 9.0
END DESCRIPTION:
XS GIS Cut Line= 3
      2724254.36      6752686.71      2724109.85      6752723.29
      2723733.06      6752875.11
#Sta/Elev= 30
  4757.2  291.22  4798.5  289.71  4816.6  288.40  4827.7  288.26  4848.4  289.84
  4858.7  290.03  4920.0  289.39  4938.8  288.73  4944.2  287.44  4968.4  284.64
  4975.1  282.63  4992.5  281.20  4997.9  281.62  5007.5  281.27  5016.7  276.31
  5020.1  275.64  5020.3  275.14  5023.8  275.14  5024.1  275.64  5029.0  279.47
  5039.8  281.82  5061.4  281.42  5102.3  281.98  5115.3  282.30  5136.8  281.71
  5183.2  282.95  5223.1  283.04  5255.4  284.14  5298.5  288.67  5312.5  288.52
#Mann=6,-1,0
  4757.2    0.12       0  4816.6     0.1       0  4920.0    0.12       0
  5020.1    0.07       0  5024.1    0.12       0  5102.3    0.05       0
Bank Sta=5020.1,5024.1
Exp/Cntr=0.3,0.1

Type RM Length L Ch R = 1,3721,369,369,369
BEGIN DESCRIPTION:
Walnut36 8.0
END DESCRIPTION:
XS GIS Cut Line= 3
      2724153.78      6752403.18      2724001.93      6752454.40
      2723626.00      6752611.00
#Sta/Elev= 30
  4807.0  286.21  4849.6  286.70  4881.1  286.54  4889.1  285.29  4920.7  282.39
  4938.8  281.93  4952.4  281.04  4969.8  280.75  4975.3  280.31  5006.2  279.73
  5015.0  274.63  5015.3  274.13  5018.8  274.13  5019.0  274.63  5022.9  276.27
  5028.3  279.93  5046.8  279.68  5052.2  280.03  5070.6  280.03  5168.7  279.22
  5180.7  280.41  5206.0  282.38  5212.0  283.68  5235.3  286.59  5244.5  287.08
  5298.7  288.42  5306.8  289.37  5336.0  290.63  5342.0  291.50  5374.5  293.16
#Mann=4,-1,0
  4807.0     0.1       0  5015.0    0.07       0  5019.0     0.1       0
  5180.7    0.12       0
Bank Sta=5015,5019
Exp/Cntr=0.3,0.1

Type RM Length L Ch R = 1,3352,224,224,224
BEGIN DESCRIPTION:
Walnut36 7.0
END DESCRIPTION:
XS GIS Cut Line= 4
      2723958.03      6752099.54      2723833.64      6752236.73
      2723650.66      6752434.36      2723427.19      6752586.94
#Sta/Elev= 30
  4757.6  283.15  4824.0  283.50  4830.7  282.78  4852.3  278.24  4880.7  277.42
  4887.5  275.44  4901.7  277.51  4922.6  276.96  4972.6  277.76  4979.4  272.81
  4984.7  271.74  4985.0  271.24  4988.7  271.74  4993.6  276.48  5000.9  278.35
  5043.4  281.78  5050.3  281.57  5057.6  282.41  5064.4  281.48  5078.6  282.12
  5085.4  280.97  5113.8  279.76  5142.1  281.35  5162.1  284.35  5192.0  287.72
  5234.3  290.94  5295.6  292.87  5379.5  293.37  5443.7  293.74  5482.7  292.40
#Mann=6,-1,0
  4757.6     0.1       0  4984.7    0.07       0  4988.7     0.1       0
  5162.1    0.05       0  5295.6    0.12       0  5379.5    0.05       0
Bank Sta=4984.7,4988.7
Exp/Cntr=0.3,0.1

Type RM Length L Ch R = 1,3128,194,194,194
BEGIN DESCRIPTION:
Walnut36 6.5
END DESCRIPTION:
XS GIS Cut Line= 3
      2723809.83      6752037.37      2723559.27      6752212.95
      2723171.43      6752335.52
#Sta/Elev= 30
  4742.9  283.15  4827.3  282.88  4909.5  274.91  4955.4  276.42  4968.3  271.02
  4968.5  270.52  4972.3  271.02  4979.0  274.64  4985.1  275.78  4991.8  271.13
  4999.9  276.07  5014.7  276.15  5020.8  272.51  5028.4  271.37  5035.6  272.59
  5041.7  278.22  5047.8  280.75  5053.2  280.75  5058.3  283.60  5063.5  280.92
  5090.6  288.01  5095.8  284.47  5122.9  287.42  5128.1  283.48  5136.2  287.43
  5155.2  291.04  5160.5  290.16  5167.6  291.35  5271.6  292.42  5455.6  292.03
#Mann=5,-1,0
  4742.9    0.12       0  4909.5     0.1       0  4968.3    0.07       0
  4972.3     0.1       0  5271.6    0.05       0
Bank Sta=4968.3,4972.3
Exp/Cntr=0.3,0.1

Type RM Length L Ch R = 1,2934,236,236,236
BEGIN DESCRIPTION:
Walnut36 6.0
END DESCRIPTION:
XS GIS Cut Line= 2
      2723758.62      6752011.74      2723340.40      6752057.40
#Sta/Elev= 30
  4816.5  283.33  4839.3  283.30  4849.3  282.79  4879.5  280.98  4909.7  278.78
  4939.8  277.21  4945.5  276.29  4951.4  276.16  4960.0  275.11  4970.0  274.91
  4980.1  275.17  4990.1  273.47  4998.2  269.90  4998.5  269.40  5002.0  269.40
  5002.2  269.90  5010.3  274.18  5030.4  275.47  5050.5  275.03  5080.7  276.47
  5090.7  276.65  5100.8  276.73  5120.9  276.19  5141.0  277.64  5151.1  277.80
  5171.2  279.19  5211.5  282.96  5220.4  286.63  5233.7  290.03  5237.2  290.67
#Mann=5,-1,0
  4816.5    0.12       0  4945.5     0.1       0  4998.2    0.07       0
  5002.2     0.1       0  5233.7    0.05       0
Bank Sta=4998.2,5002.2
Exp/Cntr=0.3,0.1

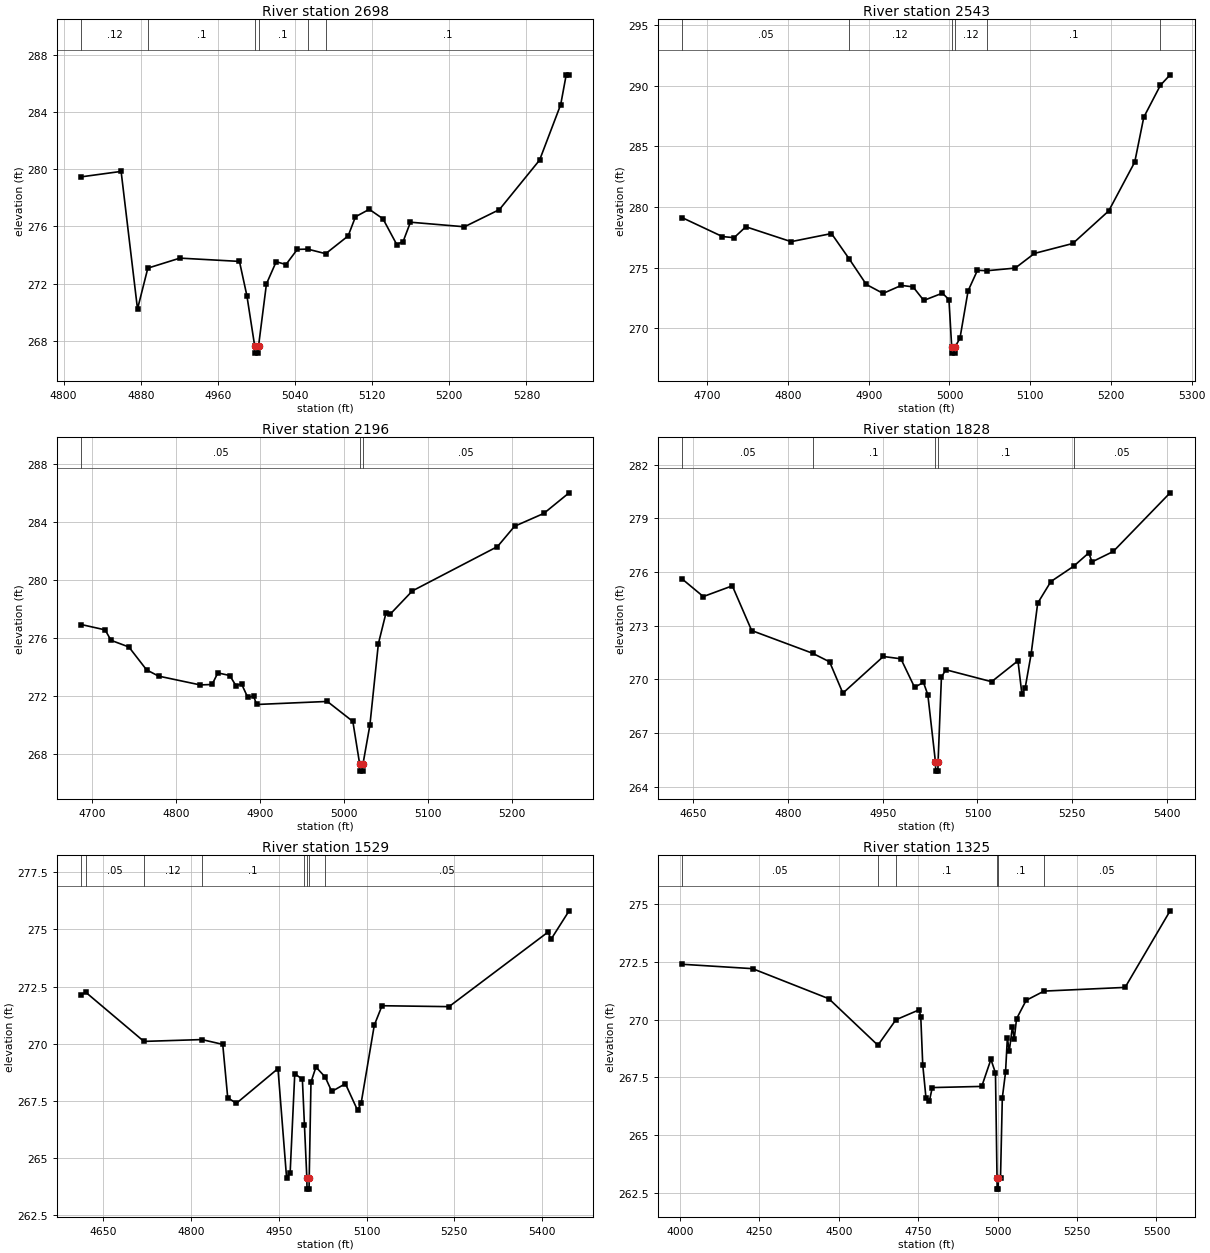
Type RM Length L Ch R = 1,2698,155,155,155
BEGIN DESCRIPTION:
Walnut36 5.5
END DESCRIPTION:
XS GIS Cut Line= 4
      2723751.33      6751783.09      2723654.38      6751816.02
      2723526.34      6751837.97      2723347.08      6752044.67
#Sta/Elev= 30
  4818.3  279.46  4859.7  279.84  4876.7  270.22  4887.4  273.08  4920.7  273.78
  4982.4  273.55  4990.1  271.16  4998.2  267.64  4998.5  267.14  5002.0  267.14
  5002.2  267.64  5010.4  271.98  5020.5  273.53  5030.6  273.33  5042.4  274.39
  5053.1  274.41  5071.8  274.09  5095.1  275.33  5102.7  276.67  5117.0  277.19
  5131.2  276.53  5145.5  274.73  5152.1  274.94  5159.7  276.29  5215.7  275.97
  5251.9  277.17  5293.6  280.63  5315.5  284.51  5321.2  286.59  5324.2  286.59
#Mann=6,-1,0
  4818.3    0.12       0  4887.4     0.1       0  4998.2    0.07       0
  5002.2     0.1       0  5053.1    0.12       0  5071.8     0.1       0
Bank Sta=4998.2,5002.2
Exp/Cntr=0.3,0.1

Type RM Length L Ch R = 1,2543,347,347,347
BEGIN DESCRIPTION:
Walnut36 5.0
END DESCRIPTION:
XS GIS Cut Line= 3
      2723630.60      6751545.31      2723440.37      6751788.58
      2723325.99      6752061.03
#Sta/Elev= 30
  4669.0  279.12  4718.8  277.56  4733.3  277.47  4747.8  278.37  4803.9  277.14
  4853.9  277.81  4875.5  275.75  4897.0  273.61  4917.8  272.87  4940.4  273.53
  4954.9  273.41  4968.2  272.29  4991.3  272.89  4999.4  272.35  5002.8  268.44
  5003.0  267.94  5006.5  267.94  5006.8  268.44  5013.0  269.16  5023.1  273.08
  5034.7  274.78  5046.2  274.74  5081.5  274.96  5105.3  276.17  5152.8  276.99
  5197.3  279.68  5229.5  283.71  5240.7  287.41  5261.3  290.05  5273.3  290.91
#Mann=6,-1,0
  4669.0    0.05       0  4875.5    0.12       0  5002.8    0.07       0
  5006.8    0.12       0  5046.2     0.1       0  5261.3    0.05       0
Bank Sta=5002.8,5006.8
Exp/Cntr=0.3,0.1

Type RM Length L Ch R = 1,2196,368,368,368
BEGIN DESCRIPTION:
Walnut36 4.5
END DESCRIPTION:
XS GIS Cut Line= 3
      2723379.75      6751464.48      2723226.35      6751611.15
      2723165.99      6751975.15
#Sta/Elev= 30
  4687.0  276.93  4715.5  276.56  4722.5  275.84  4743.8  275.38  4764.9  273.80
  4779.1  273.37  4828.8  272.76  4842.9  272.79  4849.8  273.59  4864.0  273.41
  4871.2  272.72  4878.1  272.82  4885.4  271.90  4892.3  271.99  4896.0  271.41
  4980.2  271.62  5010.6  270.24  5018.7  267.31  5019.0  266.81  5022.5  266.81
  5022.7  267.31  5030.9  269.98  5041.0  275.60  5050.1  277.73  5055.2  277.65
  5081.5  279.25  5182.9  282.31  5203.2  283.71  5238.1  284.60  5268.2  286.02
#Mann=3,-1,0
  4687.0    0.05       0  5018.7    0.04       0  5022.7    0.05       0
Bank Sta=5018.7,5022.7
Exp/Cntr=0.3,0.1

Type RM Length L Ch R = 1,1828,299,299,299
BEGIN DESCRIPTION:
Walnut36 4.0
END DESCRIPTION:
XS GIS Cut Line= 4
      2723273.95      6751389.81      2723072.46      6751427.88
      2722922.71      6751589.20      2722825.77      6751922.10
#Sta/Elev= 30
  4632.9  275.61  4666.3  274.63  4712.2  275.23  4742.8  272.73  4839.2  271.46
  4866.1  270.98  4887.1  269.23  4951.1  271.28  4978.9  271.15  5000.5  269.56
  5014.6  269.83  5021.5  269.14  5033.6  265.37  5033.9  264.87  5037.4  264.87
  5037.7  265.37  5043.0  270.11  5049.8  270.54  5122.4  269.87  5164.1  271.04
  5170.4  269.16  5175.6  269.54  5184.9  271.41  5195.3  274.26  5216.2  275.47
  5252.0  276.32  5276.1  277.07  5281.3  276.57  5314.8  277.15  5404.8  280.43
#Mann=5,-1,0
  4632.9    0.05       0  4839.2     0.1       0  5033.6    0.07       0
  5037.7     0.1       0  5252.0    0.05       0
Bank Sta=5033.6,5037.7
Exp/Cntr=0.3,0.1

Type RM Length L Ch R = 1,1529,204,204,204
BEGIN DESCRIPTION:
Walnut36 2.5
END DESCRIPTION:
XS GIS Cut Line= 4
      2723051.44      6751282.94      2722829.16      6751285.47
      2722642.25      6751543.10      2722629.62      6751836.04
#Sta/Elev= 30
  4612.4  272.15  4620.6  272.24  4719.6  270.10  4818.6  270.18  4854.3  269.97
  4862.8  267.64  4877.5  267.39  4948.7  268.91  4963.4  264.14  4969.5  264.36
  4977.4  268.69  4990.4  268.44  4993.9  266.46  4998.0  264.14  4998.3  263.64
  5001.8  263.64  5002.1  264.14  5005.1  268.32  5013.6  268.98  5029.4  268.54
  5040.6  267.91  5063.9  268.25  5084.7  267.09  5090.9  267.41  5113.3  270.81
  5126.5  271.66  5241.0  271.62  5410.2  274.88  5415.2  274.56  5446.2  275.81
#Mann=8,-1,0
  4612.4    0.12       0  4620.6    0.05       0  4719.6    0.12       0
  4818.6     0.1       0  4993.9    0.12       0  4998.0    0.07       0
  5002.1    0.12       0  5029.4    0.05       0
Bank Sta=4998,5002.1
Exp/Cntr=0.3,0.1

Type RM Length L Ch R = 1,1325,409,409,409
BEGIN DESCRIPTION:
Walnut36 2.0
END DESCRIPTION:
XS GIS Cut Line= 4
      2723501.07      6751005.09      2722637.20      6751219.79
      2722523.54      6751419.34      2722586.68      6751831.02
#Sta/Elev= 30
  4006.7  272.39  4228.3  272.20  4468.5  270.90  4622.9  268.89  4679.6  269.99
  4752.7  270.42  4757.9  270.12  4764.1  268.05  4774.4  266.60  4784.7  266.46
  4794.1  267.06  4949.9  267.11  4978.8  268.28  4993.1  267.69  4998.0  263.17
  4998.3  262.67  5001.8  262.67  5002.1  263.17  5009.0  263.17  5014.7  266.62
  5024.8  267.72  5030.6  269.22  5036.4  268.62  5046.5  269.69  5052.2  269.15
  5059.4  270.03  5089.7  270.83  5146.0  271.23  5401.3  271.39  5543.0  274.70
#Mann=6,-1,0
  4006.7    0.05       0  4622.9    0.12       0  4679.6     0.1       0
  4998.0    0.07       0  5002.1     0.1       0  5146.0    0.05       0
Bank Sta=4998,5002.1
Exp/Cntr=0.3,0.1

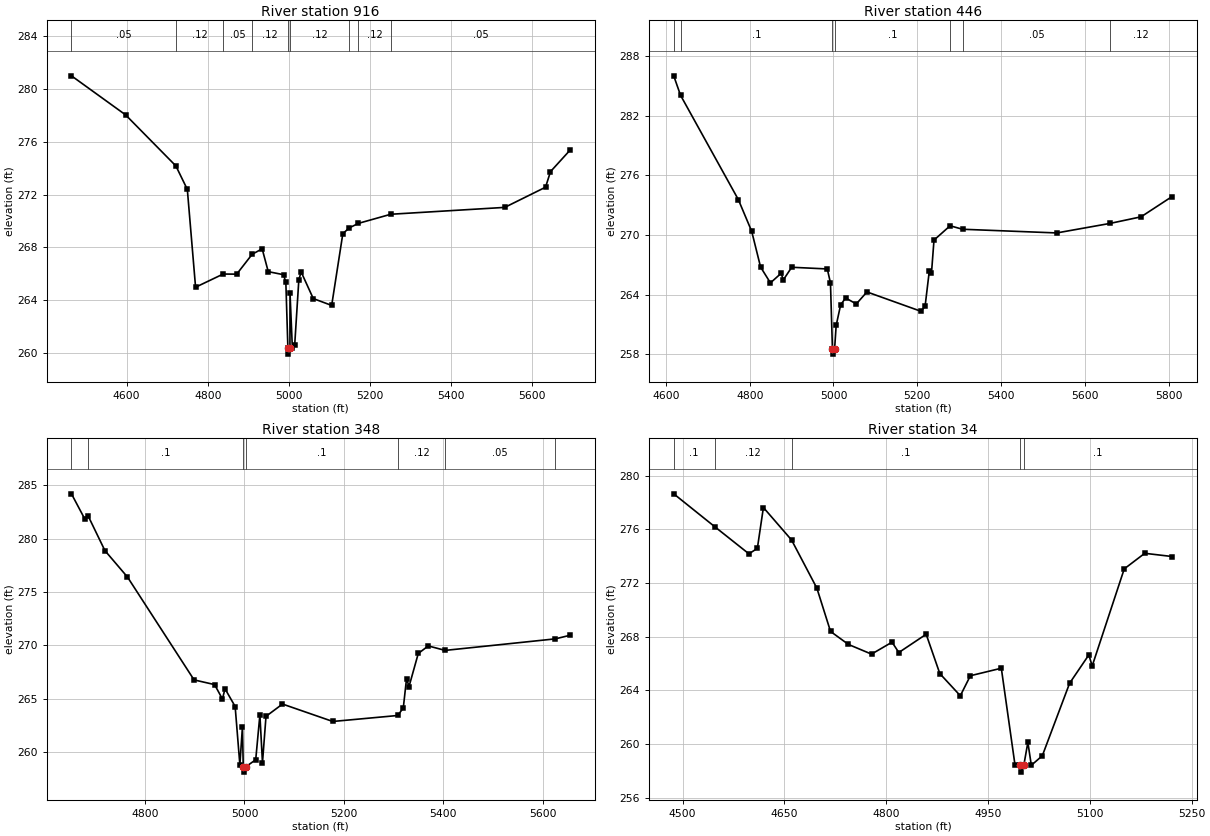
Type RM Length L Ch R = 1,916,470,470,470
BEGIN DESCRIPTION:
Walnut36 1.6
END DESCRIPTION:
XS GIS Cut Line= 4
      2722250.74      6750689.35      2722326.52      6751136.44
      2722445.24      6751348.61      2722563.62      6751867.48
#Sta/Elev= 30
  4463.9  281.00  4597.4  278.04  4721.4  274.17  4749.6  272.39  4769.9  264.98
  4838.0  265.98  4871.3  265.97  4909.5  267.48  4934.1  267.89  4949.1  266.16
  4986.8  265.93  4992.5  265.34  4997.5  260.41  4998.1  259.91  5002.6  260.41
  5002.8  264.51  5008.5  260.41  5014.3  260.60  5024.5  265.54  5030.2  266.14
  5060.1  264.12  5105.5  263.60  5133.0  269.04  5149.0  269.48  5171.5  269.82
  5251.3  270.51  5532.2  271.03  5632.8  272.56  5645.0  273.74  5692.7  275.35
#Mann=9,-1,0
  4463.9    0.05       0  4721.4    0.12       0  4838.0    0.05       0
  4909.5    0.12       0  4997.5    0.07       0  5002.6    0.12       0
  5149.0    0.05       0  5171.5    0.12       0  5251.3    0.05       0
Bank Sta=4997.5,5002.6
Exp/Cntr=0.3,0.1

Type RM Length L Ch R = 1,446,98,98,98
BEGIN DESCRIPTION:
Walnut36 1.3
END DESCRIPTION:
XS GIS Cut Line= 4
      2721854.19      6750969.77      2721859.24      6751073.29
      2722051.20      6751611.30      2722351.39      6752030.04
#Sta/Elev= 30
  4618.5  285.99  4634.7  284.04  4772.8  273.55  4804.7  270.36  4825.9  266.77
  4849.4  265.18  4874.9  266.14  4880.2  265.48  4900.2  266.75  4985.2  266.58
  4992.8  265.17  4997.5  258.52  4998.1  258.02  5002.6  258.52  5006.4  260.90
  5017.0  262.96  5028.9  263.67  5054.4  263.06  5079.9  264.27  5208.5  262.33
  5218.7  262.82  5228.7  266.34  5234.0  266.17  5240.0  269.48  5278.5  270.92
  5308.2  270.57  5533.1  270.20  5660.7  271.16  5734.5  271.82  5808.6  273.86
#Mann=7,-1,0
  4618.5    0.05       0  4634.7     0.1       0  4997.5    0.07       0
  5002.6     0.1       0  5278.5    0.12       0  5308.2    0.05       0
  5660.7    0.12       0
Bank Sta=4997.5,5002.6
Exp/Cntr=0.3,0.1

Type RM Length L Ch R = 1,348,314,314,314
BEGIN DESCRIPTION:
Walnut36 1.2
END DESCRIPTION:
XS GIS Cut Line= 3
      2721783.47      6750982.38      2721929.96      6751538.05
      2721892.08      6751964.91
#Sta/Elev= 30
  4651.7  284.18  4678.7  281.81  4685.5  282.09  4719.0  278.87  4764.5  276.39
  4898.5  266.77  4939.8  266.33  4955.6  264.98  4960.8  265.94  4981.2  264.28
  4990.7  258.82  4995.9  262.40  4997.5  258.64  4998.1  258.14  5002.6  258.64
  5022.6  259.30  5031.0  263.50  5036.2  259.02  5043.3  263.36  5076.5  264.51
  5177.7  262.88  5308.7  263.44  5319.7  264.16  5326.2  266.89  5331.2  266.15
  5349.8  269.24  5369.9  269.95  5403.9  269.53  5625.7  270.61  5654.9  270.94
#Mann=7,-1,0
  4651.7    0.05       0  4685.5     0.1       0  4997.5    0.07       0
  5002.6     0.1       0  5308.7    0.12       0  5403.9    0.05       0
  5625.7    0.12       0
Bank Sta=4997.5,5002.6
Exp/Cntr=0.3,0.1

Type RM Length L Ch R = 1,34,0,0,0
BEGIN DESCRIPTION:
Walnut36 1.0
END DESCRIPTION:
XS GIS Cut Line= 3
      2721662.20      6750876.31      2721571.29      6751022.78
      2721634.44      6751581.03
#Sta/Elev= 30
  4486.9  278.64  4547.1  276.20  4597.7  274.17  4610.1  274.58  4619.0  277.62
  4660.5  275.20  4697.8  271.61  4717.9  268.39  4744.3  267.42  4778.3  266.70
  4808.5  267.59  4818.5  266.82  4858.8  268.18  4878.9  265.25  4909.1  263.60
  4923.9  265.09  4969.5  265.65  4989.6  258.46  4997.5  258.41  4998.1  257.91
  5002.6  258.41  5008.6  260.13  5013.7  258.42  5029.9  259.13  5070.1  264.53
  5098.4  266.64  5103.4  265.82  5150.6  273.05  5180.8  274.21  5221.1  273.97
#Mann=5,-1,0
  4486.9     0.1       0  4547.1    0.12       0  4660.5     0.1       0
  4997.5    0.07       0  5002.6     0.1       0
Bank Sta=4997.5,5002.6
Exp/Cntr=0.3,0.1

Chan Stop Cuts=-1