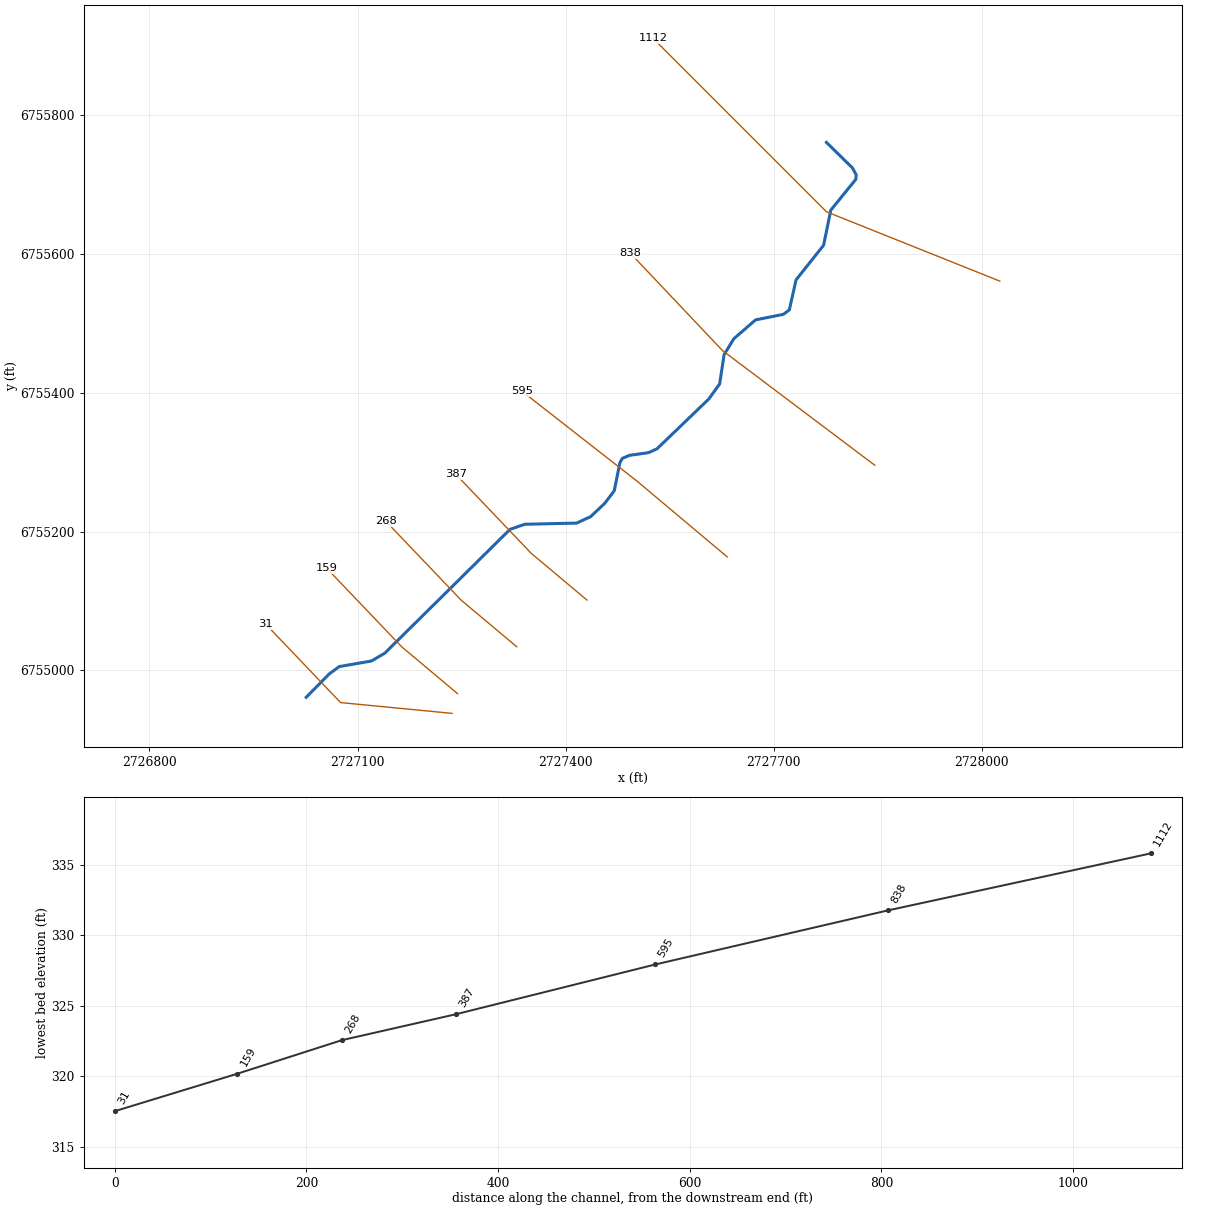
--- Walnut38.prj (project) ---

Proj Title=Walnut38 Base Level Engineering
Current Plan=p01
Default Exp/Contr=0.3,0.1
English Units
Geom File=g01
Flow File=f01
Plan File=p01
Y Axis Title=Elevation
X Axis Title(PF)=Main Channel Distance
X Axis Title(XS)=Station
BEGIN DESCRIPTION:
Walnut38
END DESCRIPTION:
DSS Export Rating Curves= 0
DSS Export Rating Curve Sorted= 0
DSS Export Volume Flow Curves= 0
DXF OffsetX= 0
DXF OffsetY= 0
DXF ScaleX= 1
DXF ScaleY= 10

--- Walnut38.p01 (plan) ---

Plan Title=Multiple Run
Program Version=4.10
Short Identifier=Multiple
Geom File=g01
Flow File=f01
Subcritical Flow
K Sum by GR= 0
Std Step Tol= 0.01
Critical Tol= 0.01
Num of Std Step Trials= 20
Max Error Tol= 0.3
Flow Tol Ratio= 0.001
Split Flow NTrial= 30
Split Flow Tol= 0.02
Split Flow Ratio= 0.02
Log Output Level= 0
Friction Slope Method= 1
Unsteady Friction Slope Method= 2
Unsteady Bridges Friction Slope Method= 1
Parabolic Critical Depth
Global Vel Dist= 1 , 1 , 1
Global Log Level= 0
CheckData=True
Encroach Param=-1 ,0,0, 0
BEGIN DESCRIPTION:
Multiple Run
END DESCRIPTION:
Computation Interval=1HOUR
Output Interval=1HOUR
Run HTab= 0
Run UNet= 0
Run PostProcess= 0
Run WQNet= 0
UNET Theta= 1
UNET Theta Warmup= 1
UNET ZTol= 0.02
UNET ZSATol= 0.05
UNET MxIter= 20
UNET MaxInSteps= 0
UNET DtIC= 0
UNET DtMin= 0
UNET MaxCRTS= 20
UNET WFStab= 2
UNET SFStab= 1
UNET WFX= 1
UNET SFX= 1
UNET DSS MLevel= 4
UNET DZMax Abort= 100
UNET Convert EG Bridges= 0
UNET Use Existing IB Tables=-1
UNET Froude Reduction=False
UNET Froude Limit= 1
UNET Froude Power= 10
UNET Time Slicing=0,0, 5
UNET Junction Losses=0
Instantaneous Interval=1HOUR
Write IC File= 0
Write IC File at Sim End=0
Echo Input=False
Echo Parameters=False
Echo Output=False
Write Detailed= 0
WQ AD Non Conservative
WQ ULTIMATE=-1
WQ Max Comp Step=1HOUR
WQ Output Interval=15MIN
WQ Output Selected Increments= 0
WQ Output face flow=0
WQ Output face velocity=0
WQ Output face area=0
WQ Output face dispersion=0
WQ Output cell volume=0
WQ Output cell surface area=0
WQ Output cell continuity=0
WQ Output cumulative cell continuity=0
WQ Output face conc=0
WQ Output face dconc_dx=0
WQ Output face courant=0
WQ Output face peclet=0
WQ Output face adv mass=0
WQ Output face disp mass=0
WQ Output cell mass=0
WQ Output cell source sink temp=0
WQ Output cell source sink nsm=0
WQ Output MaxMinRange=-1
WQ Daily Max Min Mean=-1
WQ Daily Range=0
WQ Daily Time=0
WQ Create Restart=0
WQ Fixed Restart=0
WQ System Summary=0
WQ Use Fixed Temperature=0
Sorting and Armoring Iterations= 10
XS Update Threshold= 0.02
Hydraulics Update Threshold= 0.02
Energy Slope Method= 1
Volume Change Method= 0
XS Weighting Method= 0
Number of US Weighted Cross Sections= 1
Number of DS Weighted Cross Sections= 1
Upstream XS Weight=0.25
Main XS Weight=0.5
Downstream XS Weight=0.25
Number of DS XS's Weighted with US Boundary= 1
Upstream Boundary Weight= 1
Weight of XSs Associated with US Boundary= 0
Number of US XS's Weighted with DS Boundary= 1
Downstream Boundary Weight= 0.5
Weight of XSs Associated with DS Boundary= 0.5
Sediment Output Level= 4
Mass or Volume Output= 0
Output Increment Type= 1
Profile and TS Output Increment= 10
XS Output Flag= 0
XS Output Increment= 10
Disregard all LS=0
Disregard all Conn=0
Disregard all Breaches=0
Disregard all Pumps=0

--- Walnut38.f01 (steady flow) ---

Flow Title=Multiple
Number of Profiles=7
Profile Names=10-year,25-year,50-year,1pct_min,100-year,1pct_plu,500-year
River Rch & RM= Walnut38,Reach-1,1112
      68      78      86      47      95     189     114
River Rch & RM= Walnut38,Reach-1,31
     173     216     248     142     284     566     371
Boundary for River Rch & Prof#=Walnut38,Reach-1,1
Up Type=0
Dn Type=3
Dn Slope=0.02
Boundary for River Rch & Prof#=Walnut38,Reach-1,2
Up Type=0
Dn Type=3
Dn Slope=0.02
Boundary for River Rch & Prof#=Walnut38,Reach-1,3
Up Type=0
Dn Type=3
Dn Slope=0.02
Boundary for River Rch & Prof#=Walnut38,Reach-1,4
Up Type=0
Dn Type=3
Dn Slope=0.02
Boundary for River Rch & Prof#=Walnut38,Reach-1,5
Up Type=0
Dn Type=3
Dn Slope=0.02
Boundary for River Rch & Prof#=Walnut38,Reach-1,6
Up Type=0
Dn Type=3
Dn Slope=0.02
Boundary for River Rch & Prof#=Walnut38,Reach-1,7
Up Type=0
Dn Type=3
Dn Slope=0.02

--- Walnut38.g01 (geometry) ---

Geom Title=Existing Conditions

River Reach=Walnut38,Reach-1
Reach XY= 30
      2727776.00      6755761.00      2727813.33      6755724.40
      2727818.80      6755714.44      2727818.42      6755707.80
      2727782.27      6755663.31      2727771.89      6755612.70
      2727732.24      6755562.86      2727722.46      6755519.49
      2727713.94      6755513.14      2727673.80      6755505.11
      2727642.58      6755478.01      2727628.48      6755455.12
      2727622.02      6755412.66      2727606.22      6755390.88
      2727531.77      6755319.27      2727519.58      6755313.69
      2727492.05      6755309.83      2727481.64      6755305.35
      2727478.15      6755298.92      2727470.12      6755258.76
      2727456.34      6755240.60      2727436.08      6755221.44
      2727415.66      6755212.12      2727341.22      6755210.47
      2727319.83      6755203.14      2727139.23      6755024.57
      2727120.03      6755013.34      2727073.65      6755005.29
      2727059.08      6754994.58      2727026.00      6754961.00

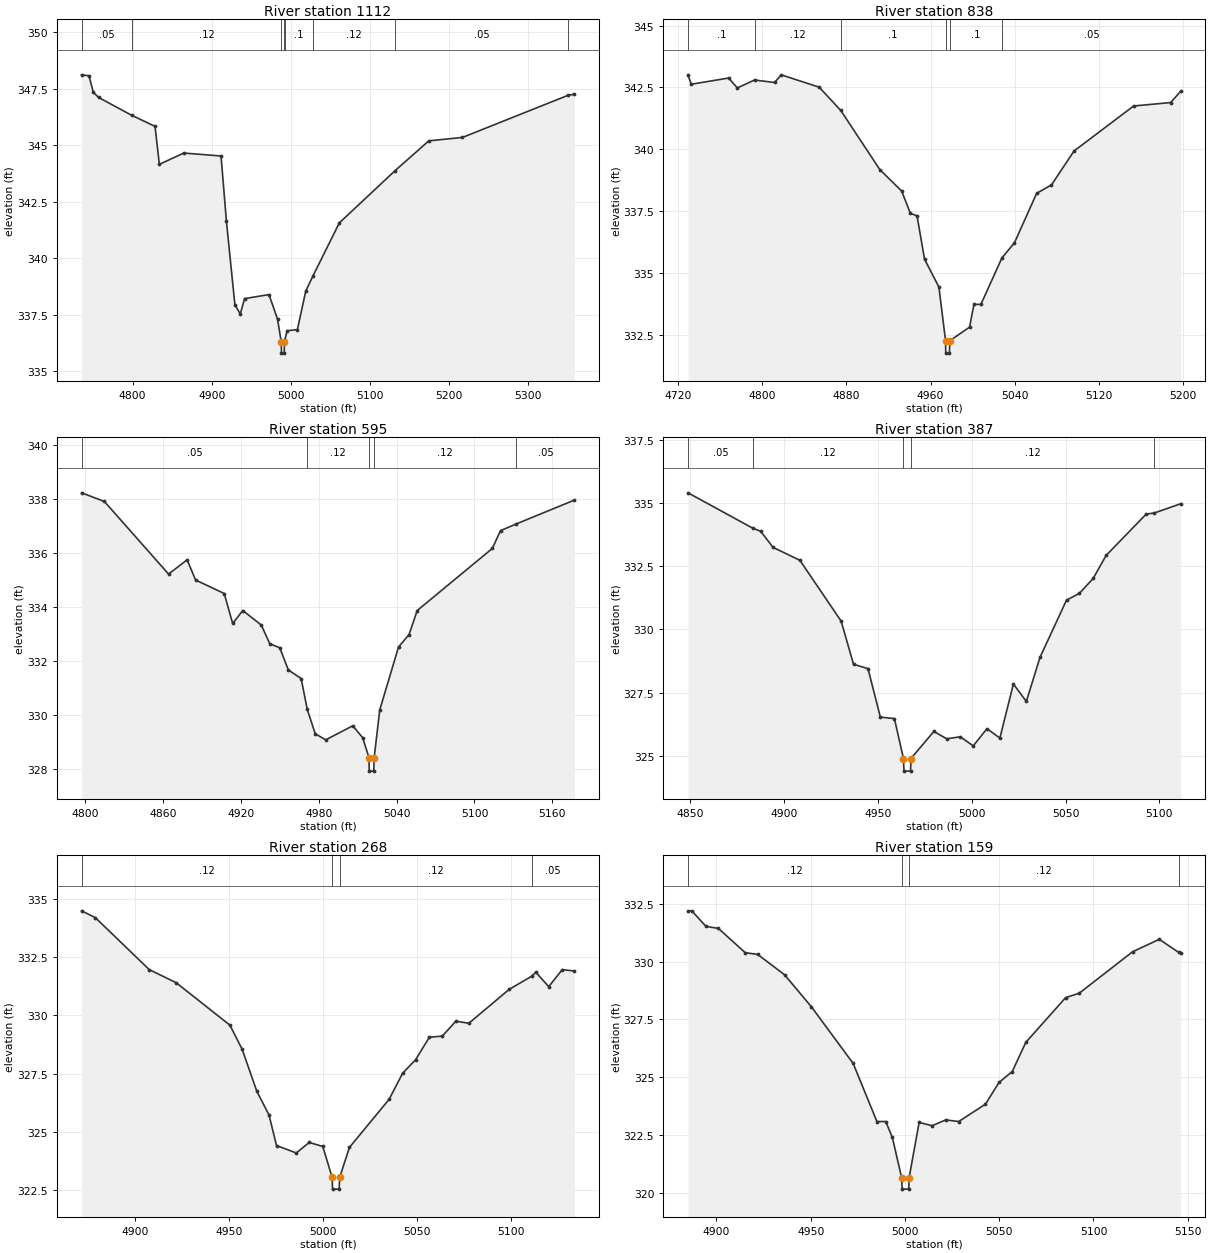
Type RM Length L Ch R = 1,1112,274,274,274
BEGIN DESCRIPTION:
Walnut38 4.0
END DESCRIPTION:
XS GIS Cut Line= 3
      2728025.97      6755561.01      2727776.00      6755661.00
      2727525.99      6755911.01
#Sta/Elev= 30
  4735.4  348.11  4744.8  348.07  4750.2  347.34  4756.9  347.11  4798.8  346.32
  4828.3  345.83  4833.7  344.15  4864.6  344.65  4911.7  344.52  4918.5  341.63
  4929.2  337.94  4936.0  337.53  4941.4  338.21  4972.3  338.39  4983.1  337.30
  4987.8  336.30  4988.1  335.80  4991.6  335.80  4991.8  336.30  4992.3  336.37
  4995.2  336.79  5008.2  336.84  5018.8  338.55  5028.1  339.23  5061.2  341.56
  5131.6  343.87  5174.3  345.19  5216.8  345.34  5350.7  347.21  5358.2  347.25
#Mann=8,-1,0
  4735.4    0.05       0  4798.8    0.12       0  4987.8    0.07       0
  4991.8    0.12       0  4992.3     0.1       0  5028.1    0.12       0
  5131.6    0.05       0  5350.7    0.12       0
Bank Sta=4987.8,4991.8
Exp/Cntr=0.3,0.1

Type RM Length L Ch R = 1,838,243,243,243
BEGIN DESCRIPTION:
Walnut38 3.0
END DESCRIPTION:
XS GIS Cut Line= 3
      2727845.61      6755295.62      2727626.00      6755461.00
      2727493.01      6755601.54
#Sta/Elev= 30
  4729.5  342.99  4732.7  342.63  4768.1  342.88  4776.4  342.48  4792.7  342.80
  4811.8  342.70  4818.1  343.01  4854.2  342.51  4874.7  341.57  4911.8  339.18
  4932.6  338.31  4940.9  337.41  4947.2  337.31  4954.3  335.56  4968.0  334.43
  4974.3  332.26  4974.5  331.76  4978.0  331.76  4978.3  332.26  4997.1  332.81
  5001.3  333.73  5007.9  333.73  5027.9  335.61  5039.8  336.22  5060.9  338.22
  5075.0  338.56  5096.4  339.93  5153.1  341.75  5188.3  341.89  5197.9  342.35
#Mann=6,-1,0
  4729.5     0.1       0  4792.7    0.12       0  4874.7     0.1       0
  4974.3    0.07       0  4978.3     0.1       0  5027.9    0.05       0
Bank Sta=4974.3,4978.3
Exp/Cntr=0.3,0.1

Type RM Length L Ch R = 1,595,208,208,208
BEGIN DESCRIPTION:
Walnut38 2.0
END DESCRIPTION:
XS GIS Cut Line= 3
      2727632.99      6755163.39      2727503.36      6755272.29
      2727337.40      6755401.94
#Sta/Elev= 30
  4797.1  338.23  4814.7  337.91  4864.2  335.22  4878.5  335.75  4885.0  335.00
  4907.1  334.50  4913.6  333.39  4921.4  333.87  4935.7  333.33  4942.2  332.64
  4949.9  332.49  4956.5  331.67  4966.4  331.35  4971.1  330.21  4977.3  329.30
  4985.4  329.08  5006.2  329.60  5013.8  329.16  5018.7  328.42  5018.9  327.92
  5022.4  327.92  5022.7  328.42  5027.0  330.19  5041.5  332.52  5049.6  332.98
  5055.9  333.87  5113.8  336.17  5120.1  336.83  5132.4  337.08  5177.0  337.96
#Mann=5,-1,0
  4797.1    0.05       0  4971.1    0.12       0  5018.7    0.07       0
  5022.7    0.12       0  5132.4    0.05       0
Bank Sta=5018.7,5022.7
Exp/Cntr=0.3,0.1

Type RM Length L Ch R = 1,387,119,119,119
BEGIN DESCRIPTION:
Walnut38 1.7
END DESCRIPTION:
XS GIS Cut Line= 3
      2727430.74      6755101.18      2727350.38      6755168.58
      2727241.48      6755282.67
#Sta/Elev= 30
  4848.8  335.41  4883.3  334.01  4887.5  333.89  4894.1  333.25  4908.4  332.74
  4930.4  330.33  4937.0  328.62  4944.7  328.45  4951.3  326.53  4958.8  326.47
  4963.6  324.89  4963.9  324.39  4967.4  324.39  4967.6  324.89  4979.8  325.96
  4986.7  325.67  4993.9  325.75  5000.8  325.39  5008.1  326.07  5015.0  325.70
  5022.2  327.84  5029.1  327.15  5036.4  328.90  5050.5  331.16  5057.4  331.43
  5064.7  332.02  5071.6  332.93  5093.0  334.57  5097.3  334.61  5111.4  334.98
#Mann=5,-1,0
  4848.8    0.05       0  4883.3    0.12       0  4963.6    0.07       0
  4967.6    0.12       0  5097.3    0.05       0
Bank Sta=4963.6,4967.6
Exp/Cntr=0.3,0.1

Type RM Length L Ch R = 1,268,109,109,109
BEGIN DESCRIPTION:
Walnut38 1.5
END DESCRIPTION:
XS GIS Cut Line= 3
      2727329.61      6755033.78      2727249.27      6755101.16
      2727140.70      6755214.90
#Sta/Elev= 30
  4871.7  334.48  4879.0  334.19  4907.7  331.96  4922.0  331.40  4950.6  329.58
  4957.1  328.55  4964.9  326.75  4971.4  325.73  4975.4  324.42  4985.9  324.10
  4992.8  324.55  5000.0  324.38  5005.0  323.05  5005.2  322.55  5008.7  322.55
  5009.0  323.05  5014.2  324.34  5035.3  326.40  5042.5  327.52  5049.4  328.10
  5056.7  329.06  5063.6  329.11  5070.8  329.75  5077.7  329.66  5099.1  331.11
  5111.4  331.69  5113.3  331.85  5120.2  331.23  5127.4  331.96  5133.8  331.90
#Mann=4,-1,0
  4871.7    0.12       0  5005.0    0.07       0  5009.0    0.12       0
  5111.4    0.05       0
Bank Sta=5005,5009
Exp/Cntr=0.3,0.1

Type RM Length L Ch R = 1,159,128,128,128
BEGIN DESCRIPTION:
Walnut38 1.2
END DESCRIPTION:
XS GIS Cut Line= 3
      2727244.09      6754966.33      2727163.71      6755033.75
      2727055.65      6755146.95
#Sta/Elev= 30
  4884.9  332.19  4886.9  332.19  4894.4  331.52  4901.0  331.43  4915.3  330.38
  4921.8  330.31  4936.1  329.43  4950.4  328.04  4972.5  325.60  4985.1  323.09
  4989.8  323.09  4993.3  322.40  4998.2  320.67  4998.5  320.17  5002.0  320.17
  5002.2  320.67  5007.5  323.05  5014.4  322.91  5021.6  323.16  5028.5  323.09
  5042.7  323.84  5049.9  324.78  5056.9  325.25  5064.1  326.51  5085.2  328.44
  5092.4  328.63  5120.7  330.42  5134.9  330.96  5145.1  330.40  5146.3  330.35
#Mann=4,-1,0
  4884.9    0.12       0  4998.2    0.07       0  5002.2    0.12       0
  5145.1    0.05       0
Bank Sta=4998.2,5002.2
Exp/Cntr=0.3,0.1

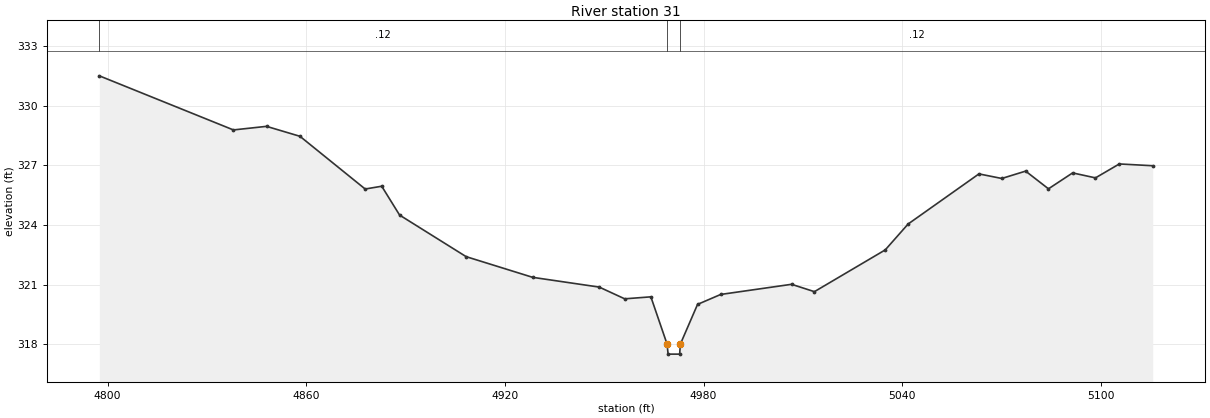
Type RM Length L Ch R = 1,31,0,0,0
BEGIN DESCRIPTION:
Walnut38 1.0
END DESCRIPTION:
XS GIS Cut Line= 3
      2727236.28      6754937.82      2727075.55      6754953.38
      2726967.34      6755066.74
#Sta/Elev= 30
  4797.5  331.50  4838.0  328.78  4848.0  328.96  4858.1  328.46  4877.8  325.81
  4882.8  325.95  4888.2  324.50  4908.3  322.41  4928.4  321.37  4948.5  320.88
  4956.2  320.29  4964.1  320.39  4969.0  318.01  4969.3  317.51  4972.8  317.51
  4973.0  318.01  4978.2  320.01  4985.2  320.51  5006.6  321.02  5013.5  320.65
  5034.9  322.75  5041.8  324.05  5063.2  326.57  5070.1  326.34  5077.3  326.71
  5084.2  325.82  5091.5  326.62  5098.4  326.37  5105.6  327.07  5115.7  326.98
#Mann=3,-1,0
  4797.5    0.12       0  4969.0    0.07       0  4973.0    0.12       0
Bank Sta=4969,4973
Exp/Cntr=0.3,0.1

Chan Stop Cuts=-1