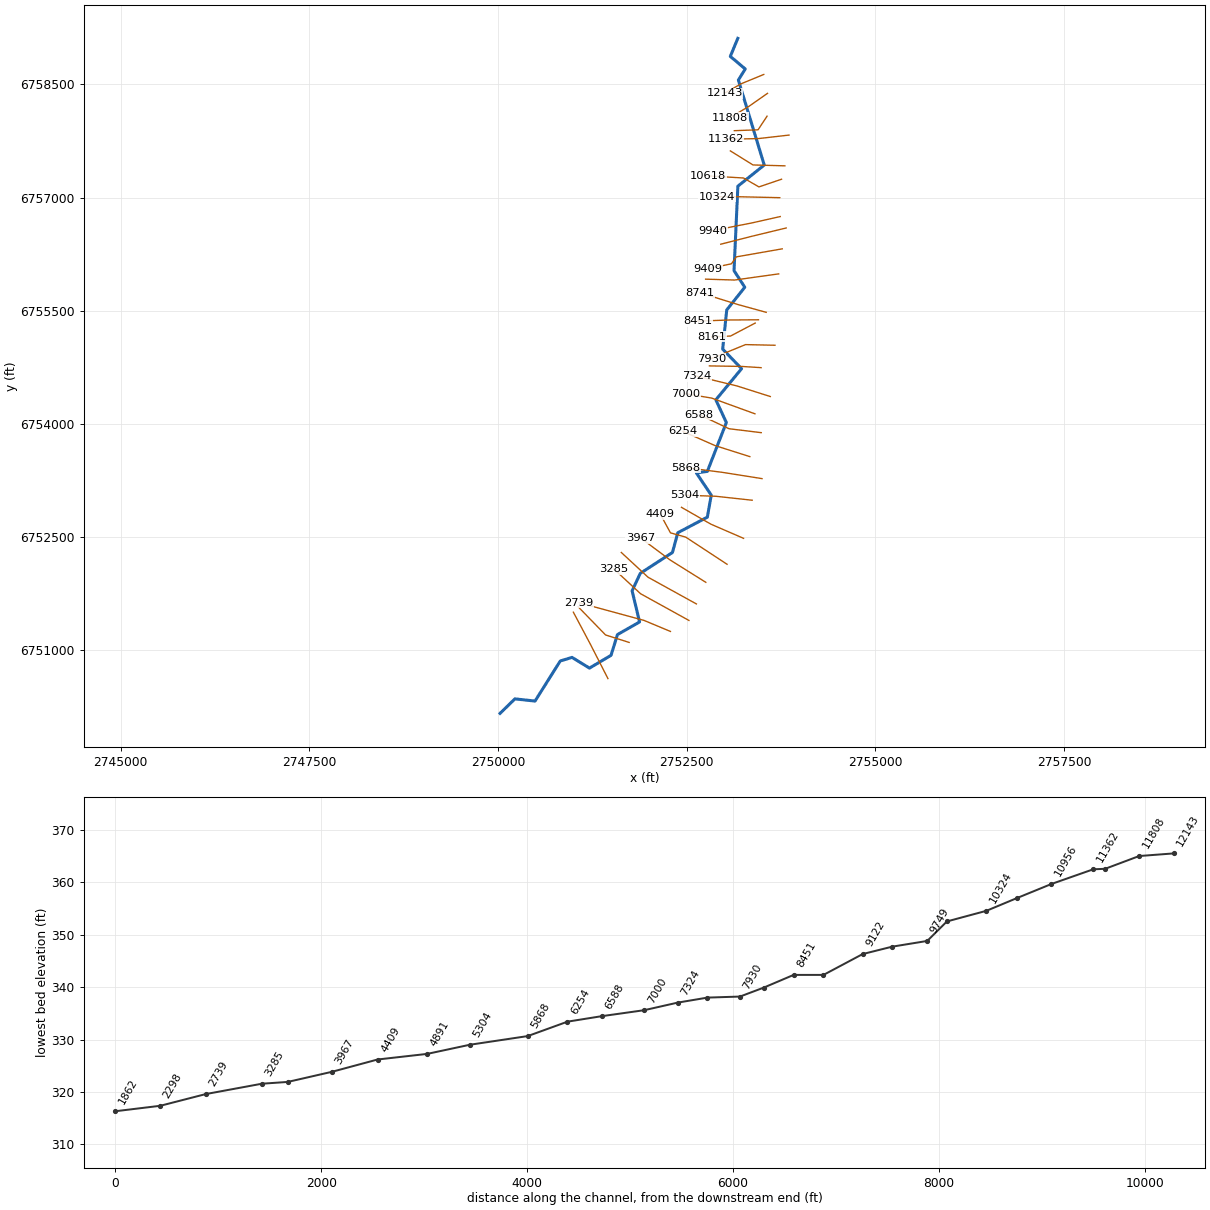
--- Walnut4.prj (project) ---

Proj Title=Walnut4 Base Level Engineering
Current Plan=p01
Default Exp/Contr=0.3,0.1
English Units
Geom File=g01
Flow File=f01
Plan File=p01
Y Axis Title=Elevation
X Axis Title(PF)=Main Channel Distance
X Axis Title(XS)=Station
BEGIN DESCRIPTION:
Walnut4
END DESCRIPTION:
DSS Export Rating Curves= 0
DSS Export Rating Curve Sorted= 0
DSS Export Volume Flow Curves= 0
DXF OffsetX= 0
DXF OffsetY= 0
DXF ScaleX= 1
DXF ScaleY= 10

--- Walnut4.p01 (plan) ---

Plan Title=Multiple Run
Program Version=4.10
Short Identifier=Multiple
Geom File=g01
Flow File=f01
Subcritical Flow
K Sum by GR= 0
Std Step Tol= 0.01
Critical Tol= 0.01
Num of Std Step Trials= 20
Max Error Tol= 0.3
Flow Tol Ratio= 0.001
Split Flow NTrial= 30
Split Flow Tol= 0.02
Split Flow Ratio= 0.02
Log Output Level= 0
Friction Slope Method= 1
Unsteady Friction Slope Method= 2
Unsteady Bridges Friction Slope Method= 1
Parabolic Critical Depth
Global Vel Dist= 1 , 1 , 1
Global Log Level= 0
CheckData=True
Encroach Param=-1 ,0,0, 0
BEGIN DESCRIPTION:
Multiple Run
END DESCRIPTION:
Computation Interval=1HOUR
Output Interval=1HOUR
Run HTab= 0
Run UNet= 0
Run PostProcess= 0
Run WQNet= 0
UNET Theta= 1
UNET Theta Warmup= 1
UNET ZTol= 0.02
UNET ZSATol= 0.05
UNET MxIter= 20
UNET MaxInSteps= 0
UNET DtIC= 0
UNET DtMin= 0
UNET MaxCRTS= 20
UNET WFStab= 2
UNET SFStab= 1
UNET WFX= 1
UNET SFX= 1
UNET DSS MLevel= 4
UNET DZMax Abort= 100
UNET Convert EG Bridges= 0
UNET Use Existing IB Tables=-1
UNET Froude Reduction=False
UNET Froude Limit= 1
UNET Froude Power= 10
UNET Time Slicing=0,0, 5
UNET Junction Losses=0
Instantaneous Interval=1HOUR
Write IC File= 0
Write IC File at Sim End=0
Echo Input=False
Echo Parameters=False
Echo Output=False
Write Detailed= 0
WQ AD Non Conservative
WQ ULTIMATE=-1
WQ Max Comp Step=1HOUR
WQ Output Interval=15MIN
WQ Output Selected Increments= 0
WQ Output face flow=0
WQ Output face velocity=0
WQ Output face area=0
WQ Output face dispersion=0
WQ Output cell volume=0
WQ Output cell surface area=0
WQ Output cell continuity=0
WQ Output cumulative cell continuity=0
WQ Output face conc=0
WQ Output face dconc_dx=0
WQ Output face courant=0
WQ Output face peclet=0
WQ Output face adv mass=0
WQ Output face disp mass=0
WQ Output cell mass=0
WQ Output cell source sink temp=0
WQ Output cell source sink nsm=0
WQ Output MaxMinRange=-1
WQ Daily Max Min Mean=-1
WQ Daily Range=0
WQ Daily Time=0
WQ Create Restart=0
WQ Fixed Restart=0
WQ System Summary=0
WQ Use Fixed Temperature=0
Sorting and Armoring Iterations= 10
XS Update Threshold= 0.02
Hydraulics Update Threshold= 0.02
Energy Slope Method= 1
Volume Change Method= 0
XS Weighting Method= 0
Number of US Weighted Cross Sections= 1
Number of DS Weighted Cross Sections= 1
Upstream XS Weight=0.25
Main XS Weight=0.5
Downstream XS Weight=0.25
Number of DS XS's Weighted with US Boundary= 1
Upstream Boundary Weight= 1
Weight of XSs Associated with US Boundary= 0
Number of US XS's Weighted with DS Boundary= 1
Downstream Boundary Weight= 0.5
Weight of XSs Associated with DS Boundary= 0.5
Sediment Output Level= 4
Mass or Volume Output= 0
Output Increment Type= 1
Profile and TS Output Increment= 10
XS Output Flag= 0
XS Output Increment= 10
Disregard all LS=0
Disregard all Conn=0
Disregard all Breaches=0
Disregard all Pumps=0

--- Walnut4.f01 (steady flow) ---

Flow Title=Multiple
Number of Profiles=7
Profile Names=10-year,25-year,50-year,1pct_min,100-year,1pct_plu,500-year
River Rch & RM= Walnut4,Reach-1,12143
     507     678     817     489     976    1948    1397
River Rch & RM= Walnut4,Reach-1,9409
     656     887    1077     649    1295    2583    1876
Boundary for River Rch & Prof#=Walnut4,Reach-1,1
Up Type=0
Dn Type=3
Dn Slope=0.013
Boundary for River Rch & Prof#=Walnut4,Reach-1,2
Up Type=0
Dn Type=3
Dn Slope=0.013
Boundary for River Rch & Prof#=Walnut4,Reach-1,3
Up Type=0
Dn Type=3
Dn Slope=0.013
Boundary for River Rch & Prof#=Walnut4,Reach-1,4
Up Type=0
Dn Type=3
Dn Slope=0.013
Boundary for River Rch & Prof#=Walnut4,Reach-1,5
Up Type=0
Dn Type=3
Dn Slope=0.013
Boundary for River Rch & Prof#=Walnut4,Reach-1,6
Up Type=0
Dn Type=3
Dn Slope=0.013
Boundary for River Rch & Prof#=Walnut4,Reach-1,7
Up Type=0
Dn Type=3
Dn Slope=0.013

--- Walnut4.g01 (geometry) ---

Geom Title=Existing Conditions
Program Version=4.10

River Reach=Walnut4         ,Reach-1
Reach XY= 30
        2753176.        6759111.      2753077.03      6758871.43
      2753274.49      6758705.13      2753183.61      6758557.67
      2753526.37       6757431.2      2753176.98      6757150.72
      2753125.96      6756030.98       2753268.5        6755811.
      2753029.44      6755509.75      2752975.54      6754990.75
      2753226.12      6754731.11      2752884.98      6754318.06
      2753024.38      6754017.04      2752772.64       6753369.1
      2752626.97      6753349.26       2752824.4      6753054.49
      2752772.34      6752762.55      2752381.12      6752555.89
      2752309.92      6752294.17      2751883.86      6752017.21
      2751775.51      6751786.04      2751874.55      6751372.97
      2751581.19      6751205.56      2751496.54      6750930.47
      2751210.78      6750761.24      2750979.42      6750903.21
      2750823.56      6750855.48      2750489.67      6750324.22
      2750222.57      6750353.21        2750026.        6750161.

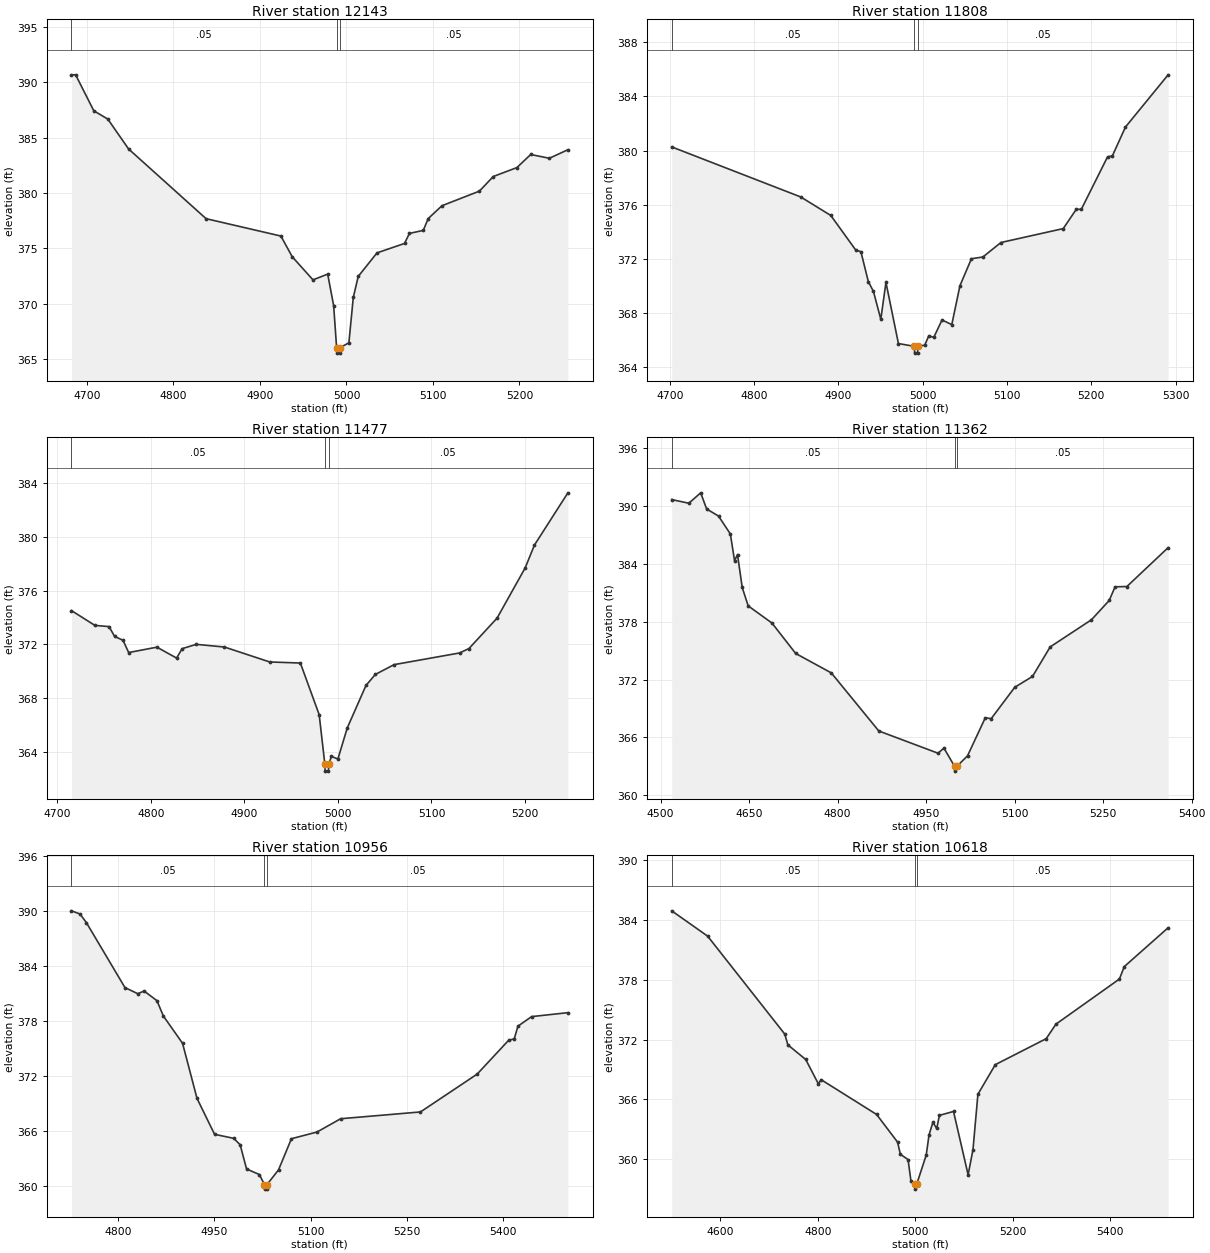
Type RM Length L Ch R = 1 ,12143   ,335,335,335
BEGIN DESCRIPTION:
Walnut4 24.0
END DESCRIPTION:
XS GIS Cut Line= 3
      2753519.86      6758631.98        2753226.        6758511.
       2753002.9      6758385.23
#Sta/Elev= 30
  4682.1  390.67  4686.9  390.67  4707.9  387.42  4724.1  386.67  4748.1  383.97
  4837.7  377.67  4924.2   376.1  4937.3  374.23  4961.3  372.14  4978.3  372.66
  4985.2  369.81  4988.6  366.02  4988.9  365.52  4992.4  365.52  4992.6  366.02
  5002.8  366.45  5007.9  370.55  5013.6  372.45  5035.3  374.58  5067.1  375.43
  5072.8  376.34  5088.8  376.61  5094.5  377.68  5110.4  378.84  5153.7  380.16
  5169.7  381.48  5197.1  382.29    5213  383.47  5234.6  383.13    5256   383.9
#Mann= 3 ,-1 , 0
  4682.1     .05       0  4988.6     .04       0  4992.6     .05       0
Bank Sta=4988.6,4992.6
XS Rating Curve= 0 ,0
Exp/Cntr=0.3,0.1

Type RM Length L Ch R = 1 ,11808   ,331,331,331
BEGIN DESCRIPTION:
Walnut4 23.0
END DESCRIPTION:
XS GIS Cut Line= 3
      2753569.41      6758381.58        2753326.        6758211.
      2753075.98      6758060.99
#Sta/Elev= 30
  4702.4  380.27  4855.4  376.57  4891.1   375.2  4920.7  372.64  4926.8  372.52
  4935.6  370.31  4941.7  369.58  4950.4  367.52  4956.5  370.25  4971.3  365.73
  4990.2  365.52  4990.5  365.02    4994  365.02  4994.2  365.52  5002.5  365.61
  5007.4  366.31  5013.2  366.18    5023  367.47  5034.6  367.13  5044.3  370.01
  5057.9     372  5071.5  372.13  5092.9   373.2  5166.8  374.23  5182.3  375.66
  5188.2  375.65  5219.3  379.53  5225.1  379.61  5240.6  381.74  5291.2   385.6
#Mann= 3 ,-1 , 0
  4702.4     .05       0  4990.2     .04       0  4994.2     .05       0
Bank Sta=4990.2,4994.2
XS Rating Curve= 0 ,0
Exp/Cntr=0.3,0.1

Type RM Length L Ch R = 1 ,11477   ,115,115,115
BEGIN DESCRIPTION:
Walnut4 22.0
END DESCRIPTION:
XS GIS Cut Line= 3
      2753563.58      6758078.73       2753444.2       6757898.2
      2753130.34      6757886.58
#Sta/Elev= 30
  4715.3  374.52  4740.3  373.42  4755.4  373.33  4761.4   372.6  4770.4  372.31
  4776.4   371.4  4806.6   371.8  4827.6  370.99  4833.6  371.69  4848.7  372.01
  4878.8  371.81  4927.1   370.7  4959.9  370.62    4980  366.78  4986.1  363.08
  4986.4  362.58  4989.9  362.58  4990.1  363.08  4993.1  363.68    5000  363.48
    5010  365.79    5030  368.95    5040  369.77    5060   370.5  5130.1  371.37
  5140.1   371.7  5170.1  373.96  5200.1  377.69  5210.1   379.4  5245.8  383.28
#Mann= 3 ,-1 , 0
  4715.3     .05       0  4986.1     .04       0  4990.1     .05       0
Bank Sta=4986.1,4990.1
XS Rating Curve= 0 ,0
Exp/Cntr=0.3,0.1

Type RM Length L Ch R = 1 ,11362   ,406,406,406
BEGIN DESCRIPTION:
Walnut4 21.6
END DESCRIPTION:
XS GIS Cut Line= 3
      2753854.77      6757828.32      2753447.11      6757781.73
      2753016.12      6757772.99
#Sta/Elev= 30
  4518.7  390.69  4547.7  390.31  4567.8  391.39  4577.9  389.71    4598  388.98
  4618.1  387.12  4625.2  384.34  4630.2  384.98  4638.2  381.56  4648.3  379.65
  4688.6  377.87  4728.8  374.71  4789.2  372.69  4869.7  366.66  4970.1  364.35
  4980.1  364.88  4998.1  362.99  4998.4  362.49  5002.1  362.99  5020.1  364.08
  5050.2  368.03  5060.2  367.94  5100.2   371.2  5130.2  372.32  5160.2  375.39
  5230.2  378.21  5260.2  380.21  5270.2  381.63  5290.2  381.66  5360.1   385.7
#Mann= 3 ,-1 , 0
  4518.7     .05       0  4998.1     .04       0  5002.1     .05       0
Bank Sta=4998.1,5002.1
XS Rating Curve= 0 ,0
Exp/Cntr=0.3,0.1

Type RM Length L Ch R = 1 ,10956   ,338,338,338
BEGIN DESCRIPTION:
Walnut4 21.0
END DESCRIPTION:
XS GIS Cut Line= 3
      2753799.42      6757420.66      2753377.22       6757432.3
      2753077.27      6757618.68
#Sta/Elev= 30
  4726.6  390.05    4740   389.7    4750  388.75  4810.1  381.68  4830.1  381.01
  4840.1   381.3  4860.1  380.25  4870.1  378.58  4900.1   375.6  4922.7  369.59
  4950.1  365.67  4980.1  365.23  4990.1  364.53  5000.1  361.89  5020.1  361.28
  5028.1  360.19  5028.4  359.69  5031.9  359.69  5032.1  360.19  5050.1   361.8
  5070.2  365.19  5110.2  365.92  5147.1  367.37  5271.8  368.11  5360.4  372.24
  5409.4  375.92  5418.3  376.09  5424.1  377.47  5445.4  378.51  5502.1  378.94
#Mann= 3 ,-1 , 0
  4726.6     .05       0  5028.1     .05       0  5032.1     .05       0
Bank Sta=5028.1,5032.1
XS Rating Curve= 0 ,0
Exp/Cntr=0.3,0.1

Type RM Length L Ch R = 1 ,10618   ,294,294,294
BEGIN DESCRIPTION:
Walnut4 20.0
END DESCRIPTION:
XS GIS Cut Line= 4
       2753755.8      6757243.04      2753455.84      6757141.12
      2753251.41      6757259.46      2752786.13      6757286.71
#Sta/Elev= 30
  4500.2  384.93  4573.9  382.39  4732.3  372.55  4738.6  371.47  4775.3     370
  4801.4  367.54  4806.7  367.98  4920.8  364.48  4963.9   361.7  4969.6  360.48
  4985.4  359.95  4991.2  357.84  4999.2  357.48  4999.4  356.98  5003.2  357.48
  5022.7   360.4  5028.5  362.44  5036.4  363.69  5044.2  363.07  5049.8  364.39
  5078.7  364.78  5108.7  358.42  5118.7  360.95  5128.8  366.51  5164.5  369.48
    5269  372.09    5289  373.55  5419.3  378.08  5429.3  379.33  5519.3  383.23
#Mann= 3 ,-1 , 0
  4500.2     .05       0  4999.2     .05       0  5003.2     .05       0
Bank Sta=4999.2,5003.2
XS Rating Curve= 0 ,0
Exp/Cntr=0.3,0.1

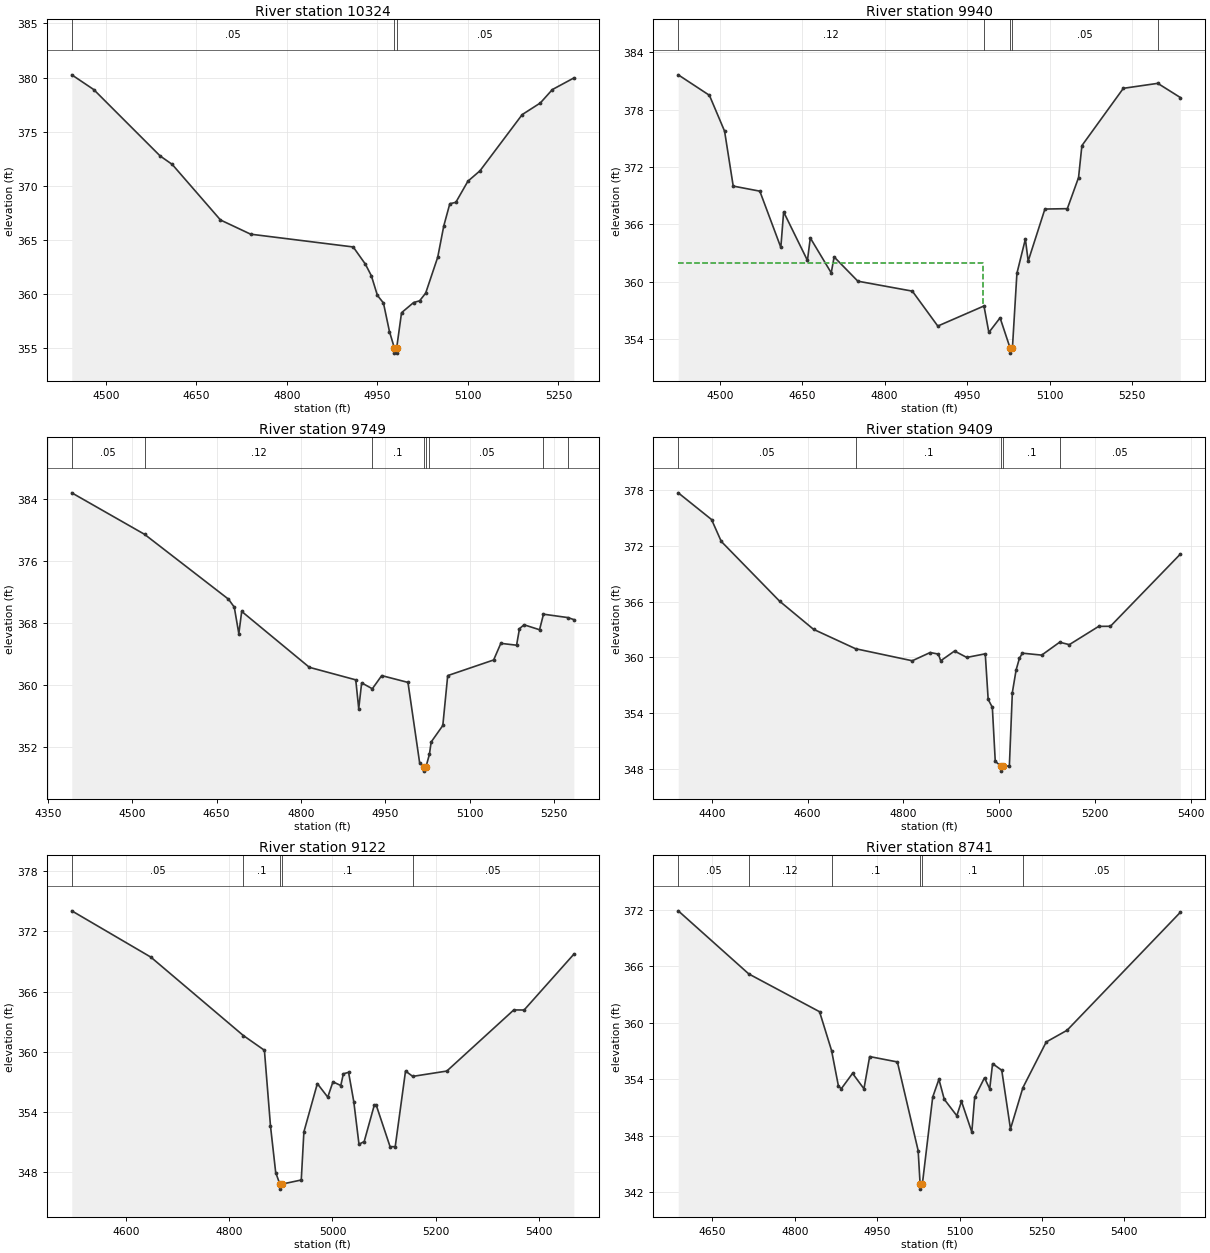
Type RM Length L Ch R = 1 ,10324   ,384,384,384
BEGIN DESCRIPTION:
Walnut4 19.0
END DESCRIPTION:
XS GIS Cut Line= 3
      2753732.43      6756998.43        2753176.        6757011.
      2752900.37      6757010.08
#Sta/Elev= 30
  4443.4  380.26  4479.8   378.9  4589.9  372.77  4609.9  371.99  4689.9  366.86
  4739.9  365.55  4909.9  364.37    4930  362.79    4940  361.71    4950   359.9
    4960   359.2    4970  356.56    4978  355.07  4978.2  354.57  4981.7  354.57
    4982  355.07    4990   358.3    5010  359.24    5020   359.4    5030  360.11
    5050  363.43    5060  366.31    5070  368.36    5080  368.49    5100  370.44
    5120   371.4    5190  376.59    5220  377.66    5240   378.9  5275.6  379.97
#Mann= 3 ,-1 , 0
  4443.4     .05       0    4978     .05       0    4982     .05       0
Bank Sta=4978,4982
XS Rating Curve= 0 ,0
Exp/Cntr=0.3,0.1

Type RM Length L Ch R = 1 ,9940    ,191,191,191
BEGIN DESCRIPTION:
Walnut4 18.0
END DESCRIPTION:
XS GIS Cut Line= 3
      2753738.28      6756748.01      2753362.66      6756663.57
      2752844.37      6756561.66
#Sta/Elev= 30
  4424.5  381.63  4481.2  379.49  4508.8  375.74  4524.5     370  4572.9  369.47
  4611.1  363.59  4616.2   367.3  4659.5  362.23  4664.7  364.58  4702.8  360.93
    4708   362.6  4751.2  360.06  4850.3  359.02  4896.6  355.37  4980.6  357.47
  4989.5   354.7  5009.9  356.23  5028.3  353.04  5028.5  352.54  5032.3  353.04
  5040.5  360.88  5055.9  364.46    5061  362.16  5091.4   367.6  5132.2  367.64
  5152.6  370.89  5158.7  374.23  5234.1  380.22  5296.7  380.74  5337.7  379.26
#Mann= 5 ,-1 , 0
  4424.5     .12       0  4980.6     .05       0  5028.3    .035       0
  5032.3     .05       0  5296.7     .12       0
#XS Ineff= 2 , 0
       0 4979.15     362               0
Permanent Ineff=
       F       F
Bank Sta=5028.3,5032.3
XS Rating Curve= 0 ,0
Exp/Cntr=0.3,0.1

Type RM Length L Ch R = 1 ,9749    ,340,340,340
BEGIN DESCRIPTION:
Walnut4 17.4
END DESCRIPTION:
XS GIS Cut Line= 3
      2753816.96      6756596.61      2753359.75      6756485.94
      2752950.11      6756381.35
#Sta/Elev= 30
  4392.4   384.8    4522  379.43  4671.2  371.05  4681.5  370.02  4689.6  366.59
  4694.7  369.47  4815.1  362.24  4897.6  360.62  4902.9   356.9  4908.1  360.23
  4927.1  359.47  4943.8  361.17  4990.5  360.29  5011.2  349.93  5018.3  349.32
  5018.6  348.82  5022.3  349.32  5028.6  350.97  5031.8  352.59  5052.5  354.72
  5061.2  361.17  5142.9  363.19  5155.7  365.34  5183.7   365.1  5188.9  367.24
    5197  367.74  5224.6   367.1  5231.6  369.11  5275.1  368.67  5285.6  368.41
#Mann= 8 ,-1 , 0
  4392.4     .05       0    4522     .12       0  4927.1      .1       0
  5018.3     .07       0  5022.3      .1       0  5028.6     .05       0
  5231.6      .1       0  5275.1     .12       0
Bank Sta=5018.3,5022.3
XS Rating Curve= 0 ,0
Exp/Cntr=0.3,0.1

Type RM Length L Ch R = 1 ,9409    ,287,287,287
BEGIN DESCRIPTION:
Walnut4 17.0
END DESCRIPTION:
XS GIS Cut Line= 4
      2753764.51      6756319.97      2753156.89       6756213.6
      2753091.86      6756121.96      2752779.21      6756055.37
#Sta/Elev= 30
  4329.7  377.74  4399.3  374.86  4419.6   372.5  4541.4  366.06  4612.4  363.02
  4700.1  360.93  4818.6  359.63  4856.1  360.52    4873  360.35  4878.1  359.63
  4906.9  360.68  4932.5  359.99  4971.1  360.38  4977.2  355.46  4985.9  354.61
    4992  348.79  5004.8  348.23    5005  347.73  5008.8  348.23  5021.5   348.3
  5027.7   356.2  5035.6  358.65  5042.4  359.88  5048.6  360.45    5089  360.24
  5126.5  361.63  5146.7  361.37  5208.1  363.34  5232.6  363.35  5378.6  371.13
#Mann= 5 ,-1 , 0
  4329.7     .05       0  4700.1      .1       0  5004.8     .07       0
  5008.8      .1       0  5126.5     .05       0
Bank Sta=5004.8,5008.8
XS Rating Curve= 0 ,0
Exp/Cntr=0.3,0.1

Type RM Length L Ch R = 1 ,9122    ,381,381,381
BEGIN DESCRIPTION:
Walnut4 16.0
END DESCRIPTION:
XS GIS Cut Line= 3
      2753717.96      6755988.02      2753132.63      6755906.48
      2752749.59      6755918.09
#Sta/Elev= 30
  4494.2  374.04  4647.6  369.43  4827.1  361.62    4868  360.15  4879.8   352.6
  4889.9  347.97    4898  346.82  4898.3  346.32    4902  346.82  4939.5  347.23
  4944.6  352.02  4970.7  356.83  4990.9  355.48    5001  357.01  5016.2  356.64
  5021.2  357.81  5031.3  357.95  5041.4  355.04  5051.5  350.79  5061.6  351.06
    5081  354.65  5085.2  354.65  5111.8  350.55  5121.8  350.55  5141.8  358.08
  5155.8  357.55  5221.9  358.08  5351.9  364.17  5371.9  364.16  5468.4  369.72
#Mann= 5 ,-1 , 0
  4494.2     .05       0  4827.1      .1       0    4898     .07       0
    4902      .1       0  5155.8     .05       0
Bank Sta=4898,4902
XS Rating Curve= 0 ,0
Exp/Cntr=0.3,0.1

Type RM Length L Ch R = 1 ,8741    ,290,290,290
BEGIN DESCRIPTION:
Walnut4 15.0
END DESCRIPTION:
XS GIS Cut Line= 3
      2753551.95      6755478.43      2753182.13      6755580.35
      2752675.48      6755737.58
#Sta/Elev= 30
  4587.7  371.88  4716.2  365.18    4845  361.17  4866.9  357.04  4879.4  353.27
  4884.6     353  4905.1  354.63  4925.8  352.99  4936.2  356.41  4986.7  355.84
  5024.5  346.43  5028.1  342.84  5028.3  342.34  5032.1  342.84    5051  352.11
  5062.3     354    5072  351.88  5094.9  350.13  5103.4  351.66  5122.2   348.4
  5127.4  352.08  5145.3  354.16  5154.8  352.98    5160  355.66  5176.7  354.96
  5192.6  348.73  5215.2  353.11  5257.7  357.96  5295.6   359.2  5501.8  371.72
#Mann= 6 ,-1 , 0
  4587.7     .05       0  4716.2     .12       0  4866.9      .1       0
  5028.1     .07       0  5032.1      .1       0  5215.2     .05       0
Bank Sta=5028.1,5032.1
XS Rating Curve= 0 ,0
Exp/Cntr=0.3,0.1

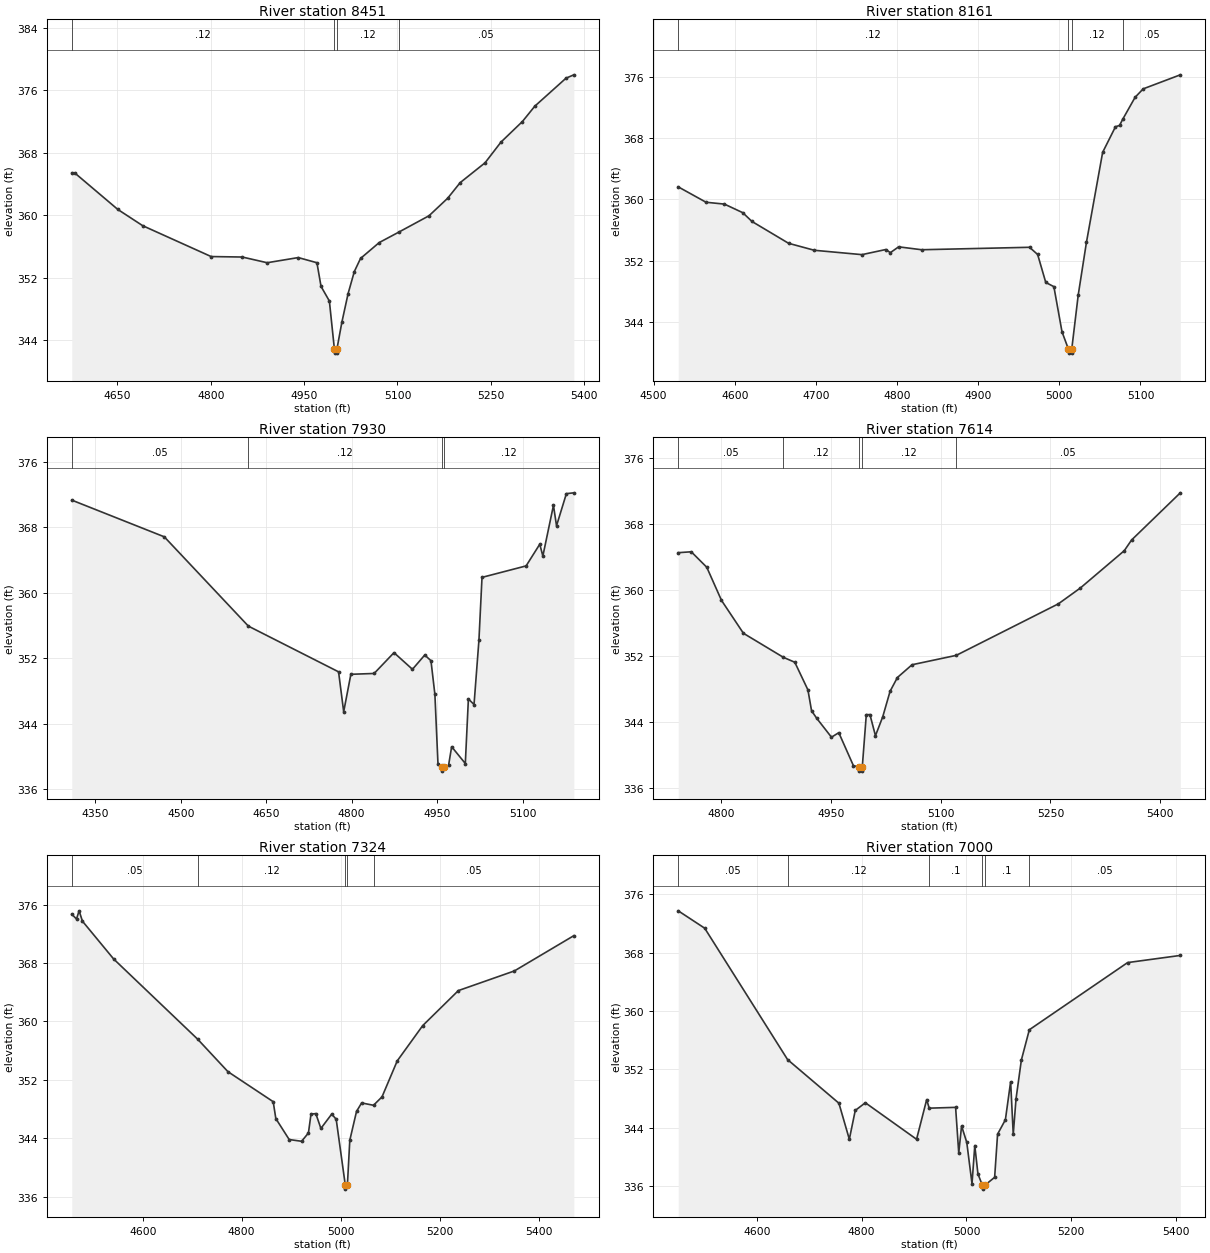
Type RM Length L Ch R = 1 ,8451    ,290,290,290
BEGIN DESCRIPTION:
Walnut4 14.0
END DESCRIPTION:
XS GIS Cut Line= 3
      2753450.02      6755379.43      2753062.74      6755376.52
      2752643.38      6755361.95
#Sta/Elev= 30
  4576.6  365.42  4581.1  365.42  4650.6  360.73  4690.6  358.65  4800.6   354.7
  4850.6  354.64  4890.6  353.91  4940.6  354.57  4970.6  353.91  4977.2  350.88
  4990.6  349.01  4998.7  342.84  4998.9  342.34  5002.4  342.34  5002.7  342.84
  5010.7   346.3  5020.7  349.96  5030.7  352.78  5040.7  354.46  5070.7  356.49
    5102  357.82  5150.7  359.92  5180.8  362.17  5200.8  364.16  5240.8   366.7
  5266.4  369.35  5300.8  371.98  5320.8  373.95  5370.9  377.53  5383.5  377.96
#Mann= 4 ,-1 , 0
  4576.6     .12       0  4998.7     .07       0  5002.7     .12       0
    5102     .05       0
Bank Sta=4998.7,5002.7
XS Rating Curve= 0 ,0
Exp/Cntr=0.3,0.1

Type RM Length L Ch R = 1 ,8161    ,231,231,231
BEGIN DESCRIPTION:
Walnut4 13.0
END DESCRIPTION:
XS GIS Cut Line= 3
      2753406.33      6755335.74      2753080.21      6755163.95
      2752830.38      6755152.33
#Sta/Elev= 30
  4530.4  361.63  4564.7  359.62  4587.3  359.38  4609.9  358.26  4621.3  357.11
  4666.4  354.26  4698.1  353.35  4756.8  352.78  4786.2  353.45  4791.8  353.04
    4802   353.8  4830.3  353.42  4963.3  353.74  4973.3   352.8  4983.3  349.15
  4993.3   348.6  5003.3  342.71  5011.3  340.42  5011.6  339.92  5015.1  339.92
  5015.3  340.42  5023.3  347.51  5033.4  354.37  5053.4  366.14  5069.2  369.48
  5074.2  369.65  5078.1  370.45  5093.4  373.33  5103.4  374.43  5149.1  376.26
#Mann= 4 ,-1 , 0
  4530.4     .12       0  5011.3     .07       0  5015.3     .12       0
  5078.1     .05       0
Bank Sta=5011.3,5015.3
XS Rating Curve= 0 ,0
Exp/Cntr=0.3,0.1

Type RM Length L Ch R = 1 ,7930    ,316,316,316
BEGIN DESCRIPTION:
Walnut4 12.5
END DESCRIPTION:
XS GIS Cut Line= 3
      2753668.38      6755041.65      2753278.22      6755050.39
      2752823.92      6754864.01
#Sta/Elev= 30
  4308.7  371.29  4471.1  366.81  4618.7  355.91    4777  350.33    4786  345.46
  4798.6  350.03  4839.4  350.13  4874.3  352.67  4906.7  350.64  4928.3  352.38
  4939.2  351.69  4946.1  347.57  4951.5  339.11  4958.8  338.71    4959  338.21
  4962.8  338.71  4970.1  338.91  4975.5  341.19  4999.5  339.14  5004.9  347.02
  5014.8  346.34  5023.4  354.19  5028.8  361.86  5106.2  363.26  5130.2  365.91
  5135.6  364.46  5154.2  370.65  5159.6  368.16  5176.9  372.08    5190  372.18
#Mann= 4 ,-1 , 0
  4308.7     .05       0  4618.7     .12       0  4958.8     .07       0
  4962.8     .12       0
Bank Sta=4958.8,4962.8
XS Rating Curve= 0 ,0
Exp/Cntr=0.3,0.1

Type RM Length L Ch R = 1 ,7614    ,290,290,290
BEGIN DESCRIPTION:
Walnut4 12.0
END DESCRIPTION:
XS GIS Cut Line= 3
      2753484.95      6754744.64        2753226.        6754761.
      2752799.42      6754767.91
#Sta/Elev= 30
  4741.4  364.54  4759.2  364.65  4780.4  362.77  4800.5  358.75  4830.5  354.75
  4884.9  351.84  4900.7  351.23  4918.6  347.88  4923.6  345.34  4930.7  344.42
  4950.8  342.13  4960.8  342.68  4980.8  338.67  4988.8  338.51  4989.1  338.01
  4992.6  338.01  4992.9  338.51  4998.4  344.87  5003.4  344.87  5010.9  342.31
  5020.9  344.62  5030.9  347.71  5040.9  349.38  5060.9  350.93  5121.3  352.07
  5260.9  358.33  5290.9  360.25  5350.9  364.78  5360.9  366.08  5427.5  371.81
#Mann= 5 ,-1 , 0
  4741.4     .05       0  4884.9     .12       0  4988.8     .07       0
  4992.9     .12       0  5121.3     .05       0
Bank Sta=4988.8,4992.9
XS Rating Curve= 0 ,0
Exp/Cntr=0.3,0.1

Type RM Length L Ch R = 1 ,7324    ,324,324,324
BEGIN DESCRIPTION:
Walnut4 11.5
END DESCRIPTION:
XS GIS Cut Line= 3
      2753606.59      6754361.97      2753163.86       6754502.6
      2752629.22      6754632.37
#Sta/Elev= 30
  4456.6  374.69  4466.2  374.03  4471.4  375.15  4478.2  373.73  4541.2  368.56
    4711  357.58  4772.2  353.13  4863.7  349.02    4869  346.71    4896  343.84
  4921.1   343.6  4934.9  344.74  4940.1  347.32  4949.8  347.39  4960.1  345.36
  4981.9  347.32    4991  346.62  5009.5  337.55  5009.8  337.05  5013.6  337.55
  5018.5  343.74  5032.1  347.69  5042.4  348.85  5066.4  348.53  5083.6  349.68
  5114.4  354.61  5165.9  359.44  5237.9  364.23  5351.1  366.92  5471.3  371.75
#Mann= 5 ,-1 , 0
  4456.6     .05       0    4711     .12       0  5009.5     .07       0
  5013.6     .12       0  5066.4     .05       0
Bank Sta=5009.5,5013.6
XS Rating Curve= 0 ,0
Exp/Cntr=0.3,0.1

Type RM Length L Ch R = 1 ,7000    ,412,412,412
BEGIN DESCRIPTION:
Walnut4 11.0
END DESCRIPTION:
XS GIS Cut Line= 3
      2753403.44      6754132.81      2752830.53      6754341.15
      2752486.79      6754398.44
#Sta/Elev= 30
    4450  373.73  4500.5  371.35  4658.7  353.35  4756.6  347.38  4776.5  342.44
  4787.8  346.39  4807.1  347.44  4904.8  342.44  4924.1  347.87  4928.9   346.7
  4979.3  346.81  4985.3  340.56  4990.7  344.26  5000.6  342.01  5010.6  336.35
  5015.9  341.58  5021.9   337.7  5030.5  336.11  5030.8  335.61  5034.6  336.11
  5053.8  337.23  5059.4  343.14  5074.3  345.11  5084.3  350.32  5089.3  343.12
  5094.6  347.97  5104.8   353.3    5120  357.44  5307.5  366.64  5408.1  367.62
#Mann= 6 ,-1 , 0
    4450     .05       0  4658.7     .12       0  4928.9      .1       0
  5030.5     .07       0  5034.6      .1       0    5120     .05       0
Bank Sta=5030.5,5034.6
XS Rating Curve= 0 ,0
Exp/Cntr=0.3,0.1

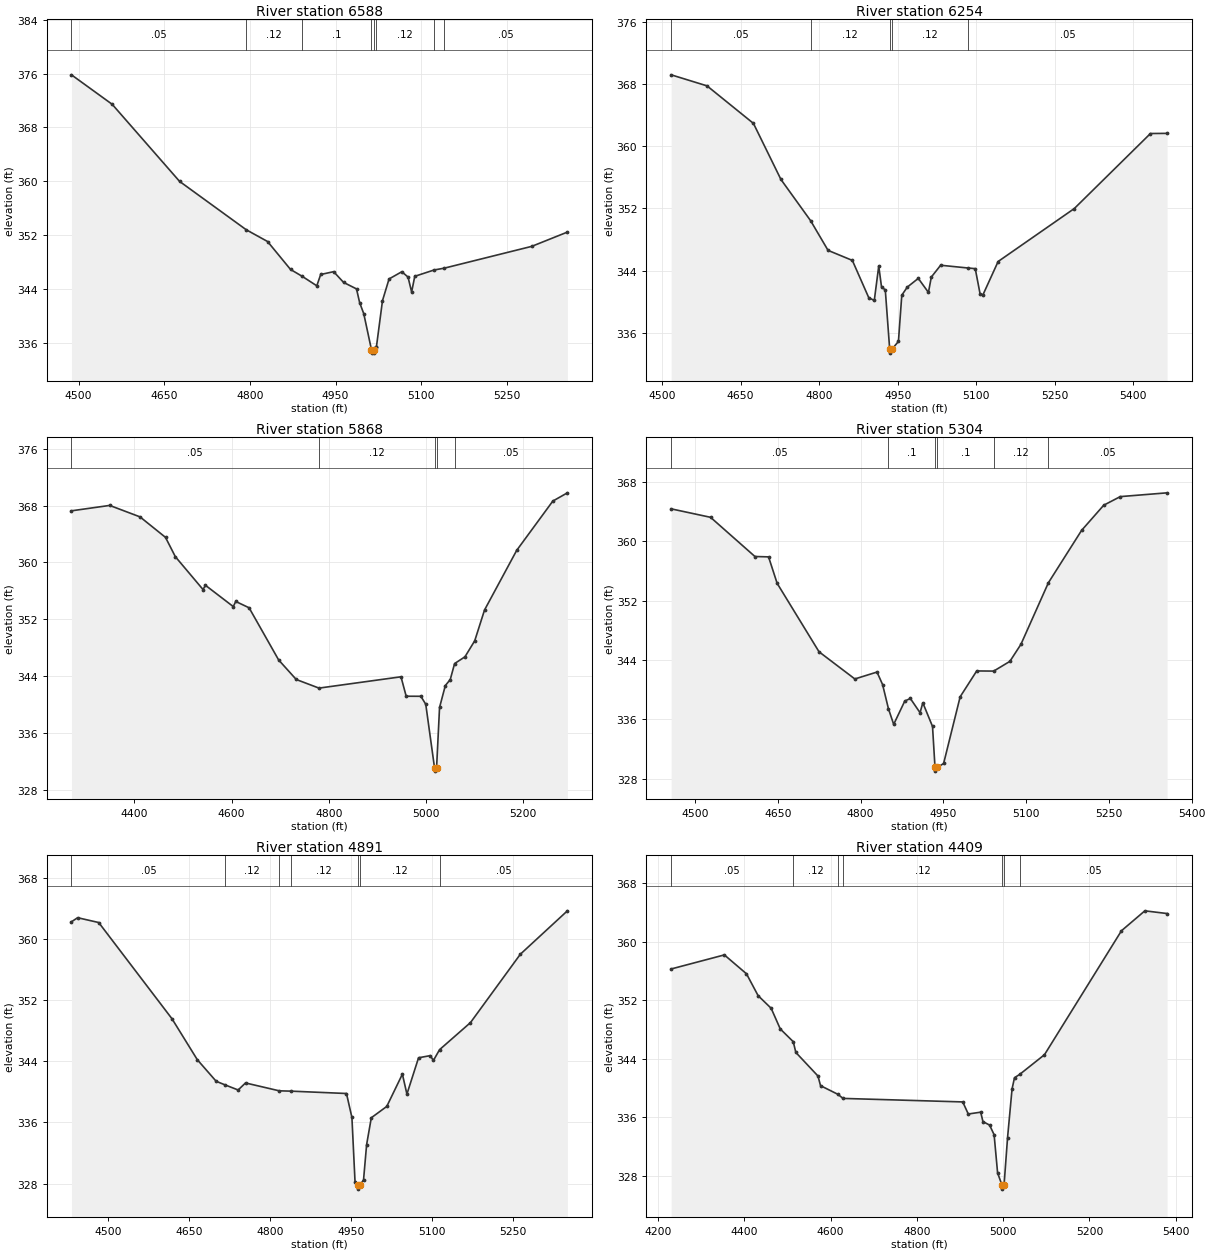
Type RM Length L Ch R = 1 ,6588    ,334,334,334
BEGIN DESCRIPTION:
Walnut4 10.0
END DESCRIPTION:
XS GIS Cut Line= 3
      2753486.73      6753882.82       2753059.7       6753934.9
      2752663.86       6754122.4
#Sta/Elev= 30
  4487.6  375.81  4558.9  371.43  4676.9  359.98  4793.5   352.8  4830.9  351.05
  4871.1   346.9  4891.7  345.87  4917.1  344.47  4923.9  346.15  4946.6  346.57
  4963.9  344.98  4986.6  344.01  4992.1  341.97  4999.3  340.33  5012.8  334.97
  5013.1  334.47  5016.6  334.47  5016.9  334.97  5020.5  335.32  5021.5  335.42
  5032.1  342.27  5043.6  345.49  5065.9  346.56  5076.8  345.77  5083.1  343.55
  5088.6  345.88  5122.4  346.82  5140.2  347.09  5293.4  350.33  5355.8  352.45
#Mann= 8 ,-1 , 0
  4487.6     .05       0  4793.5     .12       0  4891.7      .1       0
  5012.8     .07       0  5016.9      .1       0  5020.5     .12       0
  5122.4      .1       0  5140.2     .05       0
Bank Sta=5012.8,5016.9
XS Rating Curve= 0 ,0
Exp/Cntr=0.3,0.1

Type RM Length L Ch R = 1 ,6254    ,386,386,386
BEGIN DESCRIPTION:
Walnut4 9.0
END DESCRIPTION:
XS GIS Cut Line= 3
      2753335.76       6753565.1        2752876.        6753711.
      2752450.67      6753898.29
#Sta/Elev= 30
  4517.3  369.17  4585.8  367.75  4674.4  362.93  4726.9  355.73  4783.6  350.43
  4816.9  346.62  4863.3  345.33  4894.7  340.53  4905.2  340.19  4913.7  344.61
    4919  341.92  4926.2  341.54  4934.6  333.92    4935  333.42  4938.8  333.92
  4951.3  334.92  4957.7  340.86  4968.2   341.9  4989.2  343.02  5008.6  341.22
  5014.1  343.19  5031.9  344.71  5084.9  344.35    5098  344.27  5107.4  340.97
  5112.9  340.94  5141.7  345.19  5287.1  351.99  5432.6  361.63  5464.4  361.65
#Mann= 5 ,-1 , 0
  4517.3     .05       0  4783.6     .12       0  4934.6     .07       0
  4938.8     .12       0  5084.9     .05       0
Bank Sta=4934.6,4938.8
XS Rating Curve= 0 ,0
Exp/Cntr=0.3,0.1

Type RM Length L Ch R = 1 ,5868    ,564,564,564
BEGIN DESCRIPTION:
Walnut4 8.0
END DESCRIPTION:
XS GIS Cut Line= 3
      2753497.22      6753273.43      2752971.15      6753356.77
      2752486.79      6753419.27
#Sta/Elev= 30
  4270.4  367.26  4349.1  368.02  4411.5  366.41    4464  363.53  4484.2  360.82
  4541.2   356.2  4546.3  356.79  4603.5   353.8  4608.6  354.52  4636.1  353.63
  4696.9   346.3  4733.2  343.55    4780  342.34  4948.8  343.93  4959.5   341.2
  4989.7  341.19  4999.8  340.07  5017.8  331.17  5018.2  330.67  5022.1  331.17
  5028.2  339.62  5040.1   342.7  5050.2  343.54  5059.2  345.79  5080.5  346.74
  5100.6  348.99  5120.8  353.32    5187   361.7  5261.4  368.63  5291.4  369.79
#Mann= 5 ,-1 , 0
  4270.4     .05       0    4780     .12       0  5017.8     .07       0
  5022.1     .12       0  5059.2     .05       0
Bank Sta=5017.8,5022.1
XS Rating Curve= 0 ,0
Exp/Cntr=0.3,0.1

Type RM Length L Ch R = 1 ,5304    ,413,413,413
BEGIN DESCRIPTION:
Walnut4 7.0
END DESCRIPTION:
XS GIS Cut Line= 3
      2753366.94      6752986.98      2752887.82      6753039.06
      2752471.16      6753054.69
#Sta/Elev= 30
  4456.6  364.35    4528  363.21  4608.4  357.93  4633.1  357.88  4648.7  354.31
  4724.6  345.09  4789.5  341.43  4829.7  342.36  4839.8  340.67  4850.4  337.42
  4859.9  335.31    4880  338.45  4890.1   338.8  4907.7  336.88  4912.7  338.22
  4930.3  335.03  4934.8  329.51  4935.1  329.01  4939.1  329.51  4950.4  330.04
  4980.4  339.03  5010.4  342.51  5041.2  342.49  5070.5   343.8  5090.5  346.09
  5140.3  354.39  5200.5  361.45  5240.6  364.84  5270.6     366  5355.5  366.51
#Mann= 6 ,-1 , 0
  4456.6     .05       0  4850.4      .1       0  4934.8     .07       0
  4939.1      .1       0  5041.2     .12       0  5140.3     .05       0
Bank Sta=4934.8,4939.1
XS Rating Curve= 0 ,0
Exp/Cntr=0.3,0.1

Type RM Length L Ch R = 1 ,4891    ,482,482,482
BEGIN DESCRIPTION:
Walnut4 6.0
END DESCRIPTION:
XS GIS Cut Line= 3
      2753252.39      6752481.78      2752820.11      6752669.27
      2752430.23       6752892.8
#Sta/Elev= 30
  4431.3  362.22  4442.8  362.75  4481.9  362.12    4618  349.53  4664.9  344.19
  4699.9  341.37    4717  340.88  4740.7  340.23  4754.4  341.15    4817  340.12
  4838.5  340.08  4941.8  339.77  4951.9  336.64  4957.7  328.19  4962.7  327.77
  4963.1  327.27    4967  327.77  4973.5   328.5  4979.2  333.09  4987.9   336.6
  5016.6  338.08  5045.6   342.3    5054  339.69  5075.6  344.44  5097.2  344.72
  5103.2  344.09  5114.6   345.5    5172  349.04  5264.6  357.98  5351.9  363.65
#Mann= 7 ,-1 , 0
  4431.3     .05       0    4717     .12       0    4817     .05       0
  4838.5     .12       0  4962.7     .07       0    4967     .12       0
  5114.6     .05       0
Bank Sta=4962.7,4967
XS Rating Curve= 0 ,0
Exp/Cntr=0.3,0.1

Type RM Length L Ch R = 1 ,4409    ,442,442,442
BEGIN DESCRIPTION:
Walnut4 5.0
END DESCRIPTION:
XS GIS Cut Line= 4
      2753033.67      6752138.01      2752486.78       6752497.4
      2752283.65      6752554.69      2752148.23      6752804.71
#Sta/Elev= 30
  4230.2  356.27  4353.5  358.19  4404.8  355.61  4431.8  352.62    4462   350.9
  4483.1  348.08  4513.2  346.34  4519.2  344.87  4570.5  341.65  4576.5  340.33
  4616.7  339.15  4628.6  338.59  4906.2  338.11    4919  336.46  4947.8  336.71
    4953  335.43  4968.5  334.94  4978.9  333.63    4987  328.41  4997.5   326.7
  4997.9   326.2  5001.9   326.7  5010.1  333.25  5020.5  339.88  5026.2  341.42
    5038  341.86  5095.7  344.56  5274.2  361.49  5328.4  364.21    5380  363.84
#Mann= 7 ,-1 , 0
  4230.2     .05       0  4513.2     .12       0  4616.7     .05       0
  4628.6     .12       0  4997.5     .07       0  5001.9     .12       0
    5038     .05       0
Bank Sta=4997.5,5001.9
XS Rating Curve= 0 ,0
Exp/Cntr=0.3,0.1

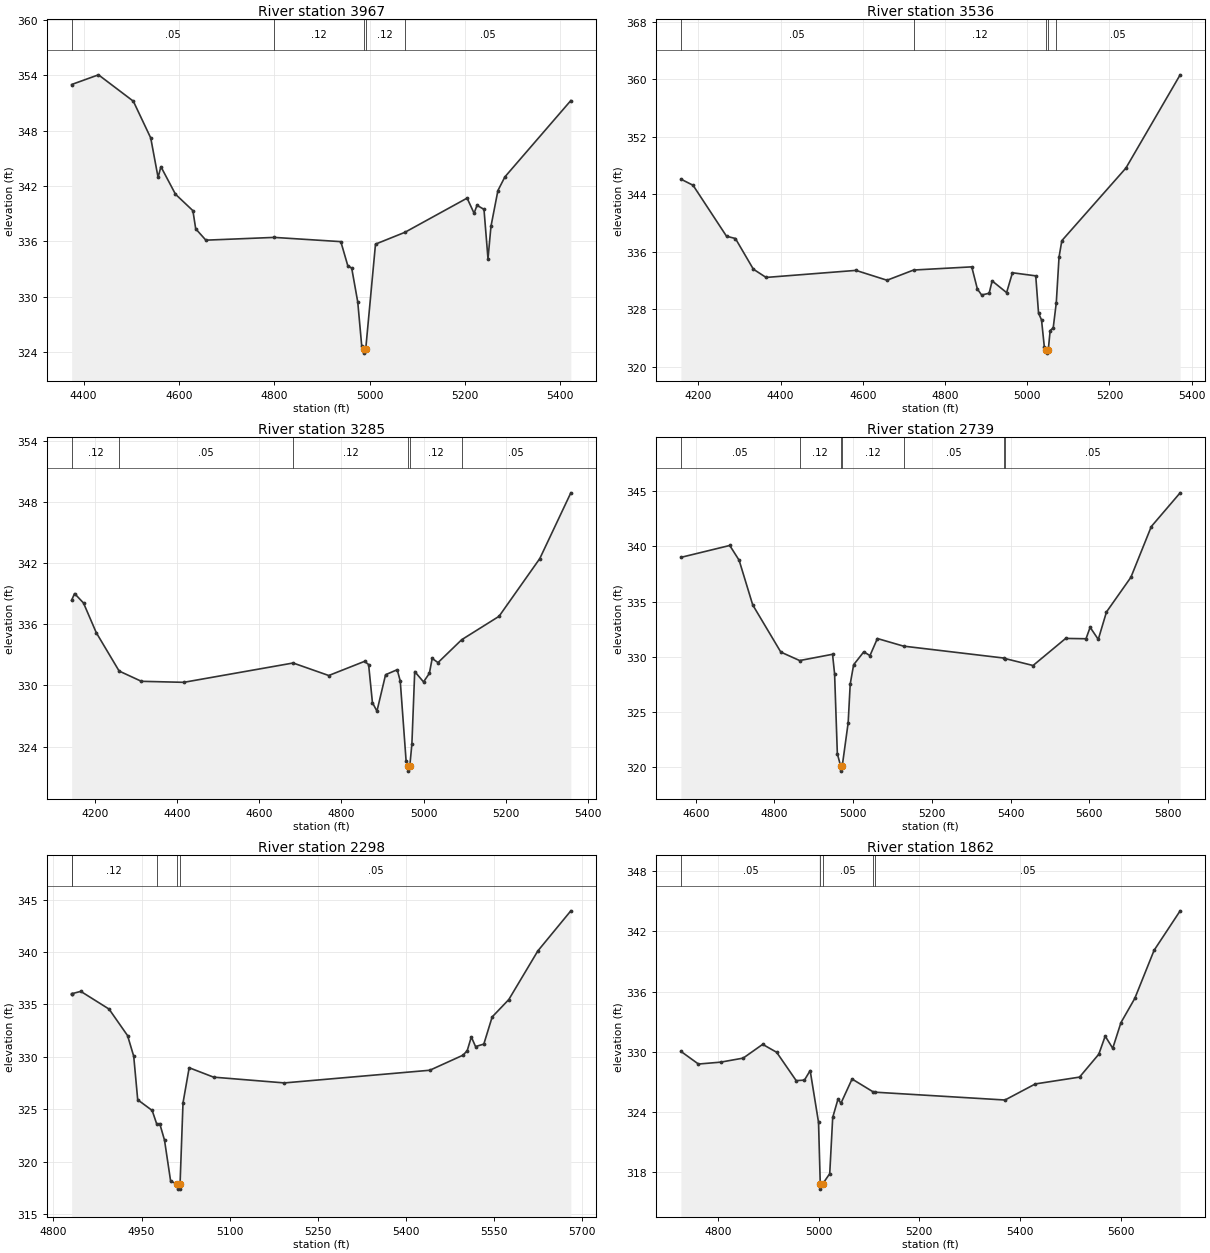
Type RM Length L Ch R = 1 ,3967    ,431,431,431
BEGIN DESCRIPTION:
Walnut4 4.0
END DESCRIPTION:
XS GIS Cut Line= 3
      2752752.44      6751898.41      2752278.45      6752195.31
      2751887.83      6752486.98
#Sta/Elev= 30
  4375.1  352.99  4431.4  354.04  4504.5  351.18    4541  347.19  4556.4  342.91
  4562.3  344.08  4592.9  341.09  4629.4  339.31  4635.3  337.34  4656.6  336.11
  4799.9  336.41  4939.6  335.95  4954.2  333.34  4962.4  333.08  4975.1   329.4
  4983.4  324.64  4987.5  324.36  4987.9  323.86  4991.9  324.36  5012.3  335.68
  5073.9  336.96  5204.4  340.67    5219  339.03  5225.2  339.89  5239.8  339.45
  5248.2  334.08  5254.4   337.6    5269  341.49  5283.6  342.97  5421.9  351.25
#Mann= 5 ,-1 , 0
  4375.1     .05       0  4799.9     .12       0  4987.5     .07       0
  4991.9     .12       0  5073.9     .05       0
Bank Sta=4987.5,4991.9
XS Rating Curve= 0 ,0
Exp/Cntr=0.3,0.1

Type RM Length L Ch R = 1 ,3536    ,251,251,251
BEGIN DESCRIPTION:
Walnut4 3.5
END DESCRIPTION:
XS GIS Cut Line= 3
      2752627.38      6751611.99      2751986.78      6751966.15
       2751632.6      6752294.28
#Sta/Elev= 30
  4157.3   346.1  4186.8  345.25  4268.2  338.17  4289.9  337.85  4333.5  333.59
  4364.5  332.44  4583.2  333.42  4658.8  332.05  4723.5  333.47    4865  333.91
  4878.7  330.82  4889.1     330  4907.3  330.24  4914.6  331.96  4949.8  330.33
    4964  333.09  5020.7  332.66  5027.5  327.49  5034.8  326.53  5041.7  322.72
  5046.8  322.42  5047.2  321.92  5051.3  322.42  5055.8  325.06  5063.2  325.42
  5070.7  328.92  5077.4  335.27  5084.2  337.55  5240.1  347.64  5372.1   360.6
#Mann= 5 ,-1 , 0
  4157.3     .05       0  4723.5     .12       0  5046.8     .07       0
  5051.3     .12       0  5070.7     .05       0
Bank Sta=5046.8,5051.3
XS Rating Curve= 0 ,0
Exp/Cntr=0.3,0.1

Type RM Length L Ch R = 1 ,3285    ,546,546,546
BEGIN DESCRIPTION:
Walnut4 3.0
END DESCRIPTION:
XS GIS Cut Line= 3
      2752528.47      6751393.22      2751887.82       6751747.4
      2751533.68       6752075.5
#Sta/Elev= 30
  4143.4  338.38  4150.5  339.04  4172.3  338.11  4203.4  335.19    4259  331.42
  4313.2  330.41  4416.3  330.31  4682.4  332.21  4769.1  330.98  4856.1  332.37
  4866.1  332.06  4875.4  328.31  4886.4  327.48  4907.4  331.06  4935.7  331.55
  4943.1  330.44  4957.3   322.6  4961.8  322.08  4962.3  321.58  4966.3  322.08
  4971.4  324.23  4978.3  331.37  4999.8  330.35    5014   331.2  5020.8  332.66
    5035  332.25  5092.6   334.5  5183.5   336.8  5282.7  342.48  5358.2  348.94
#Mann= 6 ,-1 , 0
  4143.4     .12       0    4259     .05       0  4682.4     .12       0
  4961.8     .07       0  4966.3     .12       0  5092.6     .05       0
Bank Sta=4961.8,4966.3
XS Rating Curve= 0 ,0
Exp/Cntr=0.3,0.1

Type RM Length L Ch R = 1 ,2739    ,441,441,441
BEGIN DESCRIPTION:
Walnut4 2.0
END DESCRIPTION:
XS GIS Cut Line= 3
      2752283.64       6751247.4       2751934.7      6751393.23
      2751075.28      6751627.62
#Sta/Elev= 30
  4562.2  339.01  4686.3  340.09  4710.1  338.75  4744.7  334.69  4816.1  330.41
    4864  329.64  4947.6  330.21  4952.8  328.43  4959.8  321.18  4967.9   320.1
  4968.3   319.6  4972.4   320.1  4987.3  323.99  4992.5   327.5  5001.2  329.26
    5027  330.43  5042.7  330.09  5061.6  331.64    5128  330.95  5382.4  329.87
  5386.4  329.82  5457.3  329.19  5540.2  331.65  5591.9  331.62  5602.4  332.66
  5623.1  331.56  5643.9  334.05    5706   337.2  5757.9  341.81  5831.2  344.87
#Mann= 7 ,-1 , 0
  4562.2     .05       0    4864     .12       0  4967.9     .07       0
  4972.4     .12       0    5128     .05       0  5382.4     .12       0
  5386.4     .05       0
Bank Sta=4967.9,4972.4
XS Rating Curve= 0 ,0
Exp/Cntr=0.3,0.1

Type RM Length L Ch R = 1 ,2298    ,436,436,436
BEGIN DESCRIPTION:
Walnut4 1.8
END DESCRIPTION:
XS GIS Cut Line= 3
      2751736.75      6751101.57      2751424.28      6751200.52
      2751060.38      6751574.82
#Sta/Elev= 30
    4831  336.03  4831.6  336.03  4846.6  336.25  4894.7  334.56  4926.2  332.03
  4936.7  330.06  4943.5   325.9  4968.1  324.88  4975.8   323.6    4981  323.62
  4989.1  322.05  4999.6  318.11  5011.1  317.87  5011.5  317.37  5015.1  317.37
  5015.6  317.87  5020.6   325.6  5031.1  328.96  5072.7  328.06  5193.2  327.51
  5440.7  328.72  5497.3  330.16  5504.4  330.59  5511.4   331.9  5518.6  330.98
  5532.7  331.22  5546.9  333.81  5575.2  335.47  5624.6  340.11  5680.8  343.94
#Mann= 5 ,-1 , 0
    4831     .05       0  4831.6     .12       0  4975.8     .05       0
  5011.1     .04       0  5015.6     .05       0
Bank Sta=5011.1,5015.6
XS Rating Curve= 0 ,0
Exp/Cntr=0.3,0.1

Type RM Length L Ch R = 1 ,1862    ,484,484,484
BEGIN DESCRIPTION:
Walnut4 1.6
END DESCRIPTION:
XS GIS Cut Line= 3
      2751455.52      6750622.41      2751221.15      6751080.73
       2750997.2       6751502.6
#Sta/Elev= 30
  4726.1  330.04  4760.9  328.78  4805.3  328.97  4849.8  329.37  4888.6  330.74
  4916.4  329.95  4955.2  327.13  4971.6  327.18    4983  328.13  4999.6  322.99
  5003.1  316.83  5003.5  316.33  5007.6  316.83  5021.9  317.87  5027.8  323.46
  5038.5  325.32  5044.1  324.87  5066.3  327.29  5107.6  326.03  5111.8  325.98
  5370.3   325.2  5430.6   326.8  5518.5  327.48  5556.8  329.76  5569.5  331.56
  5584.5  330.35  5600.8   332.9  5628.4  335.32  5666.7   340.1  5718.5  344.03
#Mann= 5 ,-1 , 0
  4726.1     .05       0  5003.1     .04       0  5007.6     .05       0
  5107.6     .12       0  5111.8     .05       0
Bank Sta=5003.1,5007.6
XS Rating Curve= 0 ,0
Exp/Cntr=0.3,0.1