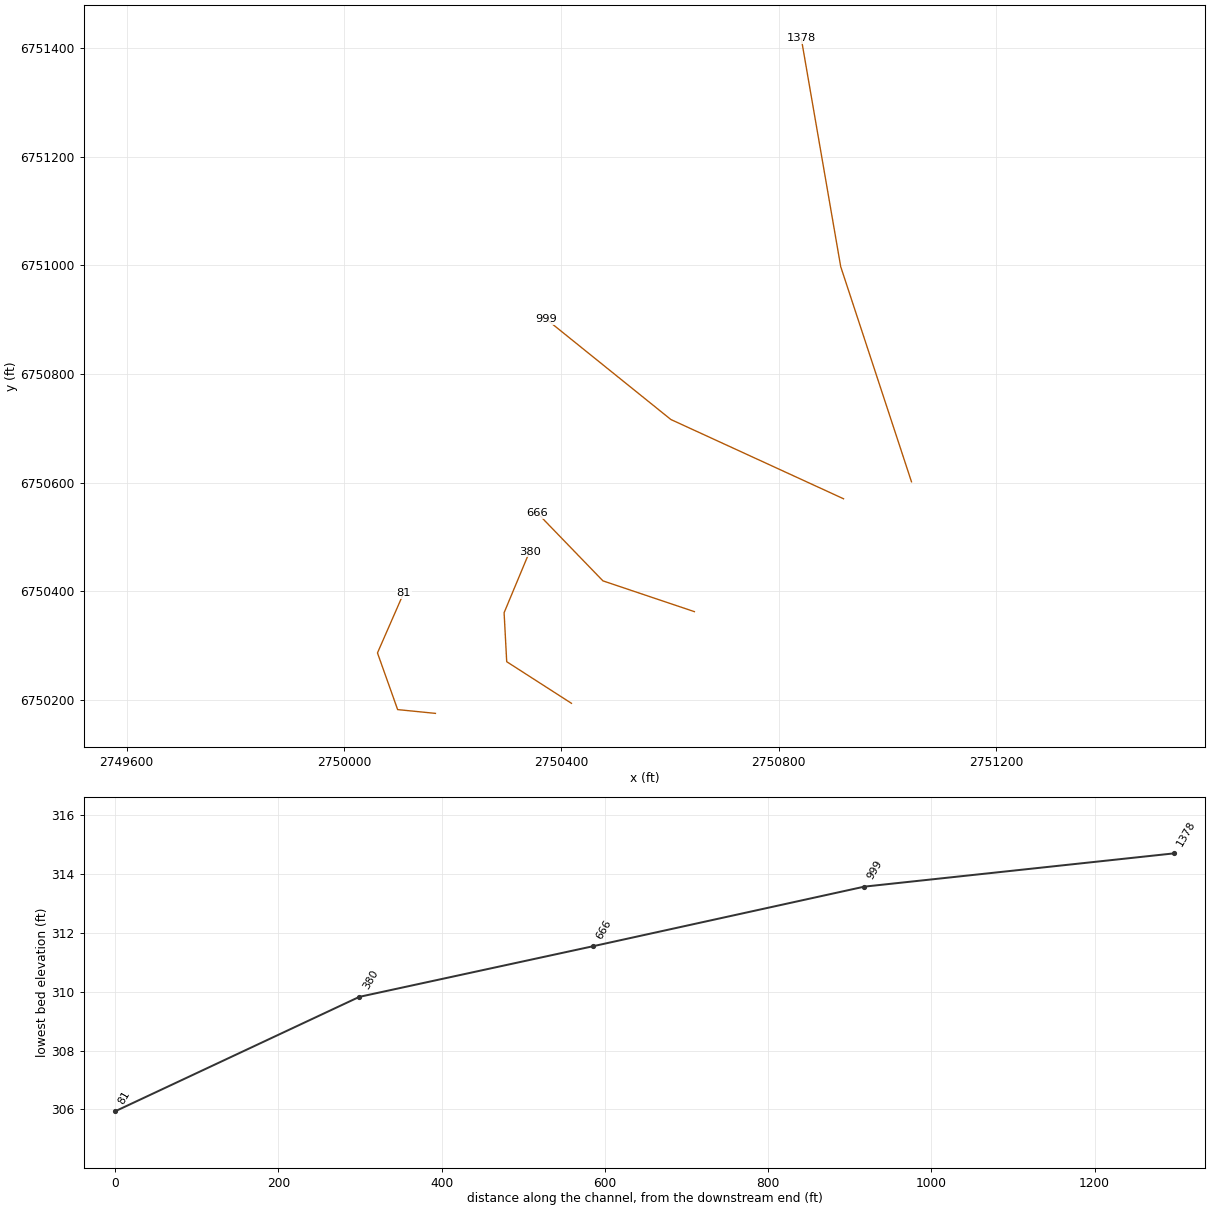
HEC-RAS study Walnut4.prj: Walnut4 Base Level Engineering

--- Walnut4.g01 (geometry) --- (continued)

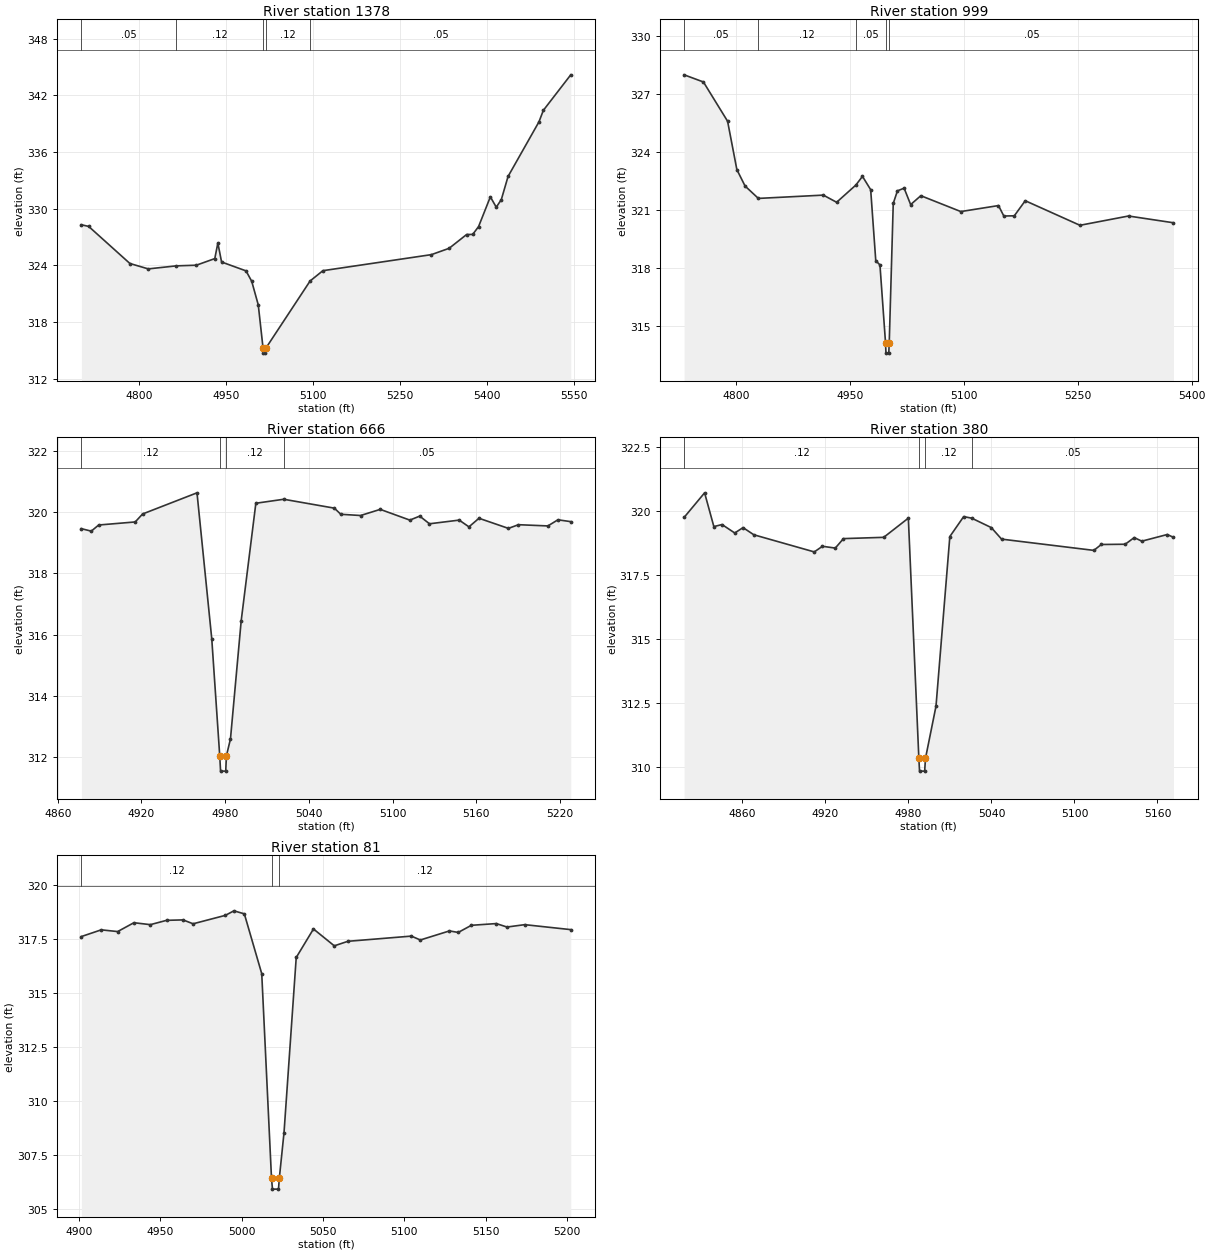
Type RM Length L Ch R = 1 ,1378    ,379,379,379
BEGIN DESCRIPTION:
Walnut4 1.3
END DESCRIPTION:
XS GIS Cut Line= 3
      2751044.07      6750601.56      2750913.86       6750997.4
      2750841.26      6751417.47
#Sta/Elev= 30
  4700.7   328.3  4713.2  328.13  4784.3   324.2  4815.9  323.63  4864.2  323.95
  4898.7  324.02  4930.5  324.72  4935.8  326.37  4942.2  324.36  4984.3  323.42
  4994.1  322.32  5005.4  319.82  5013.7  315.21  5014.1  314.71  5017.7  314.71
  5018.2  315.21  5094.7  322.35  5116.7  323.44  5303.7  325.14  5334.2  325.81
  5364.3  327.27  5374.8  327.28  5384.9  328.11  5405.2  331.26  5415.4  330.16
  5424.1  330.97  5435.7  333.42    5489  339.21  5496.5  340.42  5543.7  344.18
#Mann= 5 ,-1 , 0
  4700.7     .05       0  4864.2     .12       0  5013.7     .04       0
  5018.2     .12       0  5094.7     .05       0
Bank Sta=5013.7,5018.2
XS Rating Curve= 0 ,0
Exp/Cntr=0.3,0.1

Type RM Length L Ch R = 1 ,999     ,333,333,333
BEGIN DESCRIPTION:
Walnut4 1.0
END DESCRIPTION:
XS GIS Cut Line= 3
      2750919.08      6750570.31      2750601.36      6750716.15
      2750372.07       6750900.8
#Sta/Elev= 30
  4732.1  327.97  4757.5   327.6  4789.3  325.57  4801.5  323.07  4812.3  322.22
  4829.8  321.58  4915.3  321.75  4932.8  321.38  4958.1  322.27  4966.8  322.72
  4977.6  322.03  4984.3  318.36  4989.8  318.14  4997.2  314.08  4997.7  313.58
  5001.4  313.58    5002  314.08  5007.3  321.32  5012.8  321.97  5021.6  322.11
  5030.2  321.26  5043.6  321.72  5096.2   320.9  5145.8  321.21  5152.8  320.67
  5166.6  320.68    5181  321.46    5253  320.19  5316.9  320.67  5376.1  320.32
#Mann= 5 ,-1 , 0
  4732.1     .05       0  4829.8     .12       0  4958.1     .05       0
  4997.2     .04       0    5002     .05       0
Bank Sta=4997.2,5002
XS Rating Curve= 0 ,0
Exp/Cntr=0.3,0.1

Type RM Length L Ch R = 1 ,666     ,286,286,286
BEGIN DESCRIPTION:
Walnut4 0.6
END DESCRIPTION:
XS GIS Cut Line= 3
       2750644.6      6750362.67      2750476.36      6750419.27
      2750355.84      6750543.94
#Sta/Elev= 30
  4876.9  319.46    4884  319.38  4889.3  319.58  4915.5  319.68  4920.8  319.94
  4959.8  320.63  4970.4  315.86  4976.1  312.05  4976.7  311.55  4980.4  311.55
  4980.9  312.05  4983.8   312.6  4991.5  316.46    5002  320.29    5022  320.42
  5058.3  320.13  5062.9  319.93  5077.1  319.89  5091.2  320.09  5112.4  319.74
  5119.5  319.87  5126.5  319.62  5147.8  319.74  5154.8  319.52    5162   319.8
  5183.1  319.47  5190.3  319.59  5211.4  319.55  5218.6  319.75  5227.8  319.69
#Mann= 4 ,-1 , 0
  4876.9     .12       0  4976.1     .07       0  4980.9     .12       0
    5022     .05       0
Bank Sta=4976.1,4980.9
XS Rating Curve= 0 ,0
Exp/Cntr=0.3,0.1

Type RM Length L Ch R = 1 ,380     ,299,299,299
BEGIN DESCRIPTION:
Walnut4 0.3
END DESCRIPTION:
XS GIS Cut Line= 4
      2750418.42        6750194.      2750299.32      6750270.55
      2750294.53      6750360.67      2750341.47      6750473.25
#Sta/Elev= 30
  4817.8  319.75  4832.6  320.71  4839.3  319.39  4845.2  319.47  4854.4  319.14
  4860.4  319.35  4868.2  319.07  4911.9   318.4  4917.8  318.62  4927.1  318.55
    4933  318.92  4962.1  318.97  4979.9  319.72  4987.5  310.33    4988  309.83
  4991.7  309.83  4992.3  310.33  4999.9  312.37  5009.9     319  5019.9  319.78
  5025.7  319.72  5039.9  319.35  5047.3   318.9    5114  318.46  5119.4  318.69
  5136.7   318.7  5143.2  318.96  5148.7  318.82  5167.1  319.08  5171.6  318.97
#Mann= 4 ,-1 , 0
  4817.8     .12       0  4987.5     .07       0  4992.3     .12       0
  5025.7     .05       0
Bank Sta=4987.5,4992.3
XS Rating Curve= 0 ,0
Exp/Cntr=0.3,0.1

Type RM Length L Ch R = 1 ,81      ,0,0,0
BEGIN DESCRIPTION:
Walnut4 0.1
END DESCRIPTION:
XS GIS Cut Line= 4
      2750168.18      6750175.46      2750098.63      6750182.42
      2750061.55       6750286.7      2750109.78      6750396.93
#Sta/Elev= 30
  4901.5  317.63  4913.7  317.94  4923.8  317.86  4933.8  318.27  4943.9  318.18
  4953.9  318.38    4964   318.4  4970.2  318.22    4990  318.61  4995.3  318.82
  5001.7  318.68  5012.4  315.91  5018.4  306.44    5019  305.94  5022.7  305.94
  5023.2  306.44  5026.1  308.56  5033.6  316.66  5044.2  317.98    5057   317.2
  5065.4  317.41  5104.4  317.65  5109.9  317.47  5127.8  317.89  5133.2  317.82
  5141.3  318.15  5156.6  318.23  5163.2  318.07  5174.1  318.18  5202.4  317.95
#Mann= 3 ,-1 , 0
  4901.5     .12       0  5018.4     .07       0  5023.2     .12       0
Bank Sta=5018.4,5023.2
XS Rating Curve= 0 ,0
Exp/Cntr=0.3,0.1

Chan Stop Cuts=-1
Use User Specified Reach Order=0
Composite Channel Slope=5