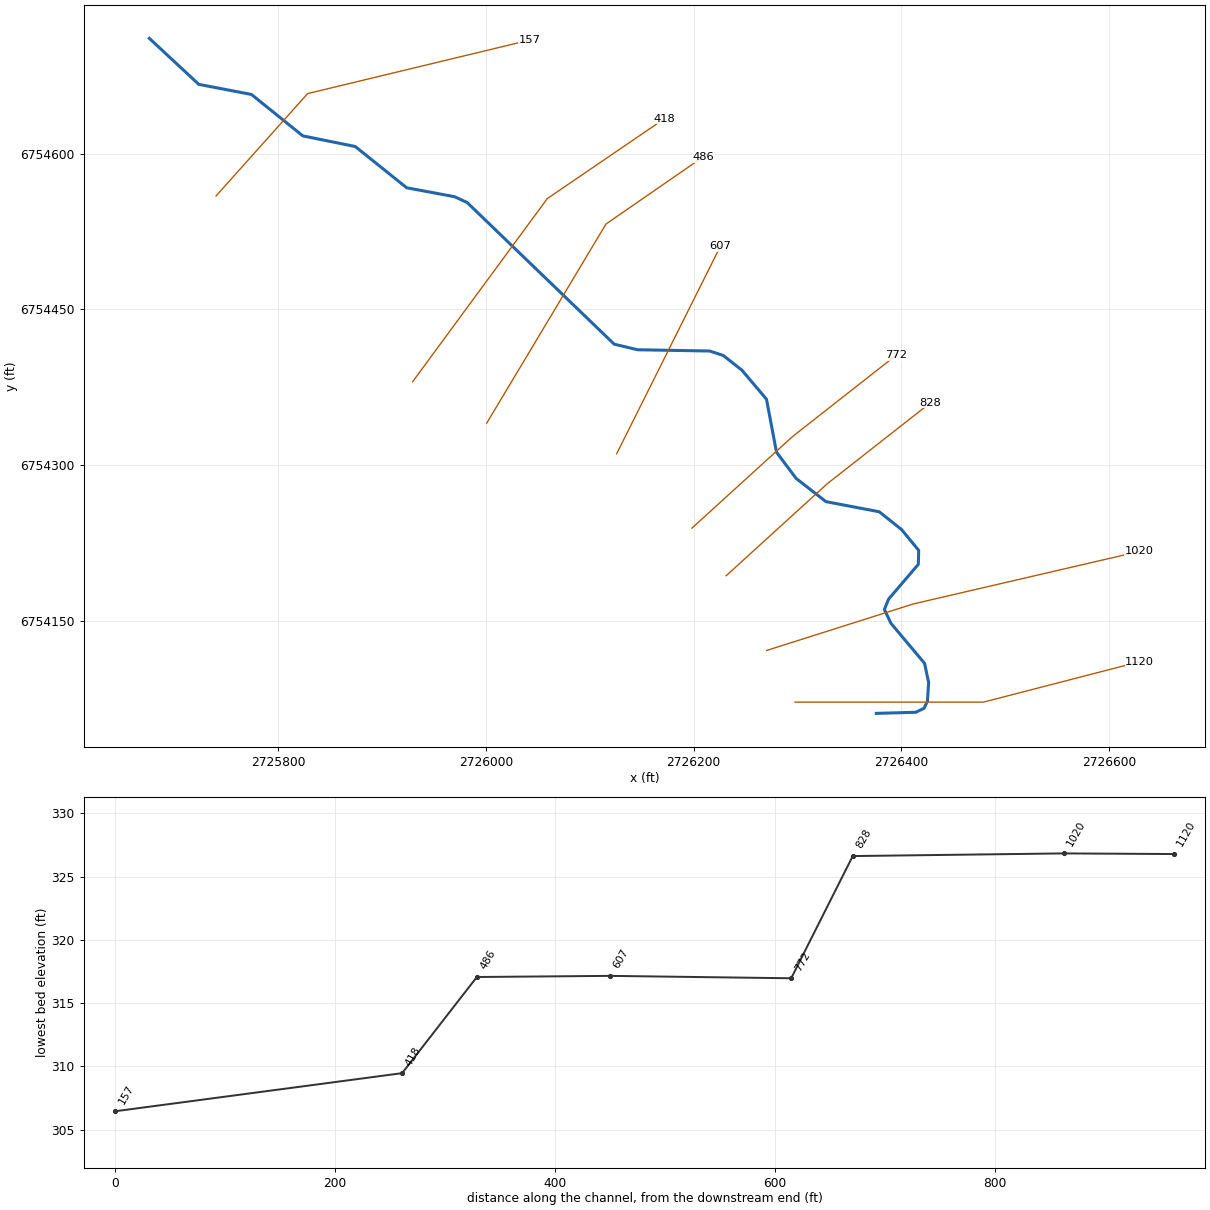
--- Walnut40.prj (project) ---

Proj Title=Walnut40 Base Level Engineering
Current Plan=p01
Default Exp/Contr=0.3,0.1
English Units
Geom File=g01
Flow File=f01
Plan File=p01
Y Axis Title=Elevation
X Axis Title(PF)=Main Channel Distance
X Axis Title(XS)=Station
BEGIN DESCRIPTION:
Walnut40
END DESCRIPTION:
DSS Export Rating Curves= 0
DSS Export Rating Curve Sorted= 0
DSS Export Volume Flow Curves= 0
DXF OffsetX= 0
DXF OffsetY= 0
DXF ScaleX= 1
DXF ScaleY= 10

--- Walnut40.p01 (plan) ---

Plan Title=Multiple Run
Program Version=4.10
Short Identifier=Multiple
Geom File=g01
Flow File=f01
Subcritical Flow
K Sum by GR= 0
Std Step Tol= 0.01
Critical Tol= 0.01
Num of Std Step Trials= 20
Max Error Tol= 0.3
Flow Tol Ratio= 0.001
Split Flow NTrial= 30
Split Flow Tol= 0.02
Split Flow Ratio= 0.02
Log Output Level= 0
Friction Slope Method= 1
Unsteady Friction Slope Method= 2
Unsteady Bridges Friction Slope Method= 1
Parabolic Critical Depth
Global Vel Dist= 1 , 1 , 1
Global Log Level= 0
CheckData=True
Encroach Param=-1 ,0,0, 0
BEGIN DESCRIPTION:
Multiple Run
END DESCRIPTION:
Computation Interval=1HOUR
Output Interval=1HOUR
Run HTab= 0
Run UNet= 0
Run PostProcess= 0
Run WQNet= 0
UNET Theta= 1
UNET Theta Warmup= 1
UNET ZTol= 0.02
UNET ZSATol= 0.05
UNET MxIter= 20
UNET MaxInSteps= 0
UNET DtIC= 0
UNET DtMin= 0
UNET MaxCRTS= 20
UNET WFStab= 2
UNET SFStab= 1
UNET WFX= 1
UNET SFX= 1
UNET DSS MLevel= 4
UNET DZMax Abort= 100
UNET Convert EG Bridges= 0
UNET Use Existing IB Tables=-1
UNET Froude Reduction=False
UNET Froude Limit= 1
UNET Froude Power= 10
UNET Time Slicing=0,0, 5
UNET Junction Losses=0
Instantaneous Interval=1HOUR
Write IC File= 0
Write IC File at Sim End=0
Echo Input=False
Echo Parameters=False
Echo Output=False
Write Detailed= 0
WQ AD Non Conservative
WQ ULTIMATE=-1
WQ Max Comp Step=1HOUR
WQ Output Interval=15MIN
WQ Output Selected Increments= 0
WQ Output face flow=0
WQ Output face velocity=0
WQ Output face area=0
WQ Output face dispersion=0
WQ Output cell volume=0
WQ Output cell surface area=0
WQ Output cell continuity=0
WQ Output cumulative cell continuity=0
WQ Output face conc=0
WQ Output face dconc_dx=0
WQ Output face courant=0
WQ Output face peclet=0
WQ Output face adv mass=0
WQ Output face disp mass=0
WQ Output cell mass=0
WQ Output cell source sink temp=0
WQ Output cell source sink nsm=0
WQ Output MaxMinRange=-1
WQ Daily Max Min Mean=-1
WQ Daily Range=0
WQ Daily Time=0
WQ Create Restart=0
WQ Fixed Restart=0
WQ System Summary=0
WQ Use Fixed Temperature=0
Sorting and Armoring Iterations= 10
XS Update Threshold= 0.02
Hydraulics Update Threshold= 0.02
Energy Slope Method= 1
Volume Change Method= 0
XS Weighting Method= 0
Number of US Weighted Cross Sections= 1
Number of DS Weighted Cross Sections= 1
Upstream XS Weight=0.25
Main XS Weight=0.5
Downstream XS Weight=0.25
Number of DS XS's Weighted with US Boundary= 1
Upstream Boundary Weight= 1
Weight of XSs Associated with US Boundary= 0
Number of US XS's Weighted with DS Boundary= 1
Downstream Boundary Weight= 0.5
Weight of XSs Associated with DS Boundary= 0.5
Sediment Output Level= 4
Mass or Volume Output= 0
Output Increment Type= 1
Profile and TS Output Increment= 10
XS Output Flag= 0
XS Output Increment= 10
Disregard all LS=0
Disregard all Conn=0
Disregard all Breaches=0
Disregard all Pumps=0

--- Walnut40.f01 (steady flow) ---

Flow Title=Multiple
Program Version=4.10
Number of Profiles= 7
Profile Names=10-year,25-year,50-year,1pct_min,100-year,1pct_plu,500-year
River Rch & RM=Walnut40,Reach-1         ,1120
      66      76      84      46      92     184     111
Boundary for River Rch & Prof#=Walnut40,Reach-1         , 1
Up Type= 0
Dn Type= 3
Dn Slope=0.012
Boundary for River Rch & Prof#=Walnut40,Reach-1         , 2
Up Type= 0
Dn Type= 3
Dn Slope=0.012
Boundary for River Rch & Prof#=Walnut40,Reach-1         , 3
Up Type= 0
Dn Type= 3
Dn Slope=0.012
Boundary for River Rch & Prof#=Walnut40,Reach-1         , 4
Up Type= 0
Dn Type= 3
Dn Slope=0.012
Boundary for River Rch & Prof#=Walnut40,Reach-1         , 5
Up Type= 0
Dn Type= 3
Dn Slope=0.012
Boundary for River Rch & Prof#=Walnut40,Reach-1         , 6
Up Type= 0
Dn Type= 3
Dn Slope=0.012
Boundary for River Rch & Prof#=Walnut40,Reach-1         , 7
Up Type= 0
Dn Type= 3
Dn Slope=0.012
DSS Import GetInterval= 0
DSS Import GetPeak= 0
DSS Import FillOption= 0

--- Walnut40.g01 (geometry) ---

Geom Title=Existing Conditions

River Reach=Walnut40,Reach-1
Reach XY= 30
      2726376.00      6754061.00      2726414.03      6754062.05
      2726421.98      6754065.92      2726425.23      6754072.76
      2726426.40      6754090.78      2726422.48      6754109.19
      2726390.06      6754147.77      2726383.80      6754161.08
      2726387.86      6754171.06      2726416.47      6754204.49
      2726416.82      6754217.95      2726400.35      6754237.98
      2726378.81      6754255.13      2726327.50      6754264.89
      2726298.87      6754287.17      2726279.90      6754312.46
      2726270.25      6754363.55      2726246.54      6754391.53
      2726228.67      6754405.58      2726215.67      6754409.90
      2726146.06      6754411.14      2726123.58      6754416.53
      2725982.06      6754552.86      2725969.96      6754558.50
      2725923.81      6754567.10      2725874.28      6754606.84
      2725823.80      6754617.07      2725774.33      6754656.96
      2725723.64      6754666.67      2725676.00      6754711.00

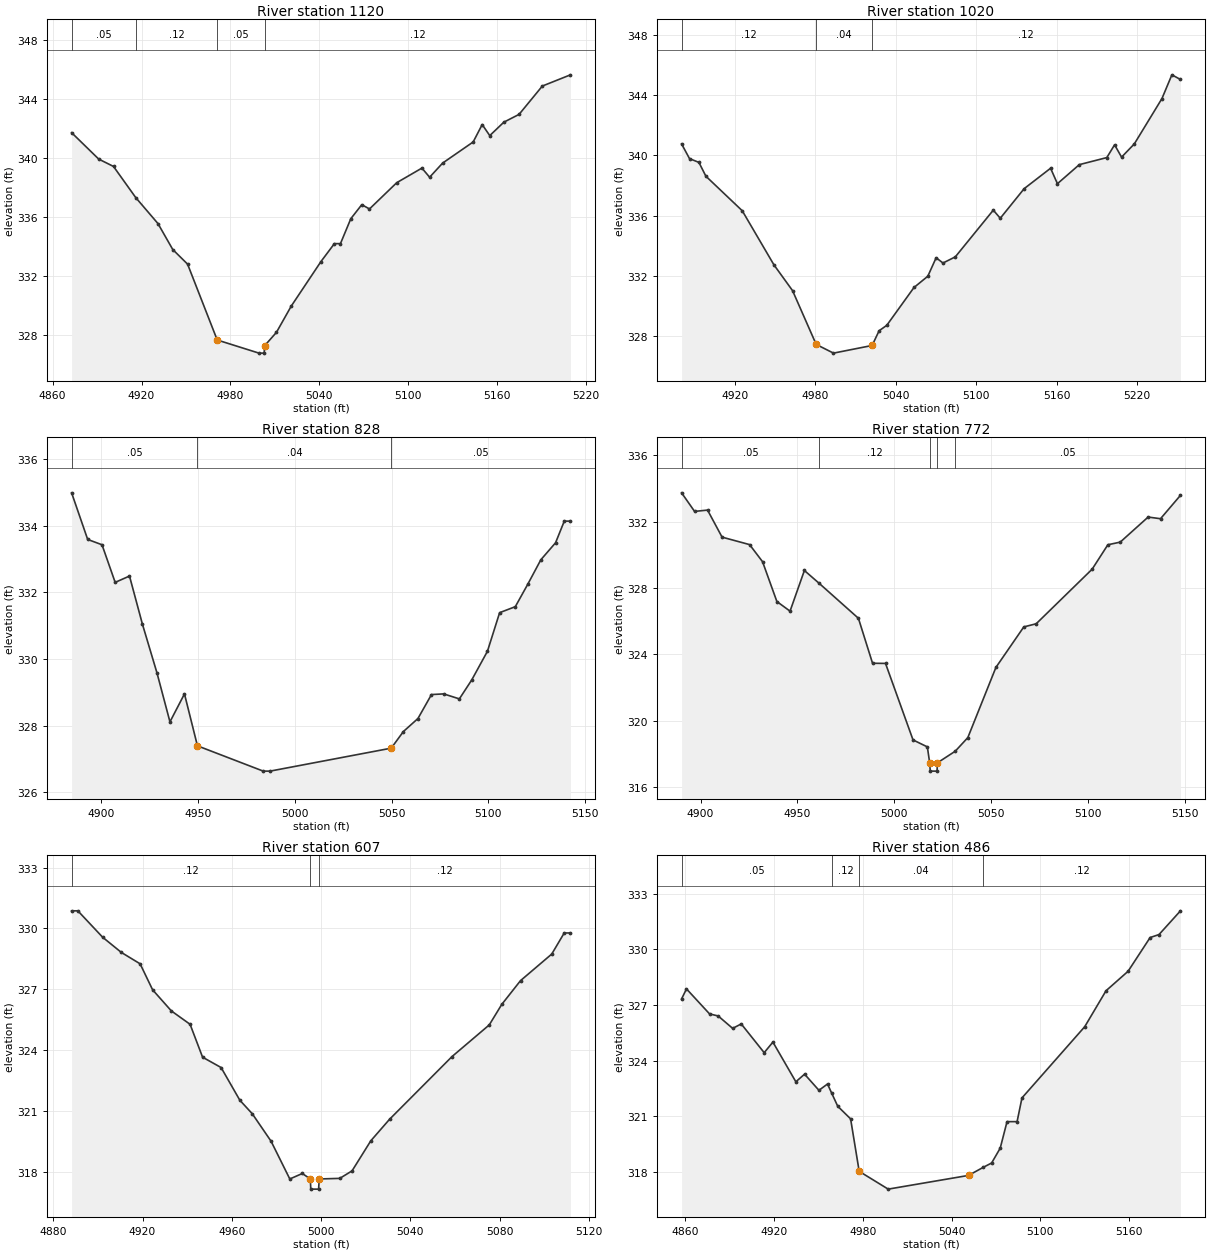
Type RM Length L Ch R = 1,1120,100,100,100
BEGIN DESCRIPTION:
Walnut40 3.0
END DESCRIPTION:
XS GIS Cut Line= 3
      2726297.71      6754071.83      2726479.21      6754071.83
      2726629.56      6754110.72
#Sta/Elev= 30
  4872.8  341.73  4891.1  339.94  4901.1  339.44  4916.1  337.33  4931.1  335.57
  4941.1  333.81  4951.1  332.82  4971.1  327.68  4999.3  326.79  5002.8  326.79
  5003.1  327.29  5011.1  328.20  5021.1  329.98  5041.1  332.99  5050.2  334.21
  5054.3  334.21  5061.3  335.90  5068.7  336.85  5073.9  336.56  5092.3  338.34
  5109.3  339.33  5114.5  338.71  5123.3  339.67  5143.9  341.10  5150.0  342.28
  5155.1  341.53  5164.6  342.44  5174.9  342.97  5190.6  344.89  5209.6  345.65
#Mann=4,-1,0
  4872.8    0.05       0  4916.1    0.12       0  4971.1    0.05       0
  5003.1    0.12       0
Bank Sta=4971.1,5003.1
Exp/Cntr=0.3,0.1

Type RM Length L Ch R = 1,1020,192,192,192
BEGIN DESCRIPTION:
Walnut40 2.7
END DESCRIPTION:
XS GIS Cut Line= 3
      2726270.39      6754121.57      2726411.50      6754166.34
      2726629.46      6754216.94
#Sta/Elev= 30
  4880.5  340.77  4886.4  339.79  4893.4  339.54  4898.6  338.62  4925.7  336.32
  4949.3  332.72  4963.2  331.00  4980.8  327.42  4993.7  326.84  5022.5  327.35
  5027.7  328.33  5033.4  328.69  5053.7  331.21  5064.0  331.96  5070.2  333.19
  5075.3  332.84  5084.5  333.25  5112.8  336.36  5118.0  335.82  5135.8  337.79
  5155.5  339.15  5160.6  338.12  5176.9  339.39  5197.4  339.86  5203.2  340.71
  5208.4  339.89  5217.9  340.77  5238.5  343.79  5245.9  345.37  5252.3  345.06
#Mann=3,-1,0
  4880.5    0.12       0  4980.8    0.04       0  5022.5    0.12       0
Bank Sta=4980.8,5022.5
Exp/Cntr=0.3,0.1

Type RM Length L Ch R = 1,828,56,56,56
BEGIN DESCRIPTION:
Walnut40 2.5
END DESCRIPTION:
XS GIS Cut Line= 3
      2726231.46      6754193.55      2726328.79      6754282.13
      2726428.01      6754359.95
#Sta/Elev= 27
  4884.7  334.99  4893.0  333.59  4900.4  333.43  4907.2  332.30  4914.6  332.49
  4921.3  331.04  4928.8  329.58  4935.5  328.11  4943.0  328.95  4949.7  327.39
  4983.7  326.63  4987.2  326.63  5049.8  327.32  5056.1  327.82  5063.6  328.21
  5070.6  328.93  5076.9  328.95  5085.0  328.80  5091.4  329.37  5099.5  330.23
  5105.8  331.39  5113.9  331.57  5120.3  332.24  5127.1  332.98  5134.7  333.49
  5139.2  334.14  5142.4  334.14
#Mann=3,-1,0
  4884.7    0.05       0  4949.7    0.04       0  5049.8    0.05       0
Bank Sta=4949.7,5049.8
Exp/Cntr=0.3,0.1

Type RM Length L Ch R = 1,772,165,165,165
BEGIN DESCRIPTION:
Walnut40 2.3
END DESCRIPTION:
XS GIS Cut Line= 3
      2726198.44      6754239.34      2726295.71      6754327.86
      2726394.92      6754405.67
#Sta/Elev= 30
  4890.2  333.74  4896.9  332.62  4903.6  332.70  4911.1  331.07  4925.3  330.62
  4932.0  329.59  4939.4  327.19  4946.2  326.61  4953.6  329.06  4961.3  328.28
  4981.5  326.18  4988.8  323.47  4995.5  323.46  5009.7  318.85  5017.1  318.43
  5018.3  317.47  5018.6  316.97  5022.1  316.97  5022.3  317.47  5031.5  318.17
  5038.0  318.99  5052.5  323.22  5066.9  325.66  5073.3  325.85  5102.2  329.14
  5110.3  330.61  5116.7  330.77  5131.1  332.28  5137.5  332.18  5147.8  333.59
#Mann=5,-1,0
  4890.2    0.05       0  4961.3    0.12       0  5018.3    0.07       0
  5022.3    0.12       0  5031.5    0.05       0
Bank Sta=5018.3,5022.3
Exp/Cntr=0.3,0.1

Type RM Length L Ch R = 1,607,121,121,121
BEGIN DESCRIPTION:
Walnut40 2.0
END DESCRIPTION:
XS GIS Cut Line= 3
      2726126.02      6754311.03      2726176.00      6754411.00
      2726226.01      6754511.03
#Sta/Elev= 30
  4888.2  330.87  4891.0  330.87  4902.1  329.57  4910.5  328.82  4918.9  328.26
  4924.5  326.98  4932.9  325.94  4941.3  325.28  4946.9  323.66  4955.2  323.15
  4963.6  321.54  4969.2  320.87  4977.6  319.52  4986.0  317.66  4991.6  317.93
  4995.2  317.66  4995.4  317.16  4998.9  317.16  4999.2  317.66  5008.4  317.69
  5013.9  318.06  5022.3  319.54  5030.7  320.60  5058.7  323.69  5075.4  325.25
  5081.0  326.26  5089.4  327.43  5103.4  328.74  5109.0  329.78  5111.8  329.78
#Mann=3,-1,0
  4888.2    0.12       0  4995.2    0.07       0  4999.2    0.12       0
Bank Sta=4995.2,4999.2
Exp/Cntr=0.3,0.1

Type RM Length L Ch R = 1,486,68,68,68
BEGIN DESCRIPTION:
Walnut40 1.7
END DESCRIPTION:
XS GIS Cut Line= 3
      2726000.88      6754340.48      2726115.71      6754532.19
      2726209.20      6754596.77
#Sta/Elev= 30
  4857.6  327.33  4860.9  327.87  4876.5  326.52  4882.3  326.41  4892.1  325.74
  4897.9  325.98  4913.4  324.43  4919.3  325.00  4934.8  322.86  4940.7  323.27
  4950.4  322.40  4956.2  322.74  4959.0  322.25  4963.1  321.54  4971.8  320.86
  4977.6  318.03  4997.2  317.07  5051.5  317.81  5061.3  318.24  5067.1  318.48
  5072.9  319.28  5077.5  320.71  5084.3  320.71  5087.6  321.99  5130.0  325.83
  5144.4  327.77  5159.3  328.82  5174.2  330.64  5180.2  330.80  5194.7  332.08
#Mann=4,-1,0
  4857.6    0.05       0  4959.0    0.12       0  4977.6    0.04       0
  5061.3    0.12       0
Bank Sta=4977.6,5051.5
Exp/Cntr=0.3,0.1

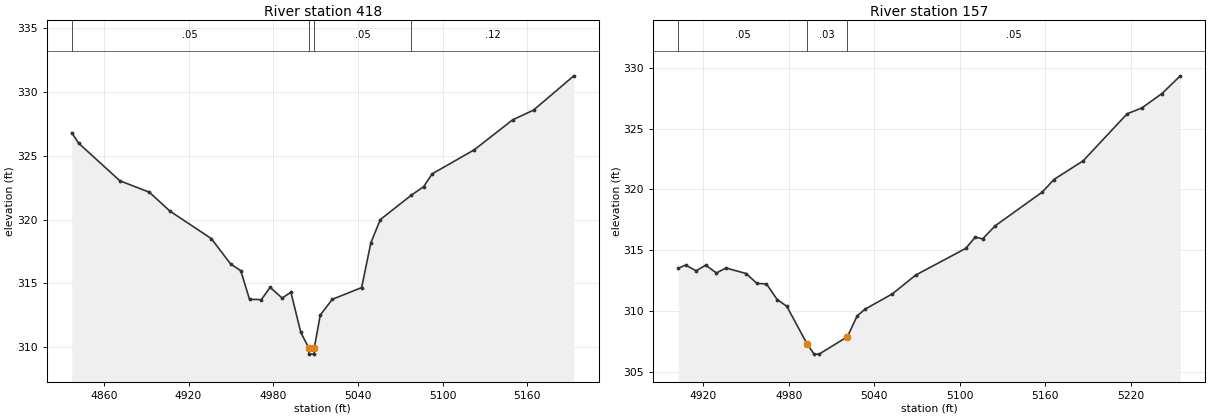
Type RM Length L Ch R = 1,418,261,261,261
BEGIN DESCRIPTION:
Walnut40 1.5
END DESCRIPTION:
XS GIS Cut Line= 3
      2725929.52      6754380.34      2726059.19      6754556.68
      2726172.15      6754633.70
#Sta/Elev= 30
  4837.3  326.81  4842.1  325.99  4871.4  323.04  4892.2  322.15  4906.8  320.67
  4936.1  318.52  4949.8  316.53  4957.0  316.00  4963.2  313.76  4971.6  313.74
  4977.8  314.70  4986.3  313.86  4992.5  314.32  4999.5  311.17  5005.1  309.97
  5005.4  309.47  5008.9  309.47  5009.1  309.97  5013.3  312.53  5021.8  313.76
  5042.6  314.68  5049.1  318.17  5055.8  320.00  5077.7  321.91  5086.5  322.58
  5092.6  323.59  5122.4  325.47  5149.5  327.81  5164.4  328.58  5192.9  331.26
#Mann=4,-1,0
  4837.3    0.05       0  5005.1    0.03       0  5009.1    0.05       0
  5077.7    0.12       0
Bank Sta=5005.1,5009.1
Exp/Cntr=0.3,0.1

Type RM Length L Ch R = 1,157,0,0,0
BEGIN DESCRIPTION:
Walnut40 1.0
END DESCRIPTION:
XS GIS Cut Line= 3
      2725740.26      6754559.25      2725828.43      6754657.80
      2726042.27      6754709.33
#Sta/Elev= 30
  4902.5  313.51  4907.6  313.78  4915.1  313.31  4921.8  313.77  4929.3  313.13
  4936.0  313.54  4950.2  313.08  4957.7  312.27  4964.4  312.23  4971.9  310.94
  4978.6  310.40  4992.8  307.32  4997.8  306.46  5001.3  306.46  5021.2  307.89
  5028.0  309.60  5033.5  310.15  5052.8  311.42  5069.0  312.95  5104.2  315.15
  5110.9  316.08  5116.0  315.93  5124.8  317.00  5158.0  319.79  5166.0  320.81
  5186.5  322.34  5217.4  326.21  5227.7  326.69  5241.8  327.87  5254.7  329.33
#Mann=3,-1,0
  4902.5    0.05       0  4992.8    0.03       0  5021.2    0.05       0
Bank Sta=4992.8,5021.2
Exp/Cntr=0.3,0.1

Chan Stop Cuts=-1