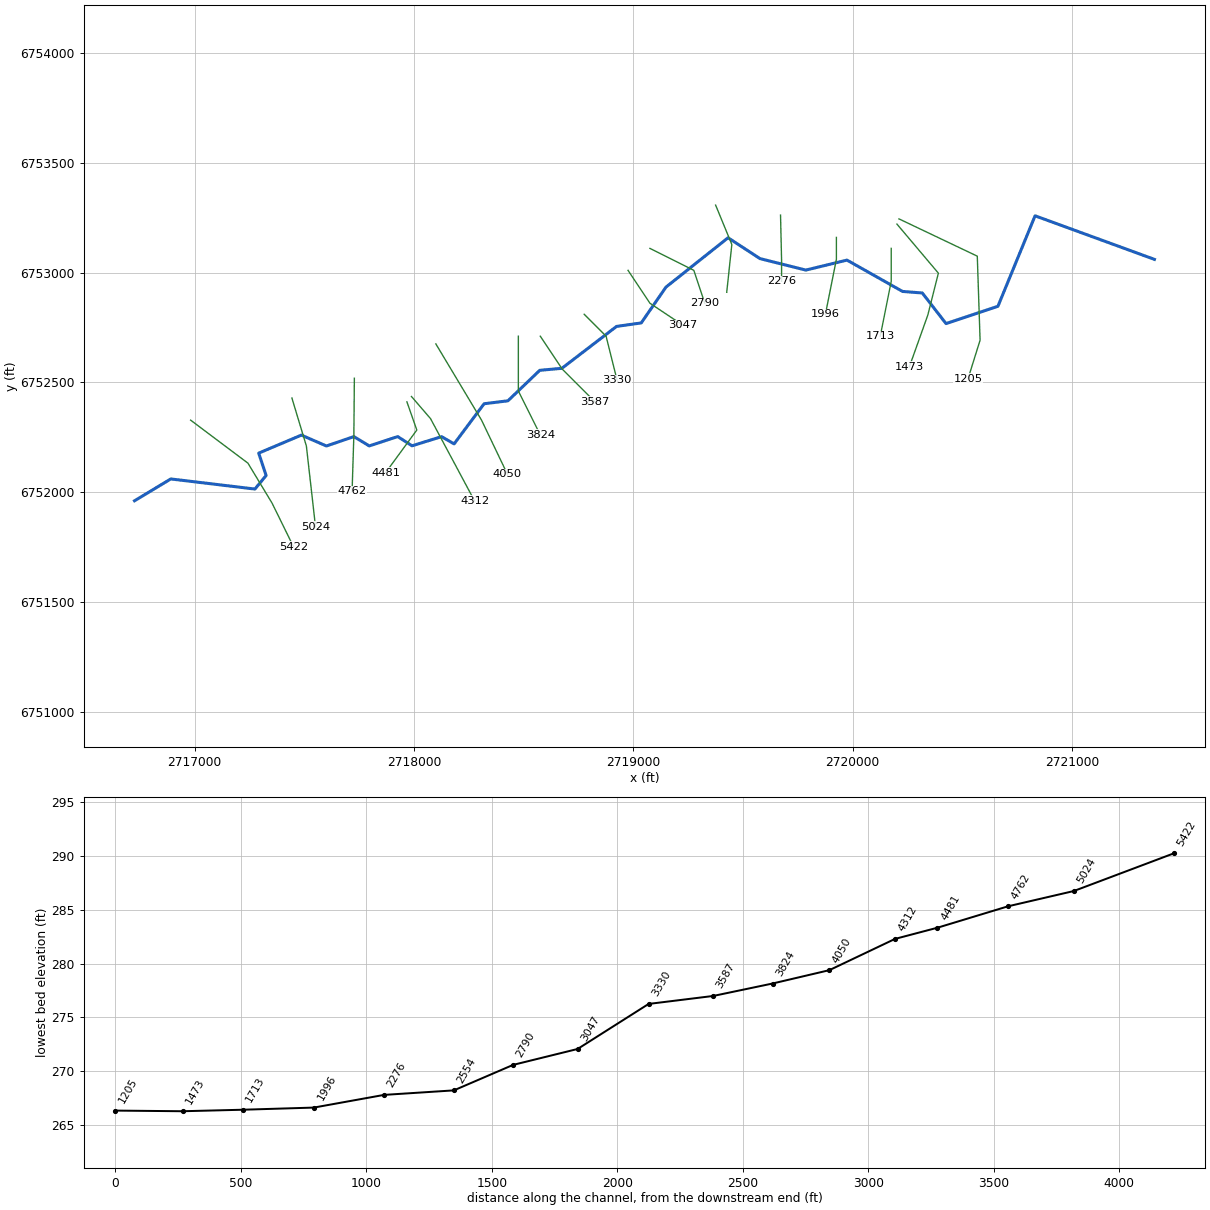
--- Walnut41.prj (project) ---

Proj Title=Walnut41 Base Level Engineering
Current Plan=p01
Default Exp/Contr=0.3,0.1
English Units
Geom File=g01
Flow File=f01
Plan File=p01
BEGIN DESCRIPTION:
Walnut41
END DESCRIPTION:

--- Walnut41.p01 (plan) ---

Plan Title=Multiple Run
Short Identifier=Multiple
Geom File=g01
Flow File=f01
Subcritical Flow
K Sum by GR= 0
Std Step Tol= 0.01
Critical Tol= 0.01
Num of Std Step Trials= 20
Max Error Tol= 0.3
Flow Tol Ratio= 0.001
Split Flow NTrial= 30
Split Flow Tol= 0.02
Split Flow Ratio= 0.02
Log Output Level= 0
Friction Slope Method= 1
Unsteady Friction Slope Method= 2
Unsteady Bridges Friction Slope Method= 1
Parabolic Critical Depth
Global Vel Dist=  1 , 1 , 1
Global Log Level= 0
CheckData=True
Encroach Param= -1, 0, 0, 0
BEGIN DESCRIPTION:
Multiple Run
END DESCRIPTION:

--- Walnut41.f01 (steady flow) ---

Flow Title=Multiple
Number of Profiles=7
Profile Names=10-year,25-year,50-year,1pct_min,100-year,1pct_plu,500-year
River Rch & RM= Walnut41,Reach-1,5422
     146     180     205     116     232     464     299
River Rch & RM= Walnut41,Reach-1,4050
     266     341     399     233     465     928     630
Boundary for River Rch & Prof#=Walnut41,Reach-1,1
Up Type=0
Dn Type=3
Dn Slope=0.005
Boundary for River Rch & Prof#=Walnut41,Reach-1,2
Up Type=0
Dn Type=3
Dn Slope=0.005
Boundary for River Rch & Prof#=Walnut41,Reach-1,3
Up Type=0
Dn Type=3
Dn Slope=0.005
Boundary for River Rch & Prof#=Walnut41,Reach-1,4
Up Type=0
Dn Type=3
Dn Slope=0.005
Boundary for River Rch & Prof#=Walnut41,Reach-1,5
Up Type=0
Dn Type=3
Dn Slope=0.005
Boundary for River Rch & Prof#=Walnut41,Reach-1,6
Up Type=0
Dn Type=3
Dn Slope=0.005
Boundary for River Rch & Prof#=Walnut41,Reach-1,7
Up Type=0
Dn Type=3
Dn Slope=0.005

--- Walnut41.g01 (geometry) ---

Geom Title=Existing Conditions

River Reach=Walnut41,Reach-1
Reach XY= 30
      2716726.00      6751961.00      2716891.21      6752060.51
      2717274.81      6752014.45      2717326.04      6752076.22
      2717292.11      6752178.16      2717486.69      6752260.23
      2717601.00      6752210.62      2717726.00      6752253.43
      2717796.06      6752211.02      2717926.00      6752253.43
      2717991.22      6752211.52      2718126.11      6752253.19
      2718182.95      6752220.18      2718319.81      6752403.14
      2718428.43      6752416.52      2718573.57      6752555.48
      2718674.50      6752564.63      2718923.58      6752755.46
      2719036.10      6752771.39      2719149.12      6752934.73
      2719432.05      6753159.41      2719577.47      6753064.56
      2719786.55      6753012.10      2719974.28      6753057.66
      2720227.66      6752914.86      2720317.66      6752907.83
      2720425.89      6752768.31      2720662.56      6752847.36
      2720831.83      6753259.47      2721376.00      6753061.00

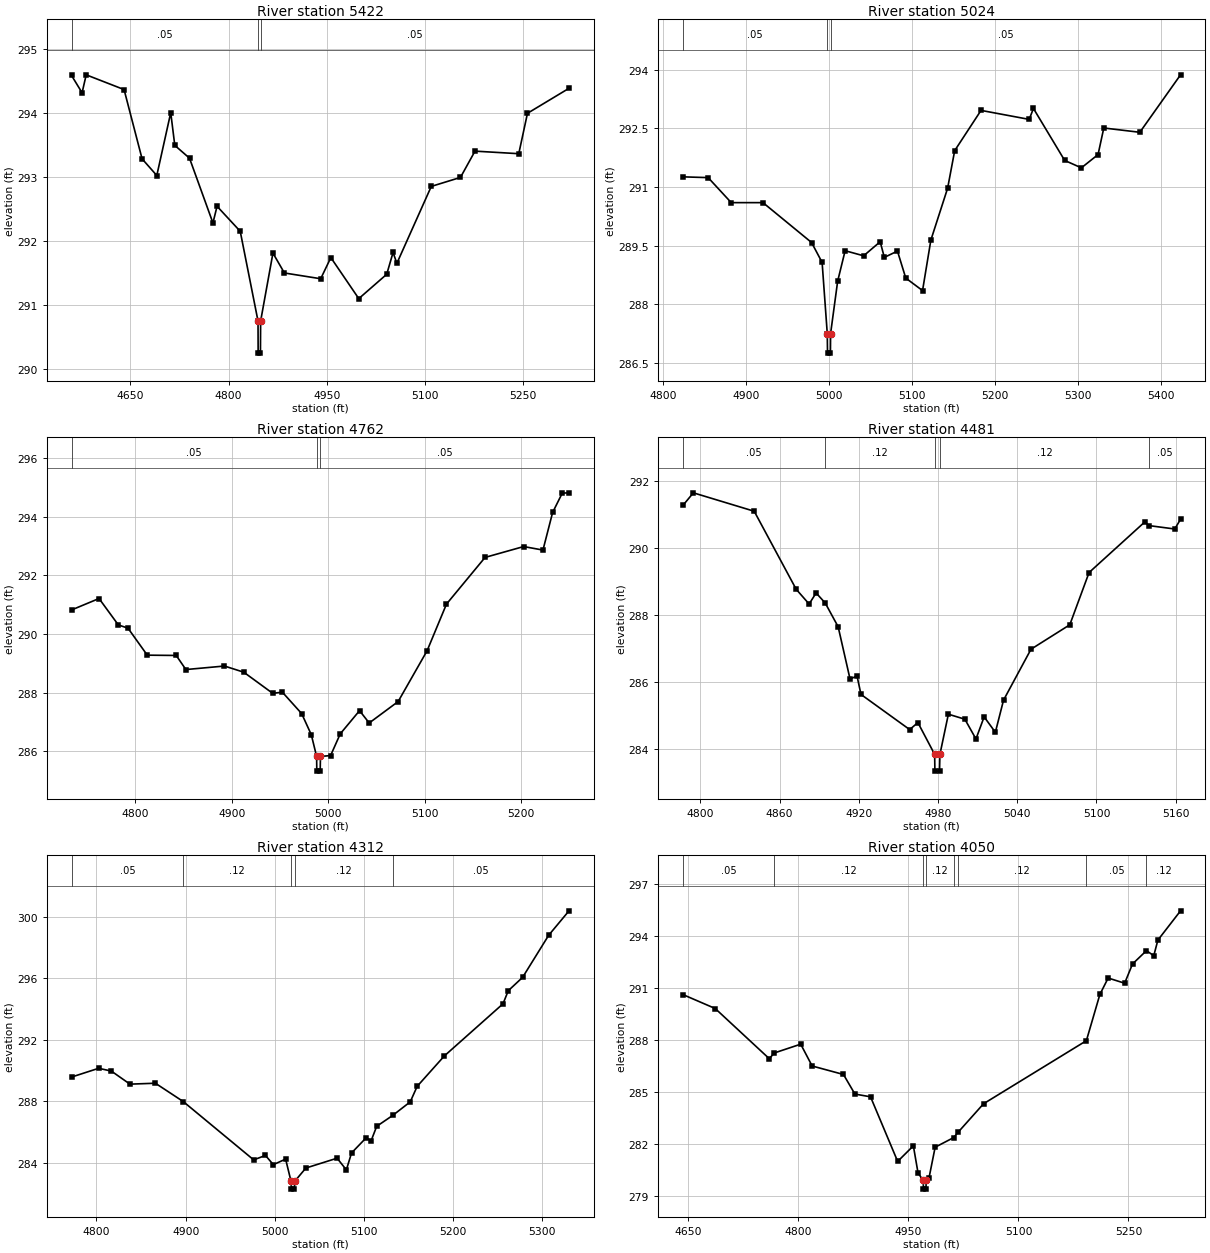
Type RM Length L Ch R = 1,5422,398,398,398
BEGIN DESCRIPTION:
Walnut41 17.0
END DESCRIPTION:
XS GIS Cut Line= 4
      2716981.77      6752328.45      2717242.98      6752132.43
      2717353.27      6751950.00      2717450.51      6751752.06
#Sta/Elev= 30
  4559.9  294.58  4576.0  294.31  4582.3  294.59  4640.2  294.36  4667.7  293.28
  4690.2  293.02  4711.5  294.00  4717.7  293.49  4740.2  293.29  4776.0  292.28
  4782.3  292.54  4817.7  292.15  4844.9  290.75  4845.1  290.25  4848.6  290.25
  4848.9  290.75  4867.7  291.81  4885.2  291.50  4940.7  291.41  4956.2  291.74
  4998.9  291.10  5041.6  291.48  5051.3  291.82  5057.1  291.65  5109.7  292.85
  5154.3  292.99  5176.5  293.40  5243.4  293.36  5256.7  293.99  5320.2  294.38
#Mann=3,-1,0
  4559.9    0.05       0  4844.9    0.04       0  4848.9    0.05       0
Bank Sta=4844.9,4848.9
Exp/Cntr=0.3,0.1

Type RM Length L Ch R = 1,5024,262,262,262
BEGIN DESCRIPTION:
Walnut41 16.5
END DESCRIPTION:
XS GIS Cut Line= 3
      2717443.55      6752429.16      2717509.52      6752210.42
      2717551.19      6751842.34
#Sta/Elev= 30
  4824.5  291.26  4854.7  291.24  4882.5  290.60  4920.7  290.60  4979.2  289.58
  4991.9  289.07  4998.1  287.25  4998.4  286.75  5001.9  286.75  5002.1  287.25
  5010.6  288.59  5019.6  289.37  5041.9  289.24  5061.8  289.60  5066.8  289.20
  5082.6  289.36  5092.6  288.67  5112.8  288.35  5122.8  289.64  5143.0  290.97
  5151.5  291.93  5183.2  292.96  5241.2  292.73  5246.3  293.01  5283.9  291.68
  5304.0  291.49  5324.1  291.83  5331.0  292.51  5374.4  292.40  5423.4  293.87
#Mann=3,-1,0
  4824.5    0.05       0  4998.1    0.04       0  5002.1    0.05       0
Bank Sta=4998.1,5002.1
Exp/Cntr=0.3,0.1

Type RM Length L Ch R = 1,4762,281,281,281
BEGIN DESCRIPTION:
Walnut41 16.0
END DESCRIPTION:
XS GIS Cut Line= 3
      2717728.27      6752519.48      2717726.00      6752261.00
      2717717.91      6752004.02
#Sta/Elev= 30
  4733.9  290.82  4762.4  291.21  4782.4  290.31  4792.4  290.20  4812.4  289.28
  4842.4  289.27  4852.4  288.79  4892.4  288.91  4912.4  288.70  4942.4  287.98
  4952.4  288.02  4972.4  287.29  4982.4  286.57  4987.9  285.83  4988.1  285.33
  4991.6  285.33  4991.9  285.83  5002.4  285.86  5012.4  286.60  5032.4  287.39
  5042.4  286.97  5072.4  287.70  5102.4  289.43  5122.5  291.02  5162.5  292.61
  5202.5  292.98  5222.5  292.86  5232.5  294.14  5242.5  294.80  5249.5  294.81
#Mann=3,-1,0
  4733.9    0.05       0  4987.9    0.04       0  4991.9    0.05       0
Bank Sta=4987.9,4991.9
Exp/Cntr=0.3,0.1

Type RM Length L Ch R = 1,4481,169,169,169
BEGIN DESCRIPTION:
Walnut41 15.5
END DESCRIPTION:
XS GIS Cut Line= 3
      2717967.85      6752411.82      2718012.99      6752283.33
      2717870.79      6752089.11
#Sta/Elev= 30
  4786.8  291.28  4794.6  291.65  4840.7  291.10  4872.5  288.77  4882.3  288.33
  4887.6  288.66  4894.5  288.36  4904.3  287.65  4913.3  286.09  4918.6  286.18
  4921.6  285.63  4958.5  284.58  4964.7  284.79  4977.4  283.84  4977.6  283.34
  4981.1  283.34  4981.4  283.84  4987.8  285.04  5000.3  284.89  5008.7  284.30
  5014.9  284.96  5023.4  284.50  5029.6  285.46  5050.4  286.98  5079.8  287.71
  5094.4  289.27  5136.6  290.78  5140.0  290.67  5159.3  290.57  5163.7  290.86
#Mann=5,-1,0
  4786.8    0.05       0  4894.5    0.12       0  4977.4    0.07       0
  4981.4    0.12       0  5140.0    0.05       0
Bank Sta=4977.4,4981.4
Exp/Cntr=0.3,0.1

Type RM Length L Ch R = 1,4312,262,262,262
BEGIN DESCRIPTION:
Walnut41 15.0
END DESCRIPTION:
XS GIS Cut Line= 3
      2717988.69      6752436.10      2718075.49      6752335.42
      2718276.02      6751960.97
#Sta/Elev= 30
  4772.1  289.58  4802.5  290.15  4816.7  289.97  4837.6  289.12  4866.1  289.18
  4897.3  287.99  4976.3  284.20  4989.5  284.49  4998.3  283.89  5012.1  284.25
  5018.2  282.80  5018.5  282.30  5022.0  282.30  5022.2  282.80  5034.8  283.67
  5069.8  284.31  5080.2  283.55  5086.0  284.65  5102.3  285.63  5108.0  285.45
  5114.2  286.38  5132.2  287.09  5151.8  287.97  5159.6  288.98  5190.0  290.95
  5255.8  294.34  5261.7  295.19  5277.8  296.06  5307.1  298.80  5329.8  300.38
#Mann=5,-1,0
  4772.1    0.05       0  4897.3    0.12       0  5018.2    0.07       0
  5022.2    0.12       0  5132.2    0.05       0
Bank Sta=5018.2,5022.2
Exp/Cntr=0.3,0.1

Type RM Length L Ch R = 1,4050,226,226,226
BEGIN DESCRIPTION:
Walnut41 14.0
END DESCRIPTION:
XS GIS Cut Line= 3
      2718099.78      6752675.72      2718308.13      6752328.47
      2718426.19      6752081.94
#Sta/Elev= 30
  4642.7  290.62  4686.5  289.82  4760.3  286.92  4766.9  287.25  4803.1  287.76
  4818.7  286.50  4861.4  286.01  4877.0  284.88  4898.3  284.72  4935.3  280.99
  4956.7  281.89  4963.1  280.32  4970.2  279.89  4970.4  279.39  4973.9  279.39
  4974.2  279.89  4978.0  280.03  4986.4  281.81  5011.8  282.37  5017.4  282.66
  5052.4  284.32  5192.6  287.96  5211.0  290.63  5222.3  291.58  5244.8  291.28
  5255.5  292.39  5274.5  293.16  5284.5  292.87  5290.1  293.77  5321.0  295.46
#Mann=8,-1,0
  4642.7    0.05       0  4766.9    0.12       0  4970.2    0.07       0
  4974.2    0.12       0  5011.8     0.1       0  5017.4    0.12       0
  5192.6    0.05       0  5274.5    0.12       0
Bank Sta=4970.2,4974.2
Exp/Cntr=0.3,0.1

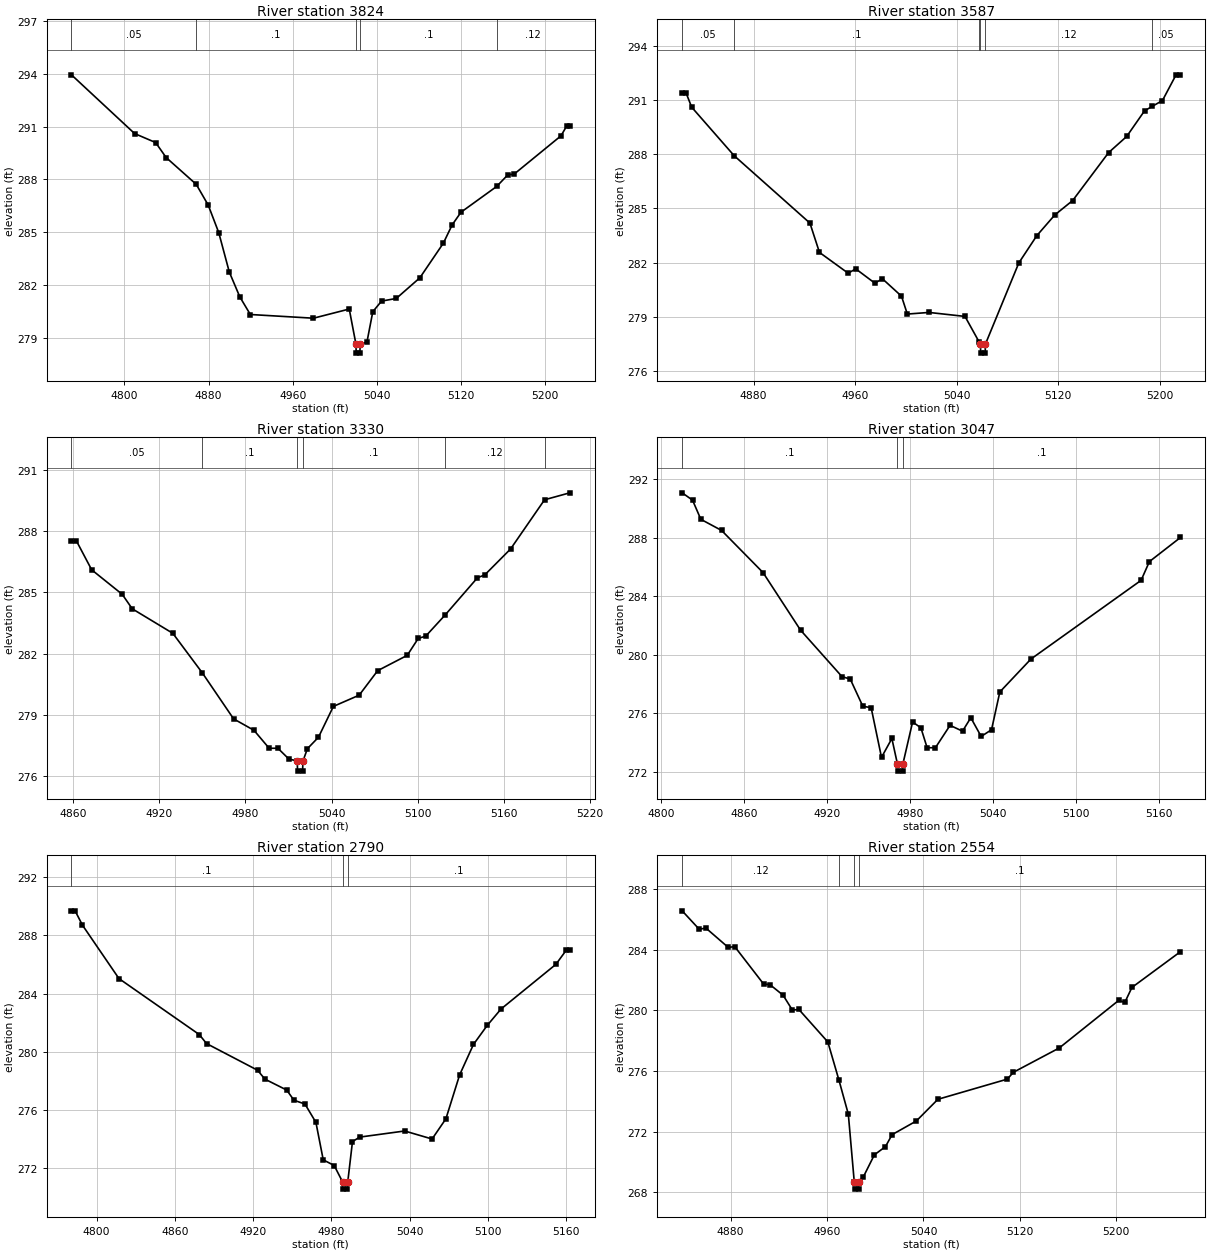
Type RM Length L Ch R = 1,3824,237,237,237
BEGIN DESCRIPTION:
Walnut41 13.0
END DESCRIPTION:
XS GIS Cut Line= 3
      2718476.00      6752711.02      2718476.00      6752461.00
      2718575.99      6752261.03
#Sta/Elev= 30
  4749.7  293.93  4809.7  290.60  4829.7  290.09  4839.7  289.24  4868.3  287.72
  4879.7  286.54  4889.7  284.98  4899.7  282.75  4909.7  281.34  4919.7  280.34
  4979.7  280.13  5013.7  280.65  5020.1  278.65  5020.3  278.15  5023.8  278.15
  5024.1  278.65  5030.5  278.77  5036.1  280.50  5044.4  281.10  5058.4  281.25
  5080.8  282.42  5103.1  284.38  5111.5  285.42  5119.9  286.14  5153.8  287.60
  5164.6  288.27  5170.2  288.29  5214.9  290.47  5220.5  291.04  5223.3  291.04
#Mann=5,-1,0
  4749.7    0.05       0  4868.3     0.1       0  5020.1    0.07       0
  5024.1     0.1       0  5153.8    0.12       0
Bank Sta=5020.1,5024.1
Exp/Cntr=0.3,0.1

Type RM Length L Ch R = 1,3587,257,257,257
BEGIN DESCRIPTION:
Walnut41 12.0
END DESCRIPTION:
XS GIS Cut Line= 3
      2718576.01      6752710.98      2718676.00      6752561.00
      2718826.01      6752410.99
#Sta/Elev= 30
  4823.8  291.39  4826.8  291.39  4831.3  290.59  4864.7  287.91  4924.4  284.18
  4931.9  282.56  4954.5  281.41  4960.5  281.65  4975.5  280.86  4981.5  281.10
  4996.5  280.14  5001.1  279.15  5018.2  279.24  5046.5  279.02  5057.7  277.60
  5058.6  277.49  5058.9  276.99  5062.4  276.99  5062.6  277.49  5088.9  281.98
  5103.1  283.49  5117.2  284.63  5131.3  285.43  5159.6  288.08  5173.8  288.97
  5187.9  290.39  5193.8  290.63  5202.0  290.96  5212.7  292.38  5216.2  292.38
#Mann=6,-1,0
  4823.8    0.05       0  4864.7     0.1       0  5057.7    0.12       0
  5058.6    0.07       0  5062.6    0.12       0  5193.8    0.05       0
Bank Sta=5058.6,5062.6
Exp/Cntr=0.3,0.1

Type RM Length L Ch R = 1,3330,283,283,283
BEGIN DESCRIPTION:
Walnut41 11.0
END DESCRIPTION:
XS GIS Cut Line= 3
      2718776.00      6752811.00      2718876.00      6752711.00
      2718926.00      6752510.98
#Sta/Elev= 30
  4858.6  287.52  4862.1  287.52  4872.7  286.11  4894.0  284.91  4901.0  284.20
  4929.3  283.00  4950.0  281.05  4971.7  278.81  4985.9  278.25  4996.5  277.37
  5002.6  277.37  5010.3  276.84  5016.1  276.75  5016.3  276.25  5019.8  276.25
  5020.1  276.75  5023.2  277.35  5030.9  277.91  5041.3  279.42  5059.3  279.97
  5072.2  281.17  5092.8  281.92  5100.5  282.75  5105.7  282.86  5119.3  283.90
  5141.8  285.72  5146.9  285.86  5164.9  287.13  5188.6  289.54  5206.2  289.88
#Mann=6,-1,0
  4858.6    0.05       0  4950.0     0.1       0  5016.1    0.07       0
  5020.1     0.1       0  5119.3    0.12       0  5188.6    0.05       0
Bank Sta=5016.1,5020.1
Exp/Cntr=0.3,0.1

Type RM Length L Ch R = 1,3047,257,257,257
BEGIN DESCRIPTION:
Walnut41 10.0
END DESCRIPTION:
XS GIS Cut Line= 3
      2718976.03      6753010.96      2719076.00      6752861.00
      2719225.99      6752761.00
#Sta/Elev= 30
  4815.3  291.08  4822.8  290.58  4828.8  289.27  4843.8  288.51  4873.8  285.63
  4900.9  281.70  4930.9  278.52  4936.9  278.35  4946.0  276.49  4952.0  276.40
  4959.5  273.00  4967.0  274.29  4971.0  272.56  4971.2  272.06  4974.7  272.06
  4975.0  272.56  4982.0  275.42  4988.0  275.02  4992.5  273.66  4998.5  273.66
  5009.1  275.19  5018.1  274.79  5024.1  275.71  5031.6  274.43  5039.1  274.89
  5045.1  277.47  5067.6  279.72  5147.3  285.10  5153.3  286.38  5175.8  288.03
#Mann=3,-1,0
  4815.3     0.1       0  4971.0    0.07       0  4975.0     0.1       0
Bank Sta=4971,4975
Exp/Cntr=0.3,0.1

Type RM Length L Ch R = 1,2790,236,236,236
BEGIN DESCRIPTION:
Walnut41 9.0
END DESCRIPTION:
XS GIS Cut Line= 3
      2719075.97      6753111.02      2719276.00      6753011.00
      2719326.01      6752860.96
#Sta/Elev= 30
  4780.8  289.68  4783.6  289.68  4789.2  288.70  4817.2  285.03  4878.7  281.19
  4884.3  280.57  4923.4  278.74  4929.0  278.13  4945.7  277.38  4951.3  276.68
  4959.7  276.42  4968.1  275.16  4973.7  272.59  4982.1  272.20  4988.5  271.08
  4988.7  270.58  4992.2  270.58  4992.5  271.08  4996.1  273.84  5001.6  274.15
  5036.1  274.57  5057.1  274.02  5067.7  275.41  5078.2  278.42  5088.8  280.51
  5099.3  281.81  5109.9  282.94  5152.0  286.01  5159.9  286.98  5162.6  286.98
#Mann=3,-1,0
  4780.8     0.1       0  4988.5    0.07       0  4992.5     0.1       0
Bank Sta=4988.5,4992.5
Exp/Cntr=0.3,0.1

Type RM Length L Ch R = 1,2554,278,278,278
BEGIN DESCRIPTION:
Walnut41 8.0
END DESCRIPTION:
XS GIS Cut Line= 3
      2719375.26      6753308.38      2719449.26      6753128.88
      2719426.00      6752910.97
#Sta/Elev= 30
  4839.9  286.55  4854.1  285.33  4859.5  285.42  4878.1  284.14  4883.5  284.19
  4907.4  281.73  4912.8  281.68  4923.6  280.99  4931.3  280.01  4936.7  280.05
  4960.7  277.91  4969.9  275.40  4977.7  273.15  4982.6  268.71  4982.9  268.21
  4986.4  268.21  4986.6  268.71  4990.0  268.99  4999.3  270.47  5008.5  271.01
  5014.0  271.80  5034.1  272.70  5052.0  274.13  5109.6  275.46  5114.6  275.91
  5152.6  277.51  5202.0  280.65  5207.0  280.51  5212.9  281.50  5253.2  283.86
#Mann=4,-1,0
  4839.9    0.12       0  4969.9     0.1       0  4982.6    0.07       0
  4986.6     0.1       0
Bank Sta=4982.6,4986.6
Exp/Cntr=0.3,0.1

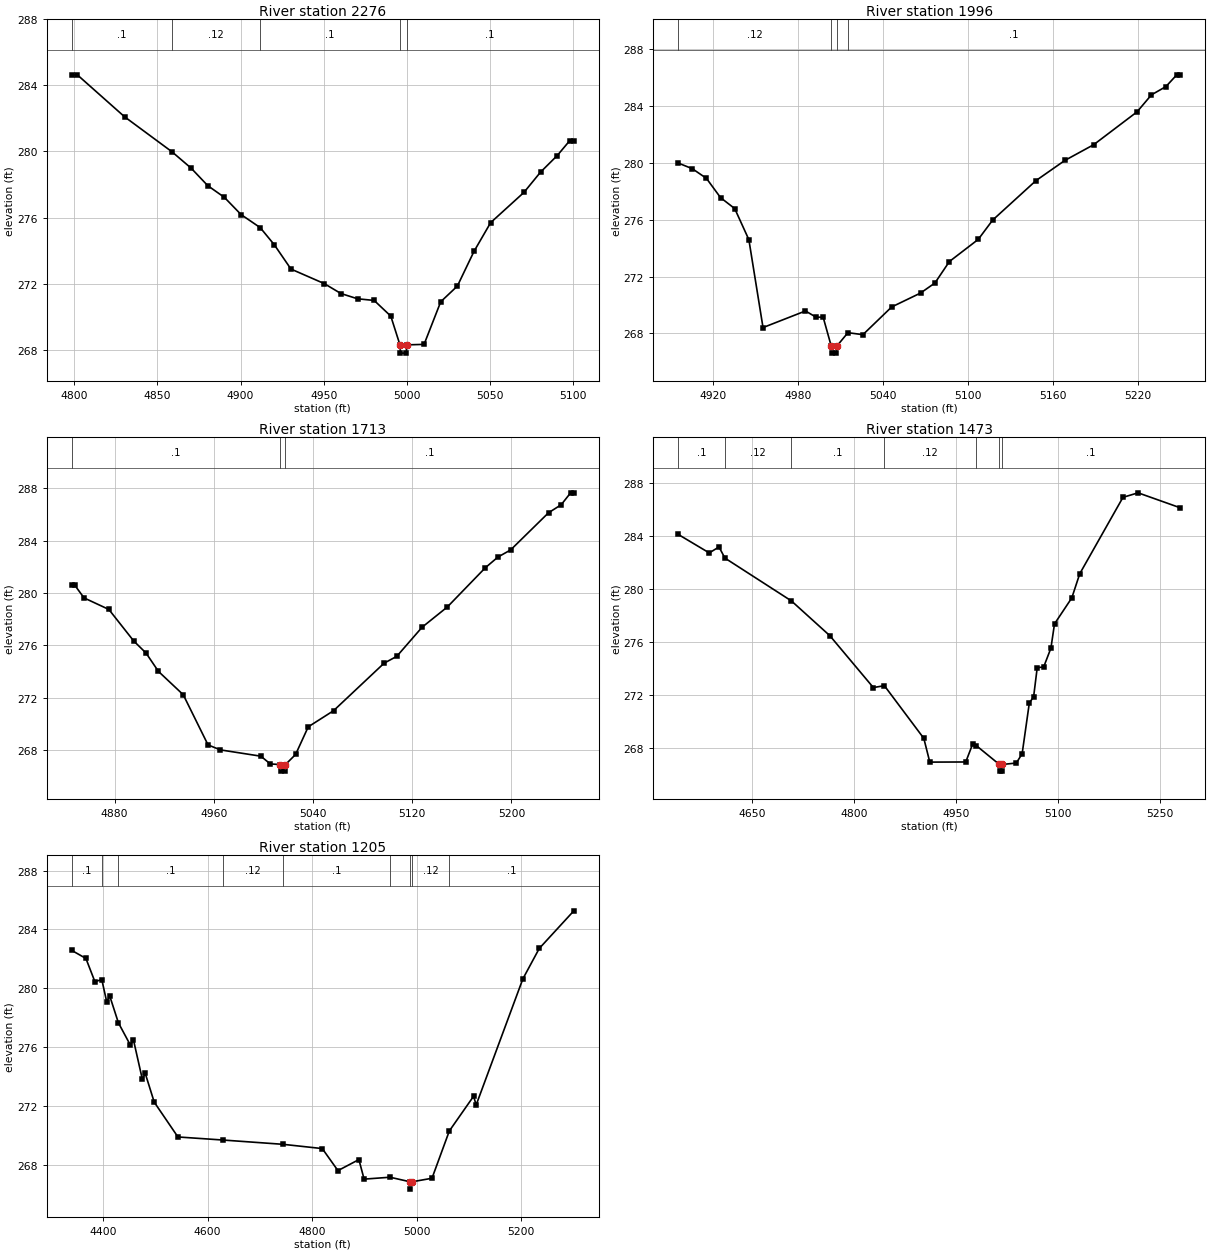
Type RM Length L Ch R = 1,2276,280,280,280
BEGIN DESCRIPTION:
Walnut41 7.0
END DESCRIPTION:
XS GIS Cut Line= 3
      2719671.31      6753262.77      2719676.00      6753061.00
      2719676.00      6752961.03
#Sta/Elev= 30
  4798.5  284.64  4801.9  284.64  4830.3  282.10  4858.8  279.98  4870.3  278.99
  4880.3  277.93  4890.3  277.22  4900.3  276.18  4911.8  275.39  4920.3  274.35
  4930.3  272.88  4950.3  272.00  4960.3  271.40  4970.3  271.08  4980.3  270.98
  4990.3  270.03  4995.8  268.29  4996.1  267.79  4999.6  267.79  4999.8  268.29
  5010.3  268.32  5020.3  270.90  5030.3  271.85  5040.3  273.95  5050.3  275.69
  5070.3  277.52  5080.3  278.75  5090.3  279.75  5097.8  280.65  5100.3  280.65
#Mann=5,-1,0
  4798.5     0.1       0  4858.8    0.12       0  4911.8     0.1       0
  4995.8    0.07       0  4999.8     0.1       0
Bank Sta=4995.8,4999.8
Exp/Cntr=0.3,0.1

Type RM Length L Ch R = 1,1996,283,283,283
BEGIN DESCRIPTION:
Walnut41 6.0
END DESCRIPTION:
XS GIS Cut Line= 3
      2719926.00      6753160.96      2719926.00      6753061.00
      2719876.00      6752811.01
#Sta/Elev= 30
  4895.2  280.00  4905.2  279.60  4915.2  278.92  4925.2  277.56  4935.2  276.79
  4945.2  274.60  4955.2  268.41  4985.2  269.58  4992.7  269.14  4997.7  269.14
  5003.4  267.11  5003.6  266.61  5007.1  266.61  5007.4  267.11  5015.2  268.05
  5025.8  267.91  5046.1  269.86  5066.5  270.84  5076.7  271.55  5086.9  273.06
  5107.3  274.62  5117.5  275.98  5148.1  278.76  5168.5  280.18  5188.9  281.29
  5219.5  283.60  5229.7  284.80  5239.9  285.38  5247.6  286.21  5250.1  286.21
#Mann=4,-1,0
  4895.2    0.12       0  5003.4    0.07       0  5007.4    0.12       0
  5015.2     0.1       0
Bank Sta=5003.4,5007.4
Exp/Cntr=0.3,0.1

Type RM Length L Ch R = 1,1713,240,240,240
BEGIN DESCRIPTION:
Walnut41 5.0
END DESCRIPTION:
XS GIS Cut Line= 3
      2720176.00      6753111.02      2720176.00      6752961.00
      2720125.99      6752710.97
#Sta/Elev= 30
  4845.3  280.60  4847.8  280.60  4855.3  279.63  4875.3  278.75  4895.3  276.35
  4905.3  275.42  4915.3  274.02  4935.3  272.24  4955.3  268.41  4965.3  268.03
  4997.9  267.55  5005.5  266.96  5013.7  266.91  5014.0  266.41  5017.5  266.41
  5017.7  266.91  5025.9  267.68  5036.1  269.79  5056.5  271.02  5097.3  274.65
  5107.5  275.17  5127.9  277.39  5148.3  278.94  5178.9  281.93  5189.1  282.75
  5199.3  283.29  5229.9  286.13  5240.1  286.74  5247.7  287.65  5250.3  287.65
#Mann=3,-1,0
  4845.3     0.1       0  5013.7    0.07       0  5017.7     0.1       0
Bank Sta=5013.7,5017.7
Exp/Cntr=0.3,0.1

Type RM Length L Ch R = 1,1473,268,268,268
BEGIN DESCRIPTION:
Walnut41 4.5
END DESCRIPTION:
XS GIS Cut Line= 4
      2720202.00      6753221.81      2720390.98      6752998.17
      2720342.96      6752807.63      2720258.70      6752571.40
#Sta/Elev= 30
  4540.4  284.12  4586.3  282.72  4600.6  283.17  4609.4  282.33  4707.4  279.10
  4764.0  276.48  4828.1  272.57  4844.4  272.71  4902.5  268.74  4911.3  266.95
  4964.3  266.96  4974.7  268.34  4979.7  268.20  5013.9  266.77  5014.2  266.27
  5017.7  266.27  5017.9  266.77  5038.8  266.88  5047.4  267.58  5058.0  271.41
  5064.3  271.87  5069.6  274.06  5079.2  274.13  5089.8  275.54  5095.1  277.37
  5120.6  279.33  5132.3  281.15  5196.0  286.91  5218.3  287.25  5280.5  286.12
#Mann=7,-1,0
  4540.4     0.1       0  4609.4    0.12       0  4707.4     0.1       0
  4844.4    0.12       0  4979.7     0.1       0  5013.9    0.07       0
  5017.9     0.1       0
Bank Sta=5013.9,5017.9
Exp/Cntr=0.3,0.1

Type RM Length L Ch R = 1,1205,0,0,0
BEGIN DESCRIPTION:
Walnut41 4.0
END DESCRIPTION:
XS GIS Cut Line= 4
      2720211.44      6753245.42      2720568.38      6753075.58
      2720581.14      6752692.80      2720526.41      6752517.84
#Sta/Elev= 30
  4339.6  282.58  4366.9  282.03  4384.1  280.45  4397.3  280.59  4406.8  279.07
  4412.4  279.49  4429.1  277.65  4452.2  276.12  4457.8  276.51  4475.0  273.80
  4480.5  274.21  4497.7  272.25  4543.1  269.88  4629.8  269.67  4744.2  269.38
  4819.5  269.09  4849.5  267.59  4889.6  268.34  4899.6  267.01  4949.2  267.14
  4987.6  266.83  4987.9  266.33  4991.6  266.83  5029.6  267.07  5062.8  270.29
  5109.2  272.65  5114.2  272.06  5203.6  280.64  5235.0  282.71  5301.2  285.27
#Mann=9,-1,0
  4339.6     0.1       0  4397.3    0.12       0  4429.1     0.1       0
  4629.8    0.12       0  4744.2     0.1       0  4949.2    0.12       0
  4987.6    0.07       0  4991.6    0.12       0  5062.8     0.1       0
Bank Sta=4987.6,4991.6
Exp/Cntr=0.3,0.1

Chan Stop Cuts=-1