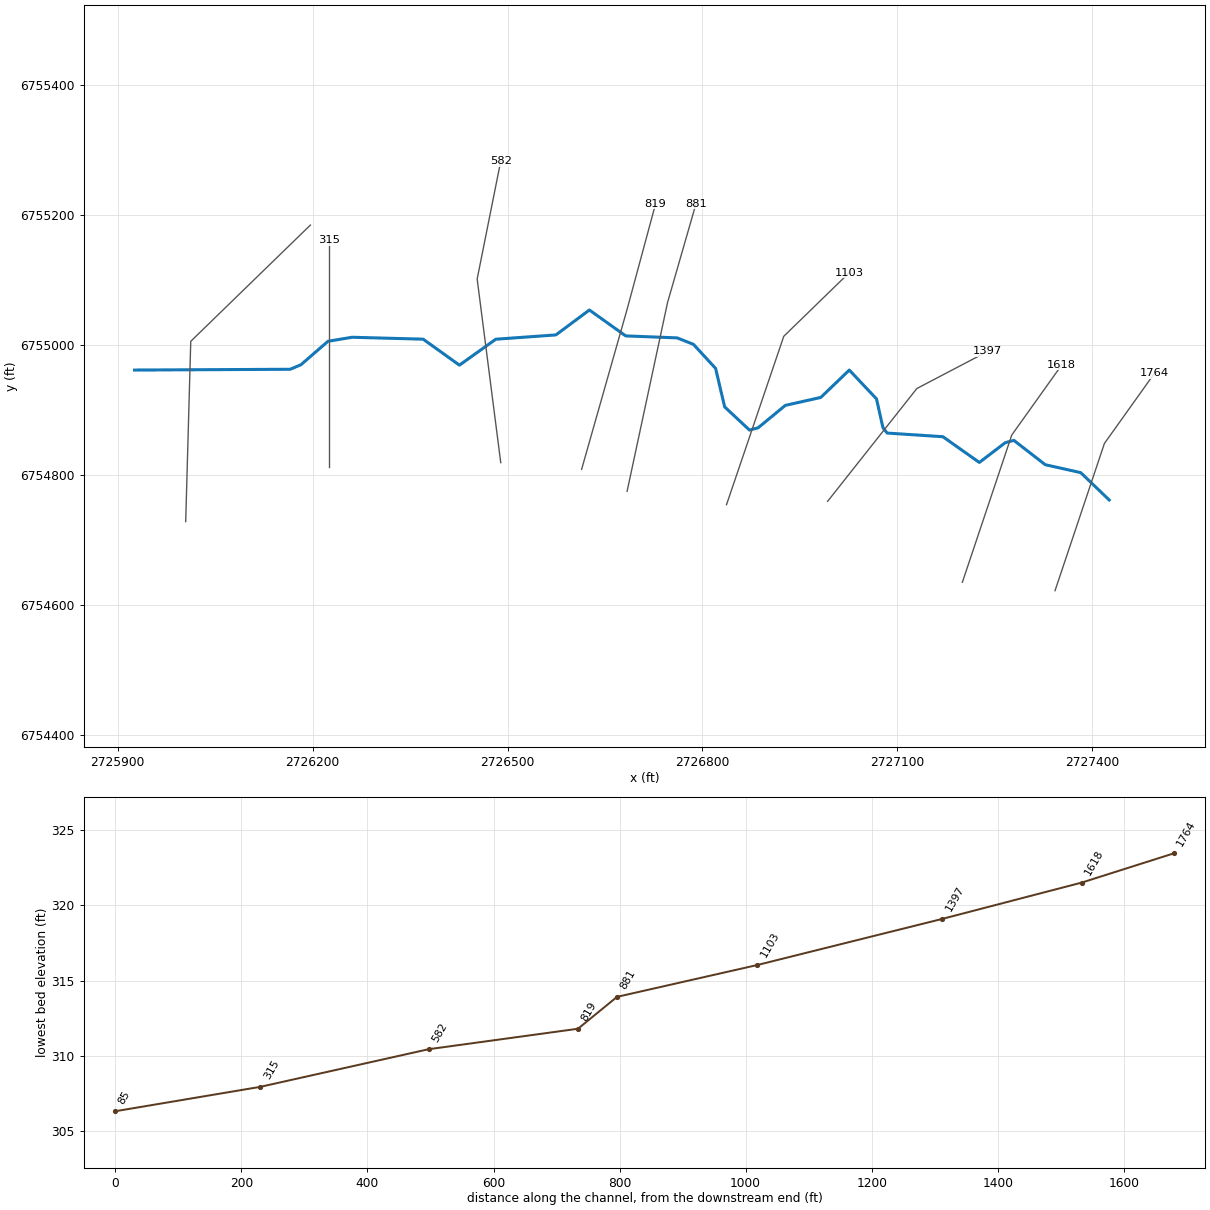
--- Walnut42.prj (project) ---

Proj Title=Walnut42 Base Level Engineering
Current Plan=p01
Default Exp/Contr=0.3,0.1
English Units
Geom File=g01
Flow File=f01
Plan File=p01
BEGIN DESCRIPTION:
Walnut42
END DESCRIPTION:

--- Walnut42.p01 (plan) ---

Plan Title=Multiple Run
Short Identifier=Multiple
Geom File=g01
Flow File=f01
Subcritical Flow
K Sum by GR= 0
Std Step Tol= 0.01
Critical Tol= 0.01
Num of Std Step Trials= 20
Max Error Tol= 0.3
Flow Tol Ratio= 0.001
Split Flow NTrial= 30
Split Flow Tol= 0.02
Split Flow Ratio= 0.02
Log Output Level= 0
Friction Slope Method= 1
Unsteady Friction Slope Method= 2
Unsteady Bridges Friction Slope Method= 1
Parabolic Critical Depth
Global Vel Dist=  1 , 1 , 1
Global Log Level= 0
CheckData=True
Encroach Param= -1, 0, 0, 0
BEGIN DESCRIPTION:
Multiple Run
END DESCRIPTION:

--- Walnut42.f01 (steady flow) ---

Flow Title=Multiple
Number of Profiles=7
Profile Names=10-year,25-year,50-year,1pct_min,100-year,1pct_plu,500-year
River Rch & RM= Walnut42,Reach-1,1764
     141     174     199     114     228     455     296
River Rch & RM= Walnut42,Reach-1,1103
     173     216     248     142     284     566     371
Boundary for River Rch & Prof#=Walnut42,Reach-1,1
Up Type=0
Dn Type=3
Dn Slope=0.005
Boundary for River Rch & Prof#=Walnut42,Reach-1,2
Up Type=0
Dn Type=3
Dn Slope=0.005
Boundary for River Rch & Prof#=Walnut42,Reach-1,3
Up Type=0
Dn Type=3
Dn Slope=0.005
Boundary for River Rch & Prof#=Walnut42,Reach-1,4
Up Type=0
Dn Type=3
Dn Slope=0.005
Boundary for River Rch & Prof#=Walnut42,Reach-1,5
Up Type=0
Dn Type=3
Dn Slope=0.005
Boundary for River Rch & Prof#=Walnut42,Reach-1,6
Up Type=0
Dn Type=3
Dn Slope=0.005
Boundary for River Rch & Prof#=Walnut42,Reach-1,7
Up Type=0
Dn Type=3
Dn Slope=0.005

--- Walnut42.g01 (geometry) ---

Geom Title=Existing Conditions

River Reach=Walnut42,Reach-1
Reach XY= 30
      2727426.00      6754761.00      2727382.14      6754803.12
      2727327.58      6754815.32      2727279.23      6754852.78
      2727265.96      6754849.19      2727226.09      6754818.79
      2727170.02      6754858.42      2727084.18      6754864.04
      2727077.72      6754872.51      2727067.85      6754916.64
      2727026.00      6754961.00      2726982.14      6754918.88
      2726927.57      6754906.65      2726885.74      6754872.19
      2726872.34      6754868.65      2726834.16      6754904.33
      2726820.26      6754963.52      2726786.10      6755000.61
      2726760.91      6755010.54      2726681.90      6755013.56
      2726626.00      6755053.44      2726574.50      6755015.09
      2726481.90      6755008.45      2726426.00      6754968.56
      2726370.14      6755008.55      2726260.84      6755011.47
      2726223.67      6755005.26      2726182.06      6754969.14
      2726165.50      6754962.22      2725926.00      6754961.00

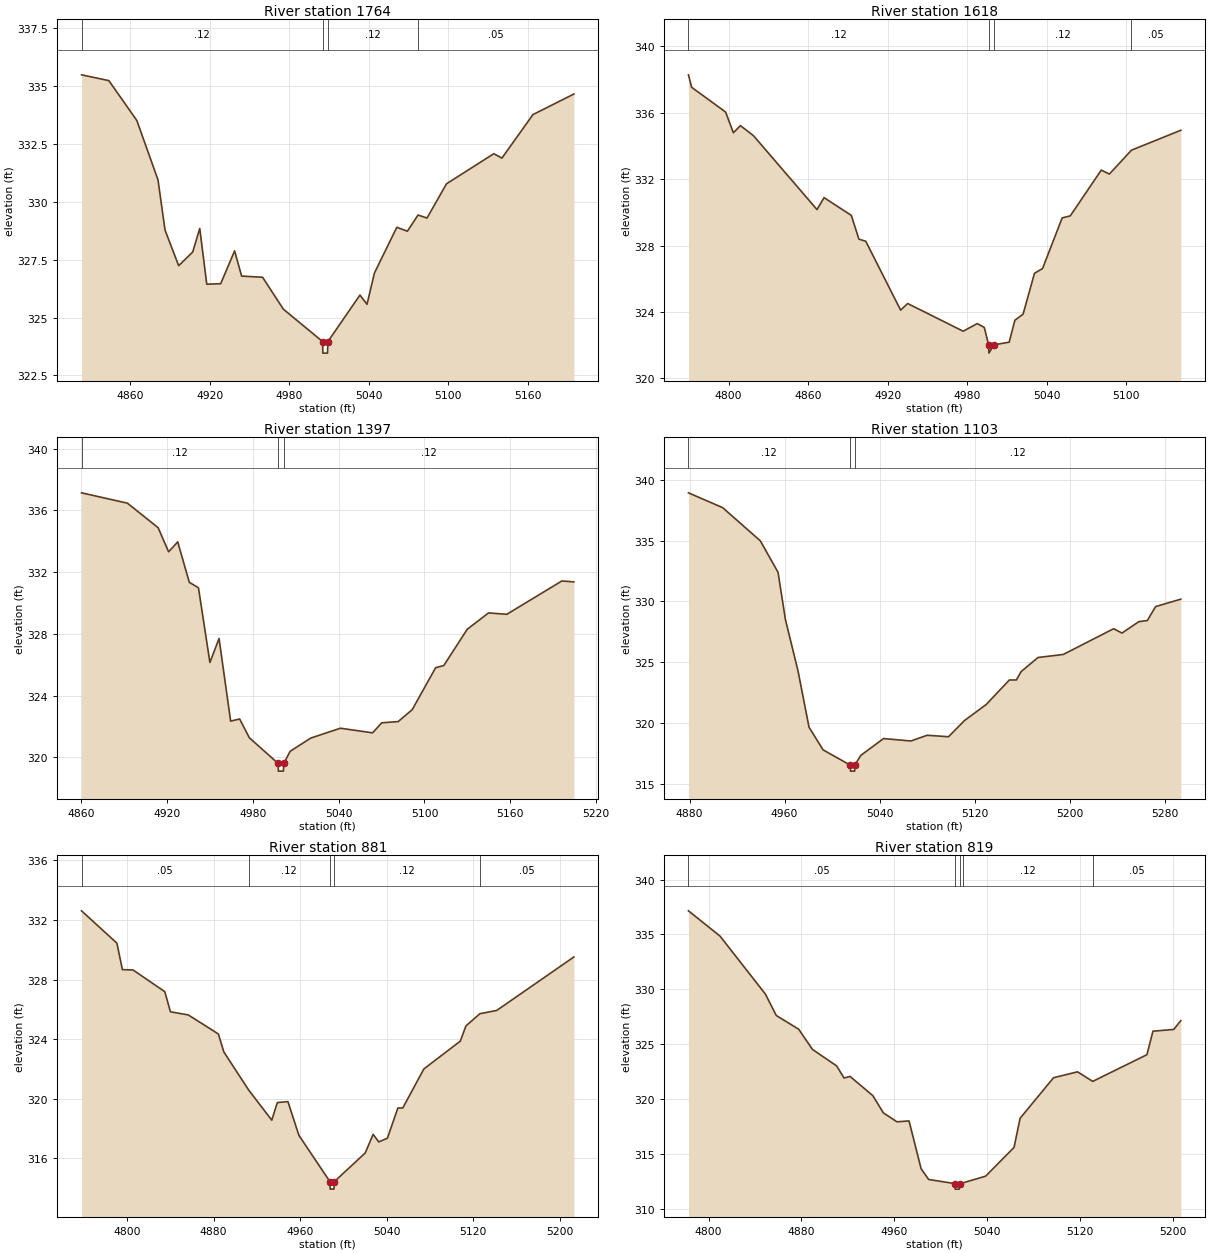
Type RM Length L Ch R = 1,1764,146,146,146
BEGIN DESCRIPTION:
Walnut42 7.0
END DESCRIPTION:
XS GIS Cut Line= 3
      2727342.60      6754621.47      2727418.60      6754848.04
      2727495.56      6754955.94
#Sta/Elev= 30
  4823.3  335.49  4843.9  335.24  4865.0  333.52  4881.0  330.95  4886.3  328.78
  4896.6  327.24  4907.2  327.83  4912.5  328.85  4917.8  326.44  4928.3  326.46
  4938.8  327.88  4944.1  326.79  4959.9  326.74  4975.6  325.36  5005.2  323.96
  5005.4  323.46  5008.9  323.46  5009.2  323.96  5033.4  325.97  5038.7  325.57
  5044.3  326.92  5061.2  328.90  5069.2  328.73  5077.2  329.43  5084.0  329.30
  5098.7  330.78  5134.4  332.08  5140.5  331.89  5163.9  333.77  5194.8  334.66
#Mann=4,-1,0
  4823.3    0.12       0  5005.2    0.07       0  5009.2    0.12       0
  5077.2    0.05       0
Bank Sta=5005.2,5009.2
Exp/Cntr=0.3,0.1

Type RM Length L Ch R = 1,1618,221,221,221
BEGIN DESCRIPTION:
Walnut42 6.0
END DESCRIPTION:
XS GIS Cut Line= 3
      2727200.00      6754634.45      2727276.00      6754861.00
      2727352.96      6754968.91
#Sta/Elev= 30
  4769.7  338.29  4772.1  337.54  4797.7  336.05  4803.6  334.80  4808.9  335.23
  4818.8  334.62  4866.7  330.17  4872.0  330.89  4892.6  329.82  4898.3  328.39
  4903.5  328.26  4929.8  324.11  4935.1  324.51  4977.0  322.84  4987.6  323.30
  4992.9  323.07  4996.2  322.02  4996.4  321.52  5000.2  322.02  5011.7  322.18
  5016.0  323.50  5022.2  323.87  5030.8  326.33  5036.9  326.62  5051.7  329.67
  5057.8  329.79  5081.2  332.55  5087.3  332.31  5104.0  333.75  5141.2  334.95
#Mann=4,-1,0
  4769.7    0.12       0  4996.2    0.07       0  5000.2    0.12       0
  5104.0    0.05       0
Bank Sta=4996.2,5000.2
Exp/Cntr=0.3,0.1

Type RM Length L Ch R = 1,1397,294,294,294
BEGIN DESCRIPTION:
Walnut42 5.0
END DESCRIPTION:
XS GIS Cut Line= 3
      2726992.60      6754758.94      2727130.00      6754932.63
      2727238.90      6754989.68
#Sta/Elev= 30
  4860.1  337.14  4892.2  336.47  4913.7  334.88  4921.0  333.32  4927.4  333.96
  4935.5  331.34  4941.9  330.99  4949.9  326.15  4956.3  327.70  4964.4  322.35
  4970.7  322.49  4977.5  321.27  4997.6  319.61  4997.8  319.11  5001.3  319.11
  5001.6  319.61  5006.0  320.39  5020.4  321.25  5041.2  321.89  5063.7  321.59
  5070.1  322.24  5081.6  322.32  5091.4  323.09  5107.8  325.81  5113.5  325.95
  5129.9  328.30  5144.8  329.36  5157.6  329.27  5196.1  331.43  5204.5  331.37
#Mann=3,-1,0
  4860.1    0.12       0  4997.6    0.07       0  5001.6    0.12       0
Bank Sta=4997.6,5001.6
Exp/Cntr=0.3,0.1

Type RM Length L Ch R = 1,1103,222,222,222
BEGIN DESCRIPTION:
Walnut42 4.0
END DESCRIPTION:
XS GIS Cut Line= 3
      2726837.02      6754753.75      2726925.17      6755013.01
      2727025.98      6755110.98
#Sta/Elev= 30
  4879.1  338.94  4907.9  337.72  4939.6  334.99  4954.5  332.40  4960.7  328.52
  4971.3  324.29  4980.6  319.65  4992.4  317.79  5015.2  316.54  5015.5  316.04
  5019.0  316.04  5019.2  316.54  5024.1  317.33  5043.3  318.72  5066.3  318.52
  5080.0  318.99  5098.0  318.87  5111.4  320.20  5129.7  321.52  5149.2  323.54
  5155.1  323.54  5159.1  324.23  5173.3  325.39  5194.6  325.64  5237.0  327.76
  5244.0  327.40  5258.2  328.34  5265.3  328.43  5272.3  329.58  5293.5  330.19
#Mann=3,-1,0
  4879.1    0.12       0  5015.2    0.07       0  5019.2    0.12       0
Bank Sta=5015.2,5019.2
Exp/Cntr=0.3,0.1

Type RM Length L Ch R = 1,881,62,62,62
BEGIN DESCRIPTION:
Walnut42 3.2
END DESCRIPTION:
XS GIS Cut Line= 3
      2726684.04      6754774.47      2726746.27      6755064.86
      2726790.07      6755216.90
#Sta/Elev= 30
  4757.9  332.62  4790.6  330.45  4795.7  328.67  4805.5  328.65  4834.9  327.19
  4840.1  325.84  4856.6  325.63  4884.4  324.35  4889.5  323.14  4912.4  320.59
  4933.8  318.56  4938.9  319.74  4948.7  319.81  4958.9  317.54  4987.6  314.43
  4987.8  313.93  4991.3  313.93  4991.6  314.43  5020.2  316.36  5027.5  317.61
  5032.7  317.10  5040.7  317.35  5050.4  319.38  5054.9  319.38  5074.4  322.00
  5108.1  323.87  5113.3  324.89  5126.2  325.71  5141.8  325.93  5213.1  329.52
#Mann=5,-1,0
  4757.9    0.05       0  4912.4    0.12       0  4987.6    0.07       0
  4991.6    0.12       0  5126.2    0.05       0
Bank Sta=4987.6,4991.6
Exp/Cntr=0.3,0.1

Type RM Length L Ch R = 1,819,237,237,237
BEGIN DESCRIPTION:
Walnut42 3.0
END DESCRIPTION:
XS GIS Cut Line= 3
      2726614.03      6754808.16      2726684.04      6755054.49
      2726727.86      6755216.89
#Sta/Elev= 30
  4782.7  337.15  4809.9  334.85  4849.0  329.57  4858.4  327.62  4877.7  326.37
  4889.6  324.53  4910.4  323.03  4916.8  321.93  4922.0  322.07  4941.6  320.32
  4950.7  318.75  4962.4  317.94  4972.8  318.02  4983.2  313.67  4989.7  312.69
  5012.4  312.31  5012.6  311.81  5016.1  311.81  5016.4  312.31  5019.2  312.38
  5038.8  312.99  5063.3  315.61  5068.5  318.26  5097.3  321.95  5118.0  322.49
  5131.1  321.62  5177.8  324.05  5183.0  326.19  5200.9  326.35  5207.0  327.15
#Mann=5,-1,0
  4782.7    0.05       0  5012.4    0.03       0  5016.4    0.05       0
  5019.2    0.12       0  5131.1    0.05       0
Bank Sta=5012.4,5016.4
Exp/Cntr=0.3,0.1

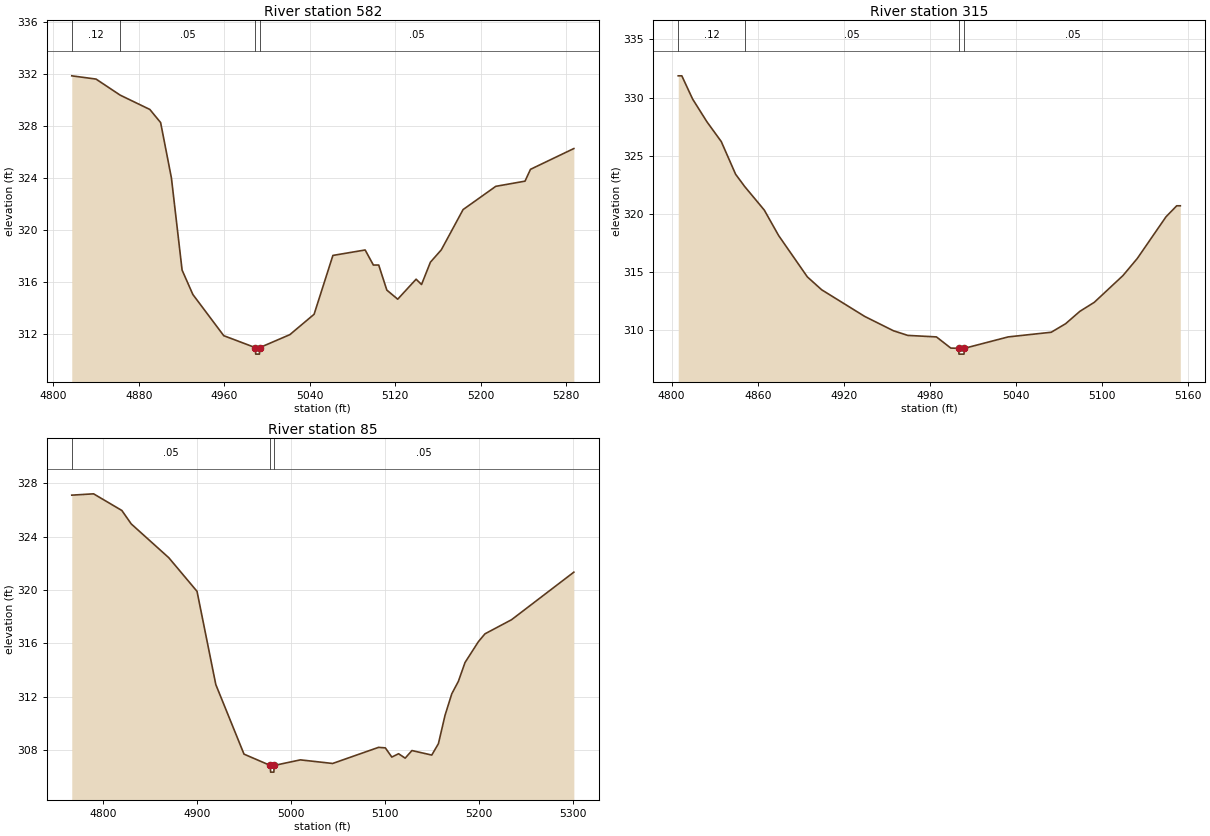
Type RM Length L Ch R = 1,582,267,267,267
BEGIN DESCRIPTION:
Walnut42 2.0
END DESCRIPTION:
XS GIS Cut Line= 3
      2726489.59      6754818.50      2726453.29      6755101.16
      2726489.59      6755282.69
#Sta/Elev= 30
  4817.2  331.88  4839.9  331.63  4862.6  330.39  4890.3  329.29  4900.4  328.28
  4910.5  324.02  4920.5  316.92  4930.6  315.04  4959.5  311.87  4989.1  310.95
  4989.4  310.45  4992.9  310.45  4993.1  310.95  5021.4  311.95  5044.1  313.52
  5061.7  318.05  5091.9  318.47  5099.6  317.31  5104.6  317.31  5112.2  315.38
  5122.4  314.68  5139.6  316.22  5144.7  315.81  5153.0  317.53  5163.2  318.48
  5183.6  321.58  5214.2  323.37  5241.6  323.77  5246.7  324.68  5287.3  326.28
#Mann=4,-1,0
  4817.2    0.12       0  4862.6    0.05       0  4989.1    0.03       0
  4993.1    0.05       0
Bank Sta=4989.1,4993.1
Exp/Cntr=0.3,0.1

Type RM Length L Ch R = 1,315,230,230,230
BEGIN DESCRIPTION:
Walnut42 1.0
END DESCRIPTION:
XS GIS Cut Line= 3
      2726226.00      6754811.04      2726226.00      6755011.00
      2726226.00      6755161.04
#Sta/Elev= 30
  4804.6  331.87  4807.1  331.87  4814.6  329.88  4824.6  327.92  4834.6  326.22
  4844.6  323.41  4850.9  322.36  4864.6  320.33  4874.6  318.14  4894.6  314.59
  4904.6  313.48  4934.6  311.19  4954.6  309.96  4964.6  309.56  4984.6  309.43
  4994.6  308.47  5000.1  308.45  5000.3  307.95  5003.8  307.95  5004.1  308.45
  5034.6  309.43  5064.6  309.83  5074.6  310.56  5084.6  311.63  5094.6  312.40
  5114.6  314.70  5124.6  316.17  5144.6  319.75  5152.1  320.70  5154.6  320.70
#Mann=4,-1,0
  4804.6    0.12       0  4850.9    0.05       0  5000.1    0.03       0
  5004.1    0.05       0
Bank Sta=5000.1,5004.1
Exp/Cntr=0.3,0.1

Type RM Length L Ch R = 1,85,0,0,0
BEGIN DESCRIPTION:
Walnut42 0.5
END DESCRIPTION:
XS GIS Cut Line= 3
      2726004.74      6754727.76      2726012.52      6755005.23
      2726196.62      6755184.15
#Sta/Elev= 30
  4766.7  327.12  4789.9  327.22  4820.0  325.97  4830.0  324.96  4870.0  322.42
  4900.0  319.90  4920.0  312.90  4950.0  307.68  4978.0  306.83  4978.3  306.33
  4981.8  306.33  4982.0  306.83  5010.0  307.25  5044.3  306.98  5093.2  308.19
  5100.4  308.15  5107.3  307.46  5114.5  307.71  5121.5  307.38  5128.7  307.95
  5149.8  307.61  5156.9  308.47  5163.9  310.59  5171.1  312.21  5178.1  313.14
  5185.2  314.56  5199.4  316.12  5206.4  316.71  5234.7  317.77  5301.0  321.34
#Mann=3,-1,0
  4766.7    0.05       0  4978.0    0.03       0  4982.0    0.05       0
Bank Sta=4978,4982
Exp/Cntr=0.3,0.1

Chan Stop Cuts=-1