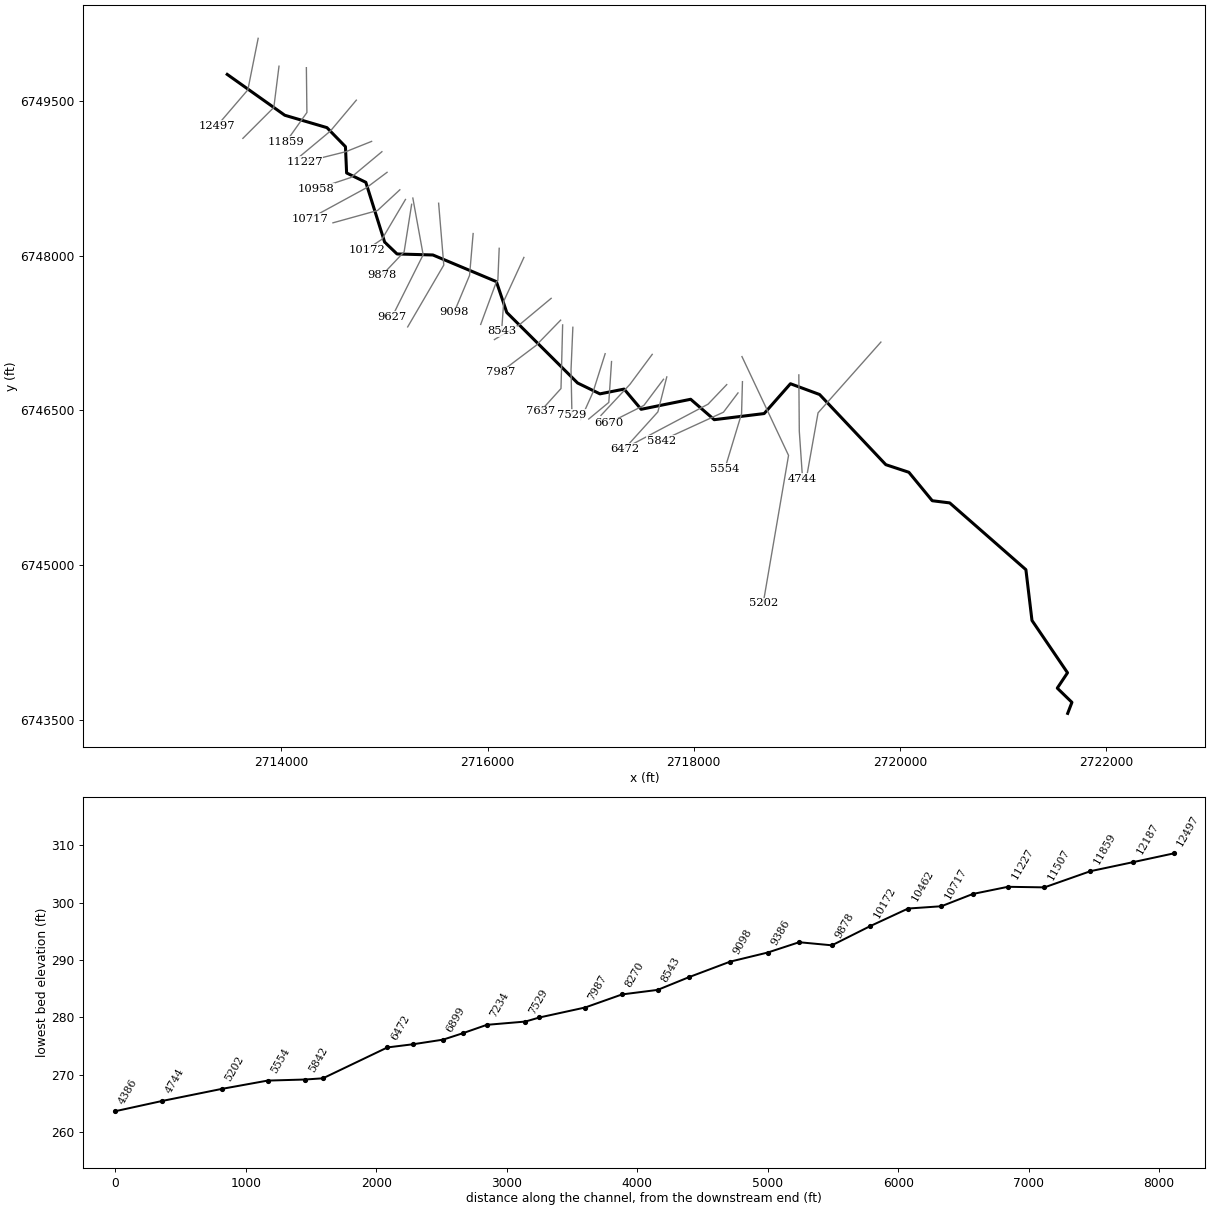
--- Walnut44.prj (project) ---

Proj Title=Walnut44 Base Level Engineering
Current Plan=p01
Default Exp/Contr=0.3,0.1
English Units
Geom File=g01
Flow File=f01
Plan File=p01
Y Axis Title=Elevation
X Axis Title(PF)=Main Channel Distance
X Axis Title(XS)=Station
BEGIN DESCRIPTION:
Walnut44
END DESCRIPTION:
DSS Export Rating Curves= 0
DSS Export Rating Curve Sorted= 0
DSS Export Volume Flow Curves= 0
DXF OffsetX= 0
DXF OffsetY= 0
DXF ScaleX= 1
DXF ScaleY= 10

--- Walnut44.p01 (plan) ---

Plan Title=Multiple Run
Program Version=4.10
Short Identifier=Multiple
Geom File=g01
Flow File=f01
Subcritical Flow
K Sum by GR= 0
Std Step Tol= 0.01
Critical Tol= 0.01
Num of Std Step Trials= 20
Max Error Tol= 0.3
Flow Tol Ratio= 0.001
Split Flow NTrial= 30
Split Flow Tol= 0.02
Split Flow Ratio= 0.02
Log Output Level= 0
Friction Slope Method= 1
Unsteady Friction Slope Method= 2
Unsteady Bridges Friction Slope Method= 1
Parabolic Critical Depth
Global Vel Dist= 1 , 1 , 1
Global Log Level= 0
CheckData=True
Encroach Param=-1 ,0,0, 0
BEGIN DESCRIPTION:
Multiple Run
END DESCRIPTION:
Computation Interval=1HOUR
Output Interval=1HOUR
Run HTab= 0
Run UNet= 0
Run PostProcess= 0
Run WQNet= 0
UNET Theta= 1
UNET Theta Warmup= 1
UNET ZTol= 0.02
UNET ZSATol= 0.05
UNET MxIter= 20
UNET MaxInSteps= 0
UNET DtIC= 0
UNET DtMin= 0
UNET MaxCRTS= 20
UNET WFStab= 2
UNET SFStab= 1
UNET WFX= 1
UNET SFX= 1
UNET DSS MLevel= 4
UNET DZMax Abort= 100
UNET Convert EG Bridges= 0
UNET Use Existing IB Tables=-1
UNET Froude Reduction=False
UNET Froude Limit= 1
UNET Froude Power= 10
UNET Time Slicing=0,0, 5
UNET Junction Losses=0
Instantaneous Interval=1HOUR
Write IC File= 0
Write IC File at Sim End=0
Echo Input=False
Echo Parameters=False
Echo Output=False
Write Detailed= 0
WQ AD Non Conservative
WQ ULTIMATE=-1
WQ Max Comp Step=1HOUR
WQ Output Interval=15MIN
WQ Output Selected Increments= 0
WQ Output face flow=0
WQ Output face velocity=0
WQ Output face area=0
WQ Output face dispersion=0
WQ Output cell volume=0
WQ Output cell surface area=0
WQ Output cell continuity=0
WQ Output cumulative cell continuity=0
WQ Output face conc=0
WQ Output face dconc_dx=0
WQ Output face courant=0
WQ Output face peclet=0
WQ Output face adv mass=0
WQ Output face disp mass=0
WQ Output cell mass=0
WQ Output cell source sink temp=0
WQ Output cell source sink nsm=0
WQ Output MaxMinRange=-1
WQ Daily Max Min Mean=-1
WQ Daily Range=0
WQ Daily Time=0
WQ Create Restart=0
WQ Fixed Restart=0
WQ System Summary=0
WQ Use Fixed Temperature=0
Sorting and Armoring Iterations= 10
XS Update Threshold= 0.02
Hydraulics Update Threshold= 0.02
Energy Slope Method= 1
Volume Change Method= 0
XS Weighting Method= 0
Number of US Weighted Cross Sections= 1
Number of DS Weighted Cross Sections= 1
Upstream XS Weight=0.25
Main XS Weight=0.5
Downstream XS Weight=0.25
Number of DS XS's Weighted with US Boundary= 1
Upstream Boundary Weight= 1
Weight of XSs Associated with US Boundary= 0
Number of US XS's Weighted with DS Boundary= 1
Downstream Boundary Weight= 0.5
Weight of XSs Associated with DS Boundary= 0.5
Sediment Output Level= 4
Mass or Volume Output= 0
Output Increment Type= 1
Profile and TS Output Increment= 10
XS Output Flag= 0
XS Output Increment= 10
Disregard all LS=0
Disregard all Conn=0
Disregard all Breaches=0
Disregard all Pumps=0

--- Walnut44.f01 (steady flow) ---

Flow Title=Multiple
Number of Profiles=7
Profile Names=10-year,25-year,50-year,1pct_min,100-year,1pct_plu,500-year
River Rch & RM= Walnut44,Reach-1,12497
     117     140     156      87     174     347     215
River Rch & RM= Walnut44,Reach-1,11507
     321     414     487     285     569    1136     777
River Rch & RM= Walnut44,Reach-1,5978
     564     754     907     542    1081    2156    1538
River Rch & RM= Walnut44,Reach-1,3579
     906    1232    1498     902    1799    3589    2595
Boundary for River Rch & Prof#=Walnut44,Reach-1,1
Up Type=0
Dn Type=3
Dn Slope=0.005
Boundary for River Rch & Prof#=Walnut44,Reach-1,2
Up Type=0
Dn Type=3
Dn Slope=0.005
Boundary for River Rch & Prof#=Walnut44,Reach-1,3
Up Type=0
Dn Type=3
Dn Slope=0.005
Boundary for River Rch & Prof#=Walnut44,Reach-1,4
Up Type=0
Dn Type=3
Dn Slope=0.005
Boundary for River Rch & Prof#=Walnut44,Reach-1,5
Up Type=0
Dn Type=3
Dn Slope=0.005
Boundary for River Rch & Prof#=Walnut44,Reach-1,6
Up Type=0
Dn Type=3
Dn Slope=0.005
Boundary for River Rch & Prof#=Walnut44,Reach-1,7
Up Type=0
Dn Type=3
Dn Slope=0.005

--- Walnut44.g01 (geometry) ---

Geom Title=Existing Conditions

River Reach=Walnut44,Reach-1
Reach XY= 30
      2713476.00      6749761.00      2714034.20      6749364.70
      2714443.05      6749244.52      2714622.55      6749059.75
      2714633.81      6748804.77      2714820.17      6748713.84
      2715002.29      6748134.17      2715122.61      6748018.83
      2715470.51      6748008.91      2716086.05      6747750.38
      2716186.75      6747451.29      2716873.47      6746766.77
      2717090.09      6746661.23      2717324.75      6746707.56
      2717489.85      6746511.53      2717970.10      6746608.77
      2718198.64      6746410.80      2718682.73      6746470.15
      2718937.54      6746759.51      2719220.23      6746655.02
      2719862.34      6745974.26      2720086.00      6745900.37
      2720312.68      6745624.37      2720482.19      6745603.18
      2721220.78      6744955.54      2721279.82      6744462.58
      2721624.45      6743954.98      2721525.11      6743805.95
      2721667.15      6743668.02      2721626.00      6743561.00

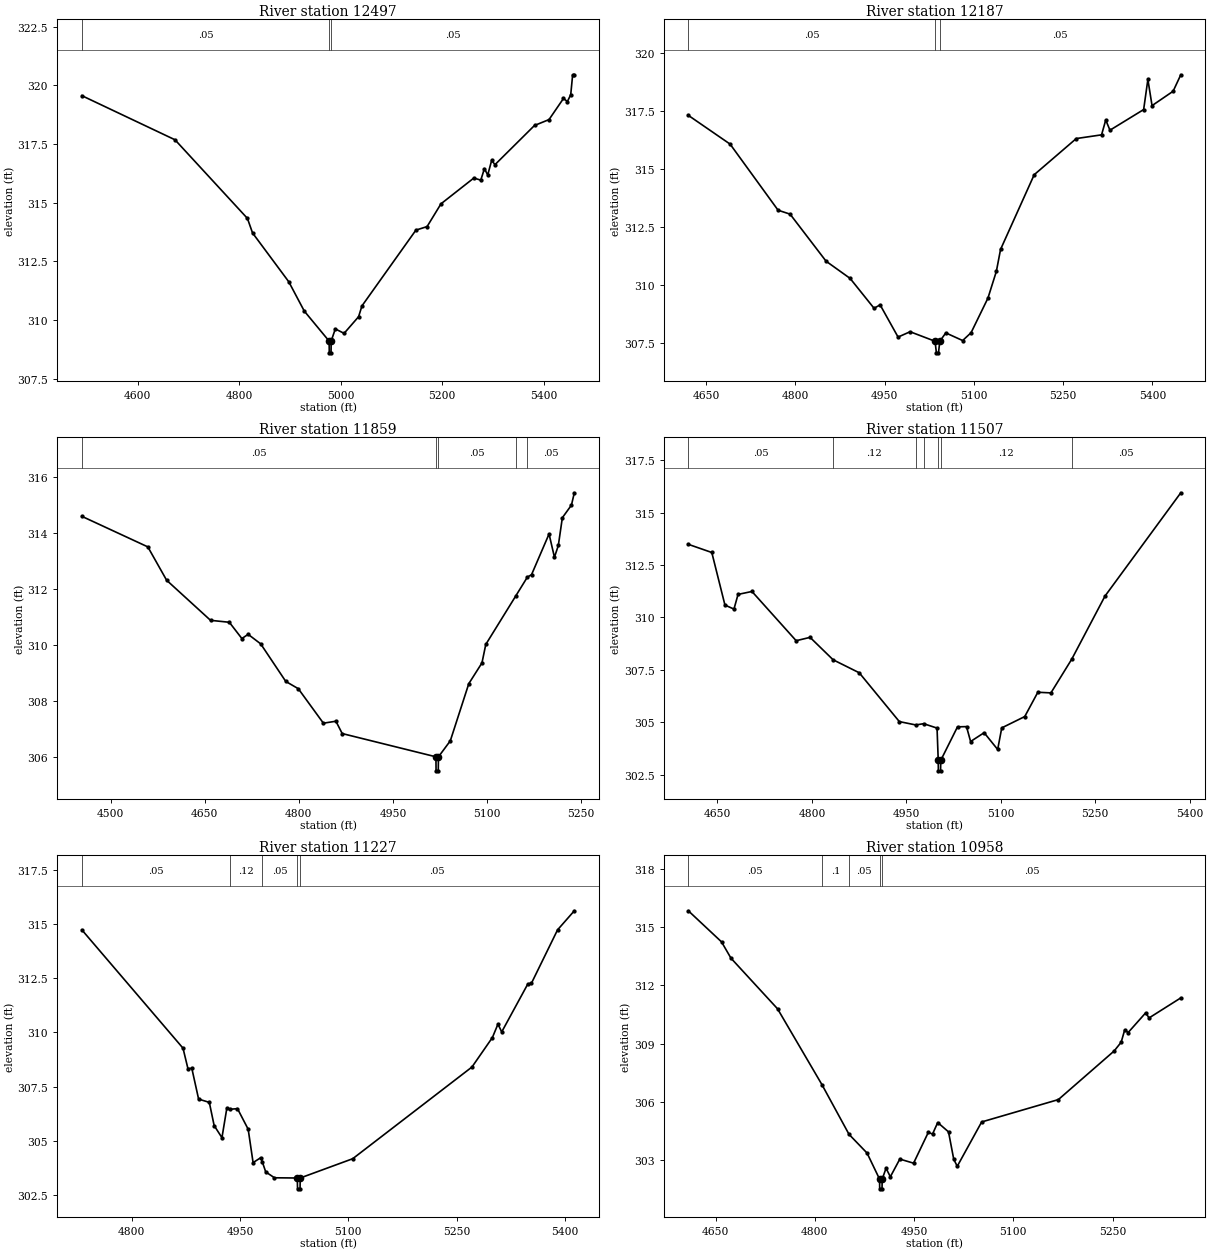
Type RM Length L Ch R = 1,12497,310,310,310
BEGIN DESCRIPTION:
Walnut44 32.0
END DESCRIPTION:
XS GIS Cut Line= 3
      2713776.00      6750111.01      2713676.00      6749611.00
      2713376.00      6749260.99
#Sta/Elev= 30
  4489.8  319.56  4673.4  317.68  4816.2  314.33  4826.3  313.71  4897.7  311.63
  4928.3  310.38  4977.3  309.10  4977.6  308.60  4981.1  308.60  4981.3  309.10
  4989.5  309.62  5006.8  309.43  5035.4  310.14  5042.0  310.60  5148.4  313.83
  5170.4  313.98  5197.8  314.95  5262.6  316.05  5276.3  315.96  5283.4  316.45
  5290.0  316.18  5297.7  316.80  5304.3  316.62  5382.2  318.29  5410.8  318.54
  5439.3  319.44  5447.0  319.31  5453.6  319.60  5457.4  320.45  5460.7  320.45
#Mann=3,-1,0
  4489.8    0.05       0  4977.3    0.04       0  4981.3    0.05       0
Bank Sta=4977.3,4981.3
Exp/Cntr=0.3,0.1

Type RM Length L Ch R = 1,12187,328,328,328
BEGIN DESCRIPTION:
Walnut44 31.0
END DESCRIPTION:
XS GIS Cut Line= 3
      2713978.08      6749840.68      2713928.08      6749440.69
      2713628.06      6749140.67
#Sta/Elev= 30
  4620.3  317.32  4690.5  316.08  4771.1  313.23  4791.3  313.06  4851.8  311.03
  4892.1  310.29  4932.4  309.00  4942.5  309.15  4972.7  307.76  4992.9  307.99
  5034.8  307.58  5037.1  307.08  5040.6  307.08  5042.8  307.58  5052.9  307.94
  5081.2  307.61  5095.4  307.95  5123.7  309.44  5137.8  310.59  5144.9  311.54
  5201.4  314.76  5272.1  316.32  5314.6  316.48  5321.6  317.12  5328.7  316.68
  5385.3  317.57  5392.4  318.87  5399.4  317.74  5434.8  318.36  5447.7  319.07
#Mann=3,-1,0
  4620.3    0.05       0  5034.8    0.04       0  5042.8    0.05       0
Bank Sta=5034.8,5042.8
Exp/Cntr=0.3,0.1

Type RM Length L Ch R = 1,11859,352,352,352
BEGIN DESCRIPTION:
Walnut44 30.0
END DESCRIPTION:
XS GIS Cut Line= 3
      2714243.55      6749826.19      2714248.76      6749391.25
      2714046.06      6749105.39
#Sta/Elev= 30
  4453.9  314.58  4559.1  313.49  4589.1  312.30  4659.1  310.87  4689.1  310.80
  4709.1  310.22  4719.1  310.37  4739.1  310.03  4779.1  308.69  4799.1  308.43
  4839.1  307.20  4859.1  307.27  4869.1  306.83  5018.6  306.00  5018.8  305.50
  5022.3  305.50  5022.6  306.00  5041.5  306.57  5071.0  308.61  5092.0  309.35
  5098.1  310.01  5146.2  311.75  5164.4  312.41  5171.1  312.50  5199.0  313.95
  5207.6  313.12  5213.8  313.54  5220.2  314.53  5234.7  314.98  5239.3  315.42
#Mann=5,-1,0
  4453.9    0.05       0  5018.6    0.05       0  5022.6    0.05       0
  5146.2    0.12       0  5164.4    0.05       0
Bank Sta=5018.6,5022.6
Exp/Cntr=0.3,0.1

Type RM Length L Ch R = 1,11507,280,280,280
BEGIN DESCRIPTION:
Walnut44 29.0
END DESCRIPTION:
XS GIS Cut Line= 3
      2714727.95      6749511.07      2714476.00      6749211.00
      2714176.02      6748961.02
#Sta/Elev= 30
  4603.7  313.49  4641.0  313.10  4661.9  310.59  4676.2  310.40  4682.7  311.10
  4704.8  311.24  4775.0  308.89  4797.1  309.05  4833.7  307.98  4875.2  307.36
  4938.9  305.03  4965.0  304.87  4977.5  304.93  4998.8  304.72  5000.7  303.18
  5000.9  302.68  5004.4  302.68  5004.7  303.18  5031.3  304.78  5045.6  304.79
  5052.1  304.08  5073.6  304.50  5095.1  303.70  5101.6  304.73  5138.1  305.27
  5158.9  306.43  5179.7  306.40  5212.8  308.01  5265.6  311.02  5386.0  315.95
#Mann=7,-1,0
  4603.7    0.05       0  4833.7    0.12       0  4965.0    0.05       0
  4977.5    0.12       0  5000.7    0.07       0  5004.7    0.12       0
  5212.8    0.05       0
Bank Sta=5000.7,5004.7
Exp/Cntr=0.3,0.1

Type RM Length L Ch R = 1,11227,269,269,269
BEGIN DESCRIPTION:
Walnut44 28.0
END DESCRIPTION:
XS GIS Cut Line= 3
      2714876.03      6749111.01      2714626.00      6749011.00
      2714226.00      6748911.00
#Sta/Elev= 30
  4731.2  314.73  4871.2  309.27  4878.0  308.33  4883.4  308.34  4892.8  306.92
  4907.6  306.77  4914.3  305.70  4925.1  305.14  4931.8  306.49  4935.7  306.45
  4946.6  306.48  4961.4  305.53  4968.2  303.99  4978.9  304.22  4980.9  304.03
  4985.7  303.56  4997.8  303.29  5029.4  303.28  5029.7  302.78  5033.2  302.78
  5033.4  303.28  5106.1  304.17  5271.1  308.40  5299.4  309.76  5307.1  310.38
  5312.3  310.02  5348.4  312.23  5353.5  312.27  5389.6  314.73  5412.8  315.61
#Mann=5,-1,0
  4731.2    0.05       0  4935.7    0.12       0  4980.9    0.05       0
  5029.4    0.04       0  5033.4    0.05       0
Bank Sta=5029.4,5033.4
Exp/Cntr=0.3,0.1

Type RM Length L Ch R = 1,10958,241,241,241
BEGIN DESCRIPTION:
Walnut44 27.0
END DESCRIPTION:
XS GIS Cut Line= 3
      2714976.03      6749011.03      2714676.00      6748761.00
      2714340.48      6748649.26
#Sta/Elev= 30
  4608.8  315.83  4659.0  314.23  4673.3  313.39  4743.6  310.79  4810.7  306.89
  4851.7  304.33  4878.9  303.37  4897.8  302.03  4898.0  301.53  4901.5  301.53
  4901.8  302.03  4907.6  302.59  4914.1  302.15  4928.4  303.06  4949.2  302.85
  4971.4  304.43  4977.9  304.35  4985.7  304.94  5002.0  304.46  5009.9  303.05
  5015.2  302.69  5052.1  304.97  5168.0  306.12  5252.3  308.62  5262.9  309.07
  5268.2  309.70  5273.5  309.57  5299.9  310.58  5305.1  310.32  5353.0  311.35
#Mann=5,-1,0
  4608.8    0.05       0  4810.7     0.1       0  4851.7    0.05       0
  4897.8    0.04       0  4901.8    0.05       0
Bank Sta=4897.8,4901.8
Exp/Cntr=0.3,0.1

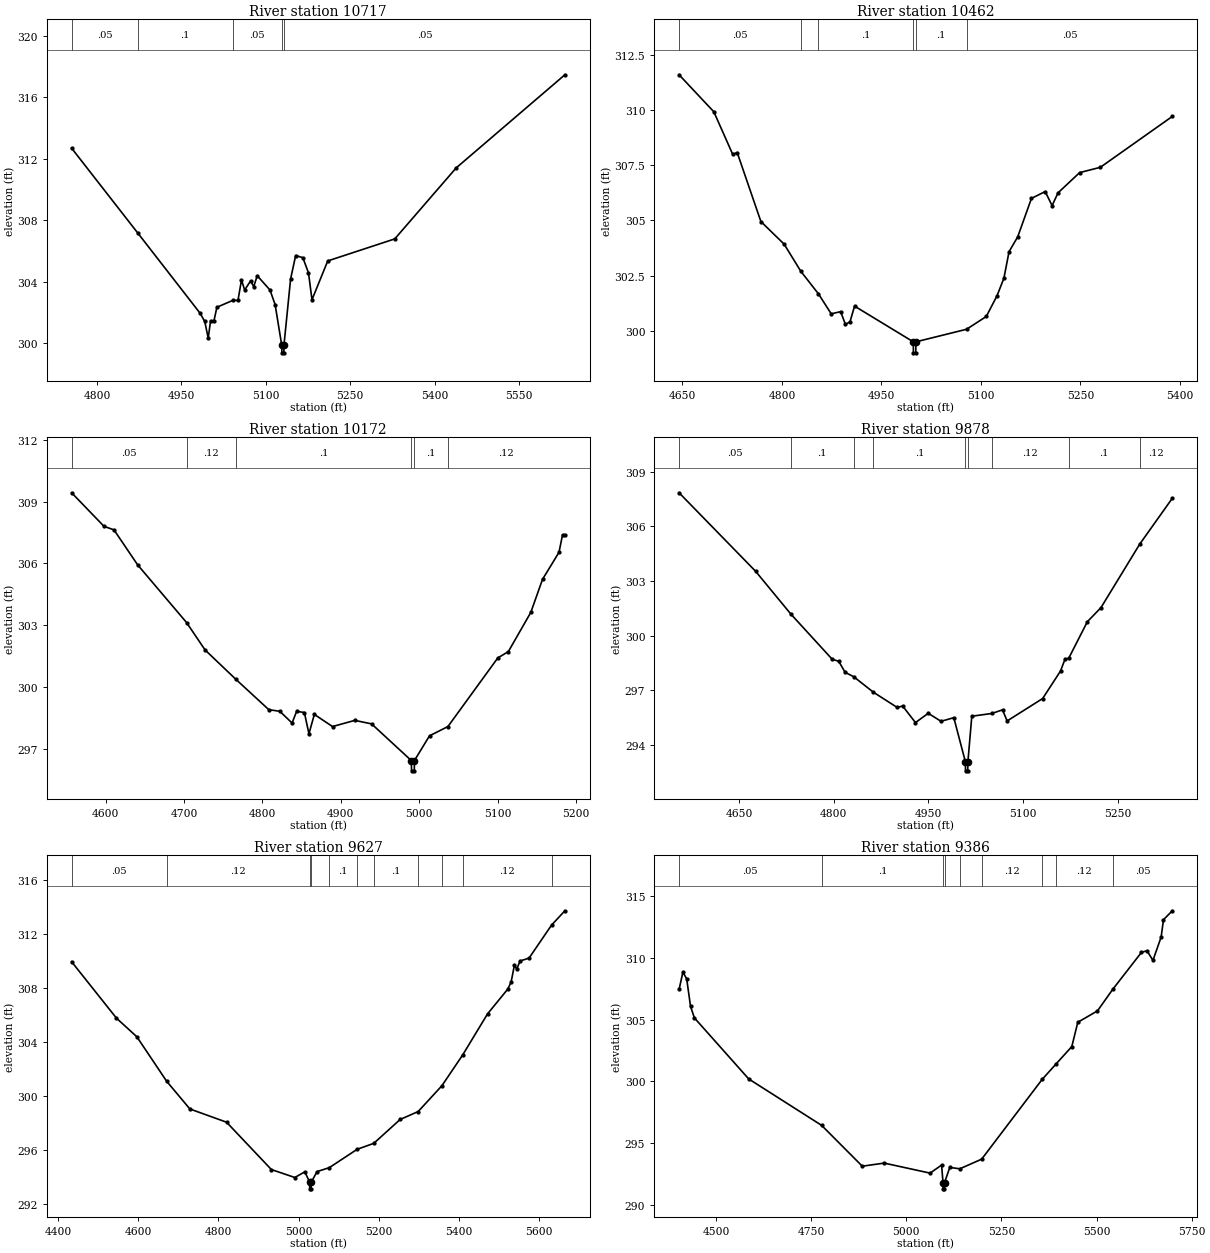
Type RM Length L Ch R = 1,10717,255,255,255
BEGIN DESCRIPTION:
Walnut44 26.0
END DESCRIPTION:
XS GIS Cut Line= 3
      2715026.02      6748811.01      2714826.00      6748661.00
      2714276.02      6748361.01
#Sta/Elev= 30
  4754.8  312.68  4872.8  307.15  4982.9  301.97  4991.3  301.43  4997.5  300.35
  5001.7  301.47  5007.7  301.47  5012.9  302.35  5040.7  302.79  5050.4  302.80
  5056.6  304.12  5062.3  303.47  5072.7  304.06  5078.4  303.69  5084.6  304.40
  5107.3  303.47  5116.4  302.52  5128.1  299.89  5128.4  299.39  5131.9  299.39
  5132.1  299.89  5143.9  304.19  5152.9  305.71  5165.7  305.57  5175.7  304.58
  5181.9  302.84  5209.9  305.36  5329.0  306.79  5438.1  311.40  5631.3  317.45
#Mann=5,-1,0
  4754.8    0.05       0  4872.8     0.1       0  5040.7    0.05       0
  5128.1    0.07       0  5132.1    0.05       0
Bank Sta=5128.1,5132.1
Exp/Cntr=0.3,0.1

Type RM Length L Ch R = 1,10462,290,290,290
BEGIN DESCRIPTION:
Walnut44 25.0
END DESCRIPTION:
XS GIS Cut Line= 3
      2715149.82      6748641.27      2714933.66      6748440.73
      2714501.41      6748320.95
#Sta/Elev= 30
  4645.0  311.61  4697.4  309.93  4725.8  308.00  4732.6  308.08  4768.3  304.95
  4803.4  303.92  4828.5  302.69  4855.0  301.67  4874.3  300.76  4888.5  300.86
  4895.7  300.28  4902.6  300.40  4909.5  301.11  4998.0  299.49  4998.2  298.99
  5001.7  298.99  5002.0  299.49  5078.3  300.06  5108.0  300.64  5124.2  301.58
  5134.6  302.38  5142.3  303.58  5155.3  304.25  5176.1  306.00  5196.8  306.31
  5207.2  305.67  5216.1  306.25  5248.7  307.17  5279.9  307.41  5388.4  309.72
#Mann=6,-1,0
  4645.0    0.05       0  4828.5    0.12       0  4855.0     0.1       0
  4998.0    0.07       0  5002.0     0.1       0  5078.3    0.05       0
Bank Sta=4998,5002
Exp/Cntr=0.3,0.1

Type RM Length L Ch R = 1,10172,294,294,294
BEGIN DESCRIPTION:
Walnut44 24.0
END DESCRIPTION:
XS GIS Cut Line= 3
      2715204.48      6748547.48      2714976.00      6748161.00
      2714826.03      6748061.02
#Sta/Elev= 30
  4556.7  309.43  4598.0  307.80  4610.7  307.63  4640.9  305.93  4703.3  303.13
  4726.9  301.80  4766.0  300.38  4808.2  298.90  4822.3  298.82  4837.9  298.25
  4843.7  298.82  4853.6  298.76  4859.4  297.73  4866.3  298.67  4889.5  298.08
  4917.9  298.38  4939.3  298.21  4990.0  296.43  4990.3  295.93  4993.8  295.93
  4994.0  296.43  5013.2  297.63  5036.7  298.08  5100.3  301.41  5113.8  301.72
  5142.4  303.62  5157.4  305.23  5178.4  306.54  5182.9  307.39  5185.9  307.39
#Mann=6,-1,0
  4556.7    0.05       0  4703.3    0.12       0  4766.0     0.1       0
  4990.0    0.07       0  4994.0     0.1       0  5036.7    0.12       0
Bank Sta=4990,4994
Exp/Cntr=0.3,0.1

Type RM Length L Ch R = 1,9878,251,251,251
BEGIN DESCRIPTION:
Walnut44 23.0
END DESCRIPTION:
XS GIS Cut Line= 3
      2715264.38      6748500.58      2715191.47      6748039.69
      2714976.02      6747811.02
#Sta/Elev= 30
  4555.2  307.85  4676.3  303.54  4732.1  301.19  4797.8  298.70  4807.9  298.60
  4818.0  297.99  4831.6  297.75  4862.7  296.90  4900.5  296.06  4909.1  296.14
  4929.4  295.23  4949.6  295.74  4969.9  295.30  4990.1  295.50  5008.4  293.08
  5008.6  292.58  5012.1  292.58  5012.4  293.08  5018.6  295.58  5050.3  295.73
  5067.2  295.93  5074.5  295.32  5130.7  296.55  5159.0  298.06  5166.3  298.73
  5171.8  298.75  5201.5  300.77  5223.0  301.54  5284.4  305.03  5336.0  307.55
#Mann=9,-1,0
  4555.2    0.05       0  4732.1     0.1       0  4831.6    0.12       0
  4862.7     0.1       0  5008.4    0.07       0  5012.4     0.1       0
  5050.3    0.12       0  5171.8     0.1       0  5284.4    0.12       0
Bank Sta=5008.4,5012.4
Exp/Cntr=0.3,0.1

Type RM Length L Ch R = 1,9627,241,241,241
BEGIN DESCRIPTION:
Walnut44 22.0
END DESCRIPTION:
XS GIS Cut Line= 3
      2715276.00      6748561.01      2715376.00      6748011.00
      2715076.02      6747411.04
#Sta/Elev= 30
  4434.0  309.95  4545.8  305.77  4596.6  304.39  4671.0  301.09  4728.8  299.04
  4820.2  298.06  4932.0  294.55  4990.5  293.96  5015.4  294.38  5027.4  293.62
  5027.6  293.12  5031.1  293.12  5031.4  293.62  5046.1  294.40  5076.4  294.69
  5145.9  296.05  5187.2  296.49  5253.0  298.26  5298.0  298.85  5357.1  300.76
  5408.9  303.04  5471.0  306.09  5521.3  307.92  5529.7  308.44  5538.1  309.72
  5543.7  309.40  5552.0  310.01  5574.4  310.22  5630.6  312.67  5663.8  313.73
#Mann=11,-1,0
  4434.0    0.05       0  4671.0    0.12       0  5027.4    0.07       0
  5031.4    0.12       0  5076.4     0.1       0  5145.9    0.12       0
  5187.2     0.1       0  5298.0    0.12       0  5357.1     0.1       0
  5408.9    0.12       0  5630.6    0.05       0
Bank Sta=5027.4,5031.4
Exp/Cntr=0.3,0.1

Type RM Length L Ch R = 1,9386,288,288,288
BEGIN DESCRIPTION:
Walnut44 21.0
END DESCRIPTION:
XS GIS Cut Line= 3
      2715526.00      6748510.98      2715576.00      6747911.00
      2715225.99      6747310.98
#Sta/Elev= 30
  4402.5  307.43  4412.5  308.83  4422.5  308.29  4432.6  306.07  4442.6  305.14
  4585.6  300.20  4777.2  296.45  4884.1  293.15  4941.8  293.40  5062.4  292.59
  5092.6  293.24  5096.4  291.82  5096.7  291.32  5100.2  291.32  5100.4  291.82
  5114.1  293.05  5140.6  292.94  5198.0  293.72  5356.9  300.16  5393.2  301.40
  5435.0  302.82  5450.7  304.78  5502.4  305.70  5543.0  307.46  5618.1  310.43
  5632.6  310.56  5648.3  309.78  5669.8  311.67  5676.0  313.07  5699.2  313.79
#Mann=9,-1,0
  4402.5    0.05       0  4777.2     0.1       0  5096.4    0.07       0
  5100.4     0.1       0  5140.6    0.05       0  5198.0    0.12       0
  5356.9     0.1       0  5393.2    0.12       0  5543.0    0.05       0
Bank Sta=5096.4,5100.4
Exp/Cntr=0.3,0.1

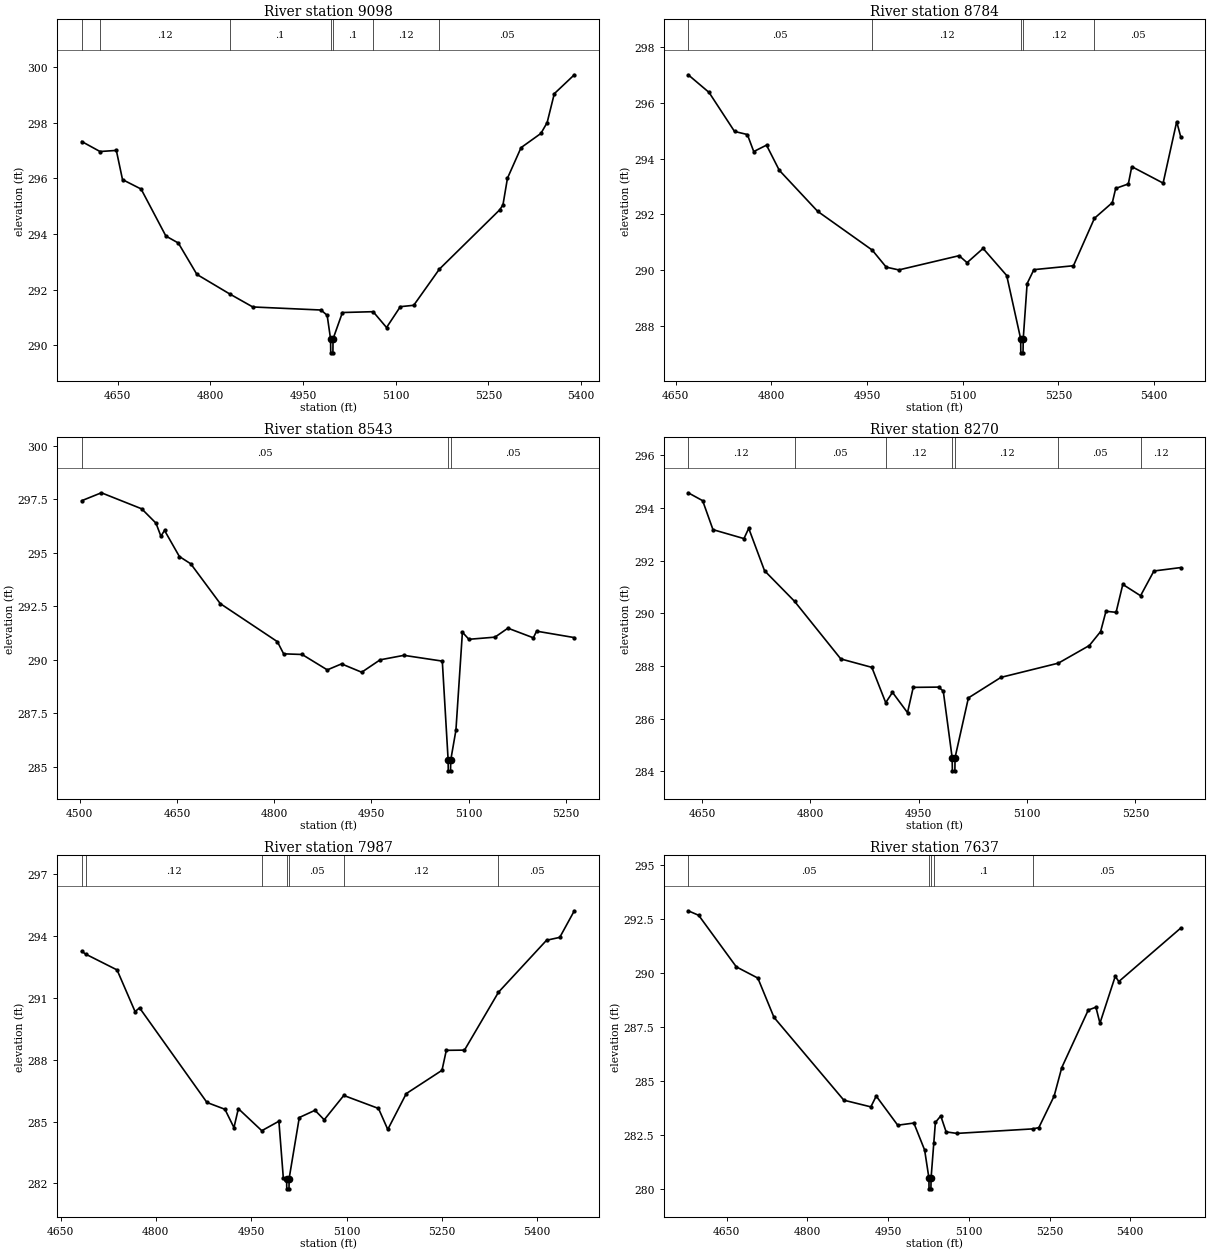
Type RM Length L Ch R = 1,9098,314,314,314
BEGIN DESCRIPTION:
Walnut44 20.0
END DESCRIPTION:
XS GIS Cut Line= 3
      2715860.74      6748216.75      2715826.00      6747811.00
      2715675.83      6747451.11
#Sta/Elev= 30
  4591.9  297.33  4621.5  296.97  4647.9  297.01  4657.9  295.96  4688.0  295.62
  4728.1  293.93  4748.2  293.68  4778.3  292.55  4831.2  291.85  4868.7  291.38
  4979.1  291.27  4989.1  291.08  4994.6  290.23  4994.9  289.73  4998.4  289.73
  4998.6  290.23  5013.8  291.18  5063.5  291.21  5085.2  290.64  5107.5  291.39
  5129.2  291.44  5170.7  292.74  5268.2  294.87  5273.6  295.05  5280.9  296.01
  5302.9  297.11  5335.0  297.62  5345.1  298.01  5356.7  299.05  5389.1  299.73
#Mann=7,-1,0
  4591.9    0.05       0  4621.5    0.12       0  4831.2     0.1       0
  4994.6    0.07       0  4998.6     0.1       0  5063.5    0.12       0
  5170.7    0.05       0
Bank Sta=4994.6,4998.6
Exp/Cntr=0.3,0.1

Type RM Length L Ch R = 1,8784,241,241,241
BEGIN DESCRIPTION:
Walnut44 19.0
END DESCRIPTION:
XS GIS Cut Line= 4
      2716113.35      6748073.58      2716100.33      6747761.05
      2716085.05      6747745.09      2715934.04      6747335.00
#Sta/Elev= 30
  4669.9  297.00  4702.5  296.37  4742.5  294.97  4762.6  294.86  4772.6  294.25
  4792.6  294.48  4812.6  293.58  4872.7  292.11  4958.3  290.72  4980.2  290.11
  4999.9  290.01  5094.4  290.52  5106.9  290.27  5132.0  290.78  5169.0  289.81
  5190.9  287.54  5191.1  287.04  5194.6  287.04  5194.9  287.54  5201.0  289.52
  5211.6  290.02  5273.6  290.16  5306.5  291.86  5334.5  292.42  5339.8  292.93
  5359.6  293.09  5365.0  293.71  5414.1  293.12  5435.4  295.32  5441.8  294.77
#Mann=5,-1,0
  4669.9    0.05       0  4958.3    0.12       0  5190.9    0.07       0
  5194.9    0.12       0  5306.5    0.05       0
Bank Sta=5190.9,5194.9
Exp/Cntr=0.3,0.1

Type RM Length L Ch R = 1,8543,273,273,273
BEGIN DESCRIPTION:
Walnut44 18.8
END DESCRIPTION:
XS GIS Cut Line= 3
      2716352.94      6747985.04      2716157.62      6747560.53
      2716136.78      6747268.86
#Sta/Elev= 30
  4503.2  297.44  4533.5  297.81  4595.7  297.06  4617.7  296.39  4625.3  295.78
  4630.9  296.05  4653.8  294.83  4671.3  294.49  4716.8  292.63  4804.9  290.85
  4814.6  290.28  4843.1  290.25  4881.9  289.53  4903.9  289.81  4935.0  289.42
  4963.4  290.00  5000.1  290.21  5059.3  289.94  5068.3  285.31  5068.5  284.81
  5072.0  284.81  5072.3  285.31  5080.3  286.71  5090.3  291.29  5100.3  290.96
  5140.5  291.06  5160.5  291.48  5199.7  291.03  5204.7  291.34  5262.9  291.04
#Mann=3,-1,0
  4503.2    0.05       0  5068.3    0.07       0  5072.3    0.05       0
Bank Sta=5068.3,5072.3
Exp/Cntr=0.3,0.1

Type RM Length L Ch R = 1,8270,283,283,283
BEGIN DESCRIPTION:
Walnut44 18.0
END DESCRIPTION:
XS GIS Cut Line= 3
      2716617.16      6747588.10      2716317.15      6747338.08
      2716067.13      6747188.07
#Sta/Elev= 30
  4630.8  294.58  4650.8  294.28  4665.1  293.18  4708.0  292.84  4714.6  293.23
  4736.5  291.62  4778.0  290.46  4842.1  288.27  4885.1  287.95  4904.3  286.61
  4913.7  287.00  4934.5  286.23  4942.4  287.19  4977.5  287.20  4984.0  287.05
  4996.3  284.52  4996.6  284.02  5000.1  284.02  5000.3  284.52  5018.8  286.79
  5063.9  287.57  5143.4  288.11  5186.3  288.78  5201.9  289.31  5209.3  290.08
  5223.3  290.04  5232.6  291.10  5257.2  290.67  5275.7  291.61  5312.9  291.74
#Mann=7,-1,0
  4630.8    0.12       0  4778.0    0.05       0  4904.3    0.12       0
  4996.3    0.07       0  5000.3    0.12       0  5143.4    0.05       0
  5257.2    0.12       0
Bank Sta=4996.3,5000.3
Exp/Cntr=0.3,0.1

Type RM Length L Ch R = 1,7987,350,350,350
BEGIN DESCRIPTION:
Walnut44 17.0
END DESCRIPTION:
XS GIS Cut Line= 3
      2716709.12      6747376.46      2716470.25      6747130.52
      2716125.17      6746870.38
#Sta/Elev= 30
  4683.4  293.27  4689.4  293.13  4739.0  292.36  4767.3  290.34  4774.4  290.52
  4880.4  285.93  4908.7  285.60  4922.9  284.71  4929.8  285.63  4966.7  284.56
  4993.6  285.02  5000.6  282.25  5005.7  282.24  5006.0  281.74  5009.5  281.74
  5009.7  282.24  5025.7  285.20  5050.4  285.55  5064.9  285.09  5095.7  286.27
  5150.3  285.64  5164.9  284.62  5194.0  286.36  5250.2  287.49  5257.0  288.46
  5285.6  288.47  5339.1  291.28  5414.7  293.80  5435.5  293.94  5458.4  295.23
#Mann=7,-1,0
  4683.4    0.05       0  4689.4    0.12       0  4966.7    0.05       0
  5005.7    0.03       0  5009.7    0.05       0  5095.7    0.12       0
  5339.1    0.05       0
Bank Sta=5005.7,5009.7
Exp/Cntr=0.3,0.1

Type RM Length L Ch R = 1,7637,108,108,108
BEGIN DESCRIPTION:
Walnut44 16.0
END DESCRIPTION:
XS GIS Cut Line= 3
      2716728.59      6747330.45      2716712.66      6746712.93
      2716512.70      6746491.74
#Sta/Elev= 30
  4578.2  292.89  4597.7  292.68  4667.7  290.29  4707.7  289.77  4737.7  287.95
  4867.6  284.11  4917.8  283.80  4927.8  284.30  4967.8  282.95  4997.8  283.05
  5017.8  281.80  5025.8  280.50  5026.0  280.00  5029.5  280.00  5029.8  280.50
  5034.9  282.14  5037.8  283.08  5047.8  283.38  5057.8  282.64  5077.8  282.57
  5219.5  282.78  5230.2  282.84  5258.6  284.30  5272.8  285.62  5322.1  288.29
  5336.3  288.42  5343.8  287.68  5372.2  289.85  5378.9  289.61  5494.1  292.09
#Mann=5,-1,0
  4578.2    0.05       0  5025.8    0.03       0  5029.8    0.05       0
  5034.9     0.1       0  5219.5    0.05       0
Bank Sta=5025.8,5029.8
Exp/Cntr=0.3,0.1

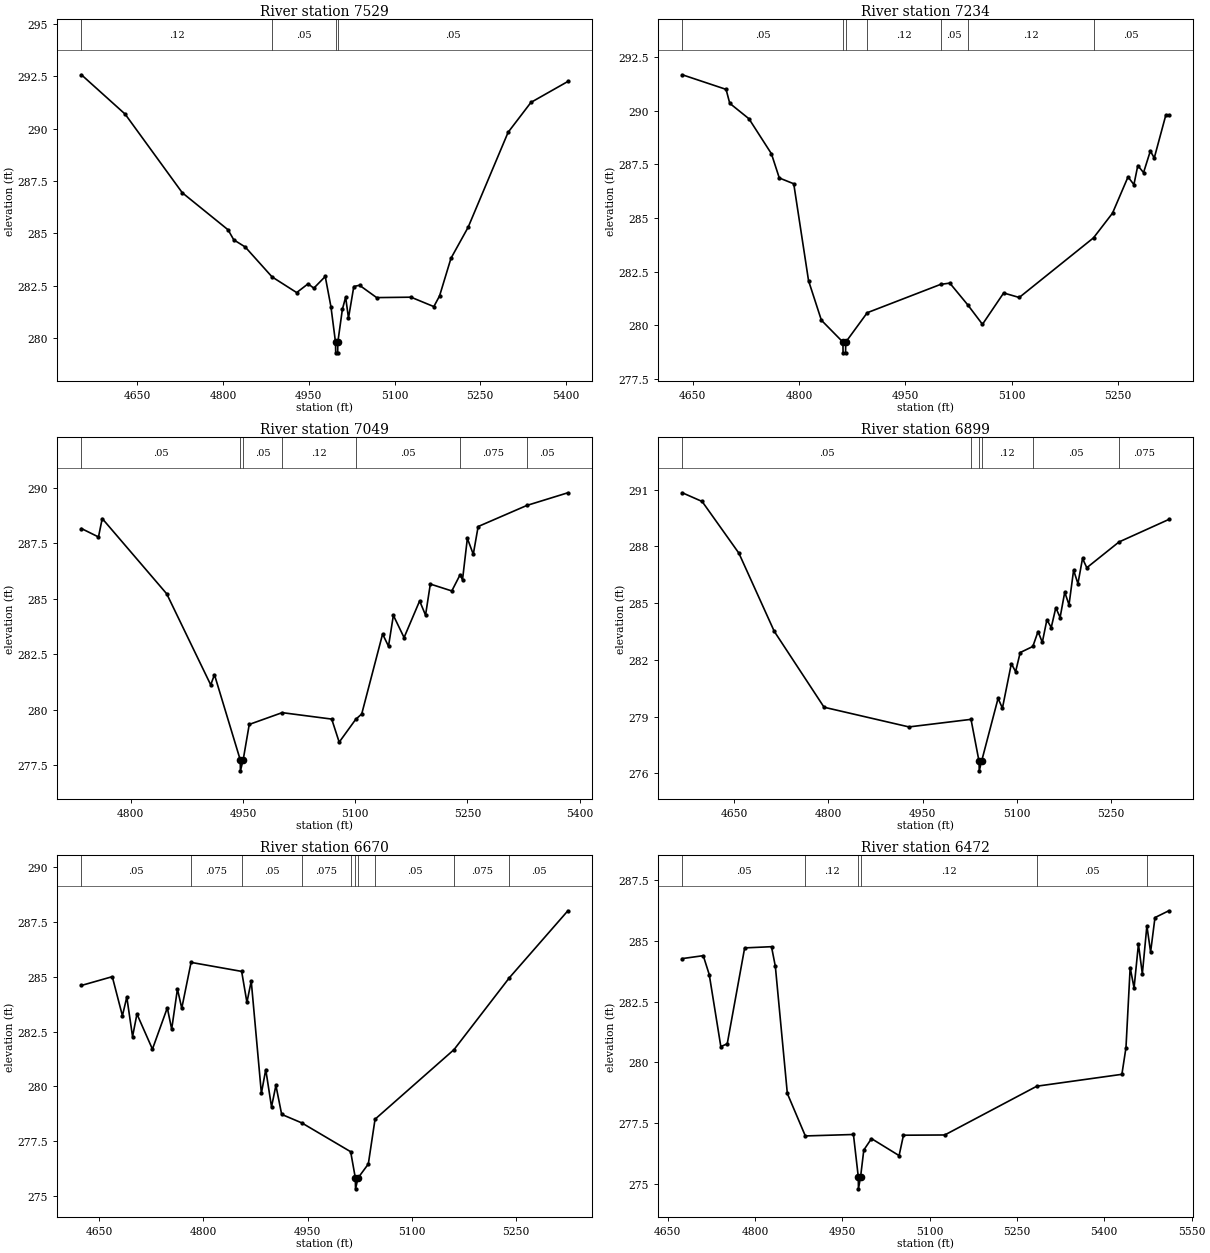
Type RM Length L Ch R = 1,7529,295,295,295
BEGIN DESCRIPTION:
Walnut44 15.8
END DESCRIPTION:
XS GIS Cut Line= 3
      2716827.68      6747307.44      2716809.98      6746895.18
      2716818.83      6746456.41
#Sta/Elev= 30
  4551.9  292.58  4628.4  290.70  4728.5  286.94  4808.6  285.17  4818.6  284.69
  4838.6  284.35  4885.6  282.92  4928.7  282.17  4948.7  282.59  4958.7  282.38
  4978.7  282.94  4988.7  281.49  4996.7  279.79  4997.0  279.29  5000.5  279.29
  5000.7  279.79  5008.7  281.37  5014.4  281.95  5019.4  280.95  5028.7  282.46
  5038.7  282.52  5068.7  281.93  5128.8  281.95  5168.8  281.50  5178.8  282.01
  5198.8  283.81  5228.8  285.29  5298.8  289.83  5338.8  291.26  5403.4  292.26
#Mann=4,-1,0
  4551.9    0.12       0  4885.6    0.05       0  4996.7    0.03       0
  5000.7    0.05       0
Bank Sta=4996.7,5000.7
Exp/Cntr=0.3,0.1

Type RM Length L Ch R = 1,7234,185,185,185
BEGIN DESCRIPTION:
Walnut44 15.0
END DESCRIPTION:
XS GIS Cut Line= 3
      2717140.85      6747050.85      2717022.31      6746675.77
      2716901.99      6746408.58
#Sta/Elev= 30
  4635.3  291.68  4697.0  291.00  4702.2  290.35  4729.3  289.63  4761.0  288.00
  4772.1  286.87  4792.5  286.60  4813.4  282.08  4831.5  280.24  4861.9  279.22
  4862.1  278.72  4865.6  278.72  4865.9  279.22  4896.2  280.59  4999.7  281.91
  5012.7  281.97  5037.7  280.97  5058.8  280.05  5088.7  281.51  5110.7  281.30
  5215.5  284.08  5242.3  285.23  5264.2  286.92  5272.5  286.56  5278.0  287.45
  5286.1  287.12  5295.7  288.13  5301.2  287.80  5317.6  289.81  5321.7  289.81
#Mann=7,-1,0
  4635.3    0.05       0  4861.9    0.05       0  4865.9    0.05       0
  4896.2    0.12       0  4999.7    0.05       0  5037.7    0.12       0
  5215.5    0.05       0
Bank Sta=4861.9,4865.9
Exp/Cntr=0.3,0.1

Type RM Length L Ch R = 1,7049,150,150,150
BEGIN DESCRIPTION:
Walnut44 14.0
END DESCRIPTION:
XS GIS Cut Line= 3
      2717202.79      6746974.76      2717176.25      6746578.45
      2716981.51      6746417.11
#Sta/Elev= 30
  4734.1  288.16  4756.9  287.78  4761.9  288.61  4848.1  285.22  4906.9  281.12
  4911.9  281.58  4946.3  277.75  4946.6  277.25  4950.3  277.75  4958.4  279.34
  5002.4  279.87  5068.6  279.58  5078.6  278.54  5100.7  279.57  5108.7  279.81
  5136.6  283.41  5144.5  282.86  5151.0  284.25  5165.3  283.25  5186.1  284.90
  5194.0  284.26  5200.4  285.66  5229.1  285.35  5240.2  286.08  5243.4  285.85
  5249.9  287.72  5257.8  287.00  5264.3  288.25  5329.4  289.20  5384.2  289.77
#Mann=7,-1,0
  4734.1    0.05       0  4946.3    0.04       0  4950.3    0.05       0
  5002.4    0.12       0  5100.7    0.05       0  5240.2   0.075       0
  5329.4    0.05       0
Bank Sta=4946.3,4950.3
Exp/Cntr=0.3,0.1

Type RM Length L Ch R = 1,6899,229,229,229
BEGIN DESCRIPTION:
Walnut44 13.2
END DESCRIPTION:
XS GIS Cut Line= 3
      2717597.39      6747044.51      2717381.54      6746753.83
      2717100.26      6746452.46
#Sta/Elev= 30
  4567.7  290.83  4599.2  290.37  4657.7  287.64  4714.0  283.51  4793.3  279.50
  4928.4  278.46  5027.2  278.86  5040.0  276.64  5040.3  276.14  5044.0  276.64
  5070.3  279.97  5077.2  279.45  5091.4  281.80  5098.2  281.38  5105.5  282.39
  5125.6  282.71  5133.9  283.50  5140.7  282.93  5148.0  284.12  5154.9  283.71
  5162.2  284.76  5169.0  284.24  5176.4  285.58  5183.2  284.91  5190.5  286.74
  5197.4  286.03  5204.7  287.36  5211.5  286.87  5262.7  288.23  5342.0  289.42
#Mann=6,-1,0
  4567.7    0.05       0  5027.2    0.12       0  5040.0    0.05       0
  5044.0    0.12       0  5125.6    0.05       0  5262.7   0.075       0
Bank Sta=5040,5044
Exp/Cntr=0.3,0.1

Type RM Length L Ch R = 1,6670,198,198,198
BEGIN DESCRIPTION:
Walnut44 13.0
END DESCRIPTION:
XS GIS Cut Line= 3
      2717706.74      6746802.78      2717516.79      6746549.51
      2717174.34      6746376.85
#Sta/Elev= 30
  4624.6  284.60  4669.0  285.00  4683.6  283.22  4689.9  284.07  4698.2  282.27
  4704.5  283.30  4726.8  281.70  4748.2  283.58  4754.5  282.61  4762.8  284.44
  4769.0  283.56  4782.4  285.65  4855.2  285.24  4862.8  283.83  4869.0  284.80
  4883.6  279.69  4889.9  280.77  4898.2  279.07  4904.5  280.05  4912.8  278.73
  4941.9  278.34  5012.1  277.03  5018.8  275.84  5019.1  275.34  5022.8  275.84
  5037.5  276.47  5047.2  278.51  5160.9  281.68  5240.5  284.95  5324.7  288.00
#Mann=10,-1,0
  4624.6    0.05       0  4782.4   0.075       0  4855.2    0.05       0
  4941.9   0.075       0  5012.1    0.12       0  5018.8    0.07       0
  5022.8    0.12       0  5047.2    0.05       0  5160.9   0.075       0
  5240.5    0.05       0
Bank Sta=5018.8,5022.8
Exp/Cntr=0.3,0.1

Type RM Length L Ch R = 1,6472,494,494,494
BEGIN DESCRIPTION:
Walnut44 12.0
END DESCRIPTION:
XS GIS Cut Line= 3
      2717738.37      6746825.75      2717652.04      6746486.20
      2717326.83      6746126.46
#Sta/Elev= 30
  4675.4  284.27  4711.3  284.39  4721.6  283.61  4741.5  280.64  4752.5  280.76
  4782.4  284.71  4828.5  284.76  4835.1  283.95  4855.7  278.71  4886.6  276.96
  4969.2  277.02  4977.5  275.28  4977.8  274.78  4981.5  275.28  4987.0  276.38
  5000.2  276.85  5047.6  276.15  5055.1  276.99  5126.0  277.00  5284.1  279.01
  5430.2  279.50  5437.2  280.60  5444.4  283.90  5451.1  283.06  5458.6  284.87
  5465.3  283.64  5473.1  285.62  5479.5  284.54  5487.0  285.96  5510.7  286.24
#Mann=6,-1,0
  4675.4    0.05       0  4886.6    0.12       0  4977.5    0.07       0
  4981.5    0.12       0  5284.1    0.05       0  5473.1    0.12       0
Bank Sta=4977.5,4981.5
Exp/Cntr=0.3,0.1

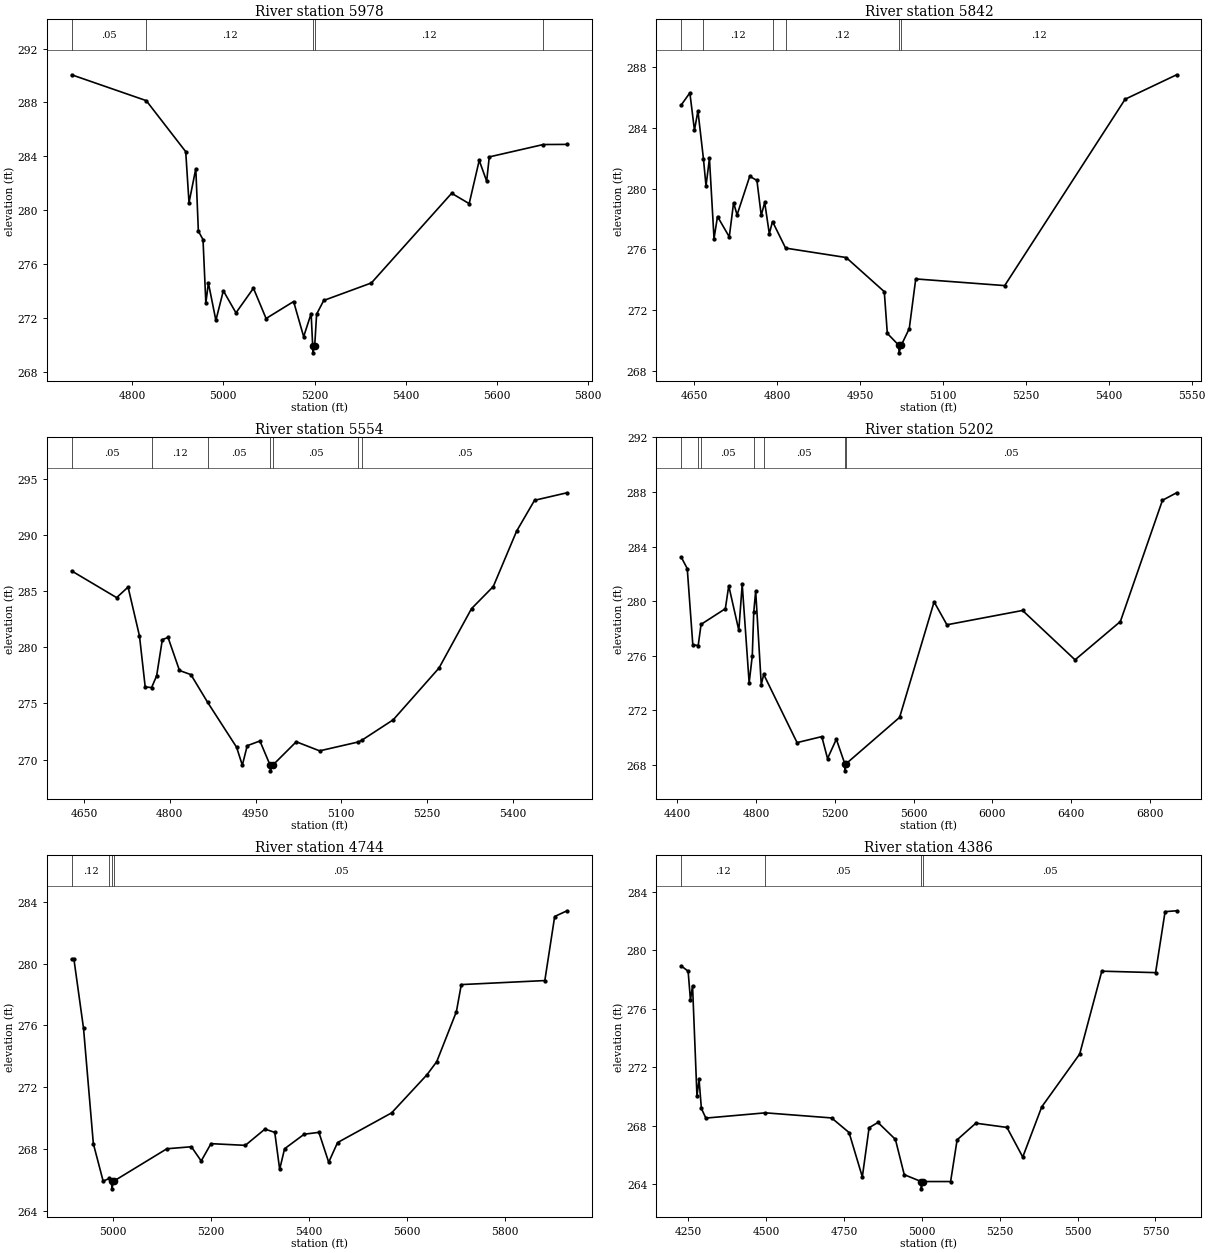
Type RM Length L Ch R = 1,5978,136,136,136
BEGIN DESCRIPTION:
Walnut44 11.2
END DESCRIPTION:
XS GIS Cut Line= 3
      2718319.66      6746750.94      2718138.37      6746561.02
      2717411.22      6746175.89
#Sta/Elev= 30
  4667.8  290.05  4831.3  288.13  4917.8  284.34  4925.0  280.55  4939.9  283.08
  4945.5  278.44  4955.7  277.81  4961.9  273.10  4967.5  274.59  4983.9  271.81
  5000.2  274.01  5027.9  272.37  5066.2  274.20  5093.9  271.95  5154.2  273.21
  5176.2  270.60  5192.6  272.32  5196.0  269.90  5196.4  269.40  5200.4  269.90
  5204.6  272.27  5220.2  273.29  5324.6  274.59  5500.5  281.25  5538.9  280.48
  5560.9  283.69  5577.2  282.15  5582.9  283.95  5701.3  284.87  5753.2  284.88
#Mann=5,-1,0
  4667.8    0.05       0  4831.3    0.12       0  5196.0    0.07       0
  5200.4    0.12       0  5701.3    0.05       0
Bank Sta=5196,5200.4
Exp/Cntr=0.3,0.1

Type RM Length L Ch R = 1,5842,288,288,288
BEGIN DESCRIPTION:
Walnut44 11.0
END DESCRIPTION:
XS GIS Cut Line= 3
      2718429.00      6746670.35      2718288.01      6746483.33
      2717686.55      6746207.05
#Sta/Elev= 30
  4626.7  285.52  4642.3  286.32  4650.6  283.86  4656.9  285.13  4666.9  281.96
  4671.5  280.18  4677.7  282.00  4686.0  276.72  4692.3  278.17  4713.6  276.83
  4721.4  279.08  4727.7  278.28  4750.6  280.82  4763.6  280.55  4771.4  278.25
  4777.7  279.10  4786.0  277.04  4791.8  277.84  4815.5  276.09  4925.0  275.47
  4994.0  273.22  4999.5  270.47  5020.2  269.69  5020.7  269.19  5024.7  269.69
  5039.2  270.79  5050.9  274.06  5211.8  273.62  5429.7  285.90  5522.8  287.51
#Mann=6,-1,0
  4626.7    0.05       0  4666.9    0.12       0  4791.8    0.05       0
  4815.5    0.12       0  5020.2    0.07       0  5024.7    0.12       0
Bank Sta=5020.2,5024.7
Exp/Cntr=0.3,0.1

Type RM Length L Ch R = 1,5554,352,352,352
BEGIN DESCRIPTION:
Walnut44 10.0
END DESCRIPTION:
XS GIS Cut Line= 3
      2718472.19      6746779.72      2718463.55      6746468.94
      2718302.41      6745936.60
#Sta/Elev= 30
  4628.1  286.81  4706.9  284.43  4726.9  285.37  4746.9  281.01  4756.9  276.47
  4768.1  276.42  4776.9  277.46  4786.9  280.69  4796.9  280.88  4816.9  277.94
  4836.9  277.57  4866.2  275.10  4916.9  271.10  4926.9  269.50  4935.5  271.24
  4957.7  271.66  4975.6  269.50  4976.1  269.00  4980.1  269.50  5021.3  271.59
  5062.2  270.78  5129.8  271.57  5136.2  271.73  5191.1  273.55  5271.2  278.16
  5328.1  283.45  5366.2  285.42  5407.0  290.35  5438.4  293.10  5495.2  293.77
#Mann=7,-1,0
  4628.1    0.05       0  4768.1    0.12       0  4866.2    0.05       0
  4975.6    0.04       0  4980.1    0.05       0  5129.8    0.12       0
  5136.2    0.05       0
Bank Sta=4975.6,4980.1
Exp/Cntr=0.3,0.1

Type RM Length L Ch R = 1,5202,458,458,458
BEGIN DESCRIPTION:
Walnut44 9.0
END DESCRIPTION:
XS GIS Cut Line= 3
      2718467.62      6747022.82      2718919.19      6746064.22
      2718673.59      6744630.24
#Sta/Elev= 30
  4420.8  283.22  4451.3  282.38  4479.6  276.79  4506.9  276.74  4521.4  278.29
  4644.7  279.44  4661.9  281.12  4713.0  277.86  4730.3  281.22  4765.5  274.00
  4781.4  275.98  4788.9  279.20  4798.7  280.73  4827.0  273.88  4839.5  274.62
  5008.7  269.62  5134.3  270.06  5163.4  268.45  5208.1  269.87  5251.5  268.05
  5251.9  267.55  5256.0  268.05  5529.2  271.47  5704.3  279.94  5769.4  278.26
  6153.3  279.31  6419.8  275.69  6649.9  278.50  6863.5  287.39  6935.3  287.94
#Mann=7,-1,0
  4420.8    0.05       0  4506.9    0.12       0  4521.4    0.05       0
  4788.9    0.12       0  4839.5    0.05       0  5251.5    0.04       0
  5256.0    0.05       0
Bank Sta=5251.5,5256
Exp/Cntr=0.3,0.1

Type RM Length L Ch R = 1,4744,358,358,358
BEGIN DESCRIPTION:
Walnut44 7.0
END DESCRIPTION:
XS GIS Cut Line= 3
      2719018.90      6746845.34      2719023.45      6746299.73
      2719055.28      6745835.95
#Sta/Elev= 30
  4916.2  280.28  4920.9  280.28  4940.5  275.81  4960.5  268.36  4980.5  265.94
  4993.3  266.11  4997.8  265.94  4998.2  265.44  5002.3  265.94  5110.5  268.03
  5160.5  268.16  5180.5  267.24  5200.5  268.36  5270.5  268.25  5310.5  269.30
  5330.6  269.09  5340.6  266.70  5350.6  268.03  5390.6  268.97  5420.6  269.09
  5440.6  267.16  5458.7  268.43  5569.0  270.35  5641.0  272.81  5661.0  273.66
  5701.1  276.89  5711.1  278.64  5881.5  278.90  5901.6  283.04  5926.7  283.41
#Mann=4,-1,0
  4916.2    0.12       0  4993.3    0.05       0  4997.8    0.04       0
  5002.3    0.05       0
Bank Sta=4997.8,5002.3
Exp/Cntr=0.3,0.1

Type RM Length L Ch R = 1,4386,415,415,415
BEGIN DESCRIPTION:
Walnut44 6.0
END DESCRIPTION:
XS GIS Cut Line= 3
      2719814.63      6747163.67      2719205.32      6746477.06
      2719087.34      6745814.57
#Sta/Elev= 30
  4227.2  278.94  4249.3  278.58  4256.8  276.60  4263.5  277.59  4277.7  270.02
  4284.4  271.16  4291.9  269.17  4306.2  268.51  4497.5  268.87  4710.1  268.52
  4766.1  267.52  4808.8  264.48  4830.5  267.85  4859.0  268.21  4915.0  267.05
  4943.4  264.63  4997.8  264.16  4998.2  263.66  5002.3  264.16  5092.3  264.16
  5113.2  267.02  5173.3  268.16  5273.2  267.87  5324.0  265.84  5385.0  269.28
  5506.8  272.90  5577.9  278.58  5750.6  278.48  5781.1  282.66  5818.1  282.72
#Mann=4,-1,0
  4227.2    0.12       0  4497.5    0.05       0  4997.8    0.03       0
  5002.3    0.05       0
Bank Sta=4997.8,5002.3
Exp/Cntr=0.3,0.1