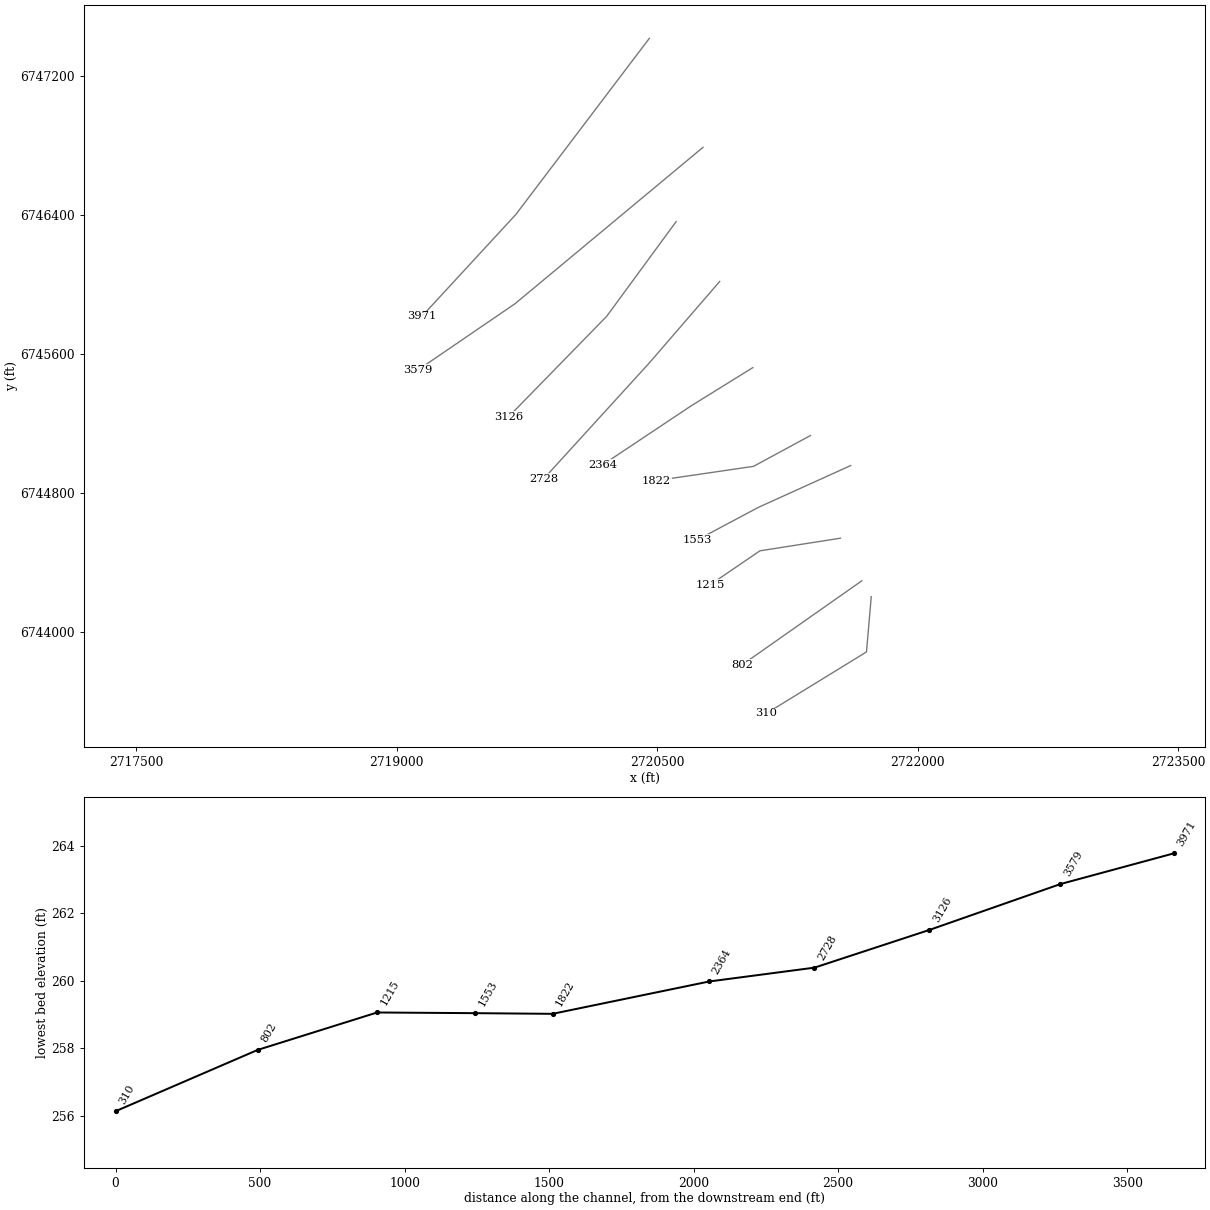
HEC-RAS study Walnut44.prj: Walnut44 Base Level Engineering

--- Walnut44.g01 (geometry) --- (continued)

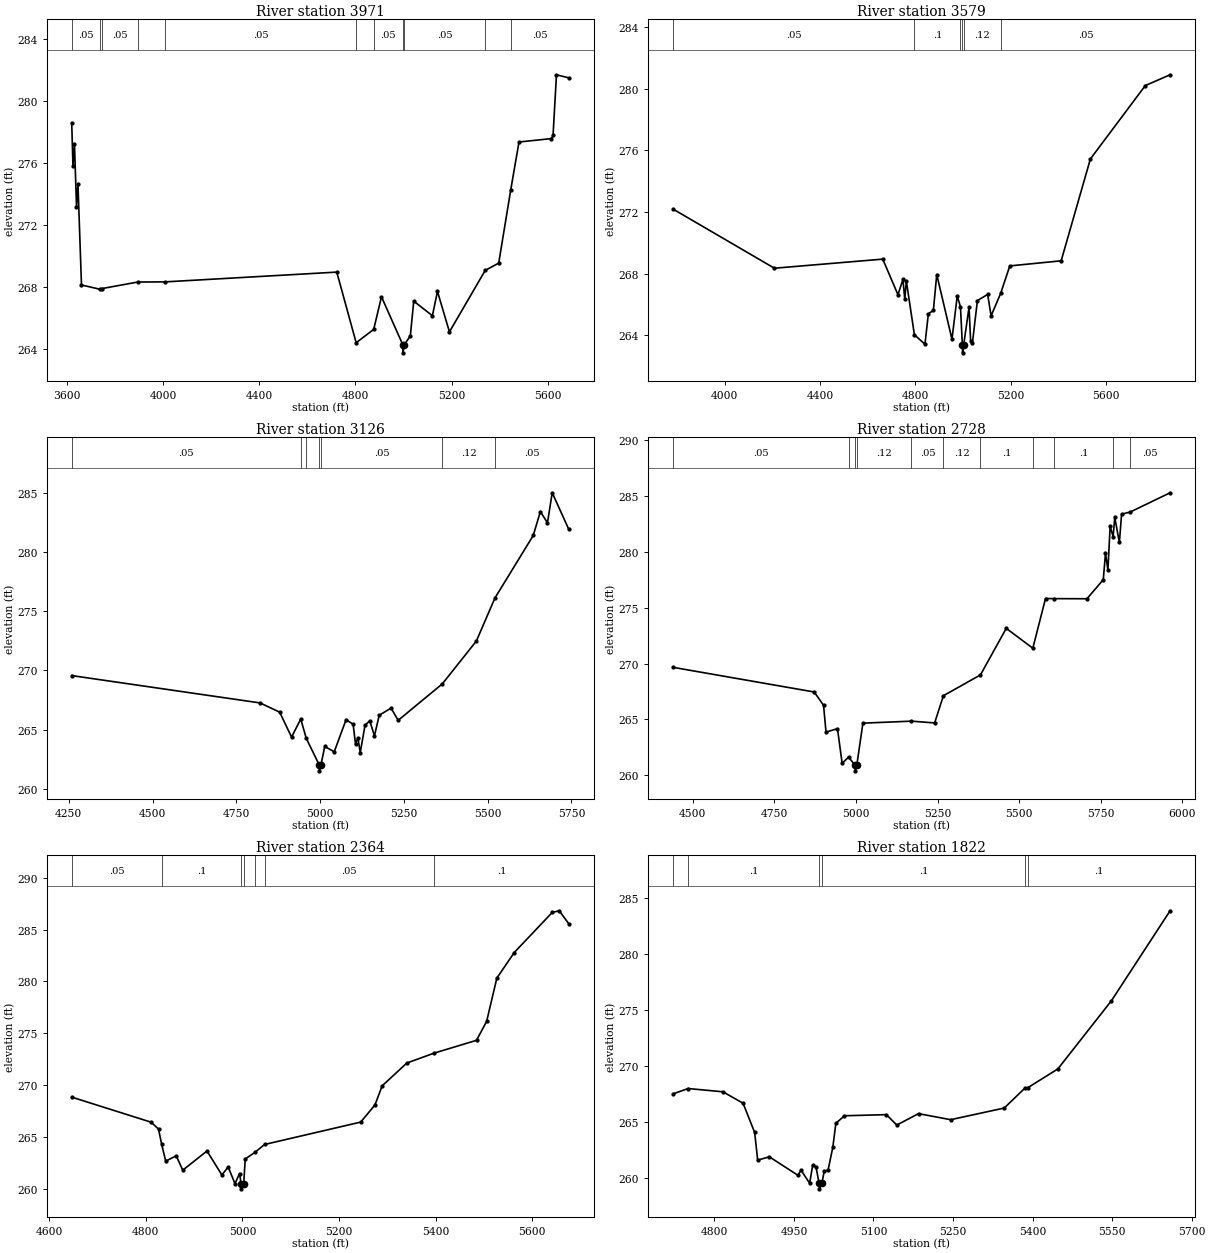
Type RM Length L Ch R = 1,3971,392,392,392
BEGIN DESCRIPTION:
Walnut44 5.0
END DESCRIPTION:
XS GIS Cut Line= 3
      2720455.71      6747418.27      2719687.29      6746404.31
      2719146.23      6745817.79
#Sta/Elev= 30
  3618.4  278.60  3623.7  275.80  3630.0  277.22  3638.3  273.20  3644.5  274.63
  3659.1  268.15  3735.1  267.88  3744.3  267.92  3893.6  268.34  4006.9  268.35
  4722.2  268.98  4802.9  264.43  4875.9  265.29  4908.3  267.39  4997.7  264.28
  4998.2  263.78  5002.3  264.28  5028.5  264.87  5042.7  267.11  5120.4  266.17
  5141.4  267.74  5191.3  265.13  5340.3  269.09  5396.5  269.56  5446.4  274.26
  5481.0  277.36  5616.0  277.58  5622.8  277.78  5637.0  281.69  5688.6  281.49
#Mann=11,-1,0
  3618.4    0.05       0  3735.1    0.12       0  3744.3    0.05       0
  3893.6    0.12       0  4006.9    0.05       0  4802.9     0.1       0
  4875.9    0.05       0  4997.7    0.05       0  5002.3    0.05       0
  5340.3    0.12       0  5446.4    0.05       0
Bank Sta=4997.7,5002.3
Exp/Cntr=0.3,0.1

Type RM Length L Ch R = 1,3579,453,453,453
BEGIN DESCRIPTION:
Walnut44 4.5
END DESCRIPTION:
XS GIS Cut Line= 3
      2720764.90      6746790.80      2719682.74      6745890.52
      2719123.50      6745508.60
#Sta/Elev= 30
  3783.5  272.20  4209.0  268.36  4663.4  268.95  4727.2  266.64  4748.0  267.63
  4755.8  266.34  4762.3  267.54  4796.1  264.04  4840.4  263.43  4854.7  265.41
  4875.6  265.62  4889.9  267.95  4953.7  263.75  4975.8  266.56  4989.3  265.86
  4997.4  263.37  4998.1  262.87  5002.6  263.37  5025.3  265.83  5031.8  263.66
  5039.6  263.54  5060.4  266.26  5103.4  266.66  5117.7  265.27  5158.0  266.73
  5196.2  268.51  5411.6  268.84  5534.2  275.45  5764.5  280.21  5868.4  280.91
#Mann=6,-1,0
  3783.5    0.05       0  4796.1     0.1       0  4989.3    0.12       0
  4997.4    0.07       0  5002.6    0.12       0  5158.0    0.05       0
Bank Sta=4997.4,5002.6
Exp/Cntr=0.3,0.1

Type RM Length L Ch R = 1,3126,398,398,398
BEGIN DESCRIPTION:
Walnut44 4.0
END DESCRIPTION:
XS GIS Cut Line= 3
      2720610.28      6746363.37      2720210.17      6745817.77
      2719646.39      6745240.34
#Sta/Elev= 30
  4258.8  269.56  4820.8  267.25  4879.4  266.47  4914.9  264.36  4942.3  265.89
  4958.6  264.27  4997.4  262.01  4998.1  261.51  5002.6  262.01  5013.9  263.57
  5042.2  263.12  5077.5  265.83  5098.6  265.45  5105.8  263.77  5112.8  264.31
  5119.9  263.05  5134.1  265.36  5148.2  265.74  5162.3  264.47  5176.5  266.21
  5211.8  266.81  5233.1  265.78  5364.8  268.86  5466.4  272.48  5521.9  276.12
  5636.1  281.40  5657.4  283.42  5678.6  282.47  5692.7  285.01  5742.4  281.91
#Mann=7,-1,0
  4258.8    0.05       0  4942.3    0.12       0  4958.6    0.05       0
  4997.4    0.04       0  5002.6    0.05       0  5364.8    0.12       0
  5521.9    0.05       0
Bank Sta=4997.4,5002.6
Exp/Cntr=0.3,0.1

Type RM Length L Ch R = 1,2728,364,364,364
BEGIN DESCRIPTION:
Walnut44 3.5
END DESCRIPTION:
XS GIS Cut Line= 3
      2720860.39      6746017.86      2720455.70      6745549.50
      2719846.42      6744881.11
#Sta/Elev= 30
  4439.3  269.66  4872.3  267.45  4900.8  266.26  4908.4  263.86  4943.5  264.17
  4957.8  261.06  4977.5  261.62  4997.4  260.89  4998.1  260.39  5002.7  260.89
  5021.4  264.66  5170.2  264.84  5241.2  264.68  5268.2  267.12  5381.6  268.98
  5460.7  273.15  5542.1  271.37  5581.0  275.82  5608.1  275.81  5708.0  275.80
  5758.0  277.51  5764.8  279.87  5772.2  278.39  5779.0  282.28  5788.1  281.37
  5793.2  283.09  5807.3  280.84  5814.1  283.37  5840.7  283.57  5962.7  285.29
#Mann=11,-1,0
  4439.3    0.05       0  4977.5    0.12       0  4997.4    0.07       0
  5002.7    0.12       0  5170.2    0.05       0  5268.2    0.12       0
  5381.6     0.1       0  5542.1    0.12       0  5608.1     0.1       0
  5788.1    0.12       0  5840.7    0.05       0
Bank Sta=4997.4,5002.7
Exp/Cntr=0.3,0.1

Type RM Length L Ch R = 1,2364,542,542,542
BEGIN DESCRIPTION:
Walnut44 3.0
END DESCRIPTION:
XS GIS Cut Line= 3
      2721051.35      6745522.23      2720692.14      6745299.43
      2720187.42      6744962.95
#Sta/Elev= 30
  4646.6  268.83  4811.0  266.41  4826.3  265.75  4832.6  264.33  4841.2  262.65
  4863.0  263.17  4876.5  261.78  4926.7  263.63  4957.5  261.32  4970.6  262.09
  4984.6  260.48  4994.1  261.46  4997.3  260.48  4998.1  259.98  5002.7  260.48
  5005.9  262.86  5025.9  263.50  5045.9  264.26  5244.9  266.42  5274.4  268.07
  5289.4  269.92  5340.5  272.12  5396.6  273.07  5484.7  274.31  5505.7  276.14
  5526.8  280.31  5562.8  282.78  5641.5  286.65  5656.0  286.81  5675.9  285.55
#Mann=7,-1,0
  4646.6    0.05       0  4832.6     0.1       0  4997.3    0.07       0
  5002.7     0.1       0  5025.9    0.12       0  5045.9    0.05       0
  5396.6     0.1       0
Bank Sta=4997.3,5002.7
Exp/Cntr=0.3,0.1

Type RM Length L Ch R = 1,1822,269,269,269
BEGIN DESCRIPTION:
Walnut44 2.5
END DESCRIPTION:
XS GIS Cut Line= 3
      2721383.23      6745131.18      2721055.89      6744953.87
      2720496.62      6744872.02
#Sta/Elev= 30
  4721.8  267.49  4750.5  267.97  4816.0  267.68  4854.0  266.66  4875.9  264.05
  4881.6  261.58  4903.5  261.88  4957.5  260.23  4963.4  260.68  4979.6  259.52
  4985.3  261.12  4991.6  261.00  4997.3  259.52  4998.1  259.02  5002.7  259.52
  5007.1  260.60  5014.3  260.68  5023.3  262.73  5029.0  264.86  5045.2  265.54
  5124.3  265.64  5143.9  264.71  5184.9  265.73  5245.6  265.19  5346.6  266.23
  5385.6  268.01  5391.6  268.06  5447.7  269.72  5548.8  275.81  5659.3  283.83
#Mann=6,-1,0
  4721.8    0.12       0  4750.5     0.1       0  4997.3    0.07       0
  5002.7     0.1       0  5385.6    0.05       0  5391.6     0.1       0
Bank Sta=4997.3,5002.7
Exp/Cntr=0.3,0.1

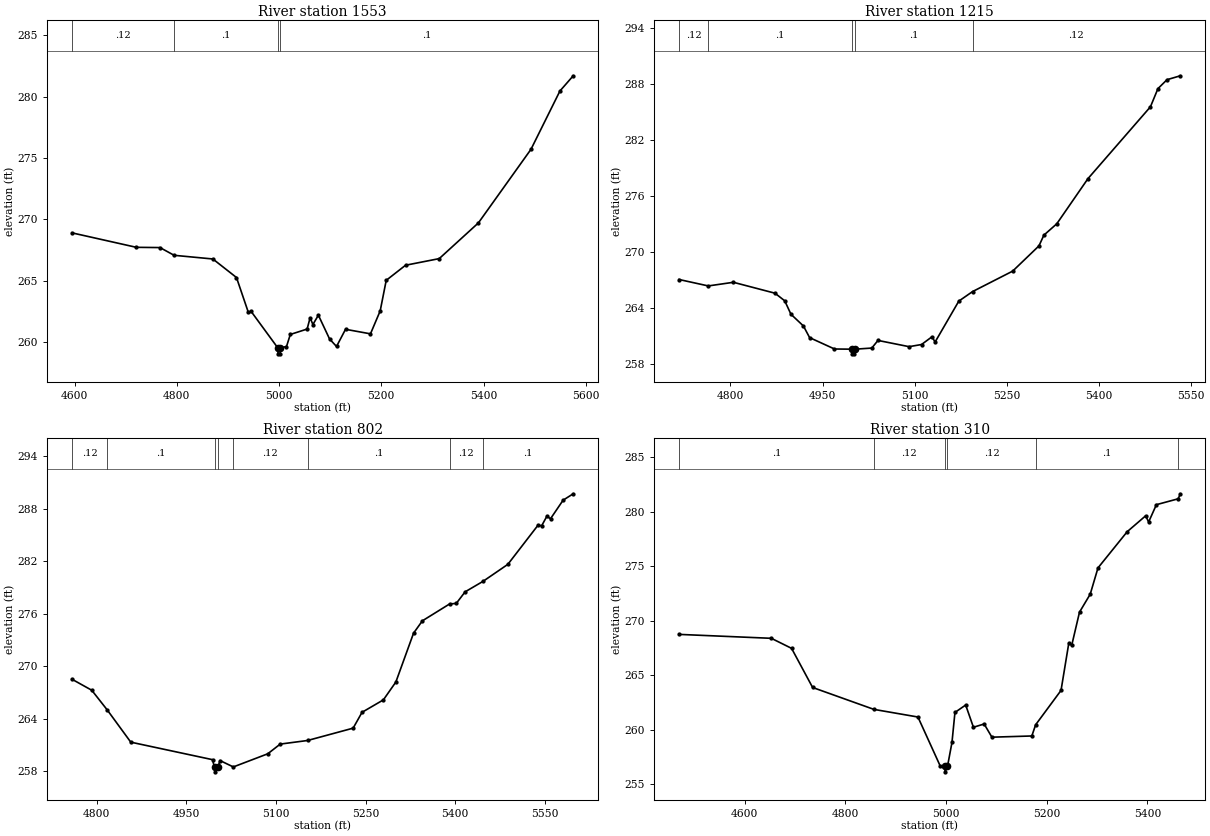
Type RM Length L Ch R = 1,1553,338,338,338
BEGIN DESCRIPTION:
Walnut44 2.0
END DESCRIPTION:
XS GIS Cut Line= 3
      2721615.11      6744958.40      2721083.17      6744717.43
      2720733.08      6744531.02
#Sta/Elev= 30
  4594.8  268.90  4720.9  267.72  4767.1  267.70  4794.7  267.07  4870.5  266.77
  4916.7  265.26  4939.8  262.43  4945.3  262.50  4997.3  259.54  4998.1  259.04
  5002.0  259.04  5002.7  259.54  5014.5  259.63  5022.0  260.62  5054.9  261.06
  5060.7  261.98  5066.2  261.43  5076.9  262.19  5098.8  260.25  5112.4  259.64
  5130.0  261.04  5178.8  260.67  5197.8  262.54  5209.6  265.03  5247.4  266.26
  5313.3  266.80  5389.9  269.71  5492.8  275.71  5549.4  280.46  5575.4  281.70
#Mann=4,-1,0
  4594.8    0.12       0  4794.7     0.1       0  4997.3    0.07       0
  5002.7     0.1       0
Bank Sta=4997.3,5002.7
Exp/Cntr=0.3,0.1

Type RM Length L Ch R = 1,1215,413,413,413
BEGIN DESCRIPTION:
Walnut44 1.6
END DESCRIPTION:
XS GIS Cut Line= 3
      2721556.02      6744540.10      2721092.26      6744467.36
      2720805.85      6744271.87
#Sta/Elev= 30
  4716.4  267.04  4764.0  266.35  4804.9  266.74  4872.6  265.57  4888.5  264.75
  4898.6  263.31  4918.9  262.05  4929.0  260.80  4969.5  259.58  4997.3  259.56
  4998.1  259.06  5002.0  259.06  5002.8  259.56  5030.2  259.68  5040.3  260.50
  5090.9  259.83  5111.2  260.06  5128.2  260.89  5133.3  260.33  5171.9  264.72
  5194.2  265.74  5259.6  267.94  5302.4  270.65  5310.4  271.80  5331.4  273.02
  5382.2  277.87  5483.9  285.58  5496.1  287.53  5510.9  288.49  5532.6  288.91
#Mann=5,-1,0
  4716.4    0.12       0  4764.0     0.1       0  4997.3    0.07       0
  5002.8     0.1       0  5194.2    0.12       0
Bank Sta=4997.3,5002.8
Exp/Cntr=0.3,0.1

Type RM Length L Ch R = 1,802,492,492,492
BEGIN DESCRIPTION:
Walnut44 1.3
END DESCRIPTION:
XS GIS Cut Line= 2
      2721678.82      6744294.58      2720992.20      6743812.59
#Sta/Elev= 30
  4758.6  268.53  4791.8  267.27  4817.6  265.03  4857.1  261.34  4993.9  259.34
  4997.2  258.45  4998.1  257.95  5002.8  258.45  5006.4  259.24  5028.7  258.51
  5086.3  260.01  5107.2  261.12  5152.9  261.53  5229.2  262.94  5244.1  264.75
  5279.8  266.17  5300.7  268.21  5330.3  273.79  5345.1  275.20  5390.5  277.12
  5401.8  277.19  5416.6  278.51  5446.6  279.71  5488.1  281.65  5538.6  286.12
  5544.7  286.06  5553.4  287.14  5559.5  286.86  5580.6  288.98  5597.5  289.71
#Mann=8,-1,0
  4758.6    0.12       0  4817.6     0.1       0  4997.2    0.07       0
  5002.8     0.1       0  5028.7    0.12       0  5152.9     0.1       0
  5390.5    0.12       0  5446.6     0.1       0
Bank Sta=4997.2,5002.8
Exp/Cntr=0.3,0.1

Type RM Length L Ch R = 1,310,0,0,0
BEGIN DESCRIPTION:
Walnut44 1.0
END DESCRIPTION:
XS GIS Cut Line= 3
      2721733.37      6744203.66      2721706.08      6743885.36
      2721129.85      6743531.45
#Sta/Elev= 30
  4469.6  268.74  4652.9  268.38  4693.1  267.46  4734.9  263.87  4856.6  261.86
  4944.1  261.16  4988.7  256.63  4997.2  256.63  4998.1  256.13  5002.8  256.63
  5011.7  258.83  5017.6  261.58  5038.9  262.26  5054.3  260.22  5075.6  260.52
  5091.0  259.31  5170.3  259.42  5177.9  260.45  5228.3  263.60  5243.7  267.93
  5249.6  267.75  5265.0  270.78  5286.3  272.43  5301.7  274.84  5359.7  278.16
  5396.4  279.62  5402.3  279.05  5417.7  280.64  5461.0  281.18  5465.3  281.64
#Mann=6,-1,0
  4469.6     0.1       0  4856.6    0.12       0  4997.2    0.07       0
  5002.8    0.12       0  5177.9     0.1       0  5461.0    0.12       0
Bank Sta=4997.2,5002.8
Exp/Cntr=0.3,0.1

Chan Stop Cuts=-1