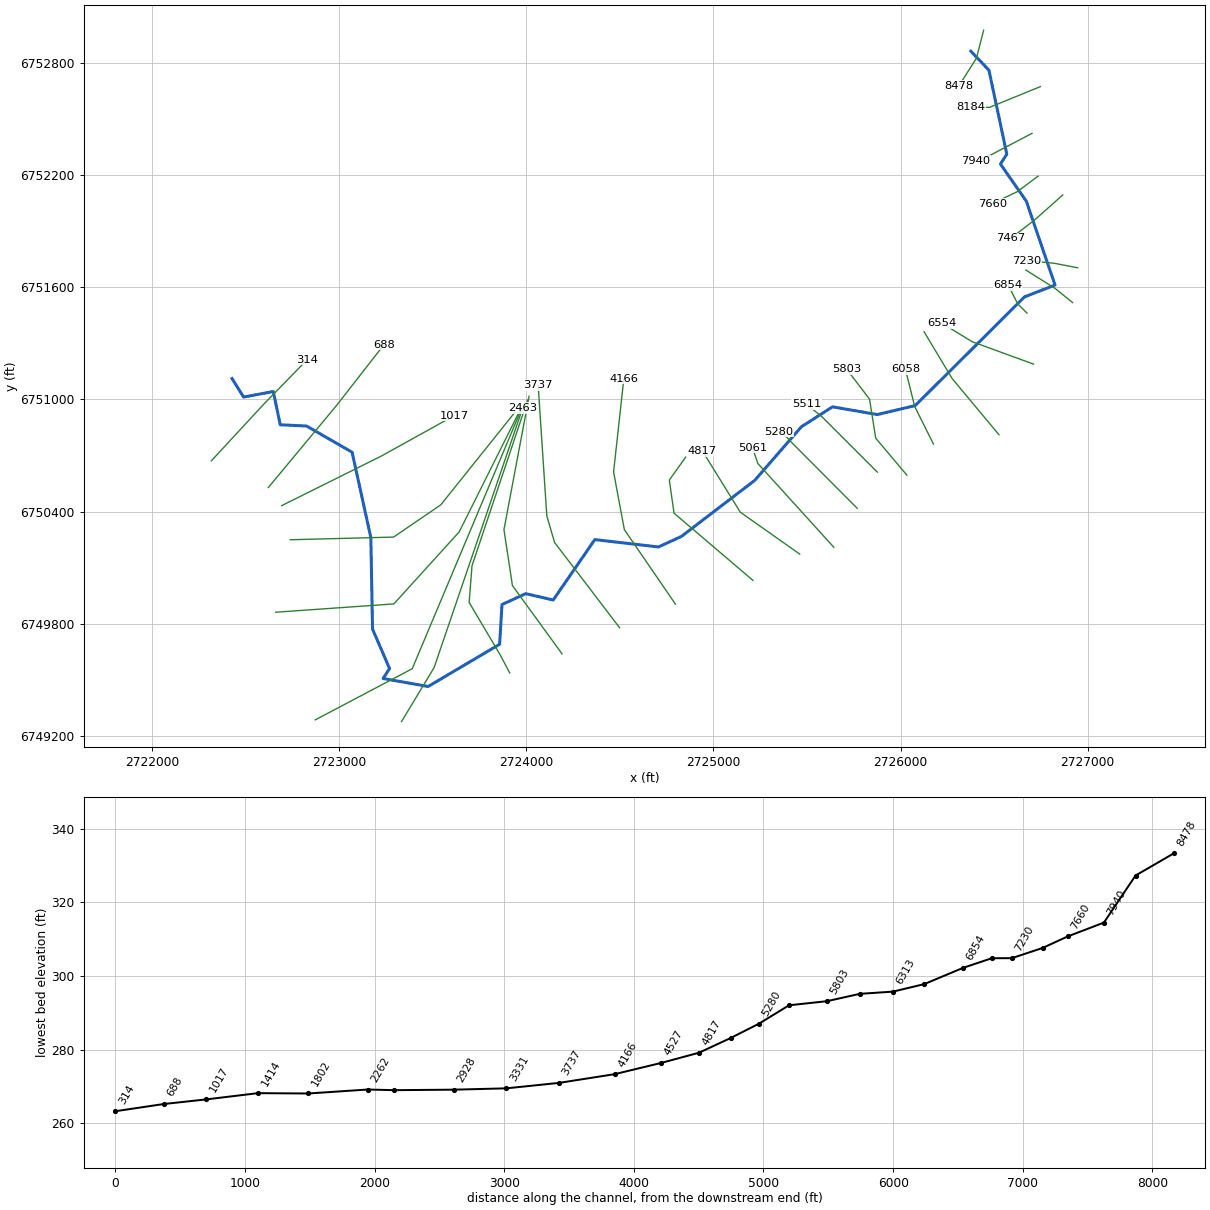
--- Walnut46.prj (project) ---

Proj Title=Walnut46 Base Level Engineering
Current Plan=p01
Default Exp/Contr=0.3,0.1
English Units
Geom File=g01
Flow File=f01
Plan File=p01
Y Axis Title=Elevation
X Axis Title(PF)=Main Channel Distance
X Axis Title(XS)=Station
BEGIN DESCRIPTION:
Walnut46
END DESCRIPTION:
DSS Export Rating Curves= 0
DSS Export Rating Curve Sorted= 0
DSS Export Volume Flow Curves= 0
DXF OffsetX= 0
DXF OffsetY= 0
DXF ScaleX= 1
DXF ScaleY= 10

--- Walnut46.p01 (plan) ---

Plan Title=Multiple Run
Program Version=4.10
Short Identifier=Multiple
Geom File=g01
Flow File=f01
Subcritical Flow
K Sum by GR= 0
Std Step Tol= 0.01
Critical Tol= 0.01
Num of Std Step Trials= 20
Max Error Tol= 0.3
Flow Tol Ratio= 0.001
Split Flow NTrial= 30
Split Flow Tol= 0.02
Split Flow Ratio= 0.02
Log Output Level= 0
Friction Slope Method= 1
Unsteady Friction Slope Method= 2
Unsteady Bridges Friction Slope Method= 1
Parabolic Critical Depth
Global Vel Dist= 1 , 1 , 1
Global Log Level= 0
CheckData=True
Encroach Param=-1 ,0,0, 0
BEGIN DESCRIPTION:
Multiple Run
END DESCRIPTION:
Computation Interval=1HOUR
Output Interval=1HOUR
Run HTab= 0
Run UNet= 0
Run PostProcess= 0
Run WQNet= 0
UNET Theta= 1
UNET Theta Warmup= 1
UNET ZTol= 0.02
UNET ZSATol= 0.05
UNET MxIter= 20
UNET MaxInSteps= 0
UNET DtIC= 0
UNET DtMin= 0
UNET MaxCRTS= 20
UNET WFStab= 2
UNET SFStab= 1
UNET WFX= 1
UNET SFX= 1
UNET DSS MLevel= 4
UNET DZMax Abort= 100
UNET Convert EG Bridges= 0
UNET Use Existing IB Tables=-1
UNET Froude Reduction=False
UNET Froude Limit= 1
UNET Froude Power= 10
UNET Time Slicing=0,0, 5
UNET Junction Losses=0
Instantaneous Interval=1HOUR
Write IC File= 0
Write IC File at Sim End=0
Echo Input=False
Echo Parameters=False
Echo Output=False
Write Detailed= 0
WQ AD Non Conservative
WQ ULTIMATE=-1
WQ Max Comp Step=1HOUR
WQ Output Interval=15MIN
WQ Output Selected Increments= 0
WQ Output face flow=0
WQ Output face velocity=0
WQ Output face area=0
WQ Output face dispersion=0
WQ Output cell volume=0
WQ Output cell surface area=0
WQ Output cell continuity=0
WQ Output cumulative cell continuity=0
WQ Output face conc=0
WQ Output face dconc_dx=0
WQ Output face courant=0
WQ Output face peclet=0
WQ Output face adv mass=0
WQ Output face disp mass=0
WQ Output cell mass=0
WQ Output cell source sink temp=0
WQ Output cell source sink nsm=0
WQ Output MaxMinRange=-1
WQ Daily Max Min Mean=-1
WQ Daily Range=0
WQ Daily Time=0
WQ Create Restart=0
WQ Fixed Restart=0
WQ System Summary=0
WQ Use Fixed Temperature=0
Sorting and Armoring Iterations= 10
XS Update Threshold= 0.02
Hydraulics Update Threshold= 0.02
Energy Slope Method= 1
Volume Change Method= 0
XS Weighting Method= 0
Number of US Weighted Cross Sections= 1
Number of DS Weighted Cross Sections= 1
Upstream XS Weight=0.25
Main XS Weight=0.5
Downstream XS Weight=0.25
Number of DS XS's Weighted with US Boundary= 1
Upstream Boundary Weight= 1
Weight of XSs Associated with US Boundary= 0
Number of US XS's Weighted with DS Boundary= 1
Downstream Boundary Weight= 0.5
Weight of XSs Associated with DS Boundary= 0.5
Sediment Output Level= 4
Mass or Volume Output= 0
Output Increment Type= 1
Profile and TS Output Increment= 10
XS Output Flag= 0
XS Output Increment= 10
Disregard all LS=0
Disregard all Conn=0
Disregard all Breaches=0
Disregard all Pumps=0

--- Walnut46.f01 (steady flow) ---

Flow Title=Multiple
Number of Profiles=7
Profile Names=10-year,25-year,50-year,1pct_min,100-year,1pct_plu,500-year
River Rch & RM= Walnut46,Reach-1,8478
     107     130     147      84     167     334     214
River Rch & RM= Walnut46,Reach-1,7075
     180     224     258     148     296     590     388
River Rch & RM= Walnut46,Reach-1,2928
     350     450     528     308     614    1226     829
Boundary for River Rch & Prof#=Walnut46,Reach-1,1
Up Type=0
Dn Type=3
Dn Slope=0.005
Boundary for River Rch & Prof#=Walnut46,Reach-1,2
Up Type=0
Dn Type=3
Dn Slope=0.005
Boundary for River Rch & Prof#=Walnut46,Reach-1,3
Up Type=0
Dn Type=3
Dn Slope=0.005
Boundary for River Rch & Prof#=Walnut46,Reach-1,4
Up Type=0
Dn Type=3
Dn Slope=0.005
Boundary for River Rch & Prof#=Walnut46,Reach-1,5
Up Type=0
Dn Type=3
Dn Slope=0.005
Boundary for River Rch & Prof#=Walnut46,Reach-1,6
Up Type=0
Dn Type=3
Dn Slope=0.005
Boundary for River Rch & Prof#=Walnut46,Reach-1,7
Up Type=0
Dn Type=3
Dn Slope=0.005

--- Walnut46.g01 (geometry) ---

Geom Title=Existing Conditions
Program Version=4.10

River Reach=Walnut46        ,Reach-1
Reach XY= 30
        2726376.        6752861.      2726472.55      6752759.75
      2726568.21       6752310.9      2726534.24      6752257.77
      2726672.38       6752059.5        2726826.        6751611.
      2726662.69       6751547.6      2726078.44      6750966.48
        2725876.      6750918.56      2725636.44      6750959.95
      2725469.67      6750852.96      2725220.39       6750566.6
       2724828.3      6750266.83       2724705.8      6750210.78
      2724365.62      6750250.03      2724143.08      6749927.14
       2723996.1       6749961.1      2723869.32      6749902.86
      2723856.79      6749690.62      2723474.45      6749464.75
      2723233.87      6749507.38      2723268.19      6749560.89
      2723177.22       6749771.5      2723168.21       6750260.9
      2723067.98      6750717.34      2722824.44      6750857.24
      2722683.92      6750863.92      2722646.58      6751041.78
      2722487.91      6751012.05        2722426.        6751111.

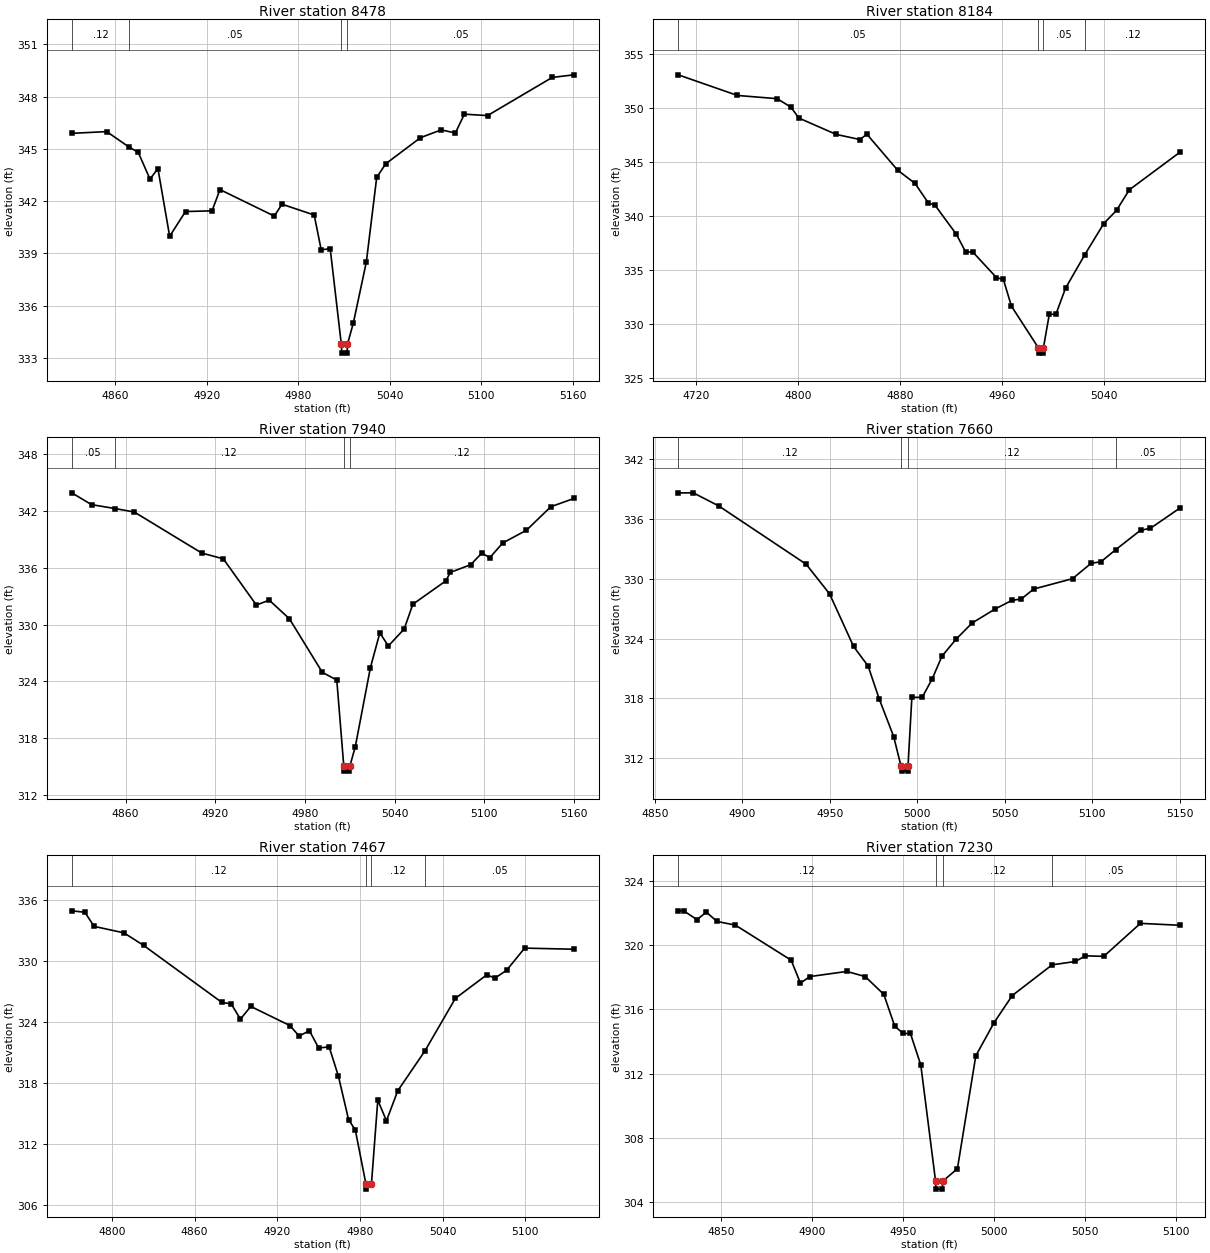
Type RM Length L Ch R = 1 ,8478    ,294,294,294
BEGIN DESCRIPTION:
Walnut46 19.0
END DESCRIPTION:
XS GIS Cut Line= 3
      2726444.41      6752973.22      2726405.95      6752823.65
      2726311.94      6752676.21
#Sta/Elev= 30
  4831.4  345.89  4854.3  345.99    4869   345.1    4875   344.8  4882.7  343.26
  4887.9  343.87  4895.6  339.98    4906   341.4  4923.4  341.44  4928.6  342.66
  4964.2  341.14  4969.3  341.82  4990.4   341.2    4995   339.2  5000.9  339.27
  5008.2  333.77  5008.5  333.27    5012  333.27  5012.2  333.77  5016.1  335.01
  5024.6   338.5  5031.4  343.36  5037.3  344.14  5060.1  345.64  5073.7  346.09
    5083  345.91  5088.9  346.99  5104.1  346.91  5146.5   349.1  5160.7  349.25
#Mann= 4 ,-1 , 0
  4831.4     .12       0    4869     .05       0  5008.2     .04       0
  5012.2     .05       0
Bank Sta=5008.2,5012.2
XS Rating Curve= 0 ,0
Exp/Cntr=0.3,0.1

Type RM Length L Ch R = 1 ,8184    ,244,244,244
BEGIN DESCRIPTION:
Walnut46 18.0
END DESCRIPTION:
XS GIS Cut Line= 3
      2726747.86      6752671.93        2726476.        6752561.
      2726376.02        6752561.
#Sta/Elev= 30
    4706  353.03  4752.4  351.12  4783.6  350.82  4794.4  350.03  4800.5  349.03
  4829.9  347.51  4848.4  347.04  4853.9  347.53    4878   344.2  4891.6  342.98
    4902  341.18  4907.4  340.94    4924  338.27  4931.4  336.61  4936.8  336.64
  4955.5  334.25  4960.9  334.08  4967.2  331.61  4988.3  327.76  4988.6  327.26
  4992.1  327.26  4992.3  327.76  4996.9  330.86  5002.1  330.86  5009.6  333.27
  5024.6  336.35  5039.6  339.26  5049.6  340.48  5059.6  342.38  5099.6  345.89
#Mann= 4 ,-1 , 0
    4706     .05       0  4988.3     .04       0  4992.3     .05       0
  5024.6     .12       0
Bank Sta=4988.3,4992.3
XS Rating Curve= 0 ,0
Exp/Cntr=0.3,0.1

Type RM Length L Ch R = 1 ,7940    ,280,280,280
BEGIN DESCRIPTION:
Walnut46 17.0
END DESCRIPTION:
XS GIS Cut Line= 3
      2726703.02      6752421.93       2726478.6      6752304.38
      2726401.66      6752274.46
#Sta/Elev= 30
    4824  343.94  4837.2  342.69  4852.8  342.28  4865.8  341.91  4910.9  337.57
  4925.4  336.95  4947.5  332.06  4956.1  332.58  4969.6  330.61  4991.6  324.94
  5001.3  324.12    5006  314.98  5006.3  314.48  5009.8  314.48    5010  314.98
  5013.7  317.08  5023.8  325.44  5030.1  329.11  5035.8  327.73  5046.4  329.53
  5052.2  332.15  5074.2  334.61  5077.3  335.52  5090.9  336.33  5098.3  337.56
  5103.7  337.08  5112.3  338.63  5128.2  339.98  5144.5  342.47  5159.9  343.34
#Mann= 4 ,-1 , 0
    4824     .05       0  4852.8     .12       0    5006     .07       0
    5010     .12       0
Bank Sta=5006,5010
XS Rating Curve= 0 ,0
Exp/Cntr=0.3,0.1

Type RM Length L Ch R = 1 ,7660    ,193,193,193
BEGIN DESCRIPTION:
Walnut46 16.0
END DESCRIPTION:
XS GIS Cut Line= 3
      2726735.06      6752193.28        2726626.        6752111.
      2726490.35      6752046.32
#Sta/Elev= 30
  4863.4  338.61    4872  338.62  4886.6   337.3  4936.5  331.46  4949.9  328.48
  4963.6  323.21  4971.9  321.25  4978.2  317.97  4986.5  314.18  4990.7  311.21
    4991  310.71  4994.5  310.71  4994.7  311.21  4996.9  318.11  5002.8  318.11
  5008.6  319.99  5014.1  322.24  5022.2  323.95  5031.3  325.56  5044.3  326.95
    5054  327.83  5059.5  327.98  5066.5  328.97  5088.7  330.01  5099.4  331.56
  5104.9   331.7  5113.4  332.92  5127.6  334.87  5133.2  335.06  5150.3  337.12
#Mann= 4 ,-1 , 0
  4863.4     .12       0  4990.7     .07       0  4994.7     .12       0
  5113.4     .05       0
Bank Sta=4990.7,4994.7
XS Rating Curve= 0 ,0
Exp/Cntr=0.3,0.1

Type RM Length L Ch R = 1 ,7467    ,237,237,237
BEGIN DESCRIPTION:
Walnut46 15.0
END DESCRIPTION:
XS GIS Cut Line= 3
      2726867.51      6752092.82      2726713.66      6751956.07
      2726587.59      6751859.91
#Sta/Elev= 30
  4770.9  334.98  4780.4  334.84  4787.1  333.45  4808.8  332.81    4823  331.58
  4879.9  325.96  4886.6  325.83  4893.3  324.32  4900.8  325.57  4929.2  323.69
  4935.9  322.66  4943.4  323.18  4950.1  321.48  4957.7  321.59  4964.4  318.72
  4971.8  314.43  4976.7  313.41  4984.4  308.09  4984.6  307.59  4988.4  308.09
    4993  316.34  4999.3  314.32  5007.5  317.27  5027.2  321.19  5049.3  326.36
    5072  328.67  5078.2  328.37  5086.5  329.13  5099.6  331.31  5135.3   331.2
#Mann= 4 ,-1 , 0
  4770.9     .12       0  4984.4     .07       0  4988.4     .12       0
  5027.2     .05       0
Bank Sta=4984.4,4988.4
XS Rating Curve= 0 ,0
Exp/Cntr=0.3,0.1

Type RM Length L Ch R = 1 ,7230    ,155,155,155
BEGIN DESCRIPTION:
Walnut46 14.3
END DESCRIPTION:
XS GIS Cut Line= 3
      2726946.87       6751703.2      2726821.71      6751727.49
      2726674.16       6751741.5
#Sta/Elev= 30
  4826.6  322.13  4829.6  322.13  4836.9  321.58    4842  322.05  4847.9  321.47
    4858  321.24  4888.6  319.06  4893.7  317.63  4898.8  318.04  4919.2  318.36
  4929.3  318.04  4939.5  316.93  4945.5  314.95  4950.2   314.5  4954.1   314.5
  4959.8  312.54  4967.9  305.32  4968.1  304.82  4971.6  304.82  4971.9  305.32
  4979.9  306.09    4990  313.11    5000  315.17    5010  316.86  5031.9  318.77
  5044.7  318.98  5050.2  319.33  5060.3   319.3  5080.4  321.35  5102.3  321.23
#Mann= 4 ,-1 , 0
  4826.6     .12       0  4967.9     .07       0  4971.9     .12       0
  5031.9     .05       0
Bank Sta=4967.9,4971.9
XS Rating Curve= 0 ,0
Exp/Cntr=0.3,0.1

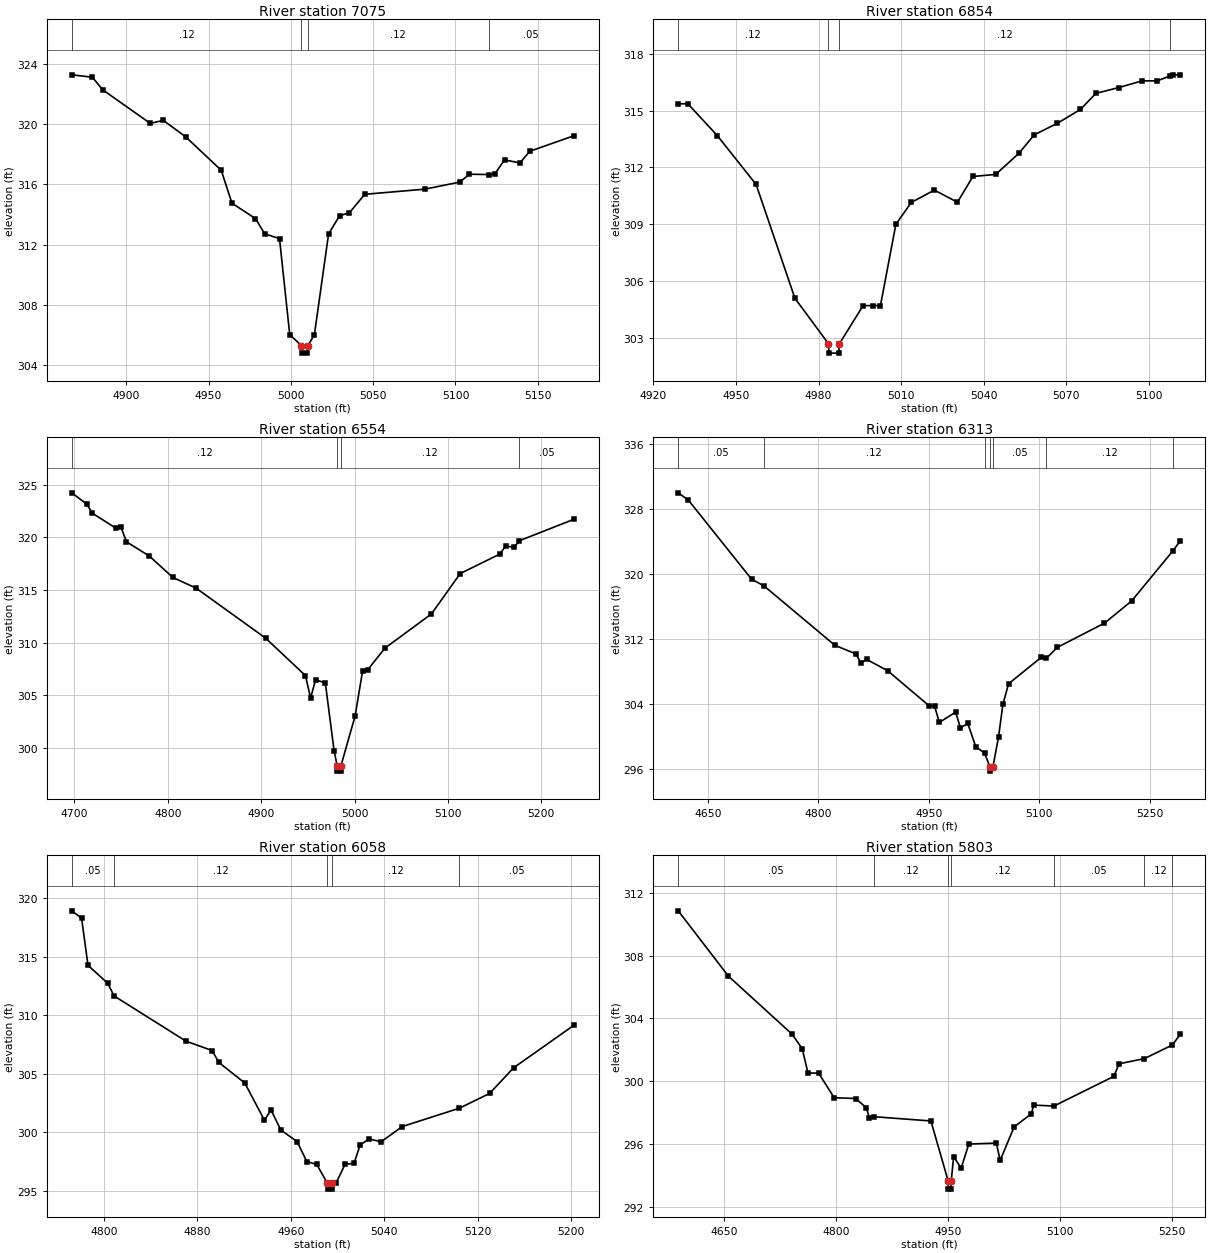
Type RM Length L Ch R = 1 ,7075    ,221,221,221
BEGIN DESCRIPTION:
Walnut46 14.0
END DESCRIPTION:
XS GIS Cut Line= 3
      2726919.77      6751517.38      2726826.38      6751593.03
      2726669.81      6751691.23
#Sta/Elev= 30
  4866.9  323.25  4879.4  323.09  4885.8  322.25  4914.6  320.03  4922.5  320.23
  4936.1  319.14  4957.7  316.92  4964.2  314.74  4978.5  313.72  4984.1  312.71
  4993.1  312.39  4999.3  306.03  5006.4   305.3  5006.6   304.8  5010.1   304.8
  5010.4   305.3  5014.3  306.03  5022.9   312.7  5029.6  313.91  5035.5   314.1
  5044.9  315.33  5081.4  315.67  5102.6  316.14  5108.5  316.66  5120.2  316.64
  5123.8  316.67  5129.8  317.61  5139.2  317.41  5145.1  318.18  5171.9  319.21
#Mann= 4 ,-1 , 0
  4866.9     .12       0  5006.4     .07       0  5010.4     .12       0
  5120.2     .05       0
Bank Sta=5006.4,5010.4
XS Rating Curve= 0 ,0
Exp/Cntr=0.3,0.1

Type RM Length L Ch R = 1 ,6854    ,300,300,300
BEGIN DESCRIPTION:
Walnut46 13.0
END DESCRIPTION:
XS GIS Cut Line= 3
      2726676.01      6751460.99        2726626.        6751511.
      2726576.01      6751610.97
#Sta/Elev= 29
    4929  315.36  4932.5  315.36  4943.2  313.68  4957.3   311.1  4971.4  305.09
  4983.6  302.69  4983.8  302.19  4987.3  302.19  4987.6  302.69  4996.2   304.7
  4999.7   304.7  5002.5   304.7  5008.1  308.99  5013.7  310.15  5022.1   310.8
  5030.5  310.16  5036.1  311.52  5044.4  311.63  5052.8  312.74  5058.4  313.72
  5066.8  314.33  5075.2  315.06  5080.8  315.91  5089.2  316.22  5097.6  316.57
  5103.1  316.57  5107.7  316.83  5108.7  316.89  5111.5  316.89
#Mann= 4 ,-1 , 0
    4929     .12       0  4983.6     .07       0  4987.6     .12       0
  5107.7     .05       0
Bank Sta=4983.6,4987.6
XS Rating Curve= 0 ,0
Exp/Cntr=0.3,0.1

Type RM Length L Ch R = 1 ,6554    ,241,241,241
BEGIN DESCRIPTION:
Walnut46 12.0
END DESCRIPTION:
XS GIS Cut Line= 3
      2726711.08      6751188.23      2726382.93      6751308.03
      2726222.25      6751406.51
#Sta/Elev= 30
  4697.1  324.25  4713.2  323.17  4719.1  322.31  4744.3  320.89  4749.7  321.01
  4755.7  319.59  4780.2  318.23  4805.4   316.2  4830.3  315.18  4904.8  310.42
  4947.4  306.86  4952.9  304.72  4958.2  306.45  4968.7  306.17  4978.1  299.69
  4981.4  298.27  4981.7  297.77  4985.2  297.77  4985.4  298.27  5000.6  303.02
  5008.6  307.29    5014   307.4  5032.5  309.47  5082.4  312.73  5113.2  316.57
  5155.8  318.43  5161.7  319.18  5171.2  319.08  5176.5  319.69  5234.9  321.73
#Mann= 4 ,-1 , 0
  4697.1     .12       0  4981.4     .07       0  4985.4     .12       0
  5176.5     .05       0
Bank Sta=4981.4,4985.4
XS Rating Curve= 0 ,0
Exp/Cntr=0.3,0.1

Type RM Length L Ch R = 1 ,6313    ,255,255,255
BEGIN DESCRIPTION:
Walnut46 11.0
END DESCRIPTION:
XS GIS Cut Line= 3
      2726526.01      6750810.99        2726276.        6751111.
      2726125.99      6751361.02
#Sta/Elev= 30
  4609.7  329.94  4623.4  329.05  4709.3  319.33  4726.3  318.49  4822.5   311.2
  4851.2  310.13  4857.7  309.05  4865.5  309.47  4894.1  308.08  4950.1  303.79
  4957.9  303.75  4964.4  301.72  4986.6  302.98  4993.1  301.05  5003.1  301.59
  5013.8  298.74  5025.9  297.94  5033.2  296.23  5033.5  295.73  5037.2  296.23
  5044.9  299.97  5050.8  303.96  5058.5  306.47  5103.2  309.74    5110  309.61
  5124.6  310.94  5188.8  313.92  5225.7  316.65  5281.3  322.76  5291.8  324.04
#Mann= 7 ,-1 , 0
  4609.7     .05       0  4726.3     .12       0  5025.9     .05       0
  5033.2     .07       0  5037.2     .05       0    5110     .12       0
  5281.3     .05       0
Bank Sta=5033.2,5037.2
XS Rating Curve= 0 ,0
Exp/Cntr=0.3,0.1

Type RM Length L Ch R = 1 ,6058    ,255,255,255
BEGIN DESCRIPTION:
Walnut46 10.0
END DESCRIPTION:
XS GIS Cut Line= 3
      2726175.98      6750761.03        2726076.        6750961.
      2726026.01      6751160.97
#Sta/Elev= 30
  4772.5  318.93  4780.9   318.3  4786.4  314.27  4803.2  312.74  4808.7  311.65
  4870.3  307.78  4892.7  306.98  4898.2  305.98  4920.6   304.2  4937.4  301.02
    4943   301.9  4951.4  300.19  4965.3   299.2  4973.7  297.48  4982.1  297.25
  4991.3  295.63  4991.5  295.13    4995  295.13  4995.3  295.63  4998.6  295.63
  5006.4  297.25  5014.1  297.34  5019.3  298.91    5027  299.42  5037.3  299.18
  5055.3  300.48  5104.2  302.05  5130.1  303.31  5150.7  305.51  5202.2  309.14
#Mann= 5 ,-1 , 0
  4772.5     .05       0  4808.7     .12       0  4991.3     .07       0
  4995.3     .12       0  5104.2     .05       0
Bank Sta=4991.3,4995.3
XS Rating Curve= 0 ,0
Exp/Cntr=0.3,0.1

Type RM Length L Ch R = 1 ,5803    ,292,292,292
BEGIN DESCRIPTION:
Walnut46 9.0
END DESCRIPTION:
XS GIS Cut Line= 4
      2726033.98      6750594.47       2725867.3      6750792.41
      2725834.34      6751001.15      2725711.52      6751161.65
#Sta/Elev= 30
  4588.9  310.85  4655.9   306.7  4741.2     303  4754.8  302.08  4762.6  300.53
  4776.9  300.51  4797.7  298.95  4826.3   298.9  4840.6  298.32  4844.8  297.67
  4851.3  297.74  4927.2  297.47  4950.4  293.63  4950.6  293.13  4954.1  293.13
  4954.4  293.63  4957.6   295.2  4967.7  294.46  4977.9     296  5014.8  296.06
  5019.9  294.96  5038.6  297.09  5061.7  297.93  5064.8  298.48  5091.9  298.42
  5172.1  300.31  5179.1  301.11    5213  301.44  5250.5  302.31  5261.1  302.99
#Mann= 7 ,-1 , 0
  4588.9     .05       0  4851.3     .12       0  4950.4     .07       0
  4954.4     .12       0  5091.9     .05       0    5213     .12       0
  5250.5     .05       0
Bank Sta=4950.4,4954.4
XS Rating Curve= 0 ,0
Exp/Cntr=0.3,0.1

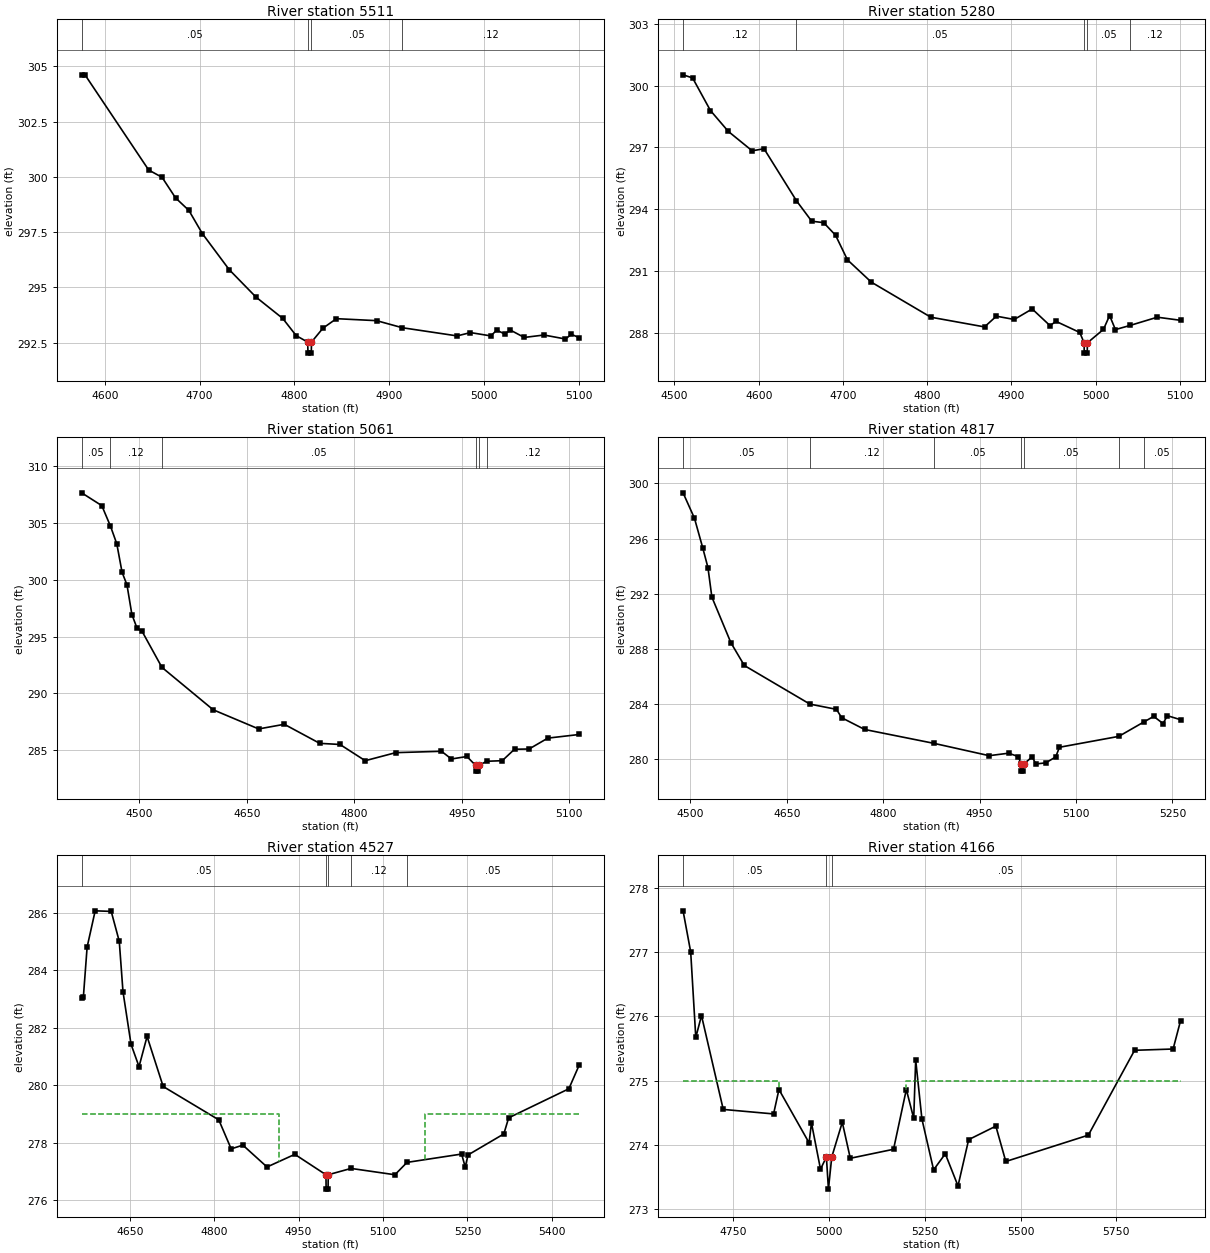
Type RM Length L Ch R = 1 ,5511    ,231,231,231
BEGIN DESCRIPTION:
Walnut46 8.0
END DESCRIPTION:
XS GIS Cut Line= 3
      2725875.99      6750611.01        2725576.        6750911.
      2725496.66       6750972.6
#Sta/Elev= 30
  4575.7  304.62  4579.2  304.62  4646.4  300.31  4660.5  299.98  4674.7  299.05
  4688.8  298.48    4703  297.43  4731.3   295.8  4759.5  294.56  4787.8  293.59
    4802  292.81  4814.1  292.52  4814.4  292.02  4817.9  292.02  4818.1  292.52
  4830.2  293.15  4844.4  293.58  4886.8  293.49  4913.9  293.17  4971.7   292.8
  4985.8  292.95  5007.2   292.8  5013.5  293.06  5021.7  292.89    5028  293.06
  5042.5  292.73  5063.3  292.84  5085.9  292.66  5092.3  292.87  5100.4  292.72
#Mann= 4 ,-1 , 0
  4575.7     .05       0  4814.1     .07       0  4818.1     .05       0
  4913.9     .12       0
Bank Sta=4814.1,4818.1
XS Rating Curve= 0 ,0
Exp/Cntr=0.3,0.1

Type RM Length L Ch R = 1 ,5280    ,219,219,219
BEGIN DESCRIPTION:
Walnut46 7.0
END DESCRIPTION:
XS GIS Cut Line= 4
      2725768.36      6750417.39        2725426.        6750761.
      2725369.29       6750820.9      2725346.95      6750826.21
#Sta/Elev= 30
  4510.2  300.52  4521.5  300.37  4542.7  298.79  4563.9  297.78  4592.2  296.84
  4606.3  296.94  4644.8  294.42  4662.9  293.43  4677.1  293.36  4691.2  292.75
  4705.3  291.56  4733.6  290.48  4804.3  288.78    4868  288.31  4882.1  288.83
  4903.3  288.67  4924.6  289.18  4945.8  288.37  4952.8  288.58  4981.1  288.04
  4986.2  287.54  4986.4  287.04  4989.9  287.04  4990.2  287.54  5009.2  288.19
  5016.5  288.86  5023.4  288.18  5040.7  288.38  5073.1  288.78  5100.7  288.63
#Mann= 5 ,-1 , 0
  4510.2     .12       0  4644.8     .05       0  4986.2     .04       0
  4990.2     .05       0  5040.7     .12       0
Bank Sta=4986.2,4990.2
XS Rating Curve= 0 ,0
Exp/Cntr=0.3,0.1

Type RM Length L Ch R = 1 ,5061    ,244,244,244
BEGIN DESCRIPTION:
Walnut46 6.0
END DESCRIPTION:
XS GIS Cut Line= 3
      2725643.34      6750209.07      2725237.09      6750656.99
      2725208.58      6750741.82
#Sta/Elev= 30
  4419.7  307.67  4447.8  306.54  4459.9  304.73  4468.7  303.18  4476.1  300.66
  4482.9  299.56  4489.8  296.94  4497.1  295.71  4503.8  295.48  4531.7  292.28
  4603.2  288.54  4666.7  286.85  4702.5  287.26  4751.9  285.58  4780.2  285.48
  4815.4  284.05    4858  284.76  4921.8  284.88  4935.7   284.2  4957.3  284.42
  4969.5  283.63  4969.8  283.13  4973.3  283.13  4973.5  283.63    4985     284
  5006.6  284.05  5023.7  285.06    5044  285.08  5070.2  286.04  5113.9  286.36
#Mann= 6 ,-1 , 0
  4419.7     .05       0  4459.9     .12       0  4531.7     .05       0
  4969.5     .07       0  4973.5     .05       0    4985     .12       0
Bank Sta=4969.5,4973.5
XS Rating Curve= 0 ,0
Exp/Cntr=0.3,0.1

Type RM Length L Ch R = 1 ,4817    ,290,290,290
BEGIN DESCRIPTION:
Walnut46 5.0
END DESCRIPTION:
XS GIS Cut Line= 3
      2725461.03      6750172.63      2725143.34      6750396.57
      2724940.58      6750724.11
#Sta/Elev= 30
  4488.8  299.32  4506.5  297.48  4519.4  295.33  4527.5   293.9  4533.6  291.76
  4563.2  288.45  4584.1   286.8  4686.1     284  4727.4  283.62  4735.6  283.01
  4771.3  282.16  4879.5  281.15    4965  280.26  4995.2  280.44  5010.6  280.19
  5014.4  279.64  5014.7  279.14  5018.2  279.14  5018.4  279.64  5031.8  280.17
  5037.7  279.66  5053.1  279.74  5068.5  280.17  5074.3  280.87  5166.6  281.66
  5205.1  282.69  5220.9  283.11  5235.5  282.59  5242.2  283.16  5262.7  282.87
#Mann= 7 ,-1 , 0
  4488.8     .05       0  4686.1     .12       0  4879.5     .05       0
  5014.4     .04       0  5018.4     .05       0  5166.6     .12       0
  5205.1     .05       0
Bank Sta=5014.4,5018.4
XS Rating Curve= 0 ,0
Exp/Cntr=0.3,0.1

Type RM Length L Ch R = 1 ,4527    ,361,361,361
BEGIN DESCRIPTION:
Walnut46 4.0
END DESCRIPTION:
XS GIS Cut Line= 4
      2725211.06      6750031.99      2724789.18      6750391.37
      2724763.88      6750568.42       2724851.4      6750691.16
#Sta/Elev= 30
  4564.6  283.02  4567.7  283.08  4574.3   284.8  4588.6  286.06  4617.1  286.04
  4631.4     285    4638  283.25  4652.3  281.42  4666.5  280.64  4680.8  281.69
  4709.4  279.95  4808.2  278.79  4830.2  277.78    4851  277.91  4893.9  277.15
  4943.3  277.59  4998.6  276.88  4998.9  276.38  5002.4  276.38  5002.6  276.88
  5043.2   277.1  5121.1  276.88  5142.6  277.31  5239.6   277.6    5246  277.15
  5251.1  277.57  5314.6   278.3  5323.2  278.86  5430.1  279.87  5448.4  280.69
#Mann= 5 ,-1 , 0
  4564.6     .05       0  4998.6     .05       0  5002.6     .12       0
  5043.2     .12       0  5142.6     .05       0
#XS Ineff= 2 , 0
       0    4915     279    5175       0     279
Permanent Ineff=
       F       F
Bank Sta=4998.6,5002.6
XS Rating Curve= 0 ,0
Exp/Cntr=0.3,0.1

Type RM Length L Ch R = 1 ,4166    ,429,429,429
BEGIN DESCRIPTION:
Walnut46 3.7
END DESCRIPTION:
XS GIS Cut Line= 4
      2724796.99      6749904.56      2724523.48      6750303.44
      2724465.97      6750611.88       2724520.7      6751110.28
#Sta/Elev= 30
  4618.8  277.64  4638.7     277    4652  275.67  4666.9  276.01  4723.7  274.55
  4855.1  274.48  4869.1  274.86  4947.8  274.03    4954  274.34  4977.6  273.62
    4993  273.81  4998.3  273.31    5007  273.81  5034.5  274.35  5055.4  273.79
  5168.3  273.93  5201.7  274.86    5221  274.41  5226.1  275.32  5242.4   274.4
  5272.9  273.61  5303.4  273.86  5336.6  273.36  5364.4  274.08  5435.4  274.29
  5461.4  273.74  5676.9  274.15  5797.6  275.47  5898.2  275.49  5917.6  275.93
#Mann= 3 ,-1 , 0
  4618.8     .05       0    4993     .04       0    5007     .05       0
#XS Ineff= 2 , 0
       0  4869.1     275  5201.7       0     275
Permanent Ineff=
       F       F
Bank Sta=4993,5007
XS Rating Curve= 0 ,0
Exp/Cntr=0.3,0.1

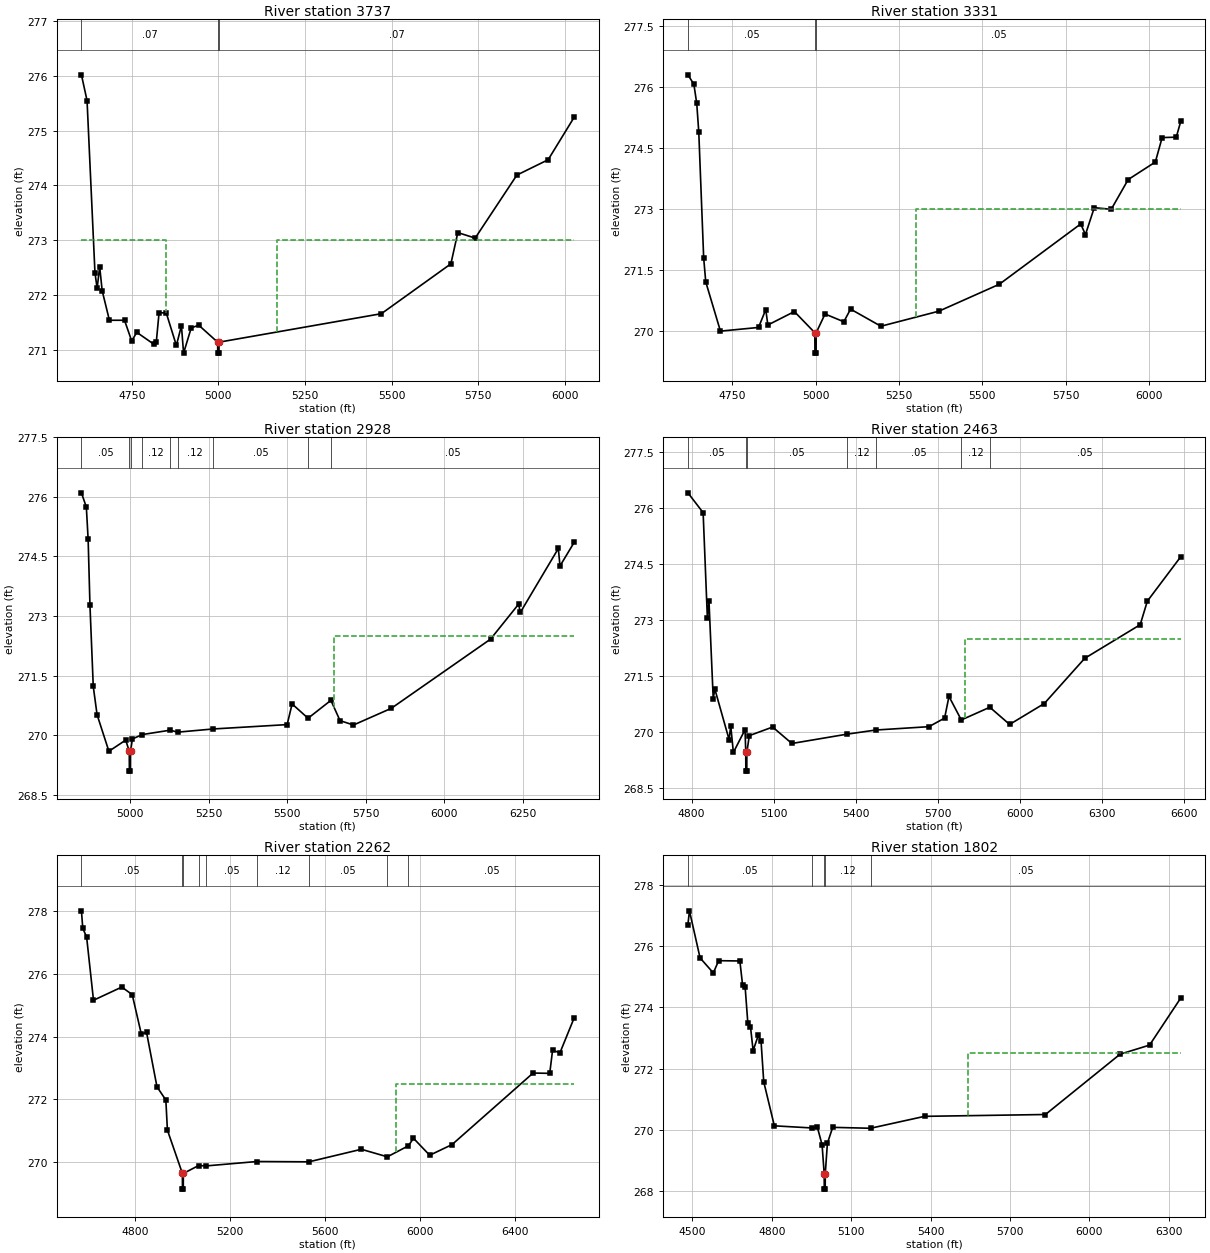
Type RM Length L Ch R = 1 ,3737    ,406,406,406
BEGIN DESCRIPTION:
Walnut46 3.4
END DESCRIPTION:
XS GIS Cut Line= 4
      2724497.85      6749779.17      2724150.23      6750235.06
      2724108.96      6750377.63      2724062.59      6751076.36
#Sta/Elev= 30
    4605  276.02  4621.2  275.55    4644  272.41  4650.3  272.12  4657.6  272.52
  4664.8  272.08  4685.7  271.54  4729.3  271.54  4750.1  271.16  4764.6  271.32
  4814.5   271.1  4821.1  271.15    4829  271.68  4849.9  271.67  4878.9  271.08
  4893.5  271.44  4899.7  270.94  4921.7   271.4  4943.4  271.45    4998  271.14
  4998.3  270.94  5001.8  270.94    5002  271.14  5470.4  271.66  5670.9  272.57
  5690.9  273.14    5741  273.04  5861.3  274.19  5951.5  274.47    6027  275.25
#Mann= 3 ,-1 , 0
    4605     .07       0    4998     .04       0    5002     .07       0
#XS Ineff= 2 , 0
       0    4850     273    5170       0     273
Permanent Ineff=
       F       F
Bank Sta=4998,5002
XS Rating Curve= 0 ,0
Exp/Cntr=0.3,0.1

Type RM Length L Ch R = 1 ,3331    ,403,403,403
BEGIN DESCRIPTION:
Walnut46 3.2
END DESCRIPTION:
XS GIS Cut Line= 4
      2724190.14      6749639.55      2723925.15      6750004.27
      2723879.81      6750303.13      2724014.13      6751015.98
#Sta/Elev= 30
  4617.2  276.29  4635.1  276.06  4643.7  275.59  4649.8  274.89  4664.5   271.8
  4670.7  271.21  4714.8     270  4829.1  270.09  4850.8  270.53    4857  270.15
  4936.6  270.48    4998  269.96  4998.3  269.46  5001.8  269.46    5002  269.96
  5028.6  270.42  5084.9  270.23  5105.2  270.54  5196.2  270.12  5370.3  270.49
  5551.3  271.15  5795.5  272.63  5809.8  272.37  5836.2  273.03  5887.1  272.99
    5938  273.72  6019.4  274.15  6039.8  274.75  6082.2  274.76  6095.7  275.15
#Mann= 3 ,-1 , 0
  4617.2     .05       0    4998     .04       0    5002     .05       0
#XS Ineff= 2 , 0
       0                    5300       0     273
Permanent Ineff=
       F       F
Bank Sta=4998,5002
XS Rating Curve= 0 ,0
Exp/Cntr=0.3,0.1

Type RM Length L Ch R = 1 ,2928    ,465,465,465
BEGIN DESCRIPTION:
Walnut46 3.0
END DESCRIPTION:
XS GIS Cut Line= 5
      2723910.88      6749537.05      2723859.62      6749633.88
       2723693.7      6749913.99      2723709.04      6750110.42
      2724006.37      6750996.52
#Sta/Elev= 30
  4845.9   276.1  4861.5  275.74  4867.2  274.93    4873  273.27  4883.5  271.23
  4895.6  270.52  4933.2   269.6  4986.6  269.88    4998   269.6  4998.3   269.1
  5001.8   269.1    5002   269.6    5008  269.91  5039.5  270.02    5128  270.13
  5151.7  270.08    5264  270.16  5499.8  270.27  5515.6  270.79  5566.3  270.43
  5638.9  270.88    5668  270.37  5710.7  270.26    5831  270.68  6146.4  272.42
  6235.7   273.3    6241  273.09  6361.9   274.7  6367.2  274.26  6412.7  274.86
#Mann= 9 ,-1 , 0
  4845.9     .05       0    4998     .04       0    5002     .05       0
  5039.5     .12       0    5128     .05       0  5151.7     .12       0
    5264     .05       0  5566.3     .12       0  5638.9     .05       0
#XS Ineff= 2 , 0
       0                    5650       0   272.5
Permanent Ineff=
       F       F
Bank Sta=4998,5002
XS Rating Curve= 0 ,0
Exp/Cntr=0.3,0.1

Type RM Length L Ch R = 1 ,2463    ,201,201,201
BEGIN DESCRIPTION:
Walnut46 2.8
END DESCRIPTION:
XS GIS Cut Line= 3
      2723332.53      6749277.76      2723506.31       6749565.5
      2723979.96      6750953.36
#Sta/Elev= 30
  4786.4  276.41  4842.1  275.88  4857.6  273.06  4863.5  273.51    4879   270.9
  4884.8  271.16  4937.2   269.8    4943  270.18  4952.7  269.46  4995.4  270.07
    4998  269.46  4998.3  268.96  5001.8  268.96    5002  269.46  5010.9  269.91
  5096.3  270.14  5166.7   269.7  5368.8  269.95  5473.2  270.06    5668  270.15
  5725.3  270.38  5741.2  270.96  5786.3  270.33  5890.6  270.67  5963.1  270.21
  6089.9  270.77  6237.8  271.98  6440.6  272.88  6466.7  273.51    6589   274.7
#Mann= 7 ,-1 , 0
  4786.4     .05       0    4998     .04       0    5002     .05       0
  5368.8     .12       0  5473.2     .05       0  5786.3     .12       0
  5890.6     .05       0
#XS Ineff= 2 , 0
       0                    5800       0   272.5
Permanent Ineff=
       F       F
Bank Sta=4998,5002
XS Rating Curve= 0 ,0
Exp/Cntr=0.3,0.1

Type RM Length L Ch R = 1 ,2262    ,460,460,460
BEGIN DESCRIPTION:
Walnut46 2.6
END DESCRIPTION:
XS GIS Cut Line= 3
      2722870.94      6749286.27       2723389.5       6749559.8
       2723968.3       6750936.6
#Sta/Elev= 30
    4572  278.01  4577.7  277.45  4593.8  277.18  4622.9  275.16  4742.3  275.58
  4786.3  275.34  4824.7  274.08  4846.7  274.14  4890.8   272.4  4928.2  271.98
  4934.8  271.02    4998  269.64  4998.3  269.14  5001.8  269.14    5002  269.64
  5066.1  269.89  5098.5  269.88  5312.3  270.02  5531.9  270.01  5753.2  270.41
  5862.8  270.17  5951.5  270.52  5973.2  270.76  6041.6  270.22  6135.9  270.56
  6477.9  272.84  6548.1  272.83    6560  273.56  6591.5  273.49  6651.8  274.61
#Mann= 9 ,-1 , 0
    4572     .05       0    4998     .04       0    5002     .05       0
  5066.1     .12       0  5098.5     .05       0  5312.3     .12       0
  5531.9     .05       0  5862.8     .12       0  5951.5     .05       0
#XS Ineff= 2 , 0
       0                    5900       0   272.5
Permanent Ineff=
       F       F
Bank Sta=4998,5002
XS Rating Curve= 0 ,0
Exp/Cntr=0.3,0.1

Type RM Length L Ch R = 1 ,1802    ,388,388,388
BEGIN DESCRIPTION:
Walnut46 2.3
END DESCRIPTION:
XS GIS Cut Line= 4
      2722660.13      6749861.81      2723291.25      6749906.26
      2723640.59      6750291.33      2723958.15      6750926.46
#Sta/Elev= 30
  4482.9  276.71  4488.8  277.16  4528.9  275.62    4579  275.13  4599.1  275.53
  4679.3  275.52  4689.6  274.73  4699.3  274.66  4709.3   273.5  4719.4  273.37
  4729.4  272.59  4749.4   273.1  4759.4  272.89  4769.5  271.57  4809.6  270.13
  4951.8  270.06  4972.3  270.08    4990  269.51    4998  268.56  4998.3  268.06
  5001.8  268.06    5002  268.56  5010.1  269.56  5030.1  270.08    5173  270.05
  5377.4  270.44  5834.2   270.5  6115.9  272.47  6227.7  272.77  6345.6  274.31
#Mann= 5 ,-1 , 0
  4482.9     .05       0  4951.8     .12       0    4998     .04       0
    5002     .12       0    5173     .05       0
#XS Ineff= 2 , 0
       0                    5540       0   272.5
Permanent Ineff=
       F       F
Bank Sta=4998,5002
XS Rating Curve= 0 ,0
Exp/Cntr=0.3,0.1

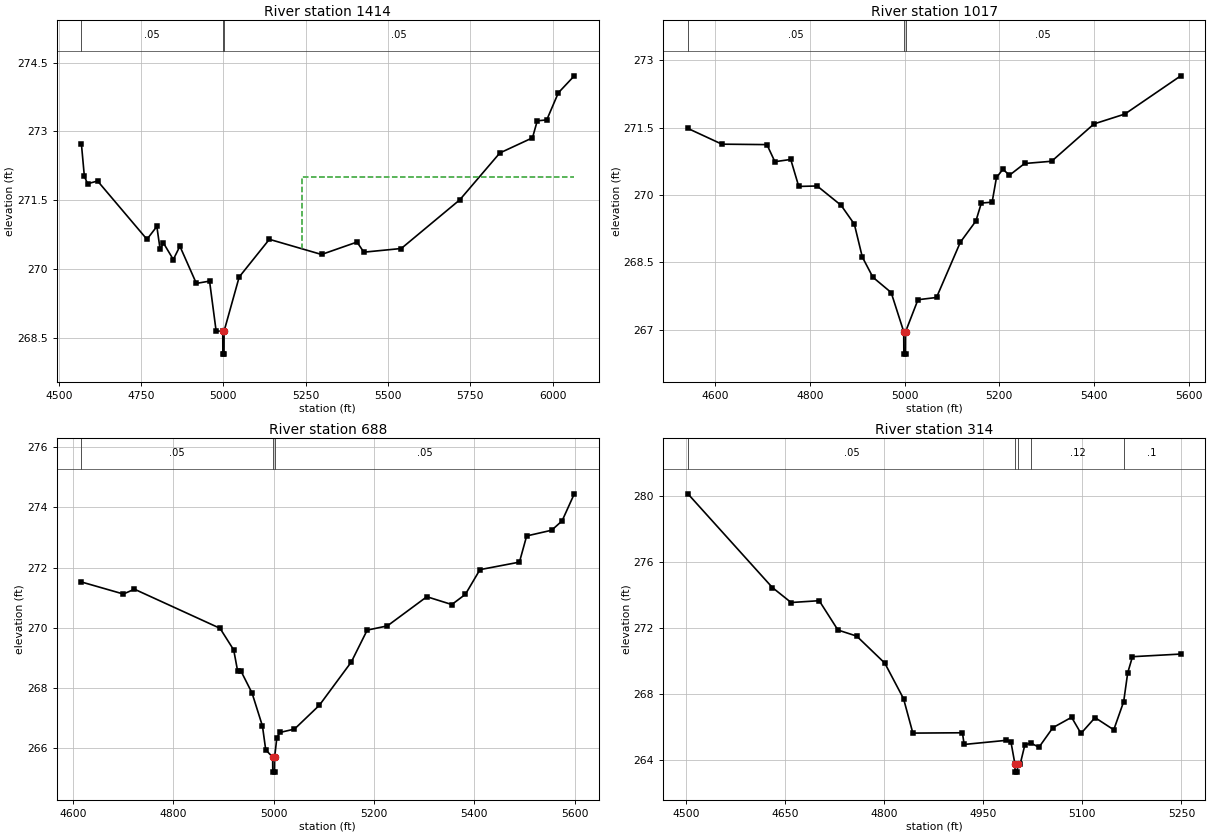
Type RM Length L Ch R = 1 ,1414    ,397,397,397
BEGIN DESCRIPTION:
Walnut46 2.0
END DESCRIPTION:
XS GIS Cut Line= 4
      2722737.07       6750249.3      2723289.78      6750263.55
      2723541.95      6750435.68      2723941.14      6750934.11
#Sta/Elev= 30
  4568.8  272.72  4577.7  272.02  4587.7  271.86  4617.8  271.92  4767.8  270.65
  4797.8  270.93  4807.8  270.43  4817.8  270.57  4847.8  270.21  4867.8   270.5
  4917.8  269.69  4957.9  269.74  4977.9  268.65    4998  268.65  4998.3  268.15
  5001.8  268.15    5002  268.65  5047.9  269.83  5139.5  270.65    5298  270.32
  5405.7  270.59  5426.4  270.37  5540.1  270.45  5717.8  271.51  5839.4  272.53
  5938.6  272.86  5953.1  273.23  5981.9  273.25  6017.1  273.84  6065.6  274.21
#Mann= 3 ,-1 , 0
  4568.8     .05       0    4998     .04       0    5002     .05       0
#XS Ineff= 2 , 0
       0                    5240       0     272
Permanent Ineff=
       F       F
Bank Sta=4998,5002
XS Rating Curve= 0 ,0
Exp/Cntr=0.3,0.1

Type RM Length L Ch R = 1 ,1017    ,329,329,329
BEGIN DESCRIPTION:
Walnut46 1.6
END DESCRIPTION:
XS GIS Cut Line= 3
      2722691.47      6750431.66      2723224.24      6750696.63
      2723614.58      6750913.16
#Sta/Elev= 30
    4542  271.48  4613.8  271.13    4709  271.12  4725.8  270.74  4759.3  270.79
  4776.2  270.19  4815.1   270.2  4865.7  269.77  4893.7  269.35  4910.5  268.62
  4932.9  268.17  4971.5  267.83    4998  266.96  4998.3  266.46  5001.8  266.46
    5002  266.96  5028.1  267.67  5067.3  267.72  5117.7  268.95  5150.5  269.42
    5162  269.82  5184.8  269.84    5194  270.39  5207.6  270.57  5221.5  270.44
  5253.4   270.7  5310.6  270.75    5400  271.58  5465.3   271.8  5583.4  272.65
#Mann= 3 ,-1 , 0
    4542     .05       0    4998     .04       0    5002     .05       0
Bank Sta=4998,5002
XS Rating Curve= 0 ,0
Exp/Cntr=0.3,0.1

Type RM Length L Ch R = 1 ,688     ,374,374,374
BEGIN DESCRIPTION:
Walnut46 1.3
END DESCRIPTION:
XS GIS Cut Line= 3
      2722620.22      6750528.53      2722984.91       6750967.3
      2723238.48       6751292.1
#Sta/Elev= 30
  4616.8  271.52  4700.4  271.12  4722.5  271.28  4893.1  269.98  4920.4  269.26
  4928.3  268.55  4934.8  268.56  4956.9  267.83  4977.7  266.73  4984.2  265.94
    4998   265.7  4998.3   265.2  5001.8   265.2    5002   265.7  5006.4  266.35
  5012.9  266.52  5041.5  266.63    5091  267.42  5154.8  268.86  5186.5  269.92
  5226.7  270.06  5305.4  271.03  5355.2  270.77  5382.3  271.11  5411.3  271.93
    5490  272.18  5504.4  273.05  5554.2  273.24    5575  273.55  5599.4  274.45
#Mann= 3 ,-1 , 0
  4616.8     .05       0    4998     .04       0    5002     .05       0
Bank Sta=4998,5002
XS Rating Curve= 0 ,0
Exp/Cntr=0.3,0.1

Type RM Length L Ch R = 1 ,314     ,0,0,0
BEGIN DESCRIPTION:
Walnut46 1.0
END DESCRIPTION:
XS GIS Cut Line= 3
      2722315.32      6750670.95      2722597.42      6750975.85
       2722828.2      6751212.32
#Sta/Elev= 30
  4503.2  280.14    4631  274.45  4659.4  273.54  4701.9  273.65  4730.2  271.87
  4758.6   271.5  4801.1  269.86  4829.5   267.7  4843.6  265.61  4918.6  265.63
  4921.2  264.92  4984.8  265.17    4992  265.08    4998  263.74  4998.3  263.24
  5001.8  263.24    5002  263.74  5006.1  263.74  5013.1   264.9  5022.5     265
  5034.4  264.75  5055.5  265.94  5083.8  266.57    5098  265.59  5119.3  266.55
  5147.6  265.81  5162.6  267.52  5168.7  269.27  5175.9  270.25    5249  270.41
#Mann= 5 ,-1 , 0
  4503.2     .05       0    4998     .04       0    5002     .05       0
  5022.5     .12       0  5162.6      .1       0
Bank Sta=4998,5002
XS Rating Curve= 0 ,0
Exp/Cntr=0.3,0.1

Chan Stop Cuts=-1
Use User Specified Reach Order=0
Composite Channel Slope=5