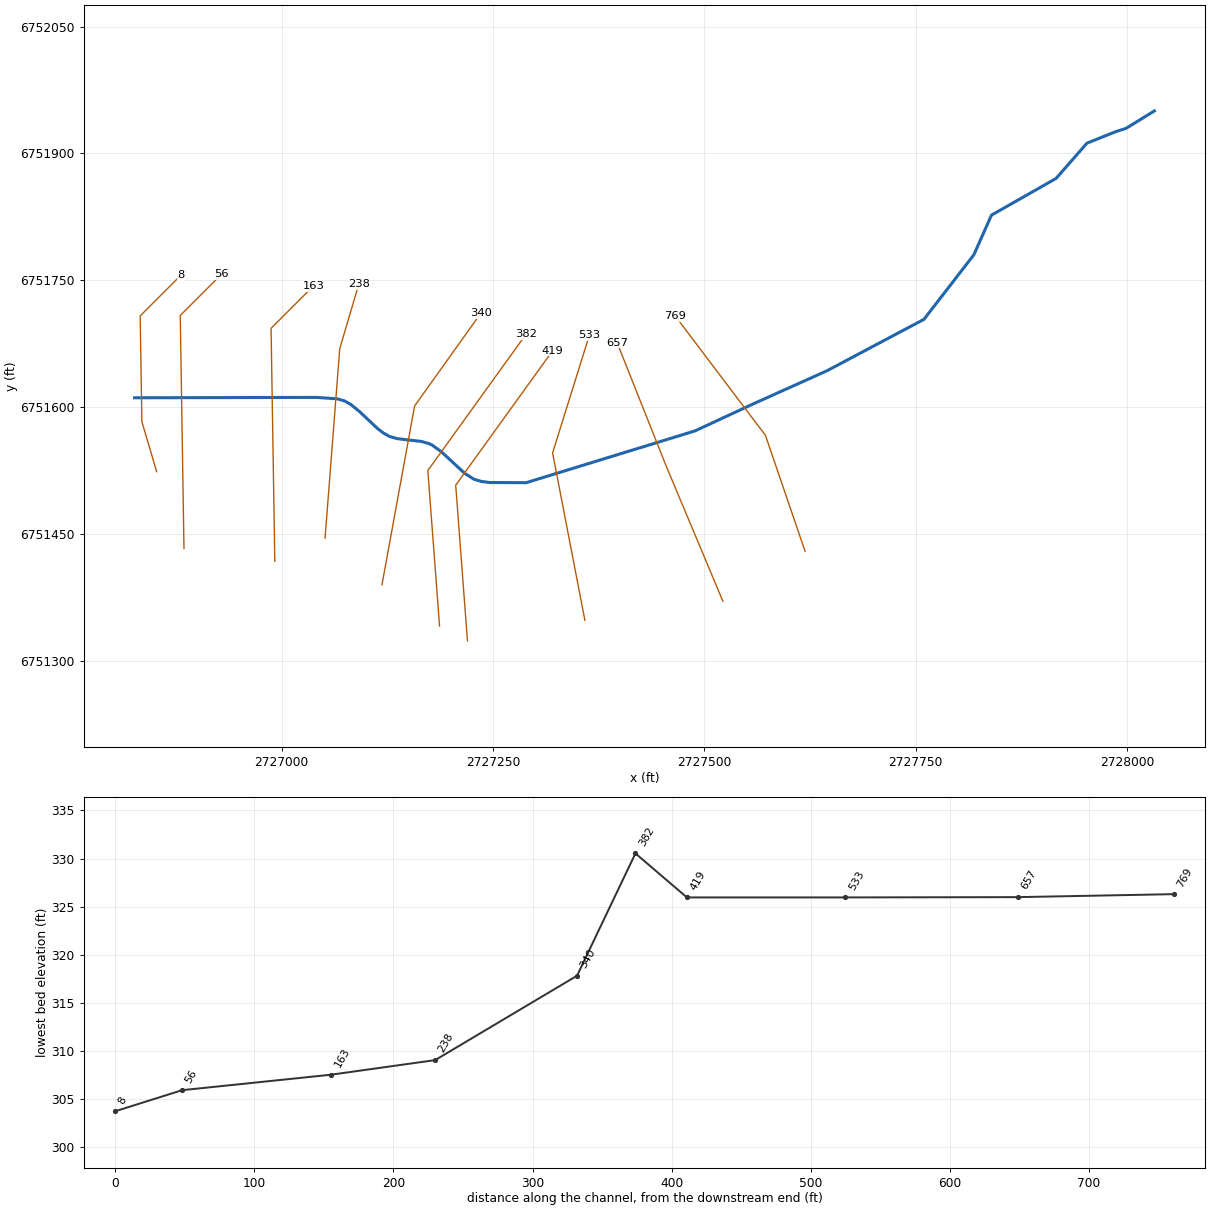
--- Walnut48.prj (project) ---

Proj Title=Walnut48 Base Level Engineering
Current Plan=p01
Default Exp/Contr=0.3,0.1
English Units
Geom File=g01
Flow File=f01
Plan File=p01
Y Axis Title=Elevation
X Axis Title(PF)=Main Channel Distance
X Axis Title(XS)=Station
BEGIN DESCRIPTION:
Walnut48
END DESCRIPTION:
DSS Export Rating Curves= 0
DSS Export Rating Curve Sorted= 0
DSS Export Volume Flow Curves= 0
DXF OffsetX= 0
DXF OffsetY= 0
DXF ScaleX= 1
DXF ScaleY= 10

--- Walnut48.p01 (plan) ---

Plan Title=Multiple Run
Program Version=4.10
Short Identifier=Multiple
Geom File=g01
Flow File=f01
Subcritical Flow
K Sum by GR= 0
Std Step Tol= 0.01
Critical Tol= 0.01
Num of Std Step Trials= 20
Max Error Tol= 0.3
Flow Tol Ratio= 0.001
Split Flow NTrial= 30
Split Flow Tol= 0.02
Split Flow Ratio= 0.02
Log Output Level= 0
Friction Slope Method= 1
Unsteady Friction Slope Method= 2
Unsteady Bridges Friction Slope Method= 1
Parabolic Critical Depth
Global Vel Dist= 1 , 1 , 1
Global Log Level= 0
CheckData=True
Encroach Param=-1 ,0,0, 0
BEGIN DESCRIPTION:
Multiple Run
END DESCRIPTION:
Computation Interval=1HOUR
Output Interval=1HOUR
Run HTab= 0
Run UNet= 0
Run PostProcess= 0
Run WQNet= 0
UNET Theta= 1
UNET Theta Warmup= 1
UNET ZTol= 0.02
UNET ZSATol= 0.05
UNET MxIter= 20
UNET MaxInSteps= 0
UNET DtIC= 0
UNET DtMin= 0
UNET MaxCRTS= 20
UNET WFStab= 2
UNET SFStab= 1
UNET WFX= 1
UNET SFX= 1
UNET DSS MLevel= 4
UNET DZMax Abort= 100
UNET Convert EG Bridges= 0
UNET Use Existing IB Tables=-1
UNET Froude Reduction=False
UNET Froude Limit= 1
UNET Froude Power= 10
UNET Time Slicing=0,0, 5
UNET Junction Losses=0
Instantaneous Interval=1HOUR
Write IC File= 0
Write IC File at Sim End=0
Echo Input=False
Echo Parameters=False
Echo Output=False
Write Detailed= 0
WQ AD Non Conservative
WQ ULTIMATE=-1
WQ Max Comp Step=1HOUR
WQ Output Interval=15MIN
WQ Output Selected Increments= 0
WQ Output face flow=0
WQ Output face velocity=0
WQ Output face area=0
WQ Output face dispersion=0
WQ Output cell volume=0
WQ Output cell surface area=0
WQ Output cell continuity=0
WQ Output cumulative cell continuity=0
WQ Output face conc=0
WQ Output face dconc_dx=0
WQ Output face courant=0
WQ Output face peclet=0
WQ Output face adv mass=0
WQ Output face disp mass=0
WQ Output cell mass=0
WQ Output cell source sink temp=0
WQ Output cell source sink nsm=0
WQ Output MaxMinRange=-1
WQ Daily Max Min Mean=-1
WQ Daily Range=0
WQ Daily Time=0
WQ Create Restart=0
WQ Fixed Restart=0
WQ System Summary=0
WQ Use Fixed Temperature=0
Sorting and Armoring Iterations= 10
XS Update Threshold= 0.02
Hydraulics Update Threshold= 0.02
Energy Slope Method= 1
Volume Change Method= 0
XS Weighting Method= 0
Number of US Weighted Cross Sections= 1
Number of DS Weighted Cross Sections= 1
Upstream XS Weight=0.25
Main XS Weight=0.5
Downstream XS Weight=0.25
Number of DS XS's Weighted with US Boundary= 1
Upstream Boundary Weight= 1
Weight of XSs Associated with US Boundary= 0
Number of US XS's Weighted with DS Boundary= 1
Downstream Boundary Weight= 0.5
Weight of XSs Associated with DS Boundary= 0.5
Sediment Output Level= 4
Mass or Volume Output= 0
Output Increment Type= 1
Profile and TS Output Increment= 10
XS Output Flag= 0
XS Output Increment= 10
Disregard all LS=0
Disregard all Conn=0
Disregard all Breaches=0
Disregard all Pumps=0

--- Walnut48.f01 (steady flow) ---

Flow Title=Multiple
Number of Profiles=7
Profile Names=10-year,25-year,50-year,1pct_min,100-year,1pct_plu,500-year
River Rch & RM= Walnut48,Reach-1,769
      82      97     108      60     121     240     148
River Rch & RM= Walnut48,Reach-1,8
     180     224     258     148     296     590     388
Boundary for River Rch & Prof#=Walnut48,Reach-1,1
Up Type=0
Dn Type=3
Dn Slope=0.05
Boundary for River Rch & Prof#=Walnut48,Reach-1,2
Up Type=0
Dn Type=3
Dn Slope=0.05
Boundary for River Rch & Prof#=Walnut48,Reach-1,3
Up Type=0
Dn Type=3
Dn Slope=0.05
Boundary for River Rch & Prof#=Walnut48,Reach-1,4
Up Type=0
Dn Type=3
Dn Slope=0.05
Boundary for River Rch & Prof#=Walnut48,Reach-1,5
Up Type=0
Dn Type=3
Dn Slope=0.05
Boundary for River Rch & Prof#=Walnut48,Reach-1,6
Up Type=0
Dn Type=3
Dn Slope=0.05
Boundary for River Rch & Prof#=Walnut48,Reach-1,7
Up Type=0
Dn Type=3
Dn Slope=0.05

--- Walnut48.g01 (geometry) ---

Geom Title=Existing Conditions

River Reach=Walnut48,Reach-1
Reach XY= 30
      2728032.25      6751950.29      2727998.40      6751929.46
      2727987.11      6751925.99      2727952.39      6751912.10
      2727915.93      6751870.43      2727839.54      6751827.03
      2727818.71      6751780.16      2727759.68      6751703.77
      2727645.10      6751643.00      2727560.03      6751604.81
      2727488.85      6751571.82      2727289.16      6751510.55
      2727245.92      6751510.80      2727236.41      6751512.00
      2727227.50      6751514.63      2727216.33      6751521.79
      2727189.06      6751547.01      2727178.19      6751554.91
      2727174.27      6751556.83      2727165.31      6751559.34
      2727136.69      6751562.67      2727127.73      6751565.19
      2727120.08      6751569.47      2727112.96      6751575.04
      2727092.61      6751594.19      2727082.08      6751602.91
      2727074.45      6751607.25      2727065.50      6751609.80
      2727041.18      6751611.44      2726826.00      6751611.00

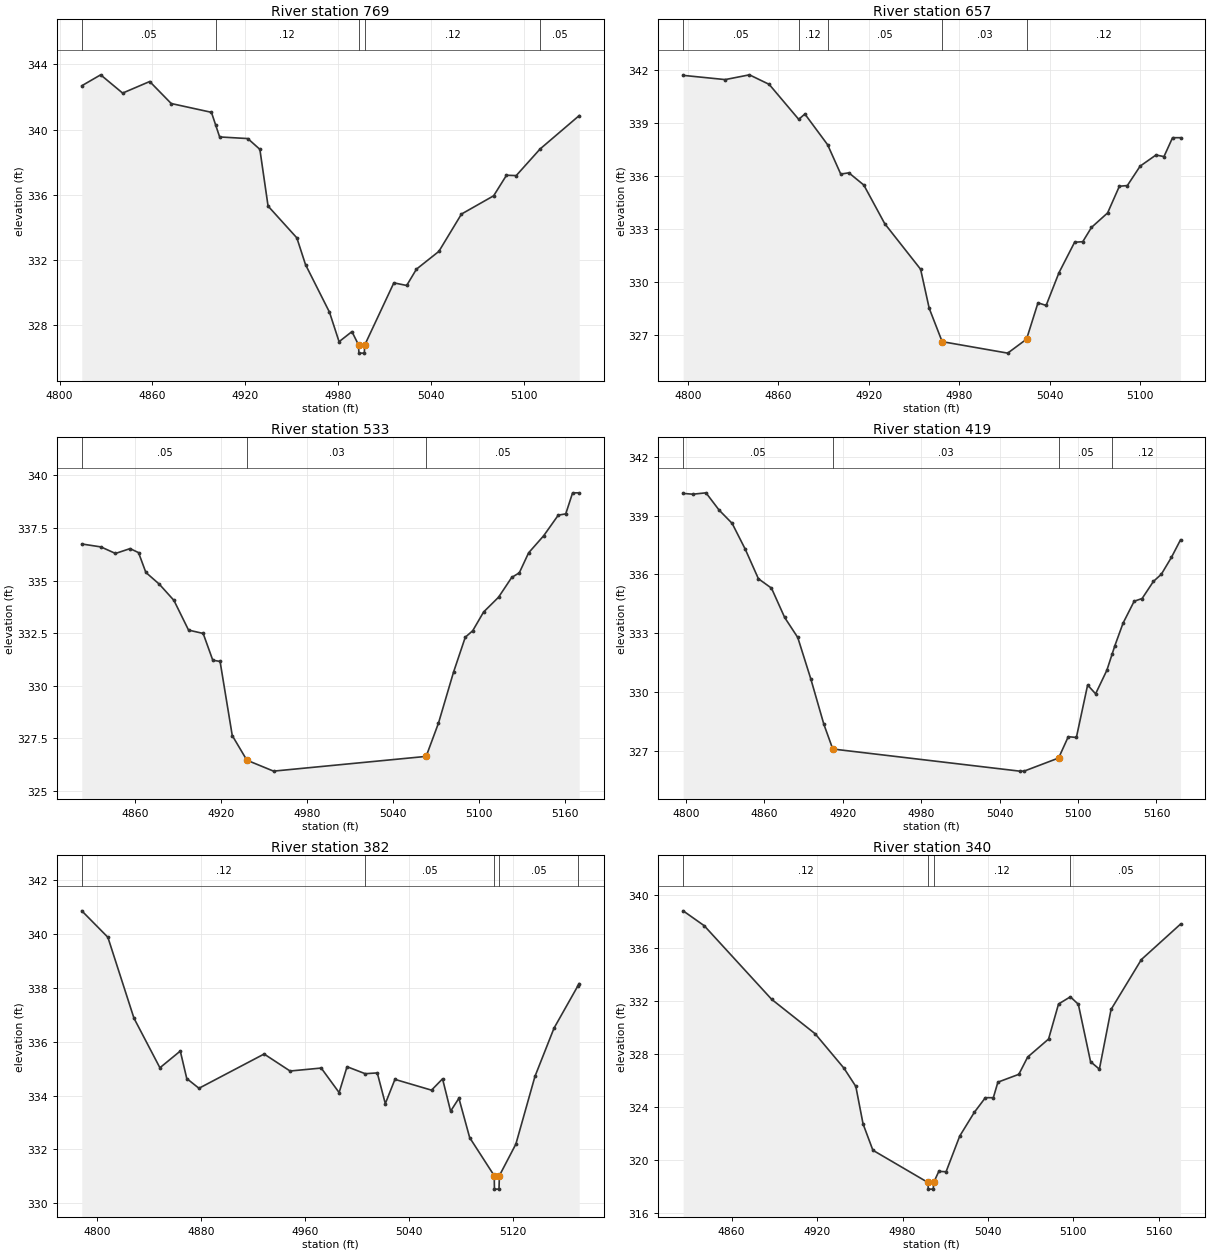
Type RM Length L Ch R = 1,769,112,112,112
BEGIN DESCRIPTION:
Walnut48 10.0
END DESCRIPTION:
XS GIS Cut Line= 3
      2727619.05      6751429.49      2727572.18      6751566.61
      2727465.68      6751707.47
#Sta/Elev= 30
  4814.4  342.69  4826.6  343.36  4840.8  342.24  4858.3  342.95  4872.2  341.60
  4898.2  341.06  4900.9  340.29  4903.5  339.55  4921.7  339.45  4929.5  338.79
  4934.8  335.31  4953.4  333.36  4959.0  331.72  4974.5  328.80  4980.7  326.99
  4989.0  327.61  4993.3  326.79  4993.5  326.29  4997.0  326.29  4997.3  326.79
  5016.1  330.60  5024.4  330.44  5030.7  331.44  5045.2  332.53  5059.8  334.82
  5080.6  335.94  5088.9  337.20  5095.2  337.18  5110.6  338.81  5135.9  340.86
#Mann=5,-1,0
  4814.4    0.05       0  4900.9    0.12       0  4993.3    0.07       0
  4997.3    0.12       0  5110.6    0.05       0
Bank Sta=4993.3,4997.3
Exp/Cntr=0.3,0.1

Type RM Length L Ch R = 1,657,124,124,124
BEGIN DESCRIPTION:
Walnut48 9.0
END DESCRIPTION:
XS GIS Cut Line= 3
      2727521.83      6751370.44      2727454.13      6751531.89
      2727396.85      6751675.94
#Sta/Elev= 30
  4796.8  341.71  4824.7  341.47  4840.8  341.74  4853.9  341.20  4873.5  339.22
  4877.6  339.52  4892.7  337.78  4901.4  336.12  4906.8  336.19  4916.7  335.50
  4930.6  333.31  4954.4  330.73  4960.1  328.52  4968.7  326.63  5012.2  325.98
  5024.7  326.77  5032.3  328.83  5037.7  328.68  5046.2  330.53  5056.6  332.26
  5062.0  332.29  5067.8  333.10  5078.5  333.92  5086.3  335.43  5091.6  335.47
  5100.1  336.57  5110.6  337.20  5115.9  337.11  5121.6  338.18  5126.9  338.18
#Mann=5,-1,0
  4796.8    0.05       0  4873.5    0.12       0  4892.7    0.05       0
  4968.7    0.03       0  5024.7    0.12       0
Bank Sta=4968.7,5024.7
Exp/Cntr=0.3,0.1

Type RM Length L Ch R = 1,533,114,114,114
BEGIN DESCRIPTION:
Walnut48 8.0
END DESCRIPTION:
XS GIS Cut Line= 3
      2727358.64      6751347.88      2727320.45      6751545.78
      2727363.86      6751684.70
#Sta/Elev= 30
  4823.0  336.74  4836.4  336.60  4846.5  336.29  4856.7  336.52  4862.6  336.33
  4867.7  335.39  4877.1  334.83  4887.3  334.06  4897.5  332.65  4907.7  332.49
  4914.4  331.22  4919.5  331.16  4928.0  327.64  4938.2  326.47  4956.8  325.95
  5063.3  326.65  5071.9  328.23  5082.4  330.65  5090.6  332.31  5095.8  332.62
  5103.4  333.51  5113.8  334.21  5123.0  335.15  5128.3  335.37  5134.8  336.32
  5145.3  337.13  5155.5  338.11  5160.7  338.17  5165.5  339.17  5170.1  339.17
#Mann=3,-1,0
  4823.0    0.05       0  4938.2    0.03       0  5063.3    0.05       0
Bank Sta=4938.2,5063.3
Exp/Cntr=0.3,0.1

Type RM Length L Ch R = 1,419,37,37,37
BEGIN DESCRIPTION:
Walnut48 7.0
END DESCRIPTION:
XS GIS Cut Line= 3
      2727219.75      6751323.57      2727205.86      6751507.59
      2727320.47      6751666.66
#Sta/Elev= 30
  4797.8  340.14  4805.3  340.10  4815.3  340.17  4825.3  339.29  4835.3  338.61
  4845.4  337.28  4855.4  335.78  4865.4  335.30  4875.5  333.80  4885.5  332.78
  4895.5  330.66  4905.5  328.34  4912.3  327.08  5055.2  325.95  5058.7  325.95
  5085.1  326.62  5092.5  327.71  5098.7  327.67  5107.3  330.35  5113.4  329.90
  5122.0  331.10  5126.1  331.94  5128.1  332.35  5134.4  333.51  5142.9  334.63
  5149.0  334.77  5157.6  335.64  5163.7  336.01  5171.4  336.87  5178.4  337.77
#Mann=4,-1,0
  4797.8    0.05       0  4912.3    0.03       0  5085.1    0.05       0
  5126.1    0.12       0
Bank Sta=4912.3,5085.1
Exp/Cntr=0.3,0.1

Type RM Length L Ch R = 1,382,42,42,42
BEGIN DESCRIPTION:
Walnut48 6.0
END DESCRIPTION:
XS GIS Cut Line= 3
      2727186.76      6751340.95      2727172.88      6751524.95
      2727289.07      6751686.23
#Sta/Elev= 30
  4788.1  340.85  4808.2  339.87  4828.3  336.87  4848.3  335.03  4864.0  335.65
  4869.0  334.63  4878.4  334.27  4928.6  335.54  4948.6  334.91  4972.6  335.02
  4986.4  334.11  4992.5  335.07  5006.5  334.81  5015.8  334.84  5022.0  333.70
  5029.4  334.60  5057.6  334.20  5066.1  334.62  5072.3  333.42  5078.7  333.90
  5087.0  332.44  5105.9  331.03  5106.1  330.53  5109.6  330.53  5109.9  331.03
  5122.6  332.20  5137.3  334.71  5152.0  336.50  5170.3  338.06  5171.4  338.15
#Mann=5,-1,0
  4788.1    0.12       0  5006.5    0.05       0  5105.9    0.07       0
  5109.9    0.05       0  5170.3    0.12       0
Bank Sta=5105.9,5109.9
Exp/Cntr=0.3,0.1

Type RM Length L Ch R = 1,340,102,102,102
BEGIN DESCRIPTION:
Walnut48 3.6
END DESCRIPTION:
XS GIS Cut Line= 3
      2727118.64      6751389.84      2727157.25      6751601.34
      2727235.37      6751710.71
#Sta/Elev= 30
  4825.9  338.77  4840.7  337.65  4888.1  332.10  4918.6  329.51  4938.9  326.91
  4947.2  325.54  4952.3  322.71  4959.2  320.73  4997.9  318.30  4998.1  317.80
  5001.6  317.80  5001.9  318.30  5005.5  319.14  5010.6  319.11  5020.2  321.80
  5030.4  323.58  5038.2  324.69  5043.8  324.69  5047.0  325.86  5061.7  326.45
  5067.9  327.75  5082.6  329.11  5089.6  331.75  5097.9  332.29  5103.5  331.73
  5112.1  327.40  5118.3  326.84  5126.5  331.34  5147.8  335.10  5175.3  337.77
#Mann=4,-1,0
  4825.9    0.12       0  4997.9    0.07       0  5001.9    0.12       0
  5097.9    0.05       0
Bank Sta=4997.9,5001.9
Exp/Cntr=0.3,0.1

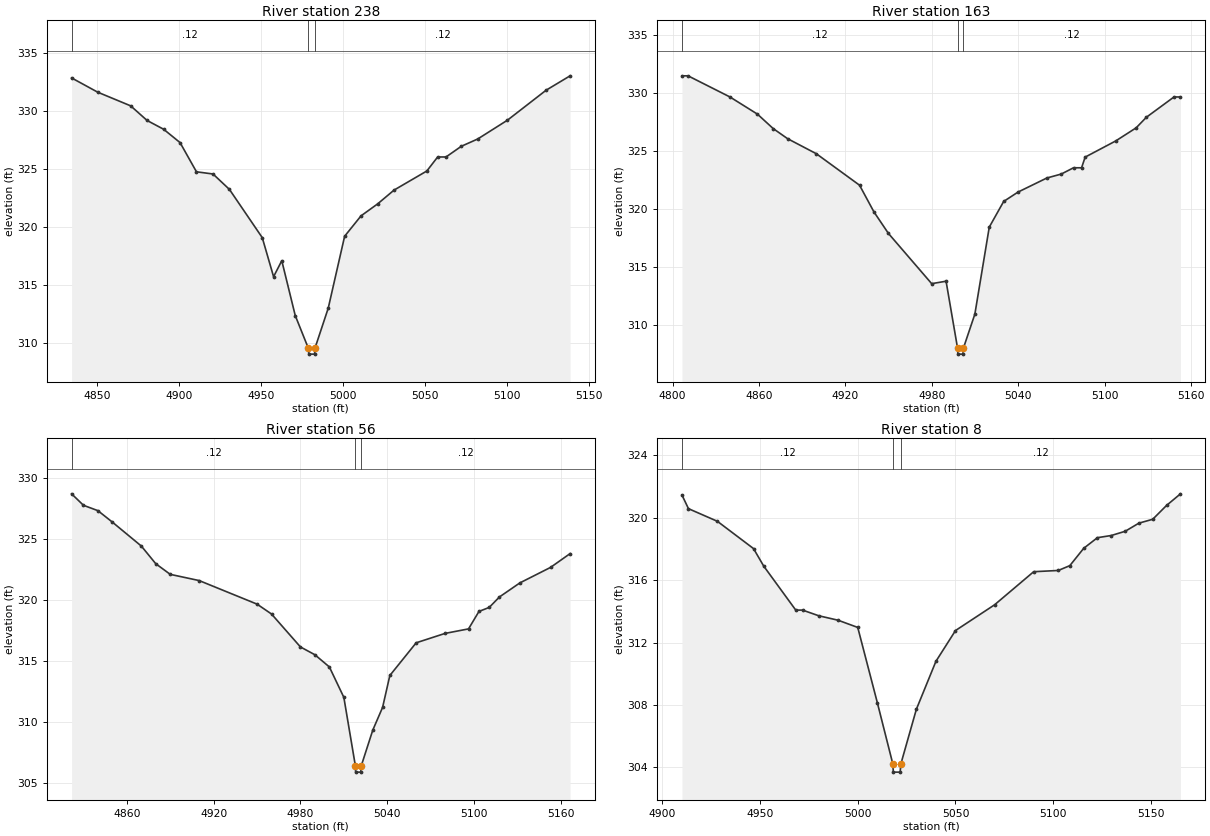
Type RM Length L Ch R = 1,238,75,75,75
BEGIN DESCRIPTION:
Walnut48 3.4
END DESCRIPTION:
XS GIS Cut Line= 3
      2727051.35      6751445.10      2727068.71      6751669.04
      2727091.15      6751744.98
#Sta/Elev= 30
  4834.6  332.85  4850.5  331.62  4870.6  330.44  4880.6  329.18  4890.7  328.42
  4900.7  327.27  4910.7  324.75  4920.8  324.56  4930.8  323.23  4950.8  319.07
  4957.7  315.70  4962.7  317.08  4970.9  312.35  4978.9  309.52  4979.2  309.02
  4982.7  309.02  4982.9  309.52  4991.0  312.98  5001.0  319.19  5011.0  320.95
  5021.1  321.98  5031.1  323.17  5051.1  324.82  5057.7  326.03  5062.8  326.03
  5072.1  326.95  5082.1  327.58  5100.2  329.20  5123.8  331.79  5138.4  333.03
#Mann=3,-1,0
  4834.6    0.12       0  4978.9    0.07       0  4982.9    0.12       0
Bank Sta=4978.9,4982.9
Exp/Cntr=0.3,0.1

Type RM Length L Ch R = 1,163,107,107,107
BEGIN DESCRIPTION:
Walnut48 3.0
END DESCRIPTION:
XS GIS Cut Line= 3
      2726991.91      6751417.67      2726987.48      6751693.16
      2727037.46      6751743.13
#Sta/Elev= 30
  4806.5  331.47  4810.7  331.47  4839.8  329.65  4858.9  328.17  4869.8  326.93
  4879.8  326.06  4899.8  324.76  4929.8  322.05  4939.8  319.75  4949.9  317.89
  4979.9  313.57  4989.9  313.78  4997.9  308.00  4998.1  307.50  5001.6  307.50
  5001.9  308.00  5009.9  310.95  5019.9  318.44  5029.9  320.65  5039.9  321.46
  5059.9  322.67  5069.9  323.01  5078.4  323.55  5084.0  323.55  5086.5  324.47
  5107.7  325.86  5121.9  326.99  5129.0  327.90  5148.2  329.65  5152.7  329.65
#Mann=3,-1,0
  4806.5    0.12       0  4997.9    0.07       0  5001.9    0.12       0
Bank Sta=4997.9,5001.9
Exp/Cntr=0.3,0.1

Type RM Length L Ch R = 1,56,48,48,48
BEGIN DESCRIPTION:
Walnut48 1.0
END DESCRIPTION:
XS GIS Cut Line= 3
      2726884.48      6751432.84      2726880.06      6751708.35
      2726928.89      6751757.18
#Sta/Elev= 30
  4821.8  328.70  4830.0  327.76  4840.0  327.32  4850.0  326.38  4870.0  324.42
  4880.0  322.97  4890.0  322.10  4910.0  321.59  4950.0  319.66  4960.0  318.85
  4980.0  316.15  4990.0  315.51  5000.0  314.51  5010.0  312.02  5018.0  306.39
  5018.2  305.89  5021.7  305.89  5022.0  306.39  5030.0  309.33  5036.8  311.20
  5041.8  313.81  5060.0  316.49  5080.0  317.26  5096.2  317.63  5103.4  319.06
  5110.5  319.39  5117.6  320.25  5131.7  321.40  5152.9  322.67  5166.4  323.80
#Mann=3,-1,0
  4821.8    0.12       0  5018.0    0.07       0  5022.0    0.12       0
Bank Sta=5018,5022
Exp/Cntr=0.3,0.1

Type RM Length L Ch R = 1,8,0,0,0
BEGIN DESCRIPTION:
Walnut48 0.2
END DESCRIPTION:
XS GIS Cut Line= 4
      2726852.16      6751523.63      2726834.69      6751582.81
      2726832.68      6751707.81      2726880.96      6751756.09
#Sta/Elev= 30
  4910.1  321.45  4913.4  320.58  4928.2  319.77  4946.7  318.02  4951.9  316.90
  4968.3  314.08  4971.8  314.08  4980.0  313.72  4990.0  313.43  5000.0  312.97
  5010.0  308.16  5018.0  304.20  5018.2  303.70  5021.7  303.70  5022.0  304.20
  5030.0  307.73  5040.0  310.80  5050.0  312.77  5070.0  314.42  5090.0  316.54
  5102.6  316.62  5108.5  316.93  5115.6  318.04  5122.6  318.72  5129.7  318.86
  5136.8  319.13  5143.8  319.65  5150.9  319.90  5158.0  320.79  5165.1  321.53
#Mann=3,-1,0
  4910.1    0.12       0  5018.0    0.07       0  5022.0    0.12       0
Bank Sta=5018,5022
Exp/Cntr=0.3,0.1

Chan Stop Cuts=-1