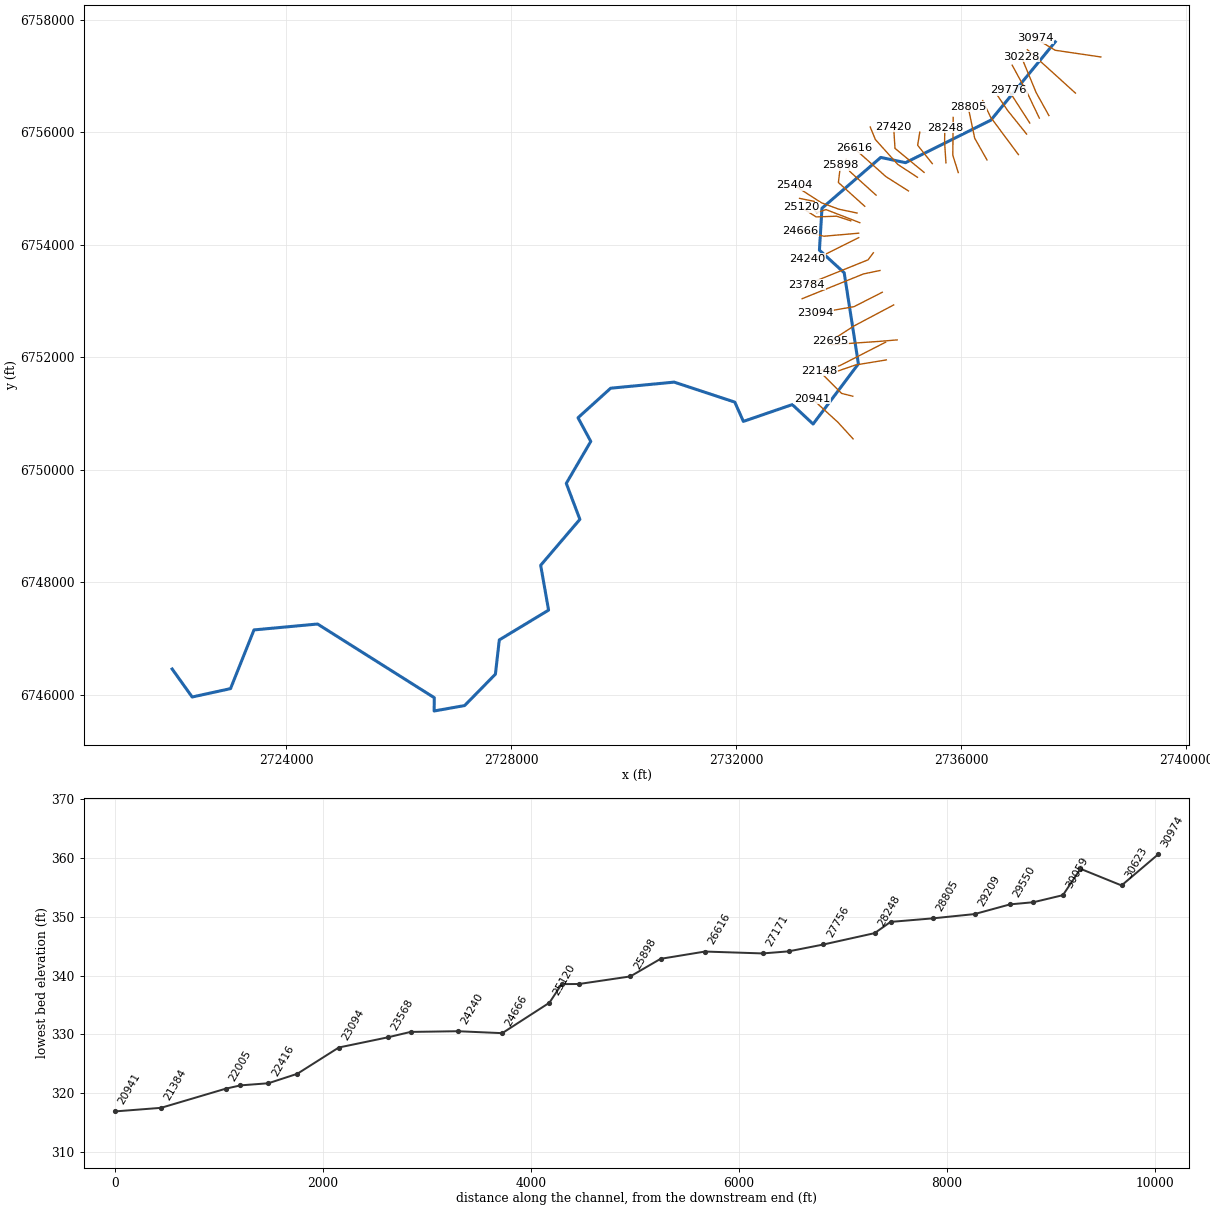
--- Walnut49.prj (project) ---

Proj Title=Walnut49 Base Level Engineering
Current Plan=p01
Default Exp/Contr=0.3,0.1
English Units
Geom File=g01
Flow File=f01
Plan File=p01
Y Axis Title=Elevation
X Axis Title(PF)=Main Channel Distance
X Axis Title(XS)=Station
BEGIN DESCRIPTION:
Walnut49
END DESCRIPTION:
DSS Export Rating Curves= 0
DSS Export Rating Curve Sorted= 0
DSS Export Volume Flow Curves= 0
DXF OffsetX= 0
DXF OffsetY= 0
DXF ScaleX= 1
DXF ScaleY= 10

--- Walnut49.p01 (plan) ---

Plan Title=Multiple Run
Program Version=4.10
Short Identifier=Multiple
Geom File=g01
Flow File=f01
Subcritical Flow
K Sum by GR= 0
Std Step Tol= 0.01
Critical Tol= 0.01
Num of Std Step Trials= 20
Max Error Tol= 0.3
Flow Tol Ratio= 0.001
Split Flow NTrial= 30
Split Flow Tol= 0.02
Split Flow Ratio= 0.02
Log Output Level= 0
Friction Slope Method= 1
Unsteady Friction Slope Method= 2
Unsteady Bridges Friction Slope Method= 1
Parabolic Critical Depth
Global Vel Dist= 1 , 1 , 1
Global Log Level= 0
CheckData=True
Encroach Param=-1 ,0,0, 0
BEGIN DESCRIPTION:
Multiple Run
END DESCRIPTION:
Computation Interval=1HOUR
Output Interval=1HOUR
Run HTab= 0
Run UNet= 0
Run PostProcess= 0
Run WQNet= 0
UNET Theta= 1
UNET Theta Warmup= 1
UNET ZTol= 0.02
UNET ZSATol= 0.05
UNET MxIter= 20
UNET MaxInSteps= 0
UNET DtIC= 0
UNET DtMin= 0
UNET MaxCRTS= 20
UNET WFStab= 2
UNET SFStab= 1
UNET WFX= 1
UNET SFX= 1
UNET DSS MLevel= 4
UNET DZMax Abort= 100
UNET Convert EG Bridges= 0
UNET Use Existing IB Tables=-1
UNET Froude Reduction=False
UNET Froude Limit= 1
UNET Froude Power= 10
UNET Time Slicing=0,0, 5
UNET Junction Losses=0
Instantaneous Interval=1HOUR
Write IC File= 0
Write IC File at Sim End=0
Echo Input=False
Echo Parameters=False
Echo Output=False
Write Detailed= 0
WQ AD Non Conservative
WQ ULTIMATE=-1
WQ Max Comp Step=1HOUR
WQ Output Interval=15MIN
WQ Output Selected Increments= 0
WQ Output face flow=0
WQ Output face velocity=0
WQ Output face area=0
WQ Output face dispersion=0
WQ Output cell volume=0
WQ Output cell surface area=0
WQ Output cell continuity=0
WQ Output cumulative cell continuity=0
WQ Output face conc=0
WQ Output face dconc_dx=0
WQ Output face courant=0
WQ Output face peclet=0
WQ Output face adv mass=0
WQ Output face disp mass=0
WQ Output cell mass=0
WQ Output cell source sink temp=0
WQ Output cell source sink nsm=0
WQ Output MaxMinRange=-1
WQ Daily Max Min Mean=-1
WQ Daily Range=0
WQ Daily Time=0
WQ Create Restart=0
WQ Fixed Restart=0
WQ System Summary=0
WQ Use Fixed Temperature=0
Sorting and Armoring Iterations= 10
XS Update Threshold= 0.02
Hydraulics Update Threshold= 0.02
Energy Slope Method= 1
Volume Change Method= 0
XS Weighting Method= 0
Number of US Weighted Cross Sections= 1
Number of DS Weighted Cross Sections= 1
Upstream XS Weight=0.25
Main XS Weight=0.5
Downstream XS Weight=0.25
Number of DS XS's Weighted with US Boundary= 1
Upstream Boundary Weight= 1
Weight of XSs Associated with US Boundary= 0
Number of US XS's Weighted with DS Boundary= 1
Downstream Boundary Weight= 0.5
Weight of XSs Associated with DS Boundary= 0.5
Sediment Output Level= 4
Mass or Volume Output= 0
Output Increment Type= 1
Profile and TS Output Increment= 10
XS Output Flag= 0
XS Output Increment= 10
Disregard all LS=0
Disregard all Conn=0
Disregard all Breaches=0
Disregard all Pumps=0

--- Walnut49.f01 (steady flow) ---

Flow Title=Multiple
Number of Profiles=7
Profile Names=10-year,25-year,50-year,1pct_min,100-year,1pct_plu,500-year
River Rch & RM= Walnut49,Reach-1,30974
     347     450     531     311     621    1238     850
River Rch & RM= Walnut49,Reach-1,27420
     526     699     838     499     995    1985    1406
River Rch & RM= Walnut49,Reach-1,25404
     770    1049    1278     773    1543    3078    2252
River Rch & RM= Walnut49,Reach-1,22148
     838    1140    1388     837    1670    3333    2427
River Rch & RM= Walnut49,Reach-1,17164
     614     806     957     562    1122    2239    1547
River Rch & RM= Walnut49,Reach-1,15916
    1072    1481    1821    1110    2214    4417    3282
River Rch & RM= Walnut49,Reach-1,13191
    1012    1386    1694    1026    2047    4084    2998
River Rch & RM= Walnut49,Reach-1,10990
    1139    1569    1926    1170    2335    4660    3445
River Rch & RM= Walnut49,Reach-1,7806
    1089    1482    1804    1086    2167    4323    3137
Boundary for River Rch & Prof#=Walnut49,Reach-1,1
Up Type=0
Dn Type=3
Dn Slope=0.005
Boundary for River Rch & Prof#=Walnut49,Reach-1,2
Up Type=0
Dn Type=3
Dn Slope=0.005
Boundary for River Rch & Prof#=Walnut49,Reach-1,3
Up Type=0
Dn Type=3
Dn Slope=0.005
Boundary for River Rch & Prof#=Walnut49,Reach-1,4
Up Type=0
Dn Type=3
Dn Slope=0.005
Boundary for River Rch & Prof#=Walnut49,Reach-1,5
Up Type=0
Dn Type=3
Dn Slope=0.005
Boundary for River Rch & Prof#=Walnut49,Reach-1,6
Up Type=0
Dn Type=3
Dn Slope=0.005
Boundary for River Rch & Prof#=Walnut49,Reach-1,7
Up Type=0
Dn Type=3
Dn Slope=0.005

--- Walnut49.g01 (geometry) ---

Geom Title=Existing Conditions

River Reach=Walnut49,Reach-1
Reach XY= 30
      2737676.00      6757611.00      2736532.05      6756219.16
      2735014.44      6755462.57      2734573.71      6755555.94
      2733528.61      6754652.53      2733483.59      6753907.65
      2733923.76      6753505.07      2734176.49      6751885.96
      2733370.92      6750816.03      2733001.10      6751161.63
      2732131.65      6750862.97      2731978.70      6751205.64
      2730901.10      6751561.21      2729772.57      6751453.21
      2729191.40      6750927.78      2729418.52      6750507.42
      2728982.98      6749760.79      2729224.80      6749121.50
      2728527.80      6748304.89      2728668.21      6747507.57
      2727792.24      6746978.22      2727722.97      6746369.01
      2727176.00      6745811.00      2726634.03      6745714.37
      2726636.22      6745950.62      2724560.85      6747260.62
      2723431.18      6747155.86      2723014.01      6746112.17
      2722331.84      6745963.05      2721976.00      6746461.00

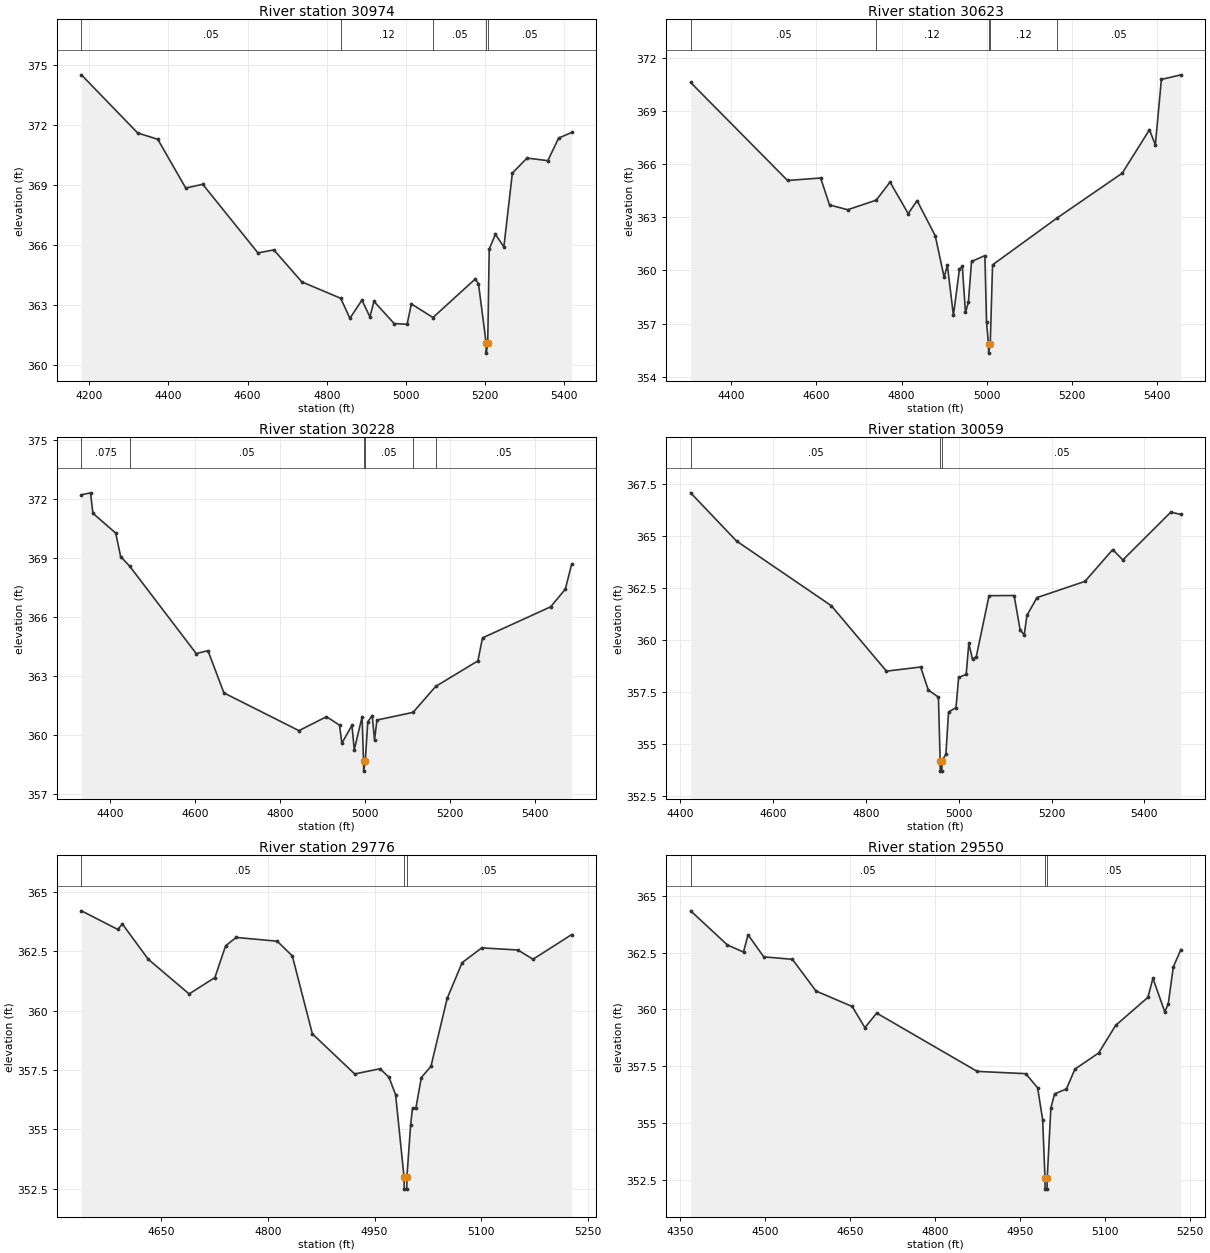
Type RM Length L Ch R = 1,30974,351,351,351
BEGIN DESCRIPTION:
Walnut49 61.0
END DESCRIPTION:
XS GIS Cut Line= 3
      2738486.65      6757341.89      2737676.00      6757461.00
      2737316.53      6757675.20
#Sta/Elev= 30
  4180.7  374.51  4322.9  371.60  4373.4  371.29  4444.1  368.85  4486.9  369.04
  4626.4  365.61  4666.5  365.76  4737.3  364.16  4835.4  363.34  4858.5  362.34
  4888.9  363.25  4909.1  362.41  4919.2  363.19  4970.2  362.08  5003.0  362.04
  5013.7  363.06  5068.3  362.38  5174.7  364.30  5183.1  364.08  5202.5  361.10
  5202.7  360.60  5206.5  361.10  5210.3  365.80  5225.9  366.54  5247.3  365.91
  5268.7  369.60  5305.7  370.35  5358.3  370.22  5385.5  371.35  5418.5  371.63
#Mann=5,-1,0
  4180.7    0.05       0  4835.4    0.12       0  5068.3    0.05       0
  5202.5    0.07       0  5206.5    0.05       0
Bank Sta=5202.5,5206.5
Exp/Cntr=0.3,0.1

Type RM Length L Ch R = 1,30623,395,395,395
BEGIN DESCRIPTION:
Walnut49 60.0
END DESCRIPTION:
XS GIS Cut Line= 3
      2738035.28      6756699.50      2737526.00      6757161.00
      2737181.09      6757470.36
#Sta/Elev= 30
  4305.0  370.60  4532.4  365.07  4610.1  365.21  4631.0  363.69  4673.6  363.42
  4740.5  363.96  4773.0  364.98  4815.6  363.20  4836.5  363.93  4879.1  361.95
  4900.0  359.60  4907.5  360.30  4921.7  357.46  4935.8  360.06  4942.6  360.22
  4950.0  357.63  4956.8  358.19  4964.2  360.50  4995.6  360.83  4999.4  357.08
  5004.1  355.83  5004.3  355.33  5008.1  355.83  5013.6  360.31  5164.2  362.94
  5317.8  365.48  5381.8  367.93  5395.6  367.08  5409.8  370.77  5455.6  371.03
#Mann=5,-1,0
  4305.0    0.05       0  4740.5    0.12       0  5004.1    0.07       0
  5008.1    0.12       0  5164.2    0.05       0
Bank Sta=5004.1,5008.1
Exp/Cntr=0.3,0.1

Type RM Length L Ch R = 1,30228,169,169,169
BEGIN DESCRIPTION:
Walnut49 59.0
END DESCRIPTION:
XS GIS Cut Line= 3
      2737563.02      6756300.24      2737337.34      6756706.47
      2737073.43      6757345.40
#Sta/Elev= 30
  4331.7  372.22  4353.1  372.32  4358.8  371.28  4412.6  370.27  4424.1  369.08
  4445.4  368.59  4602.5  364.14  4630.0  364.29  4667.7  362.14  4844.6  360.22
  4909.5  360.93  4940.3  360.50  4945.7  359.58  4969.6  360.49  4975.0  359.25
  4993.5  360.92  4996.9  358.66  4997.2  358.16  5000.9  358.66  5006.9  360.67
  5017.4  360.99  5022.8  359.75  5028.5  360.76  5113.7  361.15  5167.0  362.47
  5266.5  363.77  5277.4  364.94  5438.0  366.52  5472.7  367.42  5487.7  368.70
#Mann=6,-1,0
  4331.7   0.075       0  4445.4    0.05       0  4996.9    0.05       0
  5000.9    0.05       0  5113.7    0.12       0  5167.0    0.05       0
Bank Sta=4996.9,5000.9
Exp/Cntr=0.3,0.1

Type RM Length L Ch R = 1,30059,283,283,283
BEGIN DESCRIPTION:
Walnut49 58.0
END DESCRIPTION:
XS GIS Cut Line= 3
      2737392.91      6756255.06      2737177.62      6756706.47
      2736910.66      6757195.31
#Sta/Elev= 30
  4421.9  367.07  4520.9  364.75  4725.2  361.64  4844.2  358.49  4917.8  358.69
  4934.4  357.58  4956.2  357.24  4959.9  354.18  4960.1  353.68  4963.6  353.68
  4963.9  354.18  4972.3  354.50  4978.0  356.52  4994.1  356.74  4999.8  358.19
  5016.0  358.33  5021.7  359.83  5029.7  359.06  5037.8  359.19  5065.3  362.12
  5119.4  362.13  5132.3  360.48  5141.2  360.23  5146.9  361.17  5168.7  362.03
  5272.2  362.81  5332.0  364.34  5353.8  363.84  5457.2  366.14  5479.0  366.03
#Mann=3,-1,0
  4421.9    0.05       0  4959.9    0.05       0  4963.9    0.05       0
Bank Sta=4959.9,4963.9
Exp/Cntr=0.3,0.1

Type RM Length L Ch R = 1,29776,226,226,226
BEGIN DESCRIPTION:
Walnut49 57.5
END DESCRIPTION:
XS GIS Cut Line= 3
      2737222.76      6756168.28      2736969.28      6756560.64
      2736848.44      6756747.09
#Sta/Elev= 30
  4537.8  364.20  4588.7  363.42  4595.5  363.64  4631.8  362.16  4689.2  360.70
  4725.4  361.39  4740.6  362.73  4755.3  363.08  4813.2  362.92  4834.3  362.30
  4862.5  359.02  4922.0  357.33  4957.7  357.55  4970.2  357.19  4979.5  356.46
  4991.4  352.98  4991.7  352.48  4995.2  352.48  4995.4  352.98  5000.6  355.17
  5003.3  355.90  5008.1  355.90  5015.7  357.18  5029.2  357.65  5052.0  360.51
  5073.1  362.02  5100.7  362.64  5151.6  362.55  5172.7  362.16  5227.1  363.20
#Mann=3,-1,0
  4537.8    0.05       0  4991.4    0.04       0  4995.4    0.05       0
Bank Sta=4991.4,4995.4
Exp/Cntr=0.3,0.1

Type RM Length L Ch R = 1,29550,341,341,341
BEGIN DESCRIPTION:
Walnut49 57.0
END DESCRIPTION:
XS GIS Cut Line= 3
      2737167.22      6755970.34      2736826.92      6756393.97
      2736646.37      6756661.33
#Sta/Elev= 30
  4368.6  364.33  4433.6  362.83  4462.0  362.52  4470.0  363.28  4497.7  362.31
  4548.4  362.20  4590.0  360.81  4654.0  360.13  4676.4  359.20  4697.2  359.84
  4874.8  357.28  4960.5  357.18  4981.5  356.56  4990.4  355.16  4994.5  352.61
  4994.7  352.11  4998.2  352.11  4998.5  352.61  5004.9  355.67  5011.4  356.29
  5032.4  356.51  5047.4  357.38  5089.4  358.09  5119.3  359.30  5176.3  360.53
  5185.2  361.37  5206.2  359.89  5212.3  360.25  5221.2  361.87  5234.6  362.63
#Mann=3,-1,0
  4368.6    0.05       0  4994.5    0.04       0  4998.5    0.05       0
Bank Sta=4994.5,4998.5
Exp/Cntr=0.3,0.1

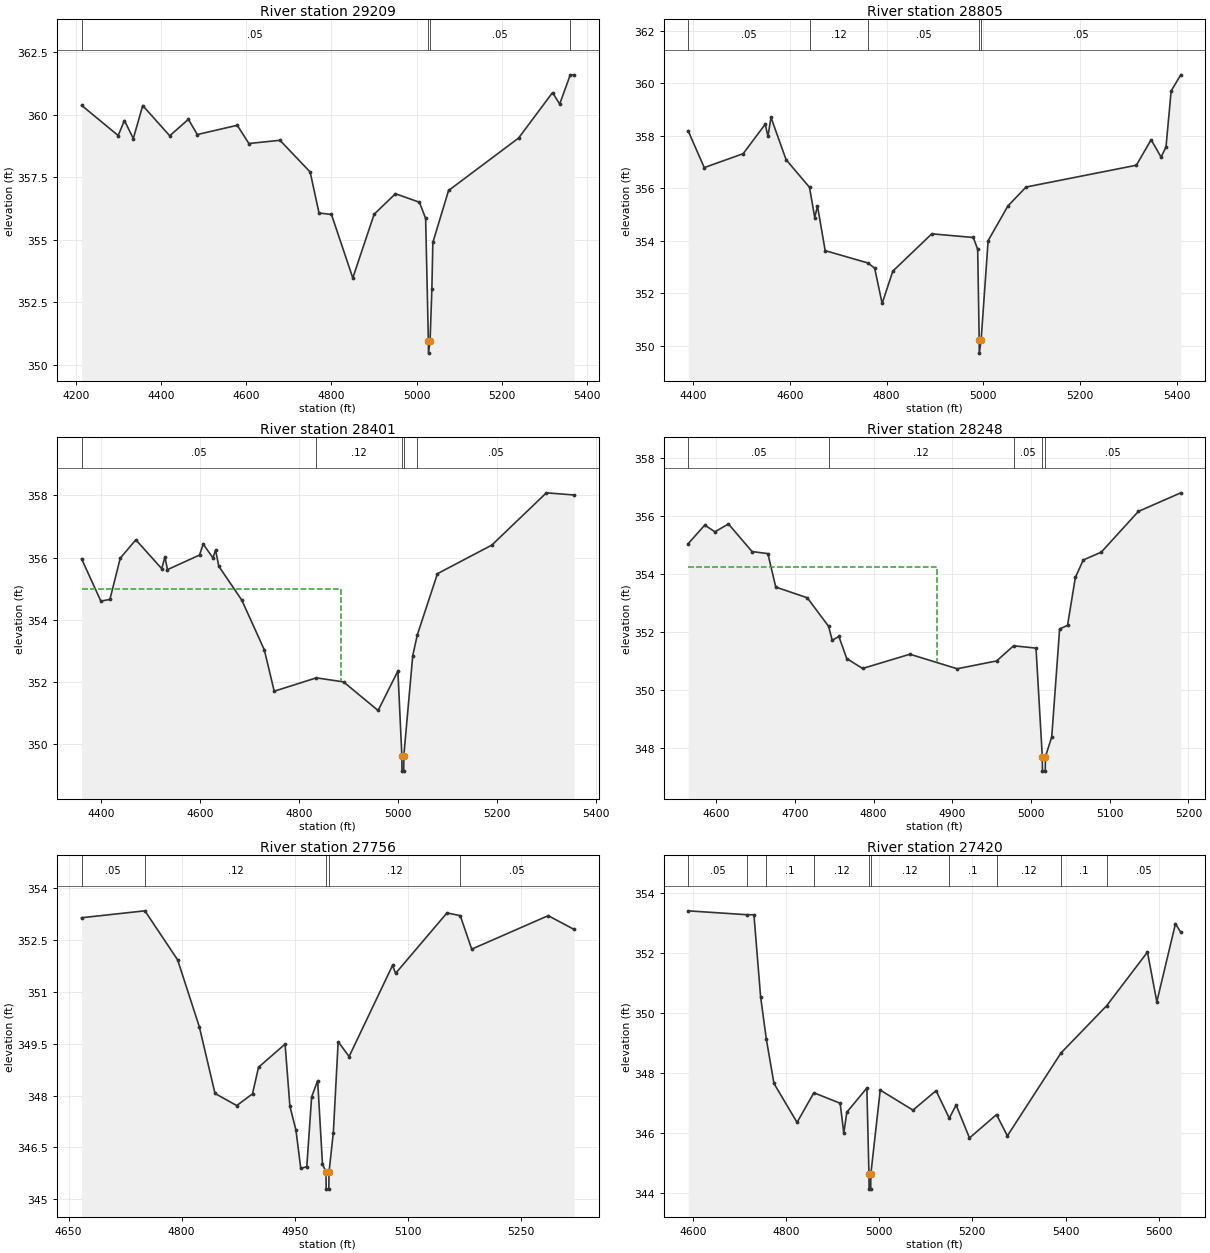
Type RM Length L Ch R = 1,29209,404,404,404
BEGIN DESCRIPTION:
Walnut49 56.0
END DESCRIPTION:
XS GIS Cut Line= 3
      2737021.40      6755605.74      2736528.31      6756268.97
      2736386.32      6756566.81
#Sta/Elev= 30
  4213.7  360.38  4299.7  359.17  4314.3  359.77  4335.2  359.05  4357.3  360.37
  4420.7  359.16  4464.5  359.82  4485.4  359.21  4579.2  359.58  4606.5  358.85
  4679.4  358.98  4750.3  357.71  4771.1  356.07  4800.3  356.01  4850.4  353.47
  4900.5  356.02  4950.5  356.84  5006.8  356.50  5021.4  355.85  5027.8  350.96
  5028.1  350.46  5031.8  350.96  5036.0  353.01  5038.3  354.89  5075.2  356.97
  5239.6  359.07  5319.3  360.89  5336.0  360.43  5360.9  361.60  5370.1  361.60
#Mann=4,-1,0
  4213.7    0.05       0  5027.8    0.04       0  5031.8    0.05       0
  5360.9    0.12       0
Bank Sta=5027.8,5031.8
Exp/Cntr=0.3,0.1

Type RM Length L Ch R = 1,28805,404,404,404
BEGIN DESCRIPTION:
Walnut49 55.0
END DESCRIPTION:
XS GIS Cut Line= 3
      2736462.32      6755512.06      2736243.59      6755897.44
      2736126.01      6756460.97
#Sta/Elev= 30
  4389.6  358.19  4422.9  356.79  4503.4  357.32  4549.0  358.44  4554.7  357.98
  4560.9  358.70  4592.2  357.09  4640.6  356.04  4651.4  354.89  4657.1  355.33
  4673.0  353.63  4761.5  353.16  4775.4  352.96  4790.8  351.62  4812.9  352.85
  4893.5  354.27  4979.4  354.13  4988.4  353.68  4991.5  350.23  4991.7  349.73
  4995.5  350.23  5010.0  354.01  5050.9  355.33  5088.4  356.05  5316.5  356.88
  5347.1  357.85  5367.6  357.19  5377.8  357.57  5388.5  359.71  5408.4  360.32
#Mann=5,-1,0
  4389.6    0.05       0  4640.6    0.12       0  4761.5    0.05       0
  4991.5    0.04       0  4995.5    0.05       0
Bank Sta=4991.5,4995.5
Exp/Cntr=0.3,0.1

Type RM Length L Ch R = 1,28401,153,153,153
BEGIN DESCRIPTION:
Walnut49 54.0
END DESCRIPTION:
XS GIS Cut Line= 3
      2735951.93      6755286.30      2735854.70      6755595.36
      2735861.63      6756267.53
#Sta/Elev= 30
  4360.6  355.96  4399.6  354.60  4417.9  354.65  4438.9  355.98  4470.4  356.57
  4522.8  355.64  4529.2  356.02  4534.4  355.61  4599.2  356.08  4606.6  356.43
  4626.3  355.99  4631.6  356.24  4638.1  355.72  4684.6  354.63  4730.2  353.03
  4750.2  351.70  4835.4  352.13  4890.3  352.00  4960.3  351.08  5000.3  352.35
  5008.3  349.63  5008.5  349.13  5012.0  349.13  5012.3  349.63  5030.3  352.84
  5039.5  353.51  5080.3  355.48  5190.3  356.40  5300.5  358.08  5356.8  358.01
#Mann=5,-1,0
  4360.6    0.05       0  4835.4    0.12       0  5008.3    0.07       0
  5012.3    0.12       0  5039.5    0.05       0
#XS Ineff=2,0
    0.00 4885.00  355.00               0
Permanent Ineff=
       F       F
Bank Sta=5008.3,5012.3
Exp/Cntr=0.3,0.1

Type RM Length L Ch R = 1,28248,492,492,492
BEGIN DESCRIPTION:
Walnut49 53.8
END DESCRIPTION:
XS GIS Cut Line= 3
      2735733.17      6755459.95      2735708.87      6755817.58
      2735712.34      6756084.90
#Sta/Elev= 30
  4564.5  355.04  4585.6  355.68  4598.6  355.45  4615.7  355.72  4645.7  354.77
  4665.8  354.70  4675.8  353.55  4715.9  353.18  4742.9  352.20  4747.5  351.72
  4756.0  351.85  4766.0  351.09  4786.1  350.75  4846.2  351.24  4906.3  350.74
  4956.4  351.01  4977.9  351.53  5006.4  351.45  5014.4  347.72  5014.6  347.22
  5018.1  347.22  5018.4  347.72  5026.4  348.40  5036.4  352.11  5046.4  352.23
  5056.4  353.88  5066.4  354.48  5089.3  354.75  5136.4  356.15  5190.3  356.79
#Mann=5,-1,0
  4564.5    0.05       0  4742.9    0.12       0  4977.9    0.05       0
  5014.4    0.04       0  5018.4    0.05       0
#XS Ineff=2,0
    0.00 4880.00  354.25               0
Permanent Ineff=
       F       F
Bank Sta=5014.4,5018.4
Exp/Cntr=0.3,0.1

Type RM Length L Ch R = 1,27756,336,336,336
BEGIN DESCRIPTION:
Walnut49 53.0
END DESCRIPTION:
XS GIS Cut Line= 3
      2735490.13      6755446.04      2735229.70      6755772.44
      2735267.89      6756005.06
#Sta/Elev= 30
  4667.3  353.15  4751.3  353.35  4794.7  351.93  4823.5  349.99  4844.3  348.06
  4873.1  347.71  4894.0  348.05  4902.0  348.82  4937.2  349.49  4943.6  347.69
  4951.6  347.00  4958.0  345.89  4966.0  345.94  4972.4  347.96  4980.4  348.43
  4986.8  346.01  4991.5  345.79  4991.7  345.29  4995.2  345.29  4995.5  345.79
  5001.2  346.93  5007.6  349.56  5022.1  349.13  5079.7  351.77  5083.8  351.54
  5151.9  353.29  5169.5  353.21  5184.7  352.24  5286.1  353.21  5320.6  352.81
#Mann=5,-1,0
  4667.3    0.05       0  4751.3    0.12       0  4991.5    0.07       0
  4995.5    0.12       0  5169.5    0.05       0
Bank Sta=4991.5,4995.5
Exp/Cntr=0.3,0.1

Type RM Length L Ch R = 1,27420,249,249,249
BEGIN DESCRIPTION:
Walnut49 52.6
END DESCRIPTION:
XS GIS Cut Line= 3
      2735344.30      6755289.79      2734826.92      6755716.89
      2734802.62      6756102.33
#Sta/Elev= 30
  4590.1  353.42  4716.3  353.29  4731.3  353.29  4745.6  350.55  4757.8  349.14
  4774.3  347.65  4823.8  346.35  4859.9  347.34  4916.3  346.99  4924.1  345.99
  4930.6  346.69  4973.6  347.50  4978.1  344.62  4978.4  344.12  4981.9  344.12
  4982.1  344.62  5002.3  347.43  5072.6  346.76  5122.1  347.41  5150.5  346.49
  5165.1  346.93  5193.8  345.83  5251.8  346.61  5275.1  345.90  5390.2  348.67
  5488.2  350.25  5575.7  352.04  5595.8  350.38  5635.8  352.99  5647.2  352.70
#Mann=10,-1,0
  4590.1    0.05       0  4716.3    0.12       0  4757.8     0.1       0
  4859.9    0.12       0  4978.1    0.07       0  4982.1    0.12       0
  5150.5     0.1       0  5251.8    0.12       0  5390.2     0.1       0
  5488.2    0.05       0
Bank Sta=4978.1,4982.1
Exp/Cntr=0.3,0.1

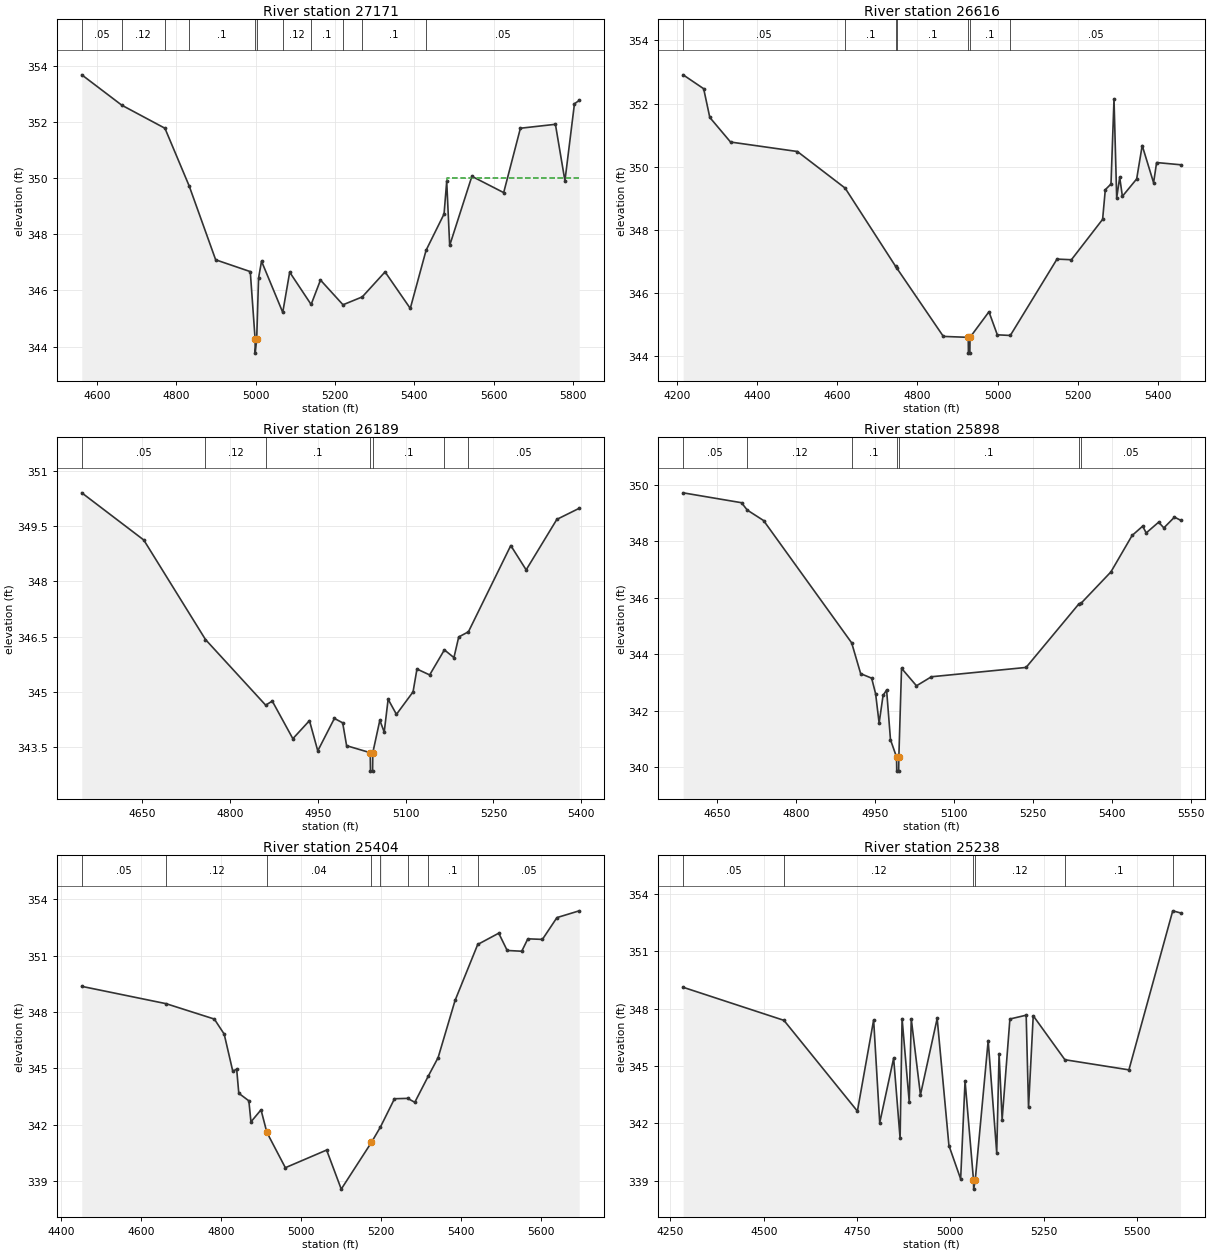
Type RM Length L Ch R = 1,27171,555,555,555
BEGIN DESCRIPTION:
Walnut49 52.3
END DESCRIPTION:
XS GIS Cut Line= 4
      2735226.27      6755202.97      2734875.53      6755432.16
      2734477.70      6755874.46      2734386.55      6756097.37
#Sta/Elev= 30
  4561.4  353.67  4662.3  352.59  4771.1  351.77  4832.2  349.72  4899.1  347.09
  4986.4  346.67  4998.6  344.27  4998.8  343.77  5002.6  344.27  5007.3  346.44
  5014.8  347.04  5068.3  345.22  5085.8  346.65  5139.9  345.50  5163.5  346.37
  5220.3  345.49  5268.9  345.77  5326.4  346.66  5390.0  345.36  5429.9  347.43
  5475.2  348.72  5481.9  349.88  5489.4  347.60  5545.4  350.06  5625.6  349.48
  5667.8  351.77  5756.1  351.91  5780.1  349.90  5804.1  352.64  5816.1  352.76
#Mann=11,-1,0
  4561.4    0.05       0  4662.3    0.12       0  4771.1    0.05       0
  4832.2     0.1       0  4998.6    0.07       0  5002.6     0.1       0
  5068.3    0.12       0  5139.9     0.1       0  5220.3    0.12       0
  5268.9     0.1       0  5429.9    0.05       0
#XS Ineff=2,0
       0                 5481.90    0.00  350.00
Permanent Ineff=
       F       F
Bank Sta=4998.6,5002.6
Exp/Cntr=0.3,0.1

Type RM Length L Ch R = 1,26616,427,427,427
BEGIN DESCRIPTION:
Walnut49 52.0
END DESCRIPTION:
XS GIS Cut Line= 3
      2735066.47      6754959.96      2734667.20      6755213.41
      2734094.31      6755723.81
#Sta/Elev= 30
  4216.1  352.91  4267.3  352.47  4282.6  351.56  4334.3  350.78  4500.9  350.48
  4620.0  349.32  4745.9  346.84  4749.1  346.78  4864.9  344.62  4927.0  344.59
  4927.4  344.09  4931.0  344.09  4931.4  344.59  4978.6  345.40  4999.5  344.67
  5031.9  344.65  5148.3  347.07  5184.2  347.05  5262.0  348.33  5268.7  349.27
  5282.9  349.45  5290.4  352.14  5297.1  349.01  5304.6  349.66  5311.3  349.06
  5346.9  349.61  5360.7  350.67  5389.1  349.49  5396.6  350.13  5456.3  350.06
#Mann=7,-1,0
  4216.1    0.05       0  4620.0     0.1       0  4745.9    0.12       0
  4749.1     0.1       0  4927.0    0.07       0  4931.4     0.1       0
  5031.9    0.05       0
Bank Sta=4927,4931.4
Exp/Cntr=0.3,0.1

Type RM Length L Ch R = 1,26189,291,291,291
BEGIN DESCRIPTION:
Walnut49 51.5
END DESCRIPTION:
XS GIS Cut Line= 3
      2734490.32      6754885.52      2734021.75      6755308.01
      2733955.86      6755517.48
#Sta/Elev= 30
  4546.2  350.40  4652.2  349.12  4757.7  346.42  4860.6  344.64  4871.9  344.75
  4907.1  343.73  4935.5  344.22  4949.7  343.40  4978.1  344.28  4992.3  344.16
  4999.0  343.54  5039.4  343.35  5039.8  342.85  5043.4  342.85  5043.8  343.35
  5055.8  344.23  5063.3  343.91  5070.0  344.80  5084.2  344.39  5112.6  345.00
  5119.3  345.62  5141.0  345.46  5166.2  346.14  5182.5  345.93  5190.7  346.49
  5207.3  346.63  5279.7  348.97  5306.0  348.31  5358.5  349.68  5396.7  349.98
#Mann=7,-1,0
  4546.2    0.05       0  4757.7    0.12       0  4860.6     0.1       0
  5039.4    0.07       0  5043.8     0.1       0  5166.2    0.12       0
  5207.3    0.05       0
Bank Sta=5039.4,5043.8
Exp/Cntr=0.3,0.1

Type RM Length L Ch R = 1,25898,494,494,494
BEGIN DESCRIPTION:
Walnut49 51.3
END DESCRIPTION:
XS GIS Cut Line= 3
      2734288.93      6754687.60      2733820.36      6755110.09
      2733858.76      6755422.42
#Sta/Elev= 30
  4585.0  349.71  4696.0  349.36  4706.9  349.10  4737.9  348.73  4905.4  344.40
  4922.5  343.31  4943.4  343.15  4950.9  342.60  4957.6  341.56  4965.1  342.54
  4971.8  342.73  4979.2  340.97  4990.7  340.36  4991.1  339.86  4994.7  339.86
  4995.1  340.36  5000.2  343.50  5028.6  342.88  5057.0  343.20  5237.0  343.53
  5337.4  345.78  5341.4  345.80  5398.2  346.91  5438.5  348.20  5458.6  348.53
  5465.3  348.29  5488.9  348.67  5498.9  348.47  5519.1  348.85  5530.6  348.74
#Mann=7,-1,0
  4585.0    0.05       0  4706.9    0.12       0  4905.4     0.1       0
  4990.7    0.07       0  4995.1     0.1       0  5337.4    0.12       0
  5341.4    0.05       0
Bank Sta=4990.7,4995.1
Exp/Cntr=0.3,0.1

Type RM Length L Ch R = 1,25404,166,166,166
BEGIN DESCRIPTION:
Walnut49 51.2
END DESCRIPTION:
XS GIS Cut Line= 4
      2734153.23      6754567.29      2733825.48      6754636.43
      2733520.80      6754749.08      2733030.15      6755063.41
#Sta/Elev= 30
  4452.0  349.36  4662.4  348.44  4783.1  347.62  4807.7  346.82  4829.1  344.85
  4838.9  344.95  4844.2  343.67  4869.3  343.27  4874.6  342.15  4899.7  342.79
  4914.3  341.59  4960.5  339.71  5063.6  340.65  5100.1  338.57  5175.6  341.06
  5198.1  341.88  5233.1  343.38  5266.0  343.40  5283.8  343.19  5317.4  344.58
  5342.1  345.57  5384.4  348.61  5441.0  351.59  5493.5  352.19  5514.6  351.27
  5551.0  351.23  5566.2  351.89  5602.6  351.86  5638.9  353.02  5694.5  353.38
#Mann=8,-1,0
  4452.0    0.05       0  4662.4    0.12       0  4914.3    0.04       0
  5175.6    0.12       0  5198.1     0.1       0  5266.0    0.12       0
  5317.4     0.1       0  5441.0    0.05       0
Bank Sta=4914.3,5175.6
Exp/Cntr=0.3,0.1

Type RM Length L Ch R = 1,25238,118,118,118
BEGIN DESCRIPTION:
Walnut49 51.0
END DESCRIPTION:
XS GIS Cut Line= 6
      2734201.89      6754395.74      2733600.17      6754628.75
      2733433.75      6754572.42      2733367.18      6754659.47
      2733392.79      6754774.69      2733130.06      6754828.27
#Sta/Elev= 30
  4284.0  349.11  4554.0  347.38  4750.8  342.63  4794.3  347.40  4810.6  342.02
  4847.9  345.40  4865.2  341.20  4870.5  347.47  4889.7  343.10  4895.1  347.45
  4919.7  343.48  4964.5  347.48  4996.0  340.83  5027.4  339.08  5039.2  344.21
  5061.7  339.05  5062.3  338.55  5066.6  339.05  5101.1  346.32  5124.0  340.45
  5130.3  345.64  5138.5  342.19  5159.3  347.45  5202.9  347.65  5209.2  342.83
  5221.8  347.62  5306.6  345.32  5478.1  344.79  5595.5  353.11  5616.4  353.00
#Mann=6,-1,0
  4284.0    0.05       0  4554.0    0.12       0  5061.7    0.07       0
  5066.6    0.12       0  5306.6     0.1       0  5595.5    0.05       0
Bank Sta=5061.7,5066.6
Exp/Cntr=0.3,0.1

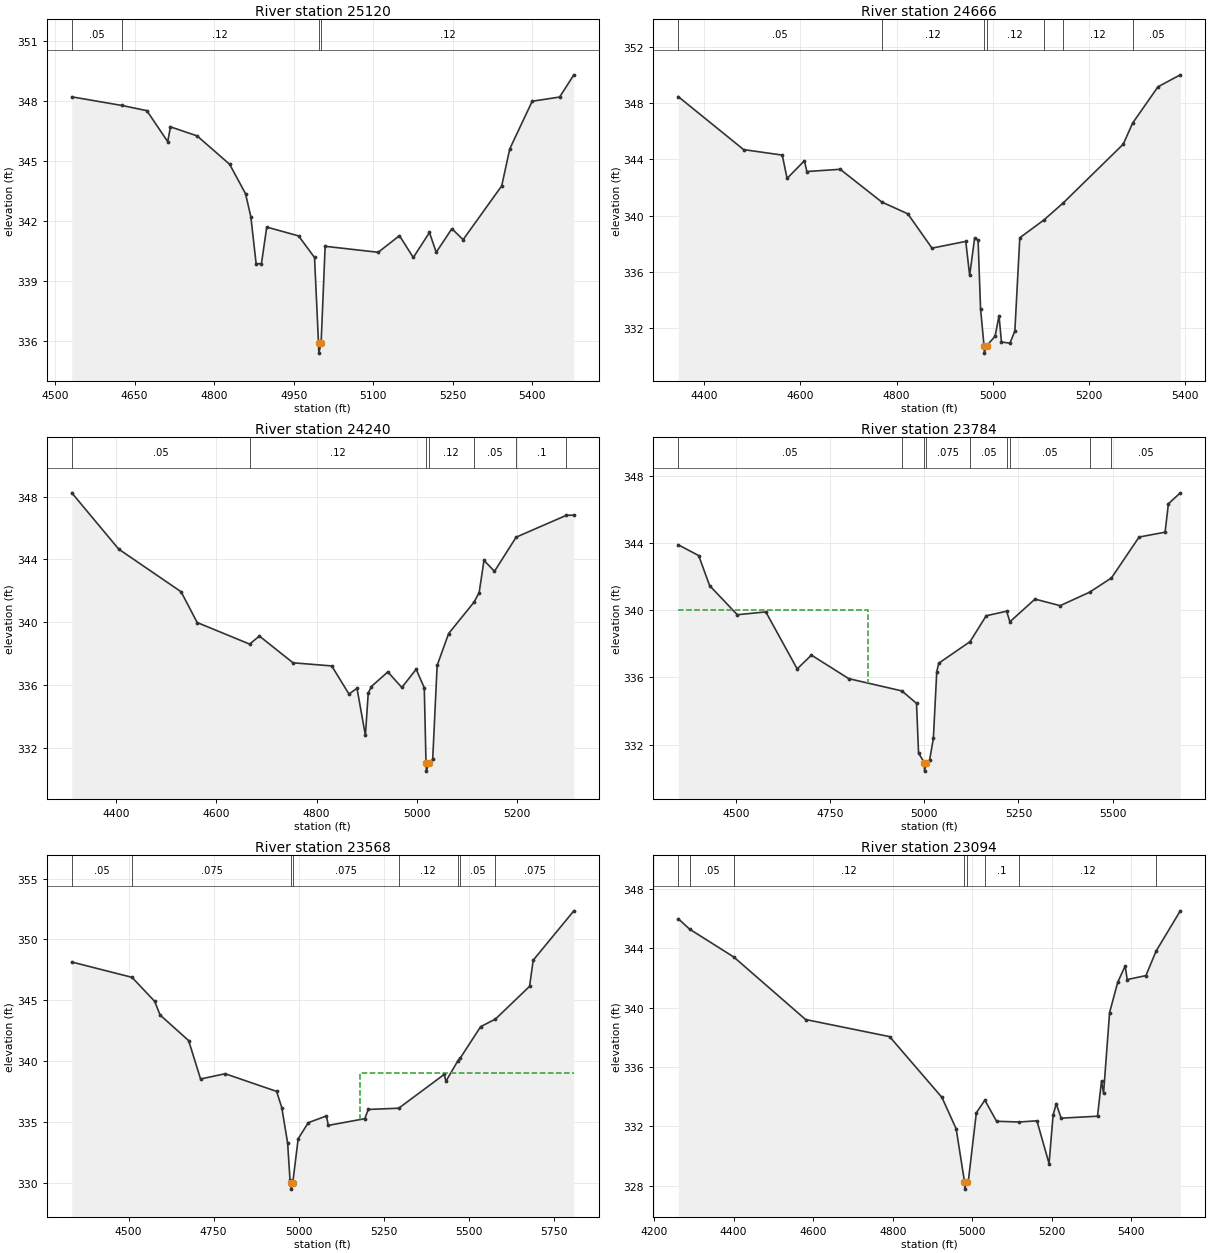
Type RM Length L Ch R = 1,25120,454,454,454
BEGIN DESCRIPTION:
Walnut49 50.8
END DESCRIPTION:
XS GIS Cut Line= 4
      2734040.50      6754429.06      2733789.64      6754510.97
      2733426.07      6754498.17      2733157.23      6754669.71
#Sta/Elev= 30
  4531.7  348.20  4625.9  347.77  4673.2  347.51  4712.6  345.96  4717.8  346.70
  4767.9  346.25  4829.3  344.83  4859.3  343.36  4869.3  342.21  4879.3  339.86
  4889.3  339.86  4899.3  341.69  4959.3  341.25  4989.4  340.17  4996.9  335.89
  4997.5  335.39  5001.8  335.89  5009.4  340.73  5109.4  340.43  5149.5  341.26
  5175.6  340.17  5206.1  341.42  5218.8  340.43  5248.4  341.61  5269.5  341.06
  5342.3  343.75  5357.5  345.60  5399.8  347.98  5451.5  348.19  5478.3  349.30
#Mann=4,-1,0
  4531.7    0.05       0  4625.9    0.12       0  4996.9    0.07       0
  5001.8    0.12       0
Bank Sta=4996.9,5001.8
Exp/Cntr=0.3,0.1

Type RM Length L Ch R = 1,24666,426,426,426
BEGIN DESCRIPTION:
Walnut49 50.0
END DESCRIPTION:
XS GIS Cut Line= 3
      2734181.36      6754208.85      2733564.33      6754155.09
      2733150.30      6754247.09
#Sta/Elev= 30
  4346.0  348.46  4481.9  344.69  4562.2  344.30  4572.2  342.64  4608.3  343.90
  4613.3  343.13  4682.6  343.29  4769.1  340.96  4823.2  340.12  4873.4  337.68
  4943.6  338.16  4951.7  335.74  4962.0  338.39  4969.2  338.25  4974.3  333.38
  4981.6  330.71  4982.2  330.21  4986.7  330.71  5004.6  331.42  5012.7  332.87
  5017.8  331.00  5035.4  330.92  5045.6  331.78  5055.9  338.42  5105.9  339.68
  5146.6  340.91  5271.0  345.08  5290.3  346.57  5343.1  349.16  5389.5  350.01
#Mann=7,-1,0
  4346.0    0.05       0  4769.1    0.12       0  4981.6    0.07       0
  4986.7    0.12       0  5105.9    0.05       0  5146.6    0.12       0
  5290.3    0.05       0
Bank Sta=4981.6,4986.7
Exp/Cntr=0.3,0.1

Type RM Length L Ch R = 1,24240,456,456,456
BEGIN DESCRIPTION:
Walnut49 49.0
END DESCRIPTION:
XS GIS Cut Line= 3
      2734181.36      6754129.48      2733528.48      6753804.32
      2733260.37      6753753.25
#Sta/Elev= 30
  4311.4  348.24  4405.1  344.66  4529.6  341.95  4561.8  339.99  4666.4  338.62
  4686.0  339.13  4753.1  337.43  4830.4  337.23  4864.8  335.44  4880.8  335.81
  4897.6  332.81  4903.2  335.50  4909.5  335.92  4942.3  336.85  4970.3  335.86
  4998.9  337.02  5015.1  335.84  5018.6  331.04  5019.3  330.54  5023.8  331.04
  5031.9  331.28  5040.8  337.26  5063.7  339.29  5114.5  341.29  5124.7  341.90
  5134.3  343.94  5155.3  343.25  5198.5  345.42  5298.8  346.81  5313.7  346.82
#Mann=7,-1,0
  4311.4    0.05       0  4666.4    0.12       0  5018.6    0.07       0
  5023.8    0.12       0  5114.5    0.05       0  5198.5     0.1       0
  5298.8    0.12       0
Bank Sta=5018.6,5023.8
Exp/Cntr=0.3,0.1

Type RM Length L Ch R = 1,23784,216,216,216
BEGIN DESCRIPTION:
Walnut49 48.2
END DESCRIPTION:
XS GIS Cut Line= 3
      2734442.55      6753860.69      2734347.79      6753735.19
      2733258.57      6753295.42
#Sta/Elev= 30
  4347.5  343.88  4401.7  343.24  4430.8  341.45  4504.2  339.72  4579.8  339.89
  4663.0  336.50  4700.8  337.32  4799.8  335.92  4940.7  335.19  4979.6  334.45
  4985.0  331.50  5000.2  330.92  5000.9  330.42  5005.4  330.92  5014.5  331.09
  5024.3  332.37  5033.3  336.34  5038.7  336.84  5121.6  338.12  5164.5  339.66
  5218.7  339.93  5227.3  339.30  5293.9  340.65  5360.7  340.26  5438.7  341.06
  5496.8  341.91  5570.0  344.34  5639.0  344.63  5647.8  346.32  5679.4  346.97
#Mann=9,-1,0
  4347.5    0.05       0  4940.7   0.075       0  5000.2    0.07       0
  5005.4   0.075       0  5121.6    0.05       0  5218.7   0.075       0
  5227.3    0.05       0  5438.7    0.12       0  5496.8    0.05       0
#XS Ineff=2,0
    0.00 4850.00  340.00               0
Permanent Ineff=
       F       F
Bank Sta=5000.2,5005.4
Exp/Cntr=0.3,0.1

Type RM Length L Ch R = 1,23568,474,474,474
BEGIN DESCRIPTION:
Walnut49 48.0
END DESCRIPTION:
XS GIS Cut Line= 3
      2734560.31      6753545.73      2734265.86      6753484.28
      2733175.20      6753043.92
#Sta/Elev= 30
  4332.7  348.15  4510.0  346.89  4576.6  344.92  4592.5  343.80  4676.5  341.70
  4711.6  338.55  4784.0  338.98  4935.3  337.53  4950.5  336.20  4967.7  333.30
  4974.6  330.30  4977.2  330.01  4978.0  329.51  4982.7  330.01  4998.7  333.64
  5028.3  334.96  5081.9  335.52  5087.3  334.74  5194.7  335.29  5204.9  336.05
  5294.5  336.15  5428.1  338.92  5433.5  338.37  5468.9  340.06  5475.0  340.24
  5535.4  342.84  5579.2  343.47  5679.4  346.15  5690.2  348.30  5809.7  352.35
#Mann=8,-1,0
  4332.7    0.05       0  4510.0   0.075       0  4977.2    0.07       0
  4982.7   0.075       0  5294.5    0.12       0  5468.9   0.075       0
  5475.0    0.05       0  5579.2   0.075       0
#XS Ineff=2,0
       0                 5180.00    0.00  339.00
Permanent Ineff=
       F       F
Bank Sta=4977.2,4982.7
Exp/Cntr=0.3,0.1

Type RM Length L Ch R = 1,23094,399,399,399
BEGIN DESCRIPTION:
Walnut49 47.0
END DESCRIPTION:
XS GIS Cut Line= 3
      2734601.22      6753159.10      2734099.44      6752903.09
      2733410.89      6752782.78
#Sta/Elev= 30
  4260.6  345.98  4289.0  345.28  4400.3  343.40  4580.9  339.19  4792.0  338.04
  4923.5  333.95  4959.4  331.83  4980.3  328.27  4981.1  327.77  4985.8  328.27
  4989.8  328.28  5010.1  332.91  5031.5  333.76  5060.9  332.34  5117.4  332.29
  5162.4  332.37  5192.9  329.49  5203.0  332.74  5210.9  333.52  5223.3  332.55
  5314.7  332.68  5324.8  335.06  5329.9  334.22  5345.1  339.66  5365.4  341.69
  5384.3  342.80  5389.4  341.88  5436.5  342.15  5462.0  343.80  5522.9  346.51
#Mann=8,-1,0
  4260.6    0.12       0  4289.0    0.05       0  4400.3    0.12       0
  4980.3    0.07       0  4985.8    0.12       0  5031.5     0.1       0
  5117.4    0.12       0  5462.0    0.05       0
Bank Sta=4980.3,4985.8
Exp/Cntr=0.3,0.1

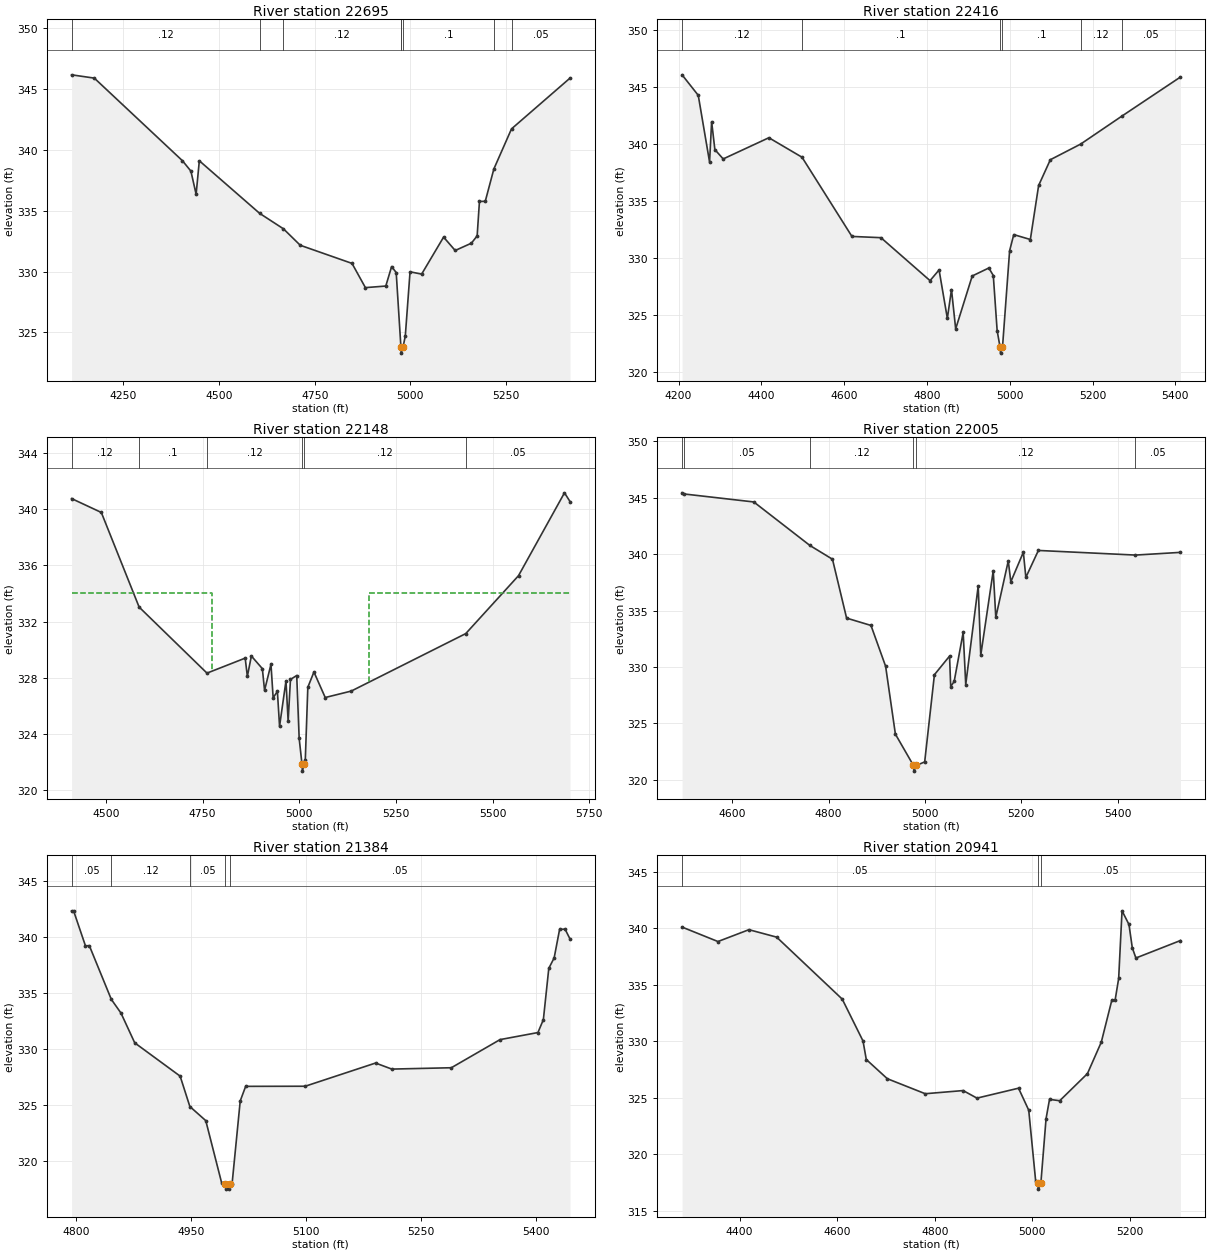
Type RM Length L Ch R = 1,22695,279,279,279
BEGIN DESCRIPTION:
Walnut49 46.0
END DESCRIPTION:
XS GIS Cut Line= 3
      2734803.50      6752933.80      2734094.32      6752557.44
      2733674.45      6752286.06
#Sta/Elev= 30
  4114.4  346.16  4173.8  345.89  4404.3  339.10  4426.3  338.25  4439.9  336.35
  4448.3  339.10  4606.0  334.78  4668.2  333.51  4712.1  332.16  4847.4  330.67
  4882.4  328.68  4935.7  328.81  4950.9  330.41  4962.9  329.92  4975.1  323.86
  4975.2  323.80  4976.0  323.30  4980.8  323.80  4986.7  324.71  4999.1  329.98
  5029.4  329.79  5086.8  332.83  5117.1  331.73  5159.4  332.33  5174.5  332.93
  5180.5  335.76  5195.7  335.77  5218.2  338.43  5264.3  341.72  5417.2  345.89
#Mann=8,-1,0
  4114.4    0.12       0  4606.0     0.1       0  4668.2    0.12       0
  4975.1     0.1       0  4975.2    0.07       0  4980.8     0.1       0
  5218.2    0.12       0  5264.3    0.05       0
Bank Sta=4975.2,4980.8
Exp/Cntr=0.3,0.1

Type RM Length L Ch R = 1,22416,268,268,268
BEGIN DESCRIPTION:
Walnut49 45.0
END DESCRIPTION:
XS GIS Cut Line= 3
      2734864.97      6752311.65      2734555.17      6752286.05
      2733664.14      6752224.60
#Sta/Elev= 30
  4208.4  346.11  4247.5  344.31  4274.8  338.46  4279.8  342.00  4287.6  339.55
  4307.7  338.73  4418.1  340.59  4498.1  338.88  4618.7  331.93  4688.8  331.82
  4807.4  328.05  4829.2  328.99  4849.2  324.74  4859.2  327.27  4869.3  323.82
  4909.3  328.46  4949.4  329.16  4960.2  328.50  4969.5  323.66  4976.7  322.19
  4977.6  321.69  4982.4  322.19  4999.6  330.67  5009.6  332.09  5049.7  331.66
  5069.7  336.40  5098.0  338.66  5171.1  340.03  5270.1  342.47  5412.4  345.92
#Mann=6,-1,0
  4208.4    0.12       0  4498.1     0.1       0  4976.7    0.07       0
  4982.4     0.1       0  5171.1    0.12       0  5270.1    0.05       0
Bank Sta=4976.7,4982.4
Exp/Cntr=0.3,0.1

Type RM Length L Ch R = 1,22148,143,143,143
BEGIN DESCRIPTION:
Walnut49 44.2
END DESCRIPTION:
XS GIS Cut Line= 3
      2734660.12      6752270.67      2733843.40      6751853.35
      2733482.42      6751763.74
#Sta/Elev= 30
  4411.2  340.77  4488.1  339.78  4585.9  333.03  4761.4  328.32  4860.2  329.39
  4865.8  328.09  4876.2  329.54  4904.6  328.64  4910.3  327.09  4926.9  328.95
  4932.5  326.56  4943.5  327.02  4949.1  324.53  4965.7  327.77  4971.3  324.89
  4977.3  327.87  4993.5  328.15  4999.8  323.67  5007.1  321.83  5008.1  321.33
  5013.1  321.83  5015.7  322.15  5022.2  327.31  5038.0  328.40  5067.2  326.58
  5134.5  327.04  5430.7  331.14  5567.1  335.27  5686.0  341.18  5700.3  340.56
#Mann=6,-1,0
  4411.2    0.12       0  4585.9     0.1       0  4761.4    0.12       0
  5007.1    0.07       0  5013.1    0.12       0  5430.7    0.05       0
#XS Ineff=2,0
    0.00 4775.00  334.00 5180.00    0.00  334.00
Permanent Ineff=
       F       F
Bank Sta=5007.1,5013.1
Exp/Cntr=0.3,0.1

Type RM Length L Ch R = 1,22005,621,621,621
BEGIN DESCRIPTION:
Walnut49 44.0
END DESCRIPTION:
XS GIS Cut Line= 3
      2734672.98      6751955.77      2734125.04      6751866.15
      2733671.82      6751709.96
#Sta/Elev= 30
  4495.9  345.44  4499.8  345.34  4644.8  344.63  4761.3  340.77  4808.1  339.55
  4837.4  334.33  4888.0  333.68  4918.4  330.06  4938.7  324.04  4976.2  321.26
  4977.2  320.76  4982.2  321.26  4999.5  321.58  5019.7  329.31  5051.1  330.96
  5053.5  328.26  5060.7  328.71  5079.4  333.06  5084.7  328.44  5110.6  337.18
  5115.9  331.04  5141.8  338.53  5147.1  334.40  5173.0  339.40  5178.3  337.55
  5204.3  340.17  5209.5  337.94  5235.5  340.33  5437.0  339.92  5530.5  340.16
#Mann=6,-1,0
  4495.9     0.1       0  4499.8    0.05       0  4761.3    0.12       0
  4976.2    0.07       0  4982.2    0.12       0  5437.0    0.05       0
Bank Sta=4976.2,4982.2
Exp/Cntr=0.3,0.1

Type RM Length L Ch R = 1,21384,443,443,443
BEGIN DESCRIPTION:
Walnut49 43.0
END DESCRIPTION:
XS GIS Cut Line= 3
      2734076.04      6751310.99      2733876.00      6751361.00
      2733562.13      6751676.32
#Sta/Elev= 30
  4793.6  342.34  4796.2  342.34  4811.7  339.22  4816.8  339.23  4845.5  334.44
  4858.1  333.22  4876.1  330.56  4935.4  327.59  4948.1  324.88  4968.9  323.62
  4989.5  318.10  4994.2  318.01  4995.2  317.51  4999.3  317.51  5000.3  318.01
  5003.3  318.01  5013.9  325.38  5021.0  326.68  5098.8  326.69  5190.7  328.76
  5211.9  328.22  5289.7  328.34  5353.3  330.85  5402.8  331.48  5409.9  332.63
  5417.0  337.21  5424.0  338.14  5431.1  340.68  5438.2  340.71  5444.7  339.83
#Mann=5,-1,0
  4793.6    0.05       0  4845.5    0.12       0  4948.1    0.05       0
  4994.2    0.04       0  5000.3    0.05       0
Bank Sta=4994.2,5000.3
Exp/Cntr=0.3,0.1

Type RM Length L Ch R = 1,20941,401,401,401
BEGIN DESCRIPTION:
Walnut49 42.0
END DESCRIPTION:
XS GIS Cut Line= 3
      2734081.48      6750552.74      2733812.68      6750847.14
      2733352.35      6751266.55
#Sta/Elev= 30
  4282.2  340.11  4355.7  338.83  4419.2  339.88  4476.0  339.22  4610.4  333.73
  4653.0  330.02  4659.7  328.38  4702.8  326.68  4780.5  325.35  4858.2  325.63
  4886.5  324.96  4971.7  325.84  4992.6  323.89  5006.8  317.62  5011.1  317.40
  5012.1  316.90  5017.4  317.40  5028.1  323.14  5035.2  324.85  5056.1  324.73
  5112.9  327.13  5141.3  329.92  5162.9  333.64  5169.7  333.66  5176.9  335.56
  5183.8  341.55  5198.0  340.34  5204.8  338.28  5212.2  337.37  5303.6  338.92
#Mann=3,-1,0
  4282.2    0.05       0  5011.1    0.04       0  5017.4    0.05       0
Bank Sta=5011.1,5017.4
Exp/Cntr=0.3,0.1