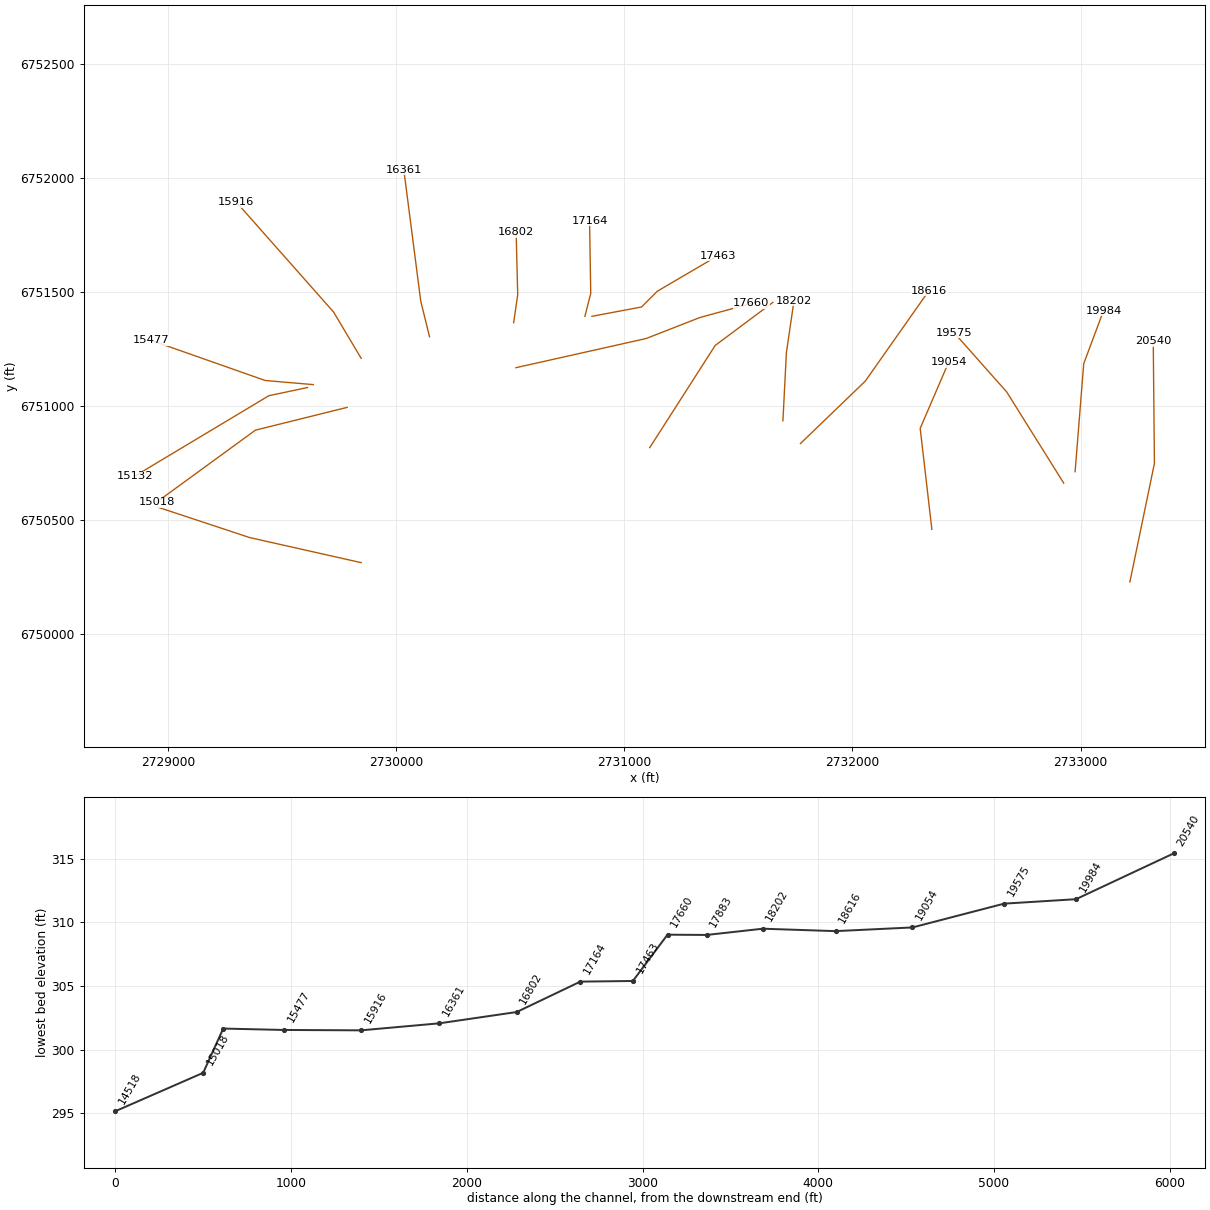
HEC-RAS study Walnut49.prj: Walnut49 Base Level Engineering

--- Walnut49.g01 (geometry) --- (continued)

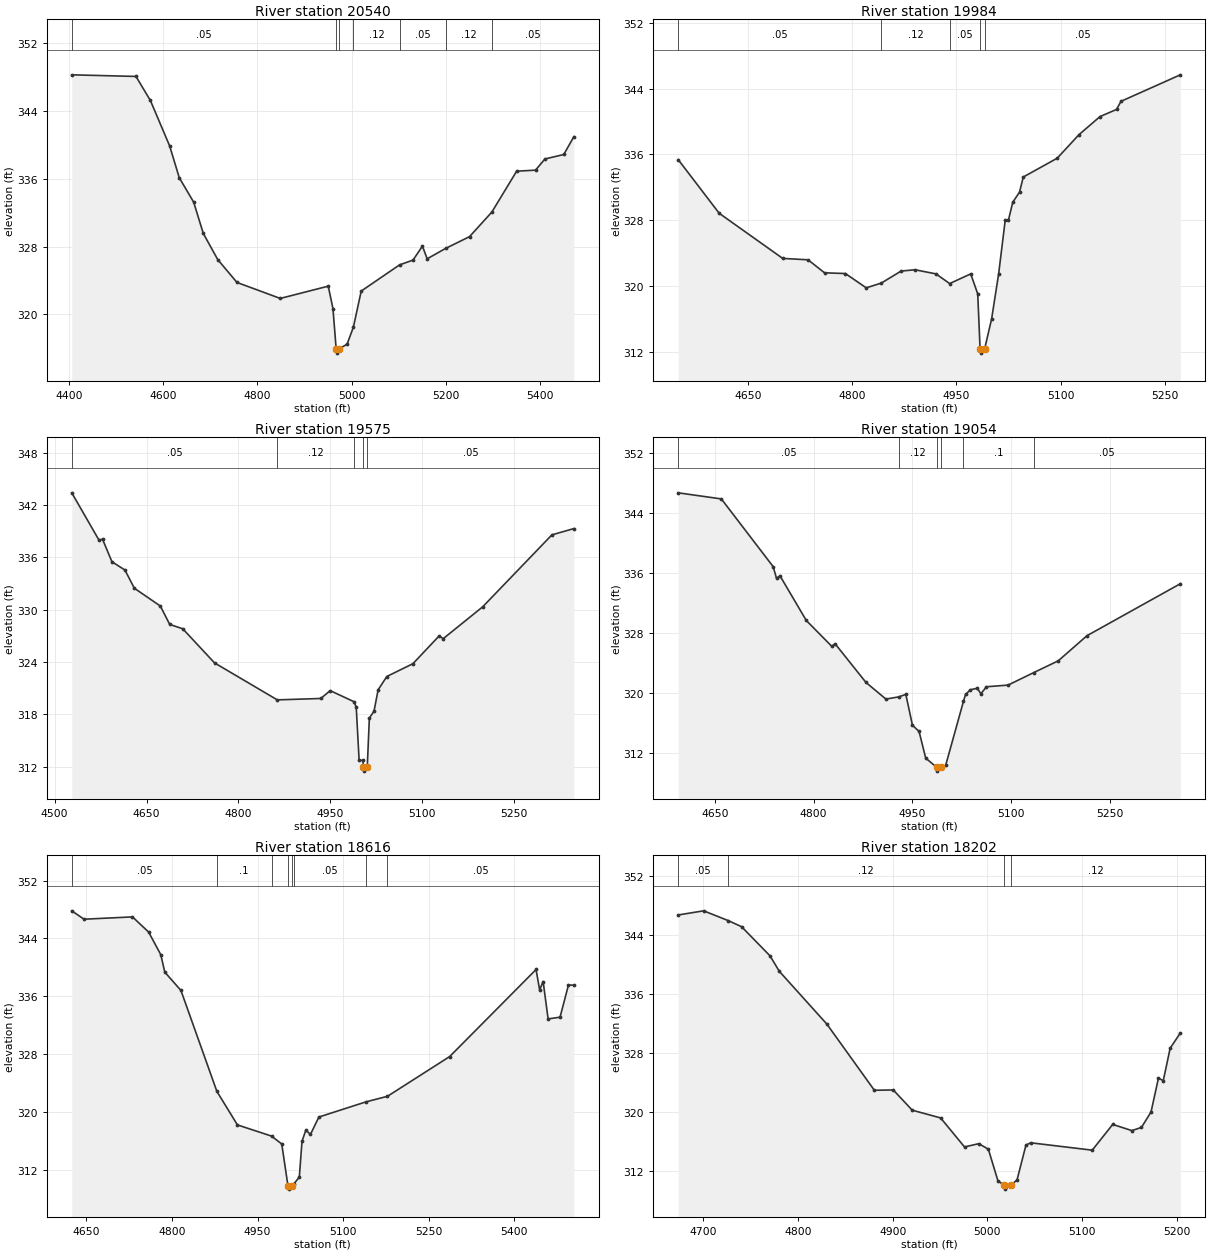
Type RM Length L Ch R = 1,20540,556,556,556
BEGIN DESCRIPTION:
Walnut49 41.0
END DESCRIPTION:
XS GIS Cut Line= 3
      2733216.12      6750227.55      2733323.66      6750747.29
      2733318.54      6751282.42
#Sta/Elev= 30
  4406.1  348.29  4542.4  348.10  4573.0  345.26  4613.9  339.89  4634.3  336.14
  4664.9  333.25  4685.3  329.56  4716.0  326.47  4756.8  323.77  4848.7  321.88
  4950.6  323.33  4960.6  320.68  4967.4  315.92  4968.5  315.42  4973.7  315.92
  4990.6  316.48  5004.0  318.49  5020.6  322.75  5101.9  325.84  5130.6  326.41
  5150.6  328.06  5160.6  326.56  5199.9  327.79  5250.6  329.18  5297.8  332.07
  5350.6  336.91  5390.6  337.03  5410.6  338.35  5450.6  338.88  5472.0  340.98
#Mann=7,-1,0
  4406.1    0.05       0  4967.4    0.05       0  4973.7    0.05       0
  5004.0    0.12       0  5101.9    0.05       0  5199.9    0.12       0
  5297.8    0.05       0
Bank Sta=4967.4,4973.7
Exp/Cntr=0.3,0.1

Type RM Length L Ch R = 1,19984,409,409,409
BEGIN DESCRIPTION:
Walnut49 40.0
END DESCRIPTION:
XS GIS Cut Line= 3
      2732976.00      6750711.01      2733013.86      6751185.10
      2733100.51      6751417.04
#Sta/Elev= 30
  4549.2  335.35  4608.2  328.83  4699.7  323.34  4736.2  323.17  4759.9  321.59
  4790.0  321.50  4820.0  319.76  4841.7  320.34  4870.2  321.80  4890.3  321.96
  4920.4  321.46  4940.2  320.28  4970.5  321.46  4980.6  319.02  4984.0  312.32
  4985.0  311.82  4990.5  312.32  5000.6  315.98  5010.7  321.45  5020.2  327.99
  5024.8  327.99  5031.1  330.18  5040.8  331.40  5046.2  333.24  5095.1  335.53
  5126.4  338.39  5156.7  340.59  5180.5  341.46  5187.0  342.45  5272.4  345.67
#Mann=5,-1,0
  4549.2    0.05       0  4841.7    0.12       0  4940.2    0.05       0
  4984.0    0.04       0  4990.5    0.05       0
Bank Sta=4984,4990.5
Exp/Cntr=0.3,0.1

Type RM Length L Ch R = 1,19575,521,521,521
BEGIN DESCRIPTION:
Walnut49 39.0
END DESCRIPTION:
XS GIS Cut Line= 3
      2732926.02      6750660.96      2732676.00      6751061.00
      2732445.45      6751320.81
#Sta/Elev= 30
  4528.0  343.38  4572.3  337.97  4578.2  338.06  4593.5  335.48  4614.7  334.53
  4630.1  332.44  4672.5  330.40  4687.8  328.29  4709.1  327.79  4760.9  323.88
  4863.3  319.64  4934.3  319.80  4949.6  320.70  4988.7  319.42  4992.1  318.78
  4996.8  312.70  5003.1  312.70  5003.6  311.97  5004.7  311.47  5010.1  311.97
  5013.5  317.55  5021.1  318.35  5027.8  320.79  5042.0  322.32  5084.6  323.79
  5127.3  326.97  5134.0  326.66  5198.4  330.31  5311.3  338.56  5347.1  339.28
#Mann=5,-1,0
  4528.0    0.05       0  4863.3    0.12       0  4988.7    0.05       0
  5003.6    0.04       0  5010.1    0.05       0
Bank Sta=5003.6,5010.1
Exp/Cntr=0.3,0.1

Type RM Length L Ch R = 1,19054,438,438,438
BEGIN DESCRIPTION:
Walnut49 38.0
END DESCRIPTION:
XS GIS Cut Line= 3
      2732348.17      6750457.99      2732296.96      6750900.91
      2732421.72      6751191.16
#Sta/Elev= 30
  4594.6  346.64  4660.0  345.83  4738.6  336.82  4743.8  335.24  4748.9  335.61
  4788.9  329.65  4827.6  326.21  4832.7  326.54  4879.5  321.40  4909.7  319.19
  4929.1  319.48  4939.9  319.81  4950.0  315.71  4960.0  314.88  4970.1  311.33
  4986.9  310.10  4987.9  309.60  4993.6  310.10  5000.3  310.35  5027.4  318.89
  5030.5  319.80  5038.0  320.43  5048.3  320.63  5053.8  319.90  5062.3  320.83
  5095.0  321.05  5133.9  322.71  5171.2  324.28  5214.7  327.62  5356.4  334.54
#Mann=6,-1,0
  4594.6    0.05       0  4929.1    0.12       0  4986.9    0.07       0
  4993.6    0.12       0  5027.4     0.1       0  5133.9    0.05       0
Bank Sta=4986.9,4993.6
Exp/Cntr=0.3,0.1

Type RM Length L Ch R = 1,18616,414,414,414
BEGIN DESCRIPTION:
Walnut49 37.0
END DESCRIPTION:
XS GIS Cut Line= 3
      2731772.12      6750834.36      2732056.29      6751108.29
      2732335.39      6751505.18
#Sta/Elev= 30
  4624.3  347.83  4645.8  346.67  4730.7  346.99  4759.0  344.89  4780.3  341.76
  4787.3  339.35  4815.6  336.81  4878.6  322.84  4914.6  318.20  4974.4  316.65
  4992.3  315.56  5003.1  309.81  5004.2  309.31  5009.8  309.81  5012.9  309.97
  5023.1  310.98  5027.8  315.93  5034.5  317.47  5042.6  316.88  5057.4  319.29
  5140.0  321.39  5177.6  322.16  5286.6  327.66  5438.0  339.71  5444.2  336.90
  5450.4  338.04  5459.1  332.87  5480.0  333.11  5494.8  337.57  5504.2  337.53
#Mann=8,-1,0
  4624.3    0.05       0  4878.6     0.1       0  4974.4    0.12       0
  5003.1    0.07       0  5009.8    0.12       0  5012.9    0.05       0
  5140.0    0.12       0  5177.6    0.05       0
Bank Sta=5003.1,5009.8
Exp/Cntr=0.3,0.1

Type RM Length L Ch R = 1,18202,319,319,319
BEGIN DESCRIPTION:
Walnut49 36.0
END DESCRIPTION:
XS GIS Cut Line= 3
      2731695.29      6750934.22      2731710.65      6751233.75
      2731743.93      6751461.60
#Sta/Elev= 30
  4673.6  346.66  4700.4  347.22  4726.3  345.90  4740.5  345.07  4770.5  341.12
  4780.3  339.03  4830.6  331.86  4880.7  322.90  4900.7  322.94  4920.7  320.20
  4950.7  319.15  4975.9  315.22  4991.0  315.66  5001.1  314.91  5011.2  310.63
  5017.9  310.00  5019.0  309.50  5024.7  310.00  5031.4  310.76  5040.8  315.47
  5045.8  315.78  5110.8  314.78  5132.4  318.27  5152.7  317.43  5162.8  317.87
  5172.9  319.96  5180.7  324.54  5185.8  324.20  5193.1  328.61  5203.8  330.65
#Mann=4,-1,0
  4673.6    0.05       0  4726.3    0.12       0  5017.9    0.07       0
  5024.7    0.12       0
Bank Sta=5017.9,5024.7
Exp/Cntr=0.3,0.1

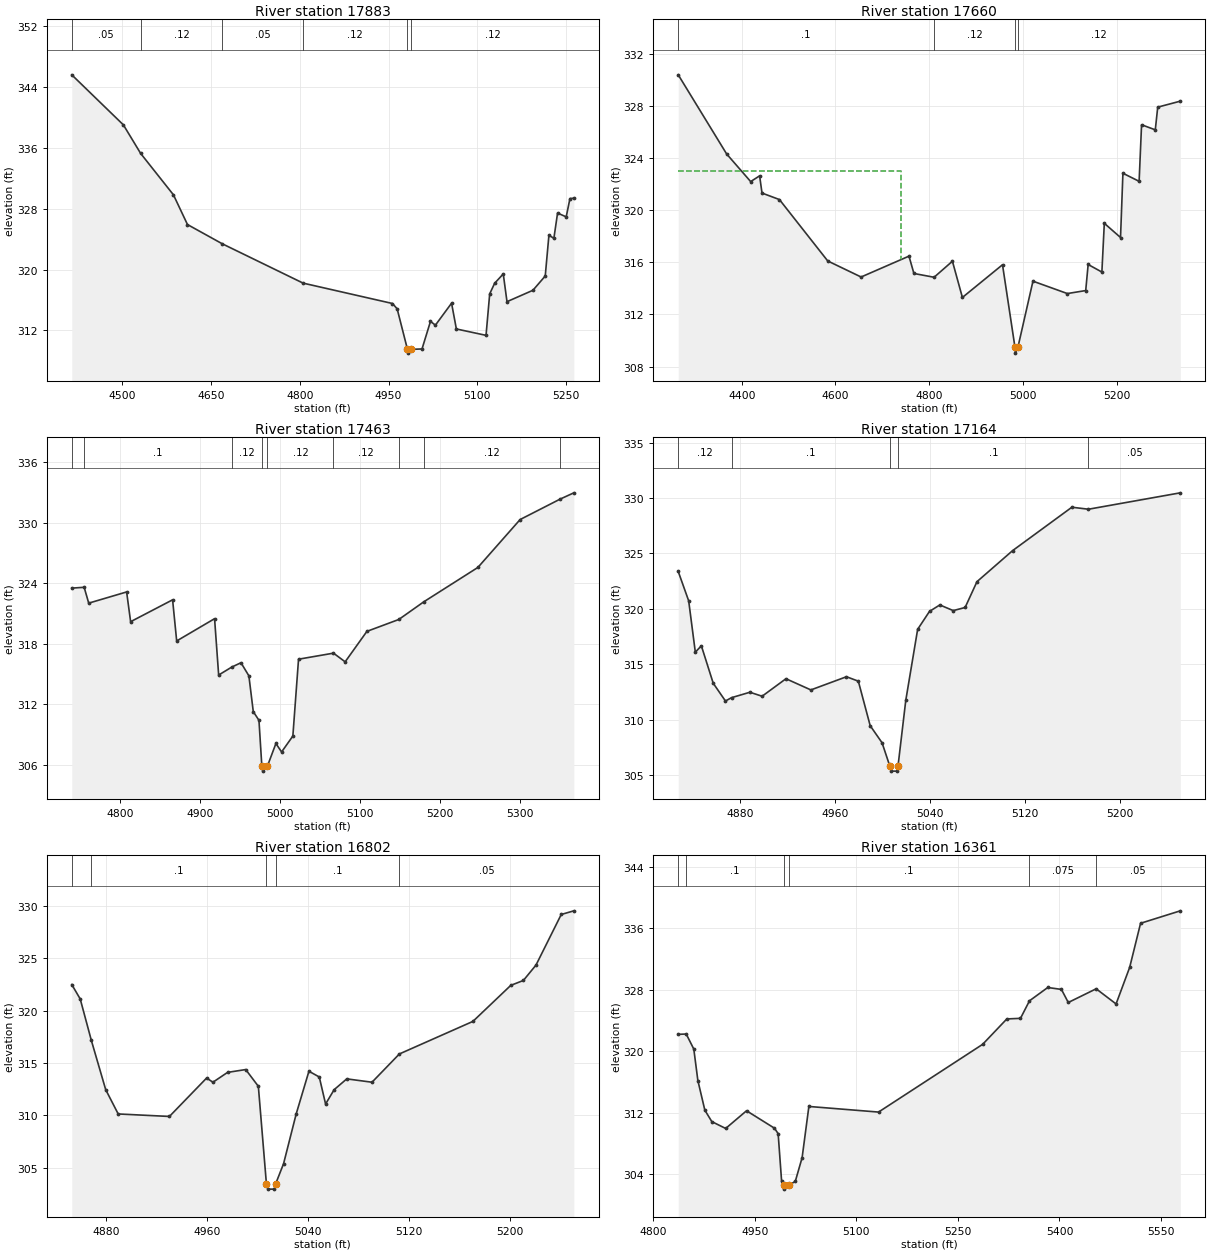
Type RM Length L Ch R = 1,17883,223,223,223
BEGIN DESCRIPTION:
Walnut49 35.0
END DESCRIPTION:
XS GIS Cut Line= 3
      2731111.55      6750816.45      2731398.29      6751264.47
      2731651.37      6751453.65
#Sta/Elev= 30
  4415.0  345.63  4502.2  339.04  4531.4  335.28  4586.7  329.84  4610.4  325.93
  4669.1  323.40  4805.7  318.22  4956.6  315.54  4964.5  314.84  4981.9  309.51
  4983.0  309.01  4988.7  309.51  5006.5  309.56  5020.8  313.19  5029.1  312.69
  5056.4  315.58  5064.5  312.19  5114.6  311.35  5120.8  316.81  5129.2  318.21
  5143.7  319.43  5150.0  315.78  5193.8  317.28  5214.6  319.16  5220.8  324.52
  5229.2  324.12  5235.4  327.44  5250.0  326.94  5256.3  329.34  5262.9  329.40
#Mann=6,-1,0
  4415.0    0.05       0  4531.4    0.12       0  4669.1    0.05       0
  4805.7    0.12       0  4981.9    0.07       0  4988.7    0.12       0
Bank Sta=4981.9,4988.7
Exp/Cntr=0.3,0.1

Type RM Length L Ch R = 1,17660,197,197,197
BEGIN DESCRIPTION:
Walnut49 34.5
END DESCRIPTION:
XS GIS Cut Line= 4
      2730525.19      6751167.18      2731096.17      6751295.20
      2731331.72      6751387.37      2731556.99      6751448.81
#Sta/Elev= 30
  4264.4  330.38  4367.7  324.31  4419.0  322.19  4438.1  322.63  4443.2  321.31
  4480.4  320.81  4583.5  316.10  4654.7  314.87  4756.9  316.47  4767.4  315.14
  4810.5  314.85  4849.6  316.08  4870.9  313.30  4956.5  315.81  4982.9  309.53
  4984.0  309.03  4989.7  309.53  5021.5  314.55  5094.9  313.60  5134.1  313.83
  5139.3  315.83  5168.6  315.25  5173.8  318.99  5208.4  317.90  5213.5  322.83
  5248.1  322.21  5253.3  326.55  5282.6  326.16  5287.8  327.90  5336.0  328.36
#Mann=4,-1,0
  4264.4     0.1       0  4810.5    0.12       0  4982.9    0.07       0
  4989.7    0.12       0
#XS Ineff=2,0
    0.00 4740.00  323.00               0
Permanent Ineff=
       F       F
Bank Sta=4982.9,4989.7
Exp/Cntr=0.3,0.1

Type RM Length L Ch R = 1,17463,299,299,299
BEGIN DESCRIPTION:
Walnut49 34.3
END DESCRIPTION:
XS GIS Cut Line= 4
      2730858.05      6751392.49      2731075.69      6751433.46
      2731144.82      6751502.59      2731411.07      6751658.75
#Sta/Elev= 30
  4739.5  323.54  4755.0  323.62  4760.7  322.05  4808.1  323.16  4813.1  320.21
  4865.6  322.38  4870.7  318.30  4918.1  320.51  4923.2  314.92  4939.6  315.71
  4951.1  316.14  4961.0  314.84  4966.5  311.29  4973.6  310.43  4977.2  305.89
  4978.3  305.39  4984.2  305.89  4994.8  308.13  5001.9  307.29  5016.0  308.87
  5023.1  316.49  5066.8  317.09  5081.4  316.23  5108.6  319.25  5148.5  320.43
  5179.9  322.19  5247.4  325.59  5300.2  330.34  5350.3  332.37  5367.4  332.99
#Mann=9,-1,0
  4739.5    0.12       0  4755.0     0.1       0  4939.6    0.12       0
  4977.2    0.07       0  4984.2    0.12       0  5066.8    0.12       0
  5148.5    0.05       0  5179.9    0.12       0  5350.3    0.05       0
Bank Sta=4977.2,4984.2
Exp/Cntr=0.3,0.1

Type RM Length L Ch R = 1,17164,362,362,362
BEGIN DESCRIPTION:
Walnut49 34.0
END DESCRIPTION:
XS GIS Cut Line= 3
      2730827.33      6751392.47      2730852.94      6751492.34
      2730847.82      6751812.40
#Sta/Elev= 30
  4828.0  323.36  4836.8  320.71  4842.4  316.08  4847.5  316.65  4857.5  313.27
  4867.8  311.67  4872.9  311.97  4888.4  312.46  4898.7  312.10  4918.8  313.68
  4939.8  312.67  4969.8  313.86  4979.8  313.46  4989.8  309.44  4999.8  307.90
  5006.2  305.84  5007.3  305.34  5012.2  305.34  5013.3  305.84  5019.8  311.73
  5029.8  318.14  5039.8  319.76  5048.5  320.34  5059.8  319.83  5069.8  320.11
  5079.8  322.44  5109.8  325.24  5159.8  329.16  5173.8  328.98  5251.2  330.46
#Mann=5,-1,0
  4828.0    0.12       0  4872.9     0.1       0  5006.2    0.07       0
  5013.3     0.1       0  5173.8    0.05       0
Bank Sta=5006.2,5013.3
Exp/Cntr=0.3,0.1

Type RM Length L Ch R = 1,16802,441,441,441
BEGIN DESCRIPTION:
Walnut49 33.0
END DESCRIPTION:
XS GIS Cut Line= 3
      2730514.98      6751364.37      2730532.90      6751487.22
      2730526.00      6751760.98
#Sta/Elev= 30
  4852.5  322.49  4859.2  321.11  4868.0  317.16  4879.4  312.45  4889.3  310.13
  4929.9  309.89  4959.4  313.56  4964.4  313.16  4976.0  314.10  4990.4  314.37
  5000.4  312.77  5006.8  303.45  5007.9  302.95  5013.0  302.95  5014.1  303.45
  5020.4  305.38  5030.4  310.13  5040.5  314.21  5048.7  313.66  5053.7  311.08
  5060.5  312.45  5070.5  313.48  5090.5  313.16  5112.2  315.86  5170.5  318.97
  5200.5  322.41  5210.5  322.88  5220.5  324.35  5240.5  329.18  5250.5  329.53
#Mann=5,-1,0
  4852.5    0.12       0  4868.0     0.1       0  5006.8    0.07       0
  5014.1     0.1       0  5112.2    0.05       0
Bank Sta=5006.8,5014.1
Exp/Cntr=0.3,0.1

Type RM Length L Ch R = 1,16361,445,445,445
BEGIN DESCRIPTION:
Walnut49 32.0
END DESCRIPTION:
XS GIS Cut Line= 3
      2730146.29      6751302.88      2730107.88      6751459.06
      2730033.63      6752035.16
#Sta/Elev= 30
  4836.8  322.19  4848.6  322.23  4859.8  320.27  4865.8  316.18  4876.1  312.33
  4886.4  310.84  4906.9  309.95  4937.7  312.25  4979.0  309.98  4984.4  309.27
  4989.5  303.09  4992.4  302.56  4993.5  302.06  4999.7  302.56  5009.7  303.06
  5019.8  306.15  5029.8  312.81  5132.7  312.08  5286.5  320.89  5322.2  324.19
  5342.4  324.27  5355.7  326.55  5382.7  328.28  5402.9  328.03  5413.0  326.33
  5454.2  328.11  5483.6  326.14  5503.7  330.90  5519.8  336.63  5578.5  338.25
#Mann=6,-1,0
  4836.8    0.12       0  4848.6     0.1       0  4992.4    0.07       0
  4999.7     0.1       0  5355.7   0.075       0  5454.2    0.05       0
Bank Sta=4992.4,4999.7
Exp/Cntr=0.3,0.1

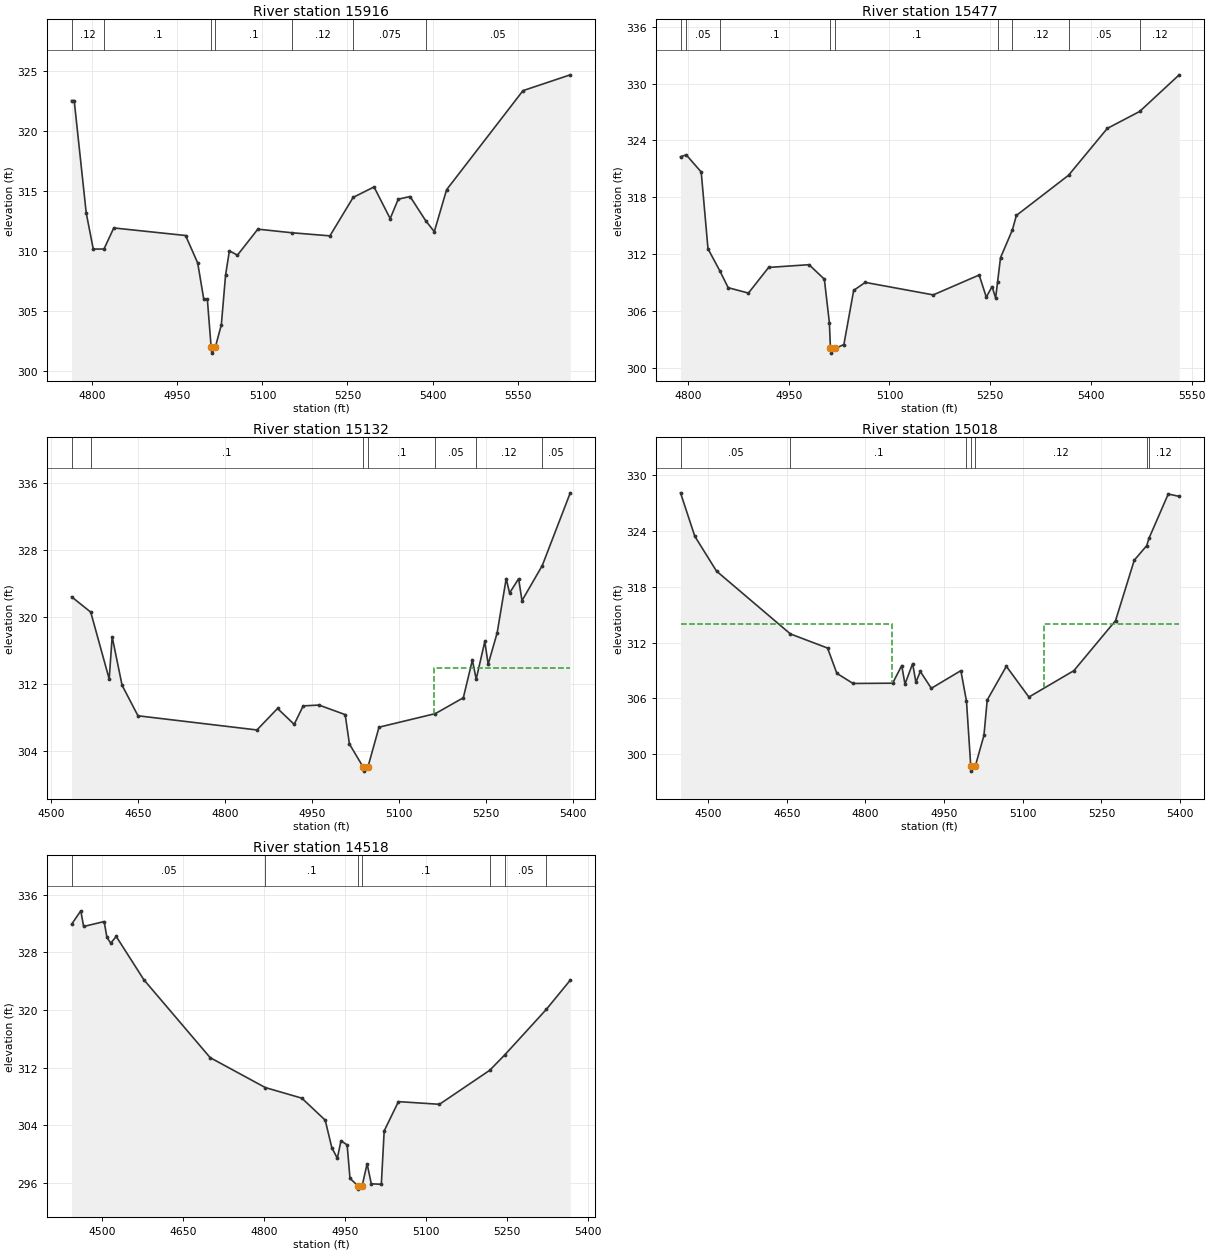
Type RM Length L Ch R = 1,15916,439,439,439
BEGIN DESCRIPTION:
Walnut49 31.0
END DESCRIPTION:
XS GIS Cut Line= 3
      2729846.73      6751208.15      2729726.00      6751411.00
      2729299.88      6751893.12
#Sta/Elev= 30
  4763.4  322.57  4768.0  322.57  4789.2  313.20  4801.6  310.19  4820.5  310.19
  4837.8  311.95  4964.4  311.32  4985.8  309.03  4996.5  306.01  5002.8  306.01
  5009.5  302.01  5010.7  301.51  5016.9  302.01  5027.5  303.87  5035.0  308.04
  5041.7  310.04  5055.9  309.68  5091.9  311.85  5151.6  311.55  5219.0  311.29
  5260.0  314.50  5296.8  315.37  5325.3  312.73  5339.5  314.35  5360.4  314.57
  5388.0  312.55  5403.1  311.64  5424.8  315.14  5559.5  323.40  5642.9  324.72
#Mann=7,-1,0
  4763.4    0.12       0  4820.5     0.1       0  5009.5    0.07       0
  5016.9     0.1       0  5151.6    0.12       0  5260.0   0.075       0
  5388.0    0.05       0
Bank Sta=5009.5,5016.9
Exp/Cntr=0.3,0.1

Type RM Length L Ch R = 1,15477,345,345,345
BEGIN DESCRIPTION:
Walnut49 30.0
END DESCRIPTION:
XS GIS Cut Line= 3
      2729636.73      6751092.94      2729426.00      6751111.00
      2728924.99      6751287.52
#Sta/Elev= 30
  4788.8  322.28  4797.3  322.48  4819.6  320.67  4829.7  312.56  4847.4  310.22
  4859.8  308.45  4889.9  307.88  4920.0  310.59  4980.2  310.88  5003.0  309.35
  5010.5  304.75  5012.1  302.04  5013.2  301.54  5019.5  302.04  5032.1  302.45
  5046.7  308.17  5063.9  309.01  5165.2  307.69  5233.6  309.79  5244.2  307.45
  5252.8  308.57  5258.1  307.36  5261.0  309.05  5265.4  311.62  5283.1  314.56
  5289.0  316.08  5366.8  320.33  5424.4  325.27  5472.6  327.06  5531.5  330.93
#Mann=9,-1,0
  4788.8    0.12       0  4797.3    0.05       0  4847.4     0.1       0
  5012.1    0.07       0  5019.5     0.1       0  5261.0    0.05       0
  5283.1    0.12       0  5366.8    0.05       0  5472.6    0.12       0
Bank Sta=5012.1,5019.5
Exp/Cntr=0.3,0.1

Type RM Length L Ch R = 1,15132,114,114,114
BEGIN DESCRIPTION:
Walnut49 29.2
END DESCRIPTION:
XS GIS Cut Line= 3
      2729611.14      6751080.12      2729442.20      6751044.29
      2728853.36      6750690.98
#Sta/Elev= 30
  4535.9  322.44  4568.9  320.61  4600.7  312.63  4605.8  317.67  4622.9  311.89
  4650.3  308.25  4855.3  306.56  4890.8  309.12  4919.5  307.23  4935.0  309.43
  4962.2  309.53  5007.4  308.39  5014.7  304.89  5038.2  302.15  5039.4  301.65
  5046.6  302.15  5065.7  306.89  5162.8  308.51  5211.0  310.40  5226.6  314.89
  5233.2  312.62  5248.0  317.11  5253.8  314.39  5269.3  318.14  5284.9  324.61
  5290.7  322.89  5306.3  324.60  5312.1  321.98  5347.0  326.16  5395.3  334.84
#Mann=7,-1,0
  4535.9    0.05       0  4568.9     0.1       0  5038.2    0.07       0
  5046.6     0.1       0  5162.8    0.05       0  5233.2    0.12       0
  5347.0    0.05       0
#XS Ineff=2,0
       0                 5160.00    0.00  314.00
Permanent Ineff=
       F       F
Bank Sta=5038.2,5046.6
Exp/Cntr=0.3,0.1

Type RM Length L Ch R = 1,15018,500,500,500
BEGIN DESCRIPTION:
Walnut49 29.0
END DESCRIPTION:
XS GIS Cut Line= 3
      2729785.30      6750993.08      2729383.31      6750893.23
      2728949.71      6750576.95
#Sta/Elev= 30
  4447.3  328.11  4474.5  323.44  4515.9  319.69  4656.8  312.93  4727.7  311.41
  4745.4  308.69  4776.3  307.60  4851.8  307.63  4869.1  309.53  4875.3  307.53
  4889.9  309.74  4896.1  307.74  4904.6  308.89  4925.5  307.08  4981.9  308.98
  4992.6  305.69  5000.8  298.67  5002.1  298.17  5009.2  298.67  5025.9  302.02
  5032.1  305.82  5068.6  309.45  5111.6  306.14  5197.4  308.98  5276.9  314.37
  5312.5  320.86  5336.3  322.43  5340.6  323.22  5377.3  327.98  5398.2  327.73
#Mann=7,-1,0
  4447.3    0.05       0  4656.8     0.1       0  4992.6    0.12       0
  5000.8    0.07       0  5009.2    0.12       0  5336.3    0.05       0
  5340.6    0.12       0
#XS Ineff=2,0
    0.00 4850.00  314.00 5140.00    0.00  314.00
Permanent Ineff=
       F       F
Bank Sta=5000.8,5009.2
Exp/Cntr=0.3,0.1

Type RM Length L Ch R = 1,14518,273,273,273
BEGIN DESCRIPTION:
Walnut49 28.0
END DESCRIPTION:
XS GIS Cut Line= 3
      2729846.77      6750312.02      2729357.71      6750422.13
      2728955.69      6750555.28
#Sta/Elev= 30
  4443.0  331.90  4460.1  333.76  4465.3  331.59  4503.4  332.27  4508.5  330.08
  4515.5  329.28  4525.8  330.20  4577.0  324.20  4700.0  313.39  4802.3  309.24
  4870.0  307.77  4913.3  304.72  4925.6  300.90  4935.8  299.43  4942.6  301.86
  4954.0  301.28  4959.3  296.64  4973.5  295.65  4974.7  295.15  4982.0  295.65
  4991.0  298.67  4998.8  295.89  5017.4  295.82  5022.7  303.23  5049.1  307.29
  5125.2  306.92  5218.3  311.63  5246.5  313.79  5323.3  320.08  5367.8  324.14
#Mann=7,-1,0
  4443.0    0.05       0  4802.3     0.1       0  4973.5    0.07       0
  4982.0     0.1       0  5218.3    0.12       0  5246.5    0.05       0
  5323.3    0.12       0
Bank Sta=4973.5,4982
Exp/Cntr=0.3,0.1