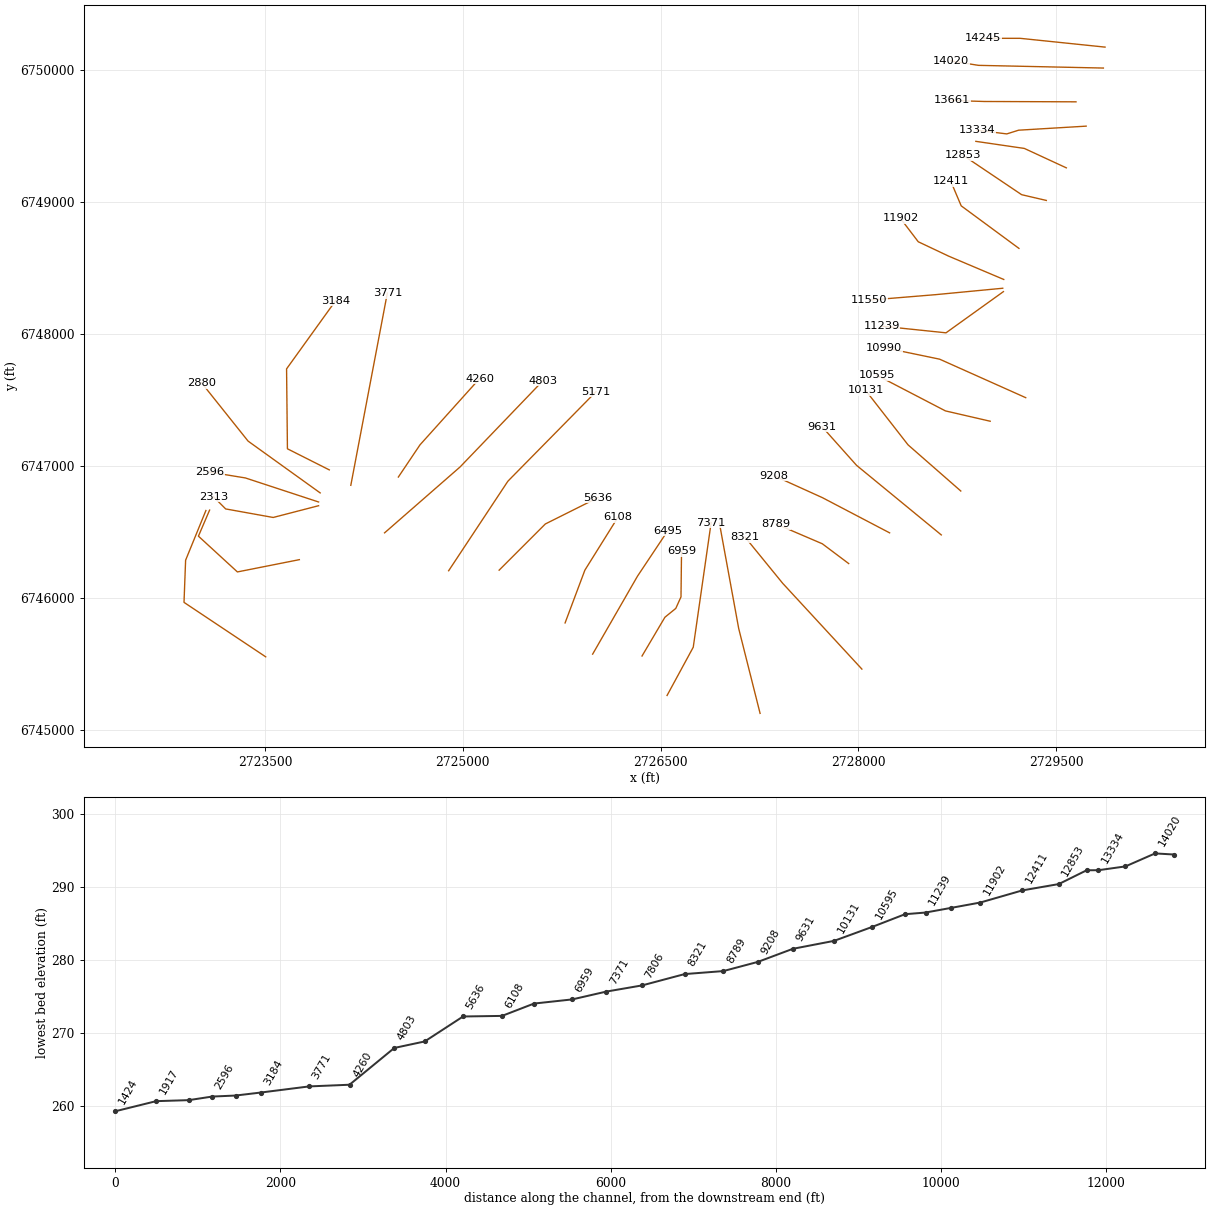
HEC-RAS study Walnut49.prj: Walnut49 Base Level Engineering

--- Walnut49.g01 (geometry) --- (continued)

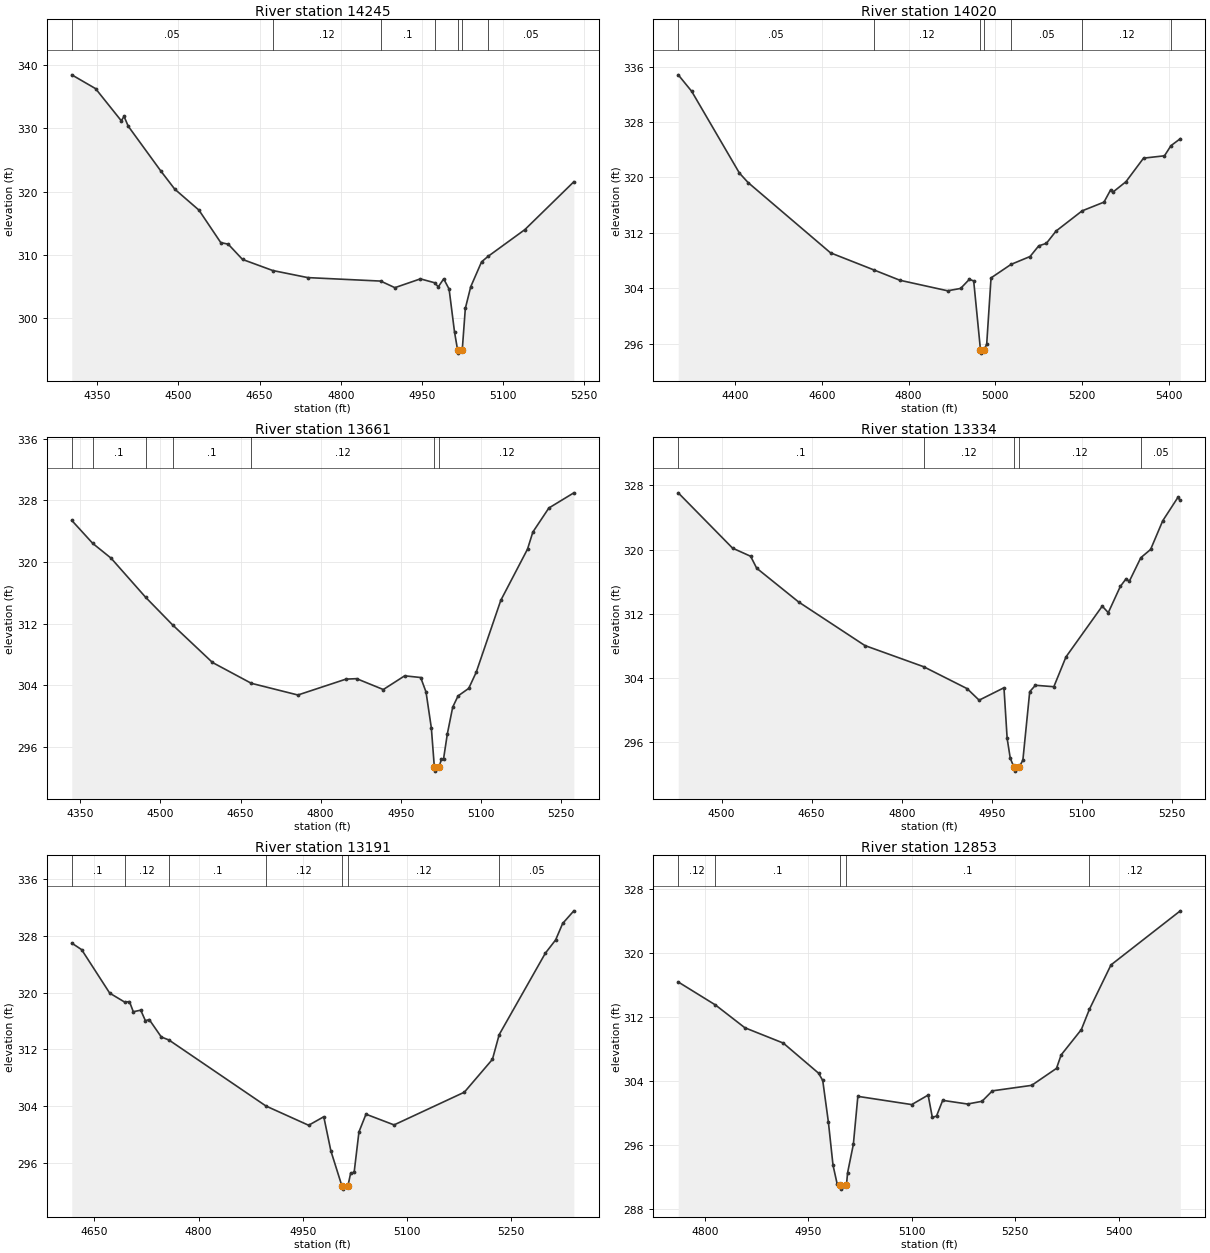
Type RM Length L Ch R = 1,14245,225,225,225
BEGIN DESCRIPTION:
Walnut49 27.0
END DESCRIPTION:
XS GIS Cut Line= 3
      2729869.79      6750176.33      2729227.13      6750242.90
      2728945.53      6750242.90
#Sta/Elev= 30
  4302.9  338.44  4346.9  336.26  4394.4  331.18  4399.5  331.88  4407.2  330.33
  4467.6  323.23  4493.2  320.38  4537.9  317.07  4578.2  311.94  4592.0  311.69
  4618.4  309.28  4674.2  307.53  4739.0  306.41  4873.7  305.86  4899.9  304.82
  4947.1  306.21  4973.2  305.60  4980.1  304.95  4990.1  306.21  5000.1  304.60
  5010.1  297.83  5015.8  294.98  5017.1  294.48  5024.4  294.98  5030.1  301.55
  5040.1  304.97  5060.1  308.90  5072.2  309.77  5140.1  313.99  5230.6  321.55
#Mann=7,-1,0
  4302.9    0.05       0  4674.2    0.12       0  4873.7     0.1       0
  4973.2    0.12       0  5015.8    0.07       0  5024.4    0.12       0
  5072.2    0.05       0
Bank Sta=5015.8,5024.4
Exp/Cntr=0.3,0.1

Type RM Length L Ch R = 1,14020,359,359,359
BEGIN DESCRIPTION:
Walnut49 26.5
END DESCRIPTION:
XS GIS Cut Line= 3
      2729856.99      6750017.59      2728909.65      6750038.08
      2728702.27      6750071.36
#Sta/Elev= 30
  4268.7  334.81  4299.7  332.43  4409.7  320.63  4429.7  319.26  4619.8  309.11
  4719.9  306.64  4779.8  305.15  4889.8  303.63  4919.8  303.97  4939.8  305.28
  4949.9  305.06  4965.5  295.13  4966.8  294.63  4974.2  295.13  4979.9  295.92
  4989.9  305.49  5036.0  307.44  5079.9  308.58  5099.9  310.12  5117.5  310.48
  5139.9  312.26  5199.9  315.17  5250.3  316.43  5265.9  318.23  5271.0  317.88
  5301.0  319.38  5341.5  322.78  5389.8  323.12  5404.7  324.58  5426.3  325.59
#Mann=7,-1,0
  4268.7    0.05       0  4719.9    0.12       0  4965.5    0.07       0
  4974.2    0.12       0  5036.0    0.05       0  5199.9    0.12       0
  5404.7    0.05       0
Bank Sta=4965.5,4974.2
Exp/Cntr=0.3,0.1

Type RM Length L Ch R = 1,13661,327,327,327
BEGIN DESCRIPTION:
Walnut49 26.0
END DESCRIPTION:
XS GIS Cut Line= 3
      2729649.59      6749761.56      2728953.17      6749764.12
      2728709.21      6749771.75
#Sta/Elev= 30
  4333.9  325.39  4373.3  322.40  4407.5  320.49  4472.3  315.41  4522.6  311.84
  4597.5  306.95  4670.2  304.25  4757.5  302.73  4847.5  304.79  4867.5  304.85
  4917.5  303.44  4957.5  305.22  4987.5  305.00  4997.5  303.12  5007.5  298.44
  5013.1  293.35  5014.4  292.85  5021.8  293.35  5026.4  294.42  5030.3  294.42
  5037.5  297.71  5047.5  301.16  5057.5  302.61  5077.5  303.59  5091.5  305.68
  5137.5  315.01  5187.6  321.66  5197.6  323.88  5227.6  327.00  5274.4  328.97
#Mann=7,-1,0
  4333.9    0.12       0  4373.3     0.1       0  4472.3    0.12       0
  4522.6     0.1       0  4670.2    0.12       0  5013.1    0.07       0
  5021.8    0.12       0
Bank Sta=5013.1,5021.8
Exp/Cntr=0.3,0.1

Type RM Length L Ch R = 1,13334,143,143,143
BEGIN DESCRIPTION:
Walnut49 25.3
END DESCRIPTION:
XS GIS Cut Line= 4
      2729726.42      6749577.22      2729214.33      6749546.49
      2729124.72      6749518.33      2728896.89      6749546.49
#Sta/Elev= 30
  4427.7  327.08  4518.3  320.17  4548.3  319.16  4558.4  317.67  4628.5  313.44
  4738.7  308.01  4836.5  305.37  4909.0  302.63  4929.0  301.19  4970.4  302.74
  4975.7  296.41  4980.9  293.94  4987.0  292.83  4988.3  292.33  4995.7  292.83
  5001.9  293.70  5013.3  302.25  5022.8  303.05  5053.5  302.87  5073.7  306.59
  5134.1  312.93  5144.2  312.12  5164.3  315.40  5174.0  316.36  5179.1  316.01
  5198.4  318.98  5214.7  320.01  5234.9  323.59  5260.1  326.50  5264.2  326.13
#Mann=5,-1,0
  4427.7     0.1       0  4836.5    0.12       0  4987.0    0.07       0
  4995.7    0.12       0  5198.4    0.05       0
Bank Sta=4987,4995.7
Exp/Cntr=0.3,0.1

Type RM Length L Ch R = 1,13191,338,338,338
BEGIN DESCRIPTION:
Walnut49 25.0
END DESCRIPTION:
XS GIS Cut Line= 3
      2729576.00      6749261.00      2729257.85      6749408.24
      2728890.11      6749461.87
#Sta/Elev= 30
  4617.7  326.99  4631.9  326.07  4672.3  319.94  4693.6  318.69  4700.7  318.74
  4706.2  317.32  4716.9  317.54  4723.6  316.06  4729.1  316.22  4746.5  313.76
  4757.4  313.34  4897.1  304.03  4958.4  301.32  4980.2  302.52  4990.4  297.71
  5006.1  292.82  5007.4  292.32  5015.0  292.82  5018.8  294.54  5023.9  294.70
  5030.8  300.39  5040.9  302.88  5081.3  301.37  5182.4  305.98  5222.8  310.61
  5232.5  314.09  5298.9  325.57  5313.7  327.44  5323.8  329.76  5339.9  331.54
#Mann=7,-1,0
  4617.7     0.1       0  4693.6    0.12       0  4757.4     0.1       0
  4897.1    0.12       0  5006.1    0.07       0  5015.0    0.12       0
  5232.5    0.05       0
Bank Sta=5006.1,5015
Exp/Cntr=0.3,0.1

Type RM Length L Ch R = 1,12853,442,442,442
BEGIN DESCRIPTION:
Walnut49 24.0
END DESCRIPTION:
XS GIS Cut Line= 3
      2729424.32      6749013.93      2729237.37      6749057.47
      2728792.62      6749356.53
#Sta/Elev= 30
  4761.5  316.40  4815.4  313.52  4858.1  310.66  4913.8  308.74  4964.9  304.97
  4971.0  304.05  4979.2  298.83  4985.9  293.43  4992.0  291.04  4996.5  290.93
  4997.8  290.43  5005.4  290.93  5007.0  292.47  5015.4  296.05  5021.9  302.06
  5100.0  301.03  5123.8  302.22  5129.9  299.41  5136.0  299.60  5144.9  301.56
  5180.9  301.10  5201.9  301.44  5216.9  302.75  5273.9  303.44  5309.9  305.57
  5316.6  307.25  5345.9  310.43  5357.5  312.95  5388.9  318.54  5489.4  325.32
#Mann=5,-1,0
  4761.5    0.12       0  4815.4     0.1       0  4996.5    0.07       0
  5005.4     0.1       0  5357.5    0.12       0
Bank Sta=4996.5,5005.4
Exp/Cntr=0.3,0.1

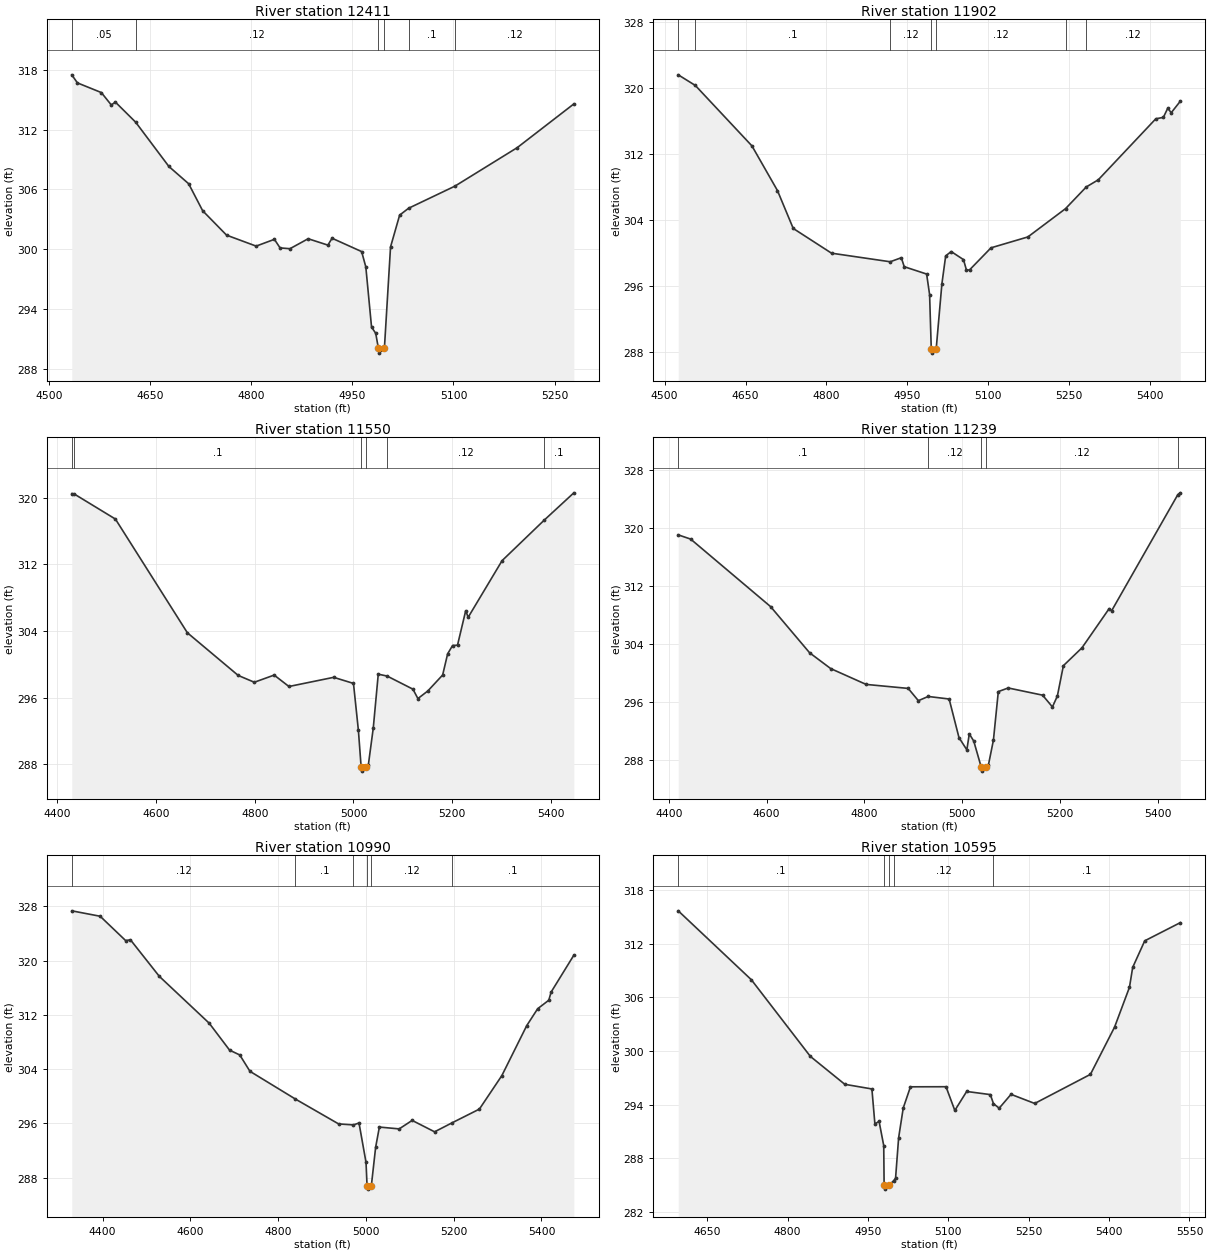
Type RM Length L Ch R = 1,12411,509,509,509
BEGIN DESCRIPTION:
Walnut49 23.0
END DESCRIPTION:
XS GIS Cut Line= 3
      2729216.92      6748650.35      2728779.07      6748972.98
      2728700.34      6749158.38
#Sta/Elev= 30
  4533.4  317.49  4541.8  316.68  4577.3  315.71  4592.0  314.47  4598.2  314.75
  4628.2  312.74  4677.6  308.29  4706.9  306.56  4727.7  303.85  4763.2  301.40
  4807.1  300.30  4834.2  300.98  4842.6  300.12  4857.3  300.04  4884.3  301.04
  4913.6  300.40  4919.8  301.09  4963.7  299.75  4969.9  298.21  4978.4  292.17
  4984.6  291.55  4988.5  290.06  4989.8  289.56  4997.5  290.06  5006.6  300.22
  5020.1  303.41  5033.4  304.10  5102.2  306.32  5194.6  310.18  5278.7  314.57
#Mann=6,-1,0
  4533.4    0.05       0  4628.2    0.12       0  4988.5    0.07       0
  4997.5    0.12       0  5033.4     0.1       0  5102.2    0.12       0
Bank Sta=4988.5,4997.5
Exp/Cntr=0.3,0.1

Type RM Length L Ch R = 1,11902,352,352,352
BEGIN DESCRIPTION:
Walnut49 22.0
END DESCRIPTION:
XS GIS Cut Line= 4
      2729101.66      6748414.83      2728684.34      6748591.49
      2728453.38      6748700.75      2728319.05      6748877.15
#Sta/Elev= 30
  4525.3  321.65  4557.0  320.36  4661.9  313.03  4709.2  307.61  4738.4  303.02
  4809.4  300.02  4918.1  298.98  4938.7  299.47  4944.1  298.38  4985.6  297.49
  4991.1  295.00  4994.2  288.40  4995.5  287.90  5003.3  288.40  5013.9  296.31
  5020.9  299.69  5031.1  300.22  5053.9  299.24  5059.4  297.97  5065.1  297.99
  5104.9  300.67  5173.2  301.99  5243.0  305.42  5281.4  308.05  5303.7  308.92
  5410.3  316.32  5424.3  316.49  5432.5  317.61  5438.8  317.05  5455.7  318.45
#Mann=7,-1,0
  4525.3    0.12       0  4557.0     0.1       0  4918.1    0.12       0
  4994.2    0.07       0  5003.3    0.12       0  5243.0     0.1       0
  5281.4    0.12       0
Bank Sta=4994.2,5003.3
Exp/Cntr=0.3,0.1

Type RM Length L Ch R = 1,11550,311,311,311
BEGIN DESCRIPTION:
Walnut49 21.5
END DESCRIPTION:
XS GIS Cut Line= 3
      2729094.00      6748348.26      2728584.49      6748299.61
      2728081.22      6748258.14
#Sta/Elev= 30
  4429.5  320.48  4434.5  320.44  4517.9  317.43  4663.6  303.78  4766.5  298.66
  4799.2  297.84  4839.4  298.70  4869.3  297.33  4959.9  298.43  5000.0  297.70
  5010.0  292.05  5015.5  287.67  5016.8  287.17  5024.6  287.67  5030.1  287.90
  5040.1  292.34  5050.2  298.81  5068.3  298.58  5120.4  297.01  5130.5  295.88
  5150.5  296.79  5180.6  298.71  5190.7  301.25  5200.7  302.25  5210.7  302.29
  5227.3  306.43  5232.3  305.64  5301.0  312.44  5386.1  317.29  5446.3  320.58
#Mann=6,-1,0
  4429.5    0.12       0  4434.5     0.1       0  5015.5    0.07       0
  5024.6     0.1       0  5068.3    0.12       0  5386.1     0.1       0
Bank Sta=5015.5,5024.6
Exp/Cntr=0.3,0.1

Type RM Length L Ch R = 1,11239,249,249,249
BEGIN DESCRIPTION:
Walnut49 21.0
END DESCRIPTION:
XS GIS Cut Line= 3
      2729099.12      6748322.66      2728663.86      6748010.30
      2728176.04      6748061.00
#Sta/Elev= 30
  4419.3  319.06  4444.7  318.48  4608.1  309.18  4687.9  302.82  4730.9  300.65
  4803.3  298.47  4889.3  297.92  4910.1  296.23  4930.2  296.81  4973.0  296.46
  4993.1  291.15  5009.2  289.46  5014.2  291.66  5023.3  290.67  5038.8  287.03
  5040.1  286.53  5047.9  287.03  5053.4  287.41  5063.5  290.79  5073.5  297.48
  5093.7  297.98  5164.0  296.99  5184.1  295.37  5194.2  296.87  5206.5  301.05
  5244.5  303.51  5300.1  308.91  5305.1  308.61  5440.5  324.61  5445.5  324.85
#Mann=5,-1,0
  4419.3     0.1       0  4930.2    0.12       0  5038.8    0.07       0
  5047.9    0.12       0  5440.5     0.1       0
Bank Sta=5038.8,5047.9
Exp/Cntr=0.3,0.1

Type RM Length L Ch R = 1,10990,395,395,395
BEGIN DESCRIPTION:
Walnut49 20.0
END DESCRIPTION:
XS GIS Cut Line= 3
      2729268.09      6747518.71      2728615.21      6747810.59
      2728195.30      6747897.65
#Sta/Elev= 30
  4329.8  327.33  4394.5  326.53  4452.6  322.94  4463.5  323.06  4529.3  317.67
  4643.0  310.76  4689.4  306.79  4712.6  306.08  4735.8  303.67  4839.1  299.59
  4937.9  295.91  4971.7  295.77  4984.3  296.05  5000.3  290.23  5002.6  286.80
  5003.9  286.30  5012.4  286.80  5022.2  292.48  5030.7  295.45  5075.8  295.18
  5105.4  296.43  5156.5  294.75  5196.2  296.07  5258.6  298.10  5309.7  303.03
  5366.5  310.41  5391.4  312.90  5416.7  314.15  5422.0  315.35  5473.8  320.79
#Mann=6,-1,0
  4329.8    0.12       0  4839.1     0.1       0  4971.7    0.12       0
  5002.6    0.07       0  5012.4    0.12       0  5196.2     0.1       0
Bank Sta=5002.6,5012.4
Exp/Cntr=0.3,0.1

Type RM Length L Ch R = 1,10595,464,464,464
BEGIN DESCRIPTION:
Walnut49 19.0
END DESCRIPTION:
XS GIS Cut Line= 3
      2728998.98      6747340.00      2728659.43      6747418.36
      2728137.10      6747689.97
#Sta/Elev= 30
  4595.7  315.66  4732.2  307.96  4842.3  299.40  4906.6  296.28  4957.2  295.76
  4962.8  291.85  4970.6  292.14  4979.3  289.43  4980.0  285.07  4981.4  284.57
  4989.9  285.07  4997.9  285.51  5001.4  285.80  5007.1  290.31  5015.7  293.63
  5029.2  296.00  5095.5  296.01  5112.0  293.36  5134.1  295.48  5178.3  295.13
  5184.1  294.12  5194.8  293.61  5216.9  295.16  5261.1  294.14  5365.1  297.39
  5410.2  302.67  5438.0  307.12  5444.0  309.34  5466.5  312.31  5532.9  314.34
#Mann=5,-1,0
  4595.7     0.1       0  4980.0    0.07       0  4989.9     0.1       0
  4997.9    0.12       0  5184.1     0.1       0
Bank Sta=4980,4989.9
Exp/Cntr=0.3,0.1

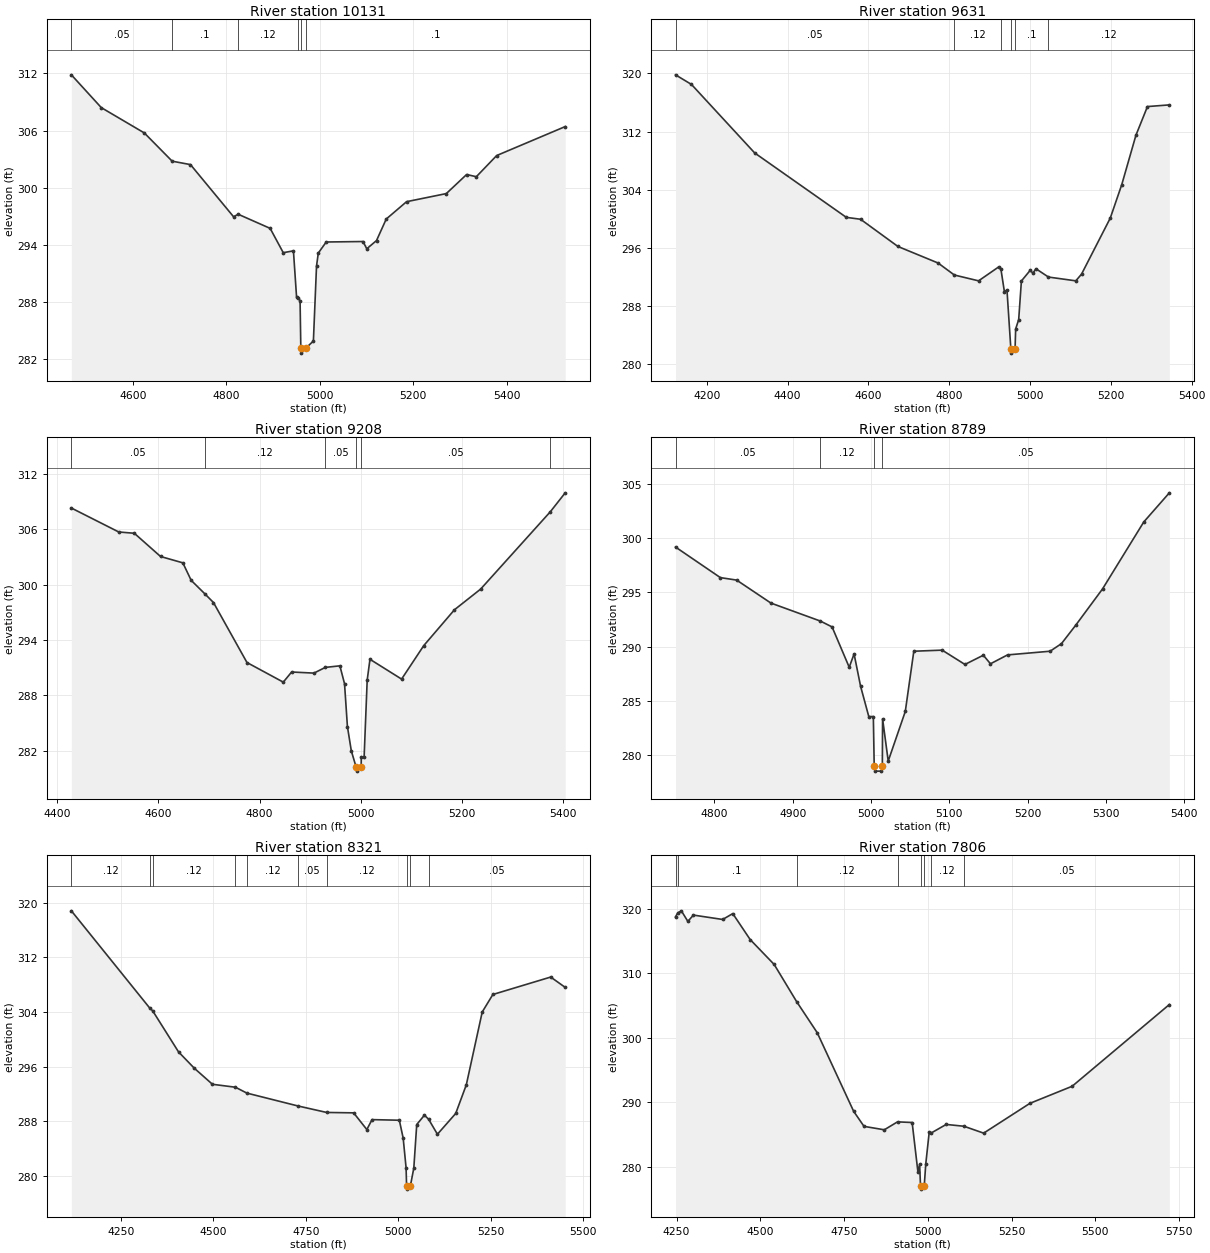
Type RM Length L Ch R = 1,10131,500,500,500
BEGIN DESCRIPTION:
Walnut49 18.0
END DESCRIPTION:
XS GIS Cut Line= 3
      2728775.98      6746811.01      2728376.00      6747161.00
      2728053.51      6747575.04
#Sta/Elev= 30
  4468.8  311.85  4532.8  308.41  4624.9  305.75  4684.4  302.79  4723.6  302.43
  4815.7  296.96  4825.7  297.22  4894.0  295.74  4922.0  293.19  4943.8  293.38
  4950.5  288.53  4953.3  288.40  4958.0  288.17  4959.6  283.15  4961.0  282.65
  4969.8  283.15  4986.5  283.92  4993.2  291.79  4997.0  293.15  5013.9  294.31
  5092.6  294.36  5100.7  293.60  5121.5  294.46  5142.3  296.72  5185.8  298.54
  5270.8  299.39  5314.2  301.39  5335.0  301.16  5378.5  303.38  5525.1  306.42
#Mann=6,-1,0
  4468.8    0.05       0  4684.4     0.1       0  4825.7    0.12       0
  4953.3     0.1       0  4959.6    0.07       0  4969.8     0.1       0
Bank Sta=4959.6,4969.8
Exp/Cntr=0.3,0.1

Type RM Length L Ch R = 1,9631,423,423,423
BEGIN DESCRIPTION:
Walnut49 17.0
END DESCRIPTION:
XS GIS Cut Line= 3
      2728628.10      6746478.11      2727985.59      6747005.70
      2727725.43      6747297.08
#Sta/Elev= 30
  4122.8  319.79  4162.3  318.47  4318.7  309.06  4545.5  300.21  4580.7  299.95
  4673.2  296.21  4772.5  293.94  4812.8  292.29  4872.7  291.49  4922.2  293.39
  4928.0  293.11  4936.6  290.01  4943.0  290.24  4952.7  282.06  4954.1  281.56
  4963.0  282.06  4964.5  284.88  4972.0  286.17  4978.7  291.47  5000.4  292.93
  5007.2  292.55  5014.7  293.15  5045.7  292.01  5113.3  291.49  5127.5  292.41
  5198.6  300.11  5227.0  304.70  5262.1  311.49  5290.6  315.43  5344.8  315.66
#Mann=6,-1,0
  4122.8    0.05       0  4812.8    0.12       0  4928.0     0.1       0
  4952.7    0.07       0  4963.0     0.1       0  5045.7    0.12       0
Bank Sta=4952.7,4963
Exp/Cntr=0.3,0.1

Type RM Length L Ch R = 1,9208,419,419,419
BEGIN DESCRIPTION:
Walnut49 16.0
END DESCRIPTION:
XS GIS Cut Line= 3
      2728236.34      6746493.78      2727726.00      6746761.00
      2727361.33      6746926.18
#Sta/Elev= 30
  4428.0  308.33  4521.7  305.73  4552.5  305.59  4604.3  303.07  4648.4  302.38
  4664.9  300.48  4691.3  299.05  4709.0  298.07  4775.2  291.56  4847.0  289.43
  4863.5  290.53  4907.6  290.41  4930.1  291.03  4958.9  291.20  4968.1  289.26
  4973.8  284.61  4981.5  281.97  4990.7  280.27  4992.1  279.77  5001.0  280.27
  5001.2  281.25  5006.8  281.25  5012.9  289.65  5018.4  291.91  5080.9  289.76
  5124.8  293.40  5185.5  297.29  5237.2  299.53  5375.2  307.94  5404.4  309.98
#Mann=6,-1,0
  4428.0    0.05       0  4691.3    0.12       0  4930.1    0.05       0
  4990.7    0.04       0  5001.0    0.05       0  5375.2     0.1       0
Bank Sta=4990.7,5001
Exp/Cntr=0.3,0.1

Type RM Length L Ch R = 1,8789,468,468,468
BEGIN DESCRIPTION:
Walnut49 15.0
END DESCRIPTION:
XS GIS Cut Line= 3
      2727925.98      6746261.01      2727726.00      6746411.00
      2727375.97      6746561.01
#Sta/Elev= 30
  4750.2  299.18  4807.5  296.36  4828.3  296.13  4872.1  294.01  4935.3  292.35
  4950.2  291.81  4972.1  288.09  4978.3  289.32  4986.6  286.34  4997.1  283.54
  5002.9  283.54  5004.0  279.01  5005.5  278.51  5013.0  278.51  5014.4  279.01
  5014.7  283.34  5021.9  279.44  5043.7  284.01  5054.6  289.57  5090.8  289.67
  5119.9  288.35  5143.4  289.20  5152.5  288.41  5174.3  289.23  5228.7  289.57
  5243.2  290.27  5261.3  291.96  5295.7  295.32  5348.3  301.49  5381.0  304.18
#Mann=4,-1,0
  4750.2    0.05       0  4935.3    0.12       0  5004.0    0.07       0
  5014.4    0.05       0
Bank Sta=5004,5014.4
Exp/Cntr=0.3,0.1

Type RM Length L Ch R = 1,8321,515,515,515
BEGIN DESCRIPTION:
Walnut49 14.0
END DESCRIPTION:
XS GIS Cut Line= 3
      2728026.01      6745460.99      2727426.00      6746111.00
      2727140.21      6746461.44
#Sta/Elev= 30
  4115.4  318.82  4327.6  304.59  4335.4  304.20  4405.5  298.18  4448.0  295.80
  4497.3  293.44  4559.5  293.01  4590.5  292.15  4728.6  290.27  4806.4  289.32
  4879.5  289.26  4915.2  286.82  4929.4  288.27  5003.2  288.18  5013.6  285.56
  5021.5  281.21  5022.8  278.60  5024.3  278.10  5033.2  278.60  5042.4  281.19
  5050.3  287.55  5071.1  288.92  5082.4  288.33  5106.3  286.13  5155.8  289.17
  5184.5  293.36  5227.6  304.02  5256.4  306.58  5412.9  309.13  5452.2  307.62
#Mann=10,-1,0
  4115.4    0.12       0  4327.6    0.05       0  4335.4    0.12       0
  4559.5     0.1       0  4590.5    0.12       0  4728.6    0.05       0
  4806.4    0.12       0  5022.8    0.07       0  5033.2    0.12       0
  5082.4    0.05       0
Bank Sta=5022.8,5033.2
Exp/Cntr=0.3,0.1

Type RM Length L Ch R = 1,7806,435,435,435
BEGIN DESCRIPTION:
Walnut49 13.0
END DESCRIPTION:
XS GIS Cut Line= 3
      2727254.31      6745125.19      2727092.37      6745767.72
      2726946.20      6746566.43
#Sta/Elev= 30
  4246.7  318.76  4253.3  319.37  4264.2  319.70  4283.6  318.06  4300.1  319.04
  4387.5  318.36  4417.7  319.27  4469.6  315.25  4541.4  311.38  4608.3  305.63
  4669.9  300.80  4778.6  288.62  4809.6  286.28  4870.2  285.75  4909.6  286.98
  4953.3  286.88  4970.5  279.23  4975.6  280.38  4978.3  277.05  4979.8  276.55
  4989.4  277.05  4994.0  280.47  5004.2  285.35  5008.7  285.21  5055.0  286.58
  5107.9  286.30  5166.8  285.23  5304.9  289.85  5431.1  292.50  5721.3  305.17
#Mann=8,-1,0
  4246.7    0.12       0  4253.3     0.1       0  4608.3    0.12       0
  4909.6     0.1       0  4978.3    0.07       0  4989.4     0.1       0
  5008.7    0.12       0  5107.9    0.05       0
Bank Sta=4978.3,4989.4
Exp/Cntr=0.3,0.1

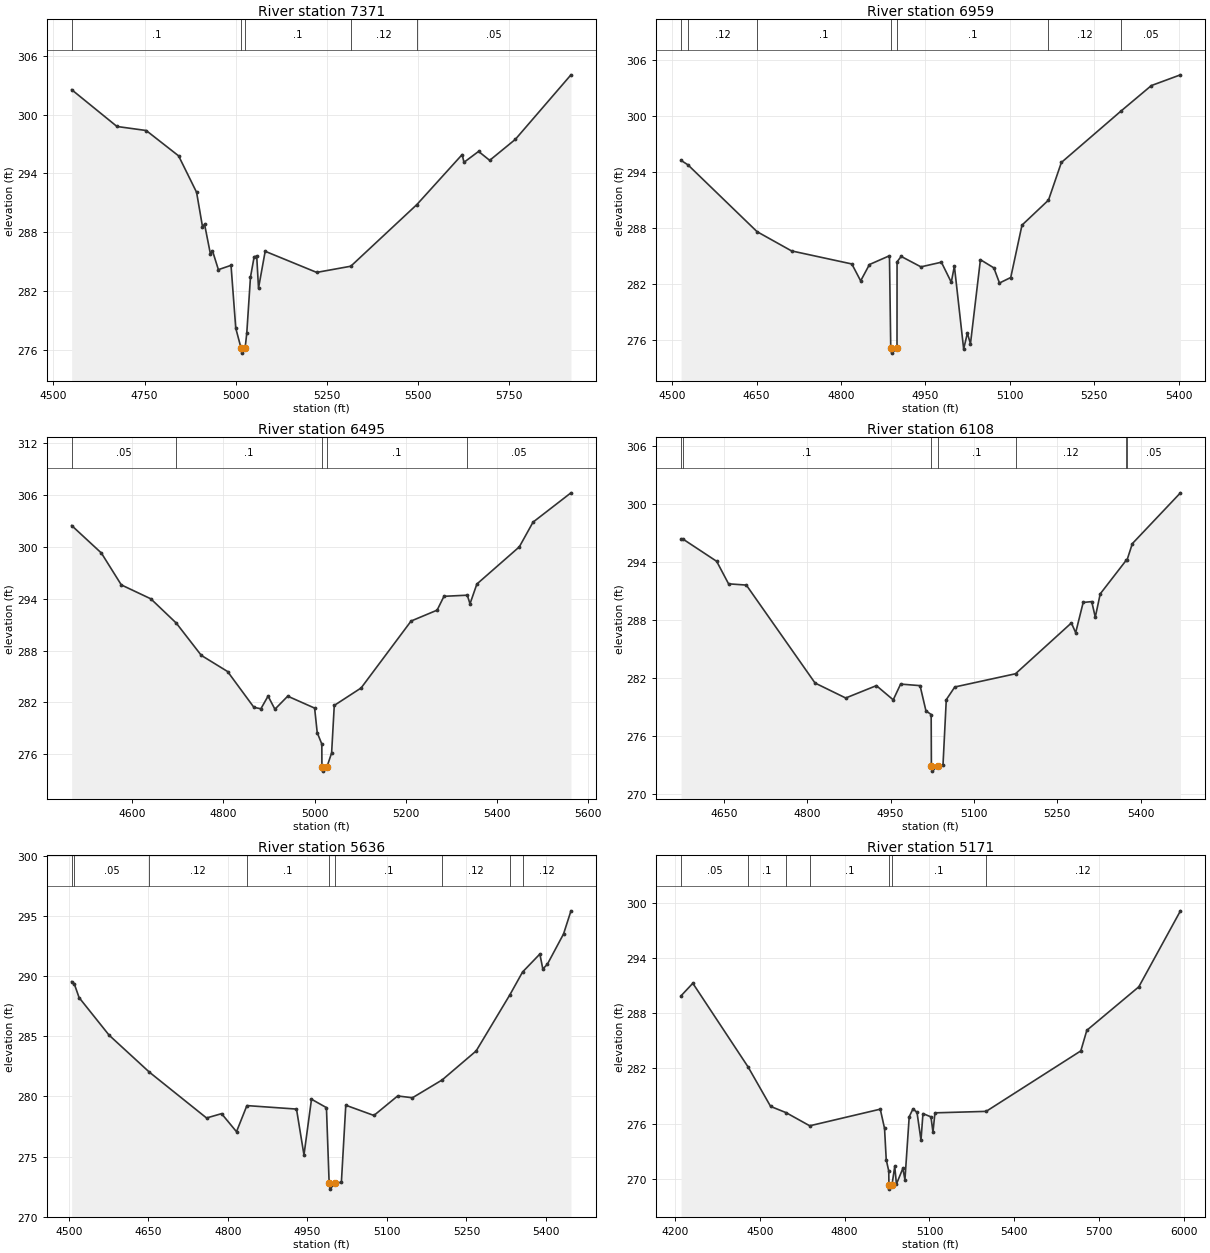
Type RM Length L Ch R = 1,7371,412,412,412
BEGIN DESCRIPTION:
Walnut49 12.0
END DESCRIPTION:
XS GIS Cut Line= 3
      2726549.14      6745261.07      2726747.62      6745626.69
      2726883.43      6746572.16
#Sta/Elev= 30
  4549.8  302.53  4674.3  298.78  4754.5  298.37  4843.5  295.79  4892.9  292.08
  4909.1  288.59  4914.8  288.83  4930.9  285.80  4936.6  286.12  4952.8  284.20
  4987.5  284.64  5000.5  278.24  5015.1  276.20  5016.6  275.70  5026.2  276.20
  5030.8  277.76  5040.9  283.44  5051.0  285.51  5058.0  285.59  5063.0  282.32
  5081.3  286.07  5222.7  283.92  5316.4  284.55  5497.9  290.83  5622.2  295.92
  5627.2  295.13  5667.3  296.24  5697.8  295.33  5768.3  297.47  5921.0  304.04
#Mann=5,-1,0
  4549.8     0.1       0  5015.1    0.07       0  5026.2     0.1       0
  5316.4    0.12       0  5497.9    0.05       0
Bank Sta=5015.1,5026.2
Exp/Cntr=0.3,0.1

Type RM Length L Ch R = 1,6959,464,464,464
BEGIN DESCRIPTION:
Walnut49 11.0
END DESCRIPTION:
XS GIS Cut Line= 5
      2726359.29      6745560.18      2726532.77      6745853.90
      2726615.21      6745920.88      2726654.71      6746008.47
      2726658.82      6746352.72
#Sta/Elev= 30
  4515.7  295.27  4527.8  294.80  4650.7  287.64  4712.0  285.58  4819.2  284.18
  4834.9  282.37  4850.5  284.12  4886.1  285.06  4888.4  275.13  4889.9  274.63
  4899.5  275.13  4899.6  284.41  4906.9  284.99  4942.1  283.87  4978.4  284.37
  4996.0  282.22  5001.5  283.95  5018.0  275.07  5024.6  276.77  5030.1  275.63
  5047.8  284.64  5071.7  283.76  5081.7  282.14  5101.7  282.73  5121.7  288.34
  5168.8  291.02  5191.7  295.05  5298.1  300.58  5351.7  303.29  5403.4  304.44
#Mann=7,-1,0
  4515.7    0.05       0  4527.8    0.12       0  4650.7     0.1       0
  4888.4    0.07       0  4899.5     0.1       0  5168.8    0.12       0
  5298.1    0.05       0
Bank Sta=4888.4,4899.5
Exp/Cntr=0.3,0.1

Type RM Length L Ch R = 1,6495,387,387,387
BEGIN DESCRIPTION:
Walnut49 10.0
END DESCRIPTION:
XS GIS Cut Line= 3
      2725984.99      6745574.47      2726324.51      6746164.71
      2726554.36      6746509.49
#Sta/Elev= 30
  4466.9  302.47  4532.1  299.29  4575.9  295.60  4640.6  293.99  4696.5  291.18
  4751.3  287.45  4809.0  285.58  4866.7  281.44  4882.0  281.27  4897.8  282.74
  4912.8  281.22  4940.9  282.73  4999.9  281.35  5005.6  278.51  5015.7  277.19
  5015.9  274.56  5017.4  274.06  5027.0  274.56  5037.2  276.17  5043.0  281.66
  5101.9  283.68  5211.5  291.42  5268.6  292.68  5283.6  294.28  5334.8  294.41
  5340.7  293.41  5355.8  295.70  5448.9  300.00  5479.0  302.86  5562.2  306.25
#Mann=5,-1,0
  4466.9    0.05       0  4696.5     0.1       0  5015.9    0.07       0
  5027.0     0.1       0  5334.8    0.05       0
Bank Sta=5015.9,5027
Exp/Cntr=0.3,0.1

Type RM Length L Ch R = 1,6108,472,472,472
BEGIN DESCRIPTION:
Walnut49 9.0
END DESCRIPTION:
XS GIS Cut Line= 3
      2725776.02      6745811.05      2725926.00      6746211.00
      2726175.97      6746610.96
#Sta/Elev= 30
  4573.1  296.42  4575.7  296.42  4637.1  294.09  4658.5  291.76  4690.5  291.63
  4814.2  281.49  4869.4  279.94  4924.6  281.22  4954.9  279.75  4968.2  281.38
  5003.2  281.22  5013.8  278.61  5023.2  278.23  5023.6  272.87  5025.1  272.37
  5034.7  272.87  5044.5  273.01  5050.4  279.77  5065.7  281.08  5175.0  282.45
  5275.6  287.71  5283.3  286.70  5296.8  289.83  5312.2  289.92  5318.6  288.31
  5327.5  290.72  5374.7  294.23  5375.9  294.25  5385.3  295.92  5471.9  301.18
#Mann=7,-1,0
  4573.1    0.05       0  4575.7     0.1       0  5023.6    0.07       0
  5034.7     0.1       0  5175.0    0.12       0  5374.7     0.1       0
  5375.9    0.05       0
Bank Sta=5023.6,5034.7
Exp/Cntr=0.3,0.1

Type RM Length L Ch R = 1,5636,465,465,465
BEGIN DESCRIPTION:
Walnut49 8.0
END DESCRIPTION:
XS GIS Cut Line= 3
      2725275.99      6746210.99      2725626.00      6746561.00
      2726026.00      6746761.00
#Sta/Elev= 30
  4505.0  289.53  4510.0  289.34  4519.1  288.20  4575.7  285.08  4651.9  282.00
  4759.6  278.20  4787.9  278.56  4816.1  277.06  4835.7  279.23  4929.3  278.94
  4943.4  275.13  4957.6  279.76  4985.8  279.06  4990.9  272.79  4992.4  272.29
  5002.0  272.79  5014.0  272.86  5022.3  279.26  5075.4  278.41  5120.2  280.03
  5148.1  279.88  5204.1  281.36  5268.3  283.77  5332.0  288.44  5355.9  290.33
  5388.5  291.82  5394.1  290.58  5402.5  290.96  5433.2  293.49  5447.2  295.41
#Mann=9,-1,0
  4505.0    0.12       0  4510.0    0.05       0  4651.9    0.12       0
  4835.7     0.1       0  4990.9    0.07       0  5002.0     0.1       0
  5204.1    0.12       0  5332.0    0.05       0  5355.9    0.12       0
Bank Sta=4990.9,5002
Exp/Cntr=0.3,0.1

Type RM Length L Ch R = 1,5171,368,368,368
BEGIN DESCRIPTION:
Walnut49 7.0
END DESCRIPTION:
XS GIS Cut Line= 3
      2724893.25      6746206.47      2725342.49      6746885.56
      2726011.02      6747564.54
#Sta/Elev= 30
  4221.2  289.91  4262.6  291.27  4458.5  282.15  4537.9  277.87  4592.7  277.19
  4676.4  275.76  4926.0  277.57  4941.1  275.48  4947.1  272.07  4956.1  270.83
  4956.6  269.37  4958.1  268.87  4967.7  269.37  4977.2  271.35  4983.2  269.42
  5006.0  271.13  5013.3  269.89  5028.4  276.75  5041.8  277.60  5056.0  277.22
  5070.1  274.20  5077.1  277.09  5105.4  276.73  5112.5  275.07  5119.5  277.17
  5300.7  277.33  5635.7  283.91  5657.0  286.15  5840.9  290.88  5988.3  299.15
#Mann=7,-1,0
  4221.2    0.05       0  4458.5     0.1       0  4592.7    0.12       0
  4676.4     0.1       0  4956.6    0.07       0  4967.7     0.1       0
  5300.7    0.12       0
Bank Sta=4956.6,4967.7
Exp/Cntr=0.3,0.1

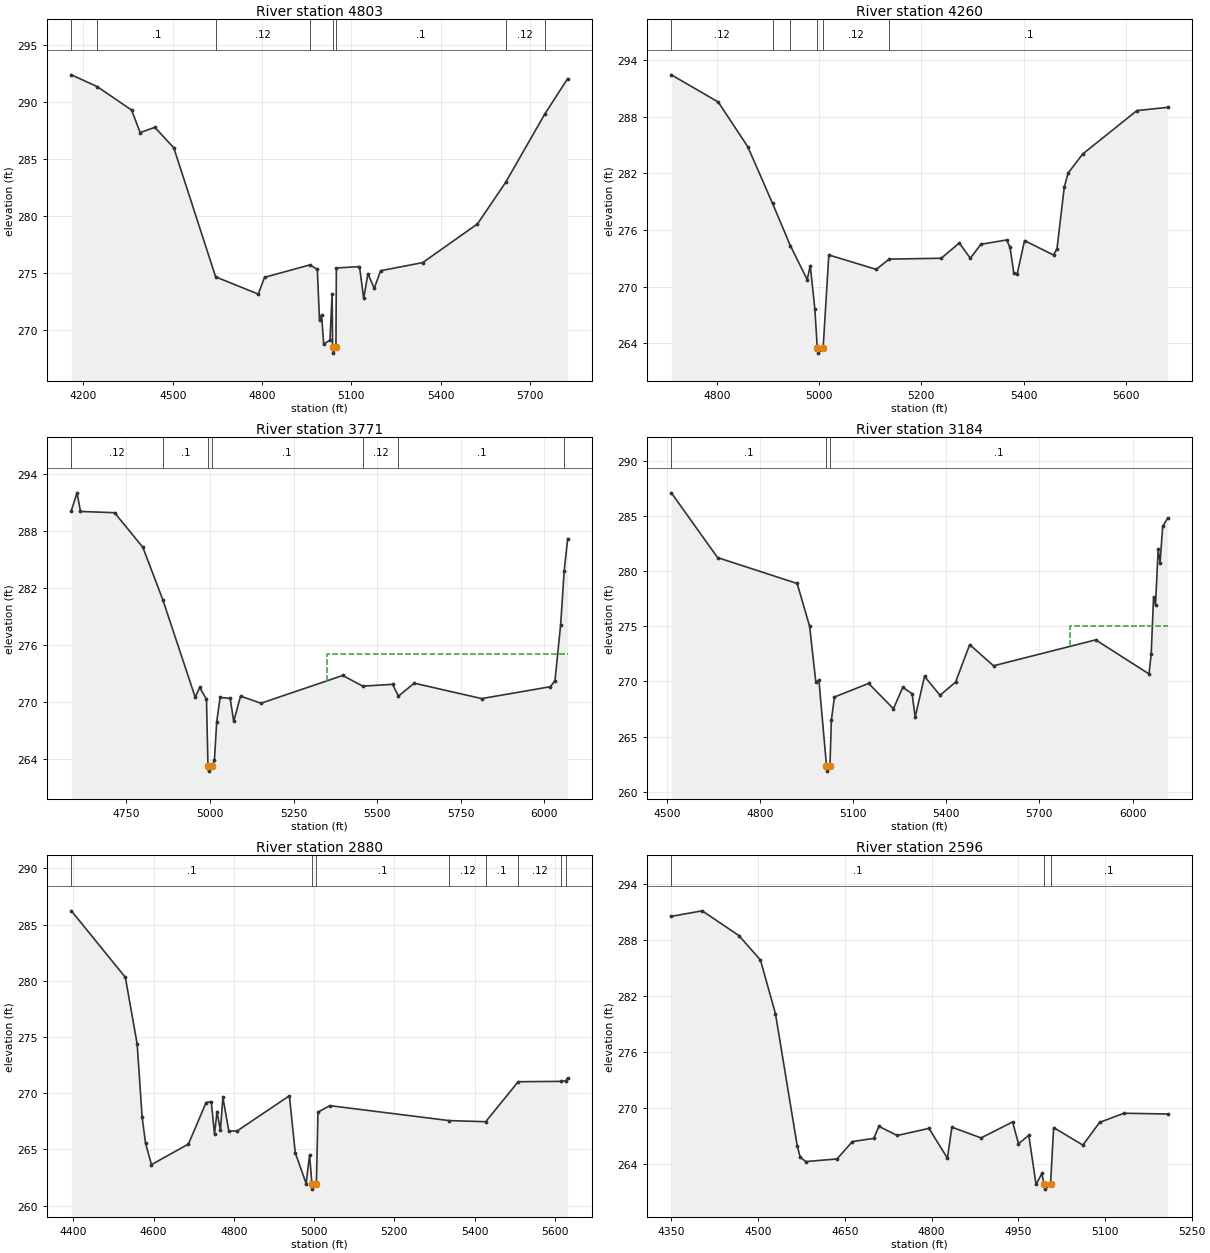
Type RM Length L Ch R = 1,4803,543,543,543
BEGIN DESCRIPTION:
Walnut49 6.0
END DESCRIPTION:
XS GIS Cut Line= 3
      2724407.46      6746493.77      2724980.13      6746993.67
      2725608.06      6747647.23
#Sta/Elev= 30
  4159.6  292.36  4246.4  291.33  4362.0  289.27  4390.5  287.30  4439.9  287.76
  4503.5  285.97  4644.1  274.66  4787.3  273.15  4808.2  274.62  4960.6  275.71
  4985.5  275.32  4992.8  270.85  4999.7  271.33  5006.9  268.77  5028.0  269.12
  5035.2  273.16  5036.9  268.48  5038.4  267.98  5048.0  268.48  5049.4  275.44
  5127.1  275.56  5141.2  272.77  5155.4  274.94  5176.7  273.65  5197.8  275.20
  5339.3  275.91  5523.3  279.30  5617.8  282.94  5750.0  288.96  5826.1  292.03
#Mann=8,-1,0
  4159.6    0.12       0  4246.4     0.1       0  4644.1    0.12       0
  4960.6     0.1       0  5036.9    0.07       0  5048.0     0.1       0
  5617.8    0.12       0  5750.0     0.1       0
Bank Sta=5036.9,5048
Exp/Cntr=0.3,0.1

Type RM Length L Ch R = 1,4260,489,489,489
BEGIN DESCRIPTION:
Walnut49 5.0
END DESCRIPTION:
XS GIS Cut Line= 3
      2724511.96      6746916.91      2724676.00      6747161.00
      2725128.35      6747663.90
#Sta/Elev= 30
  4711.3  292.45  4802.9  289.57  4860.8  284.82  4909.2  278.81  4943.9  274.34
  4976.9  270.74  4982.9  272.22  4991.9  267.62  4996.7  263.44  4998.3  262.94
  5008.0  263.44  5019.2  273.35  5111.9  271.82  5137.3  272.91  5239.0  273.00
  5274.4  274.62  5295.8  273.00  5316.7  274.48  5366.8  274.94  5373.5  274.16
  5381.0  271.40  5387.7  271.38  5401.9  274.87  5458.7  273.34  5465.4  274.02
  5479.6  280.54  5487.1  282.03  5515.5  284.05  5621.7  288.66  5681.8  289.00
#Mann=6,-1,0
  4711.3    0.12       0  4909.2     0.1       0  4943.9    0.12       0
  4996.7    0.07       0  5008.0    0.12       0  5137.3     0.1       0
Bank Sta=4996.7,5008
Exp/Cntr=0.3,0.1

Type RM Length L Ch R = 1,3771,587,587,587
BEGIN DESCRIPTION:
Walnut49 4.0
END DESCRIPTION:
XS GIS Cut Line= 2
      2724151.52      6746854.19      2724428.38      6748311.62
#Sta/Elev= 30
  4585.9  290.12  4603.0  291.98  4613.2  290.02  4715.0  289.89  4799.5  286.26
  4859.5  280.71  4956.2  270.47  4969.5  271.51  4989.8  270.26  4994.3  263.21
  4995.9  262.71  5005.6  263.21  5013.5  263.83  5020.3  267.87  5030.5  270.46
  5060.7  270.36  5071.2  267.93  5091.6  270.60  5152.7  269.85  5397.0  272.77
  5456.8  271.65  5546.1  271.84  5563.6  270.60  5610.7  271.96  5812.4  270.34
  6017.9  271.59  6031.5  272.24  6048.4  278.12  6059.0  283.77  6069.4  287.17
#Mann=7,-1,0
  4585.9    0.12       0  4859.5     0.1       0  4994.3    0.07       0
  5005.6     0.1       0  5456.8    0.12       0  5563.6     0.1       0
  6059.0    0.12       0
#XS Ineff=2,0
       0                 5350.00    0.00  275.00
Permanent Ineff=
       F       F
Bank Sta=4994.3,5005.6
Exp/Cntr=0.3,0.1

Type RM Length L Ch R = 1,3184,304,304,304
BEGIN DESCRIPTION:
Walnut49 3.0
END DESCRIPTION:
XS GIS Cut Line= 4
      2723988.19      6746971.21      2723670.96      6747131.06
      2723664.45      6747737.03      2724036.59      6748254.10
#Sta/Elev= 30
  4514.7  287.10  4663.5  281.23  4919.9  278.88  4959.9  275.00  4979.9  269.96
  4989.9  270.11  5014.2  262.37  5015.8  261.87  5025.5  262.37  5029.9  266.47
  5039.9  268.59  5149.9  269.82  5229.9  267.53  5259.9  269.47  5289.9  268.89
  5299.9  266.77  5329.9  270.46  5379.9  268.75  5429.9  269.94  5475.4  273.34
  5552.1  271.42  5881.1  273.77  6052.9  270.68  6059.9  272.47  6067.6  277.68
  6073.8  276.94  6082.3  281.97  6088.5  280.75  6096.9  284.06  6113.0  284.81
#Mann=3,-1,0
  4514.7     0.1       0  5014.2    0.07       0  5025.5     0.1       0
#XS Ineff=2,0
       0                 5800.00    0.00  275.00
Permanent Ineff=
       F       F
Bank Sta=5014.2,5025.5
Exp/Cntr=0.3,0.1

Type RM Length L Ch R = 1,2880,284,284,284
BEGIN DESCRIPTION:
Walnut49 2.5
END DESCRIPTION:
XS GIS Cut Line= 3
      2723919.21      6746796.65      2723372.70      6747189.32
      2723020.77      6747630.25
#Sta/Elev= 30
  4394.9  286.23  4529.5  280.31  4558.9  274.38  4571.3  267.87  4579.8  265.55
  4594.6  263.64  4686.7  265.47  4730.8  269.17  4743.6  269.25  4751.7  266.36
  4757.9  268.34  4766.5  266.70  4772.6  269.63  4787.3  266.63  4808.2  266.64
  4938.3  269.77  4953.0  264.70  4980.1  261.96  4988.7  264.52  4994.4  261.96
  4995.9  261.46  5005.7  261.96  5009.6  268.31  5039.0  268.89  5336.6  267.56
  5427.7  267.46  5508.7  271.02  5614.4  271.05  5627.0  271.10  5632.0  271.34
#Mann=8,-1,0
  4394.9     0.1       0  4994.4    0.07       0  5005.7     0.1       0
  5336.6    0.12       0  5427.7     0.1       0  5508.7    0.12       0
  5614.4    0.05       0  5627.0    0.12       0
Bank Sta=4994.4,5005.7
Exp/Cntr=0.3,0.1

Type RM Length L Ch R = 1,2596,283,283,283
BEGIN DESCRIPTION:
Walnut49 2.0
END DESCRIPTION:
XS GIS Cut Line= 3
      2723907.09      6746727.82      2723352.46      6746910.00
      2723081.27      6746954.52
#Sta/Elev= 30
  4349.8  290.51  4403.2  291.10  4466.7  288.45  4503.9  285.84  4529.9  280.09
  4567.5  265.96  4572.8  264.72  4582.5  264.27  4636.4  264.55  4662.9  266.41
  4700.0  266.75  4708.8  268.04  4740.4  267.06  4795.4  267.82  4827.3  264.64
  4835.1  267.95  4885.6  266.80  4940.1  268.51  4950.3  266.17  4968.1  267.09
  4980.7  261.82  4990.8  263.00  4994.4  261.82  4995.9  261.32  5005.7  261.82
  5011.1  267.91  5061.7  266.03  5090.6  268.46  5132.7  269.44  5208.4  269.36
#Mann=3,-1,0
  4349.8     0.1       0  4994.4    0.07       0  5005.7     0.1       0
Bank Sta=4994.4,5005.7
Exp/Cntr=0.3,0.1

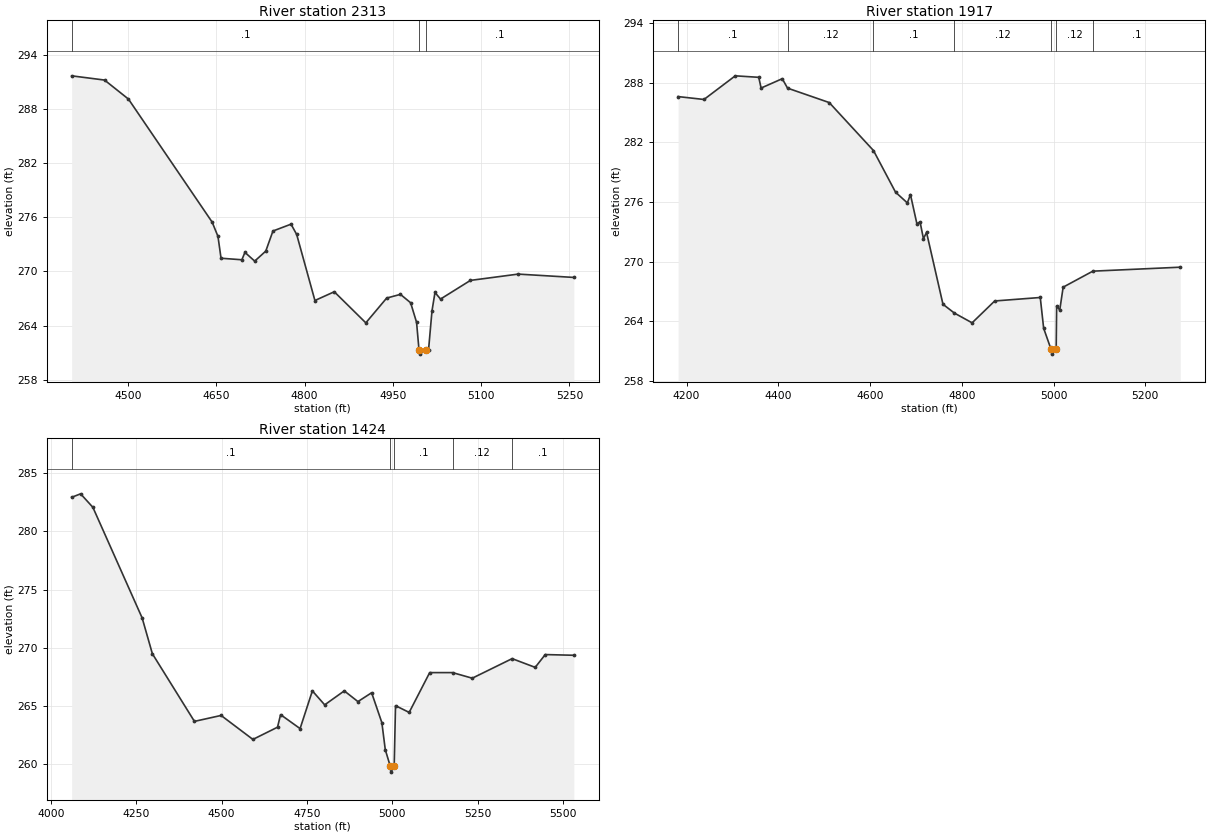
Type RM Length L Ch R = 1,2313,396,396,396
BEGIN DESCRIPTION:
Walnut49 1.6
END DESCRIPTION:
XS GIS Cut Line= 4
      2723907.05      6746699.48      2723562.97      6746610.43
      2723202.67      6746675.20      2723109.54      6746768.33
#Sta/Elev= 30
  4404.3  291.71  4460.2  291.24  4500.8  289.13  4643.0  275.48  4652.9  273.89
  4658.1  271.47  4693.5  271.30  4698.7  272.12  4715.3  271.15  4734.1  272.26
  4746.3  274.49  4777.0  275.25  4786.6  274.11  4817.6  266.78  4850.5  267.75
  4904.1  264.30  4939.5  267.05  4962.9  267.46  4980.2  266.53  4990.3  264.36
  4994.4  261.33  4995.9  260.83  5005.7  261.33  5010.7  261.33  5016.5  265.63
  5021.6  267.67  5031.0  266.94  5081.8  269.01  5162.9  269.71  5257.5  269.34
#Mann=3,-1,0
  4404.3     0.1       0  4994.4    0.07       0  5005.7     0.1       0
Bank Sta=4994.4,5005.7
Exp/Cntr=0.3,0.1

Type RM Length L Ch R = 1,1917,493,493,493
BEGIN DESCRIPTION:
Walnut49 1.3
END DESCRIPTION:
XS GIS Cut Line= 4
      2723761.30      6746290.61      2723291.73      6746197.51
      2722996.21      6746468.74      2723080.90      6746666.33
#Sta/Elev= 30
  4181.5  286.61  4237.9  286.32  4306.1  288.70  4357.3  288.55  4362.4  287.47
  4408.5  288.41  4420.1  287.46  4510.9  286.01  4607.4  281.18  4655.5  276.99
  4681.2  275.91  4688.0  276.75  4702.1  273.80  4708.9  274.01  4716.3  272.31
  4723.1  272.94  4758.9  265.71  4783.5  264.83  4822.4  263.84  4871.7  266.04
  4971.0  266.39  4978.4  263.29  4994.4  261.19  4995.9  260.69  5005.7  261.19
  5006.7  265.55  5013.5  265.13  5020.9  267.43  5085.6  269.04  5276.3  269.44
#Mann=7,-1,0
  4181.5     0.1       0  4420.1    0.12       0  4607.4     0.1       0
  4783.5    0.12       0  4994.4    0.07       0  5005.7    0.12       0
  5085.6     0.1       0
Bank Sta=4994.4,5005.7
Exp/Cntr=0.3,0.1

Type RM Length L Ch R = 1,1424,0,0,0
BEGIN DESCRIPTION:
Walnut49 1.0
END DESCRIPTION:
XS GIS Cut Line= 4
      2723506.30      6745553.83      2722886.91      6745966.76
      2722899.06      6746286.57      2723052.90      6746663.09
#Sta/Elev= 30
  4060.8  282.92  4087.0  283.22  4123.0  282.06  4267.3  272.56  4297.3  269.48
  4420.5  263.67  4498.6  264.18  4591.8  262.12  4663.9  263.17  4672.9  264.25
  4730.0  263.05  4766.0  266.29  4802.1  265.09  4859.5  266.29  4899.5  265.37
  4939.6  266.13  4969.6  263.56  4979.6  261.24  4994.3  259.81  4995.9  259.31
  5005.7  259.81  5009.6  265.02  5049.6  264.44  5109.7  267.86  5176.7  267.86
  5234.4  267.38  5351.2  269.06  5418.8  268.31  5448.2  269.41  5532.0  269.35
#Mann=5,-1,0
  4060.8     0.1       0  4994.3    0.07       0  5005.7     0.1       0
  5176.7    0.12       0  5351.2     0.1       0
Bank Sta=4994.3,5005.7
Exp/Cntr=0.3,0.1

Chan Stop Cuts=-1