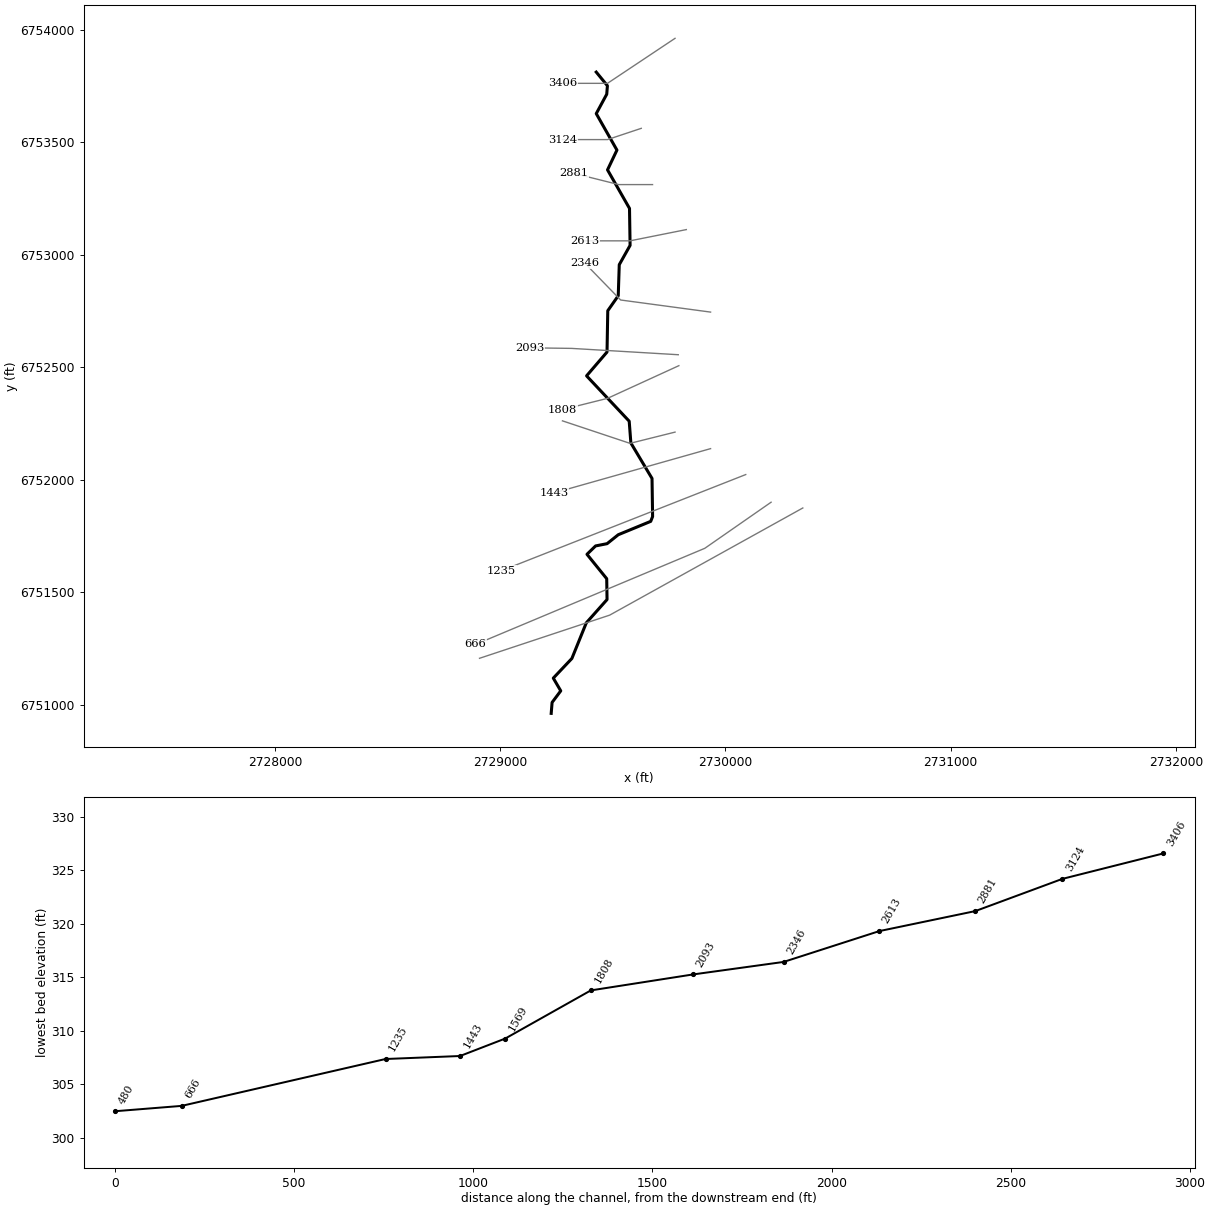
--- Walnut50.prj (project) ---

Proj Title=Walnut50 Base Level Engineering
Current Plan=p01
Default Exp/Contr=0.3,0.1
English Units
Geom File=g01
Flow File=f01
Plan File=p01
BEGIN DESCRIPTION:
Walnut50
END DESCRIPTION:

--- Walnut50.p01 (plan) ---

Plan Title=Multiple Run
Short Identifier=Multiple
Geom File=g01
Flow File=f01
Subcritical Flow
K Sum by GR= 0
Std Step Tol= 0.01
Critical Tol= 0.01
Num of Std Step Trials= 20
Max Error Tol= 0.3
Flow Tol Ratio= 0.001
Split Flow NTrial= 30
Split Flow Tol= 0.02
Split Flow Ratio= 0.02
Log Output Level= 0
Friction Slope Method= 1
Unsteady Friction Slope Method= 2
Unsteady Bridges Friction Slope Method= 1
Parabolic Critical Depth
Global Vel Dist=  1 , 1 , 1
Global Log Level= 0
CheckData=True
Encroach Param= -1, 0, 0, 0
BEGIN DESCRIPTION:
Multiple Run
END DESCRIPTION:

--- Walnut50.f01 (steady flow) ---

Flow Title=Multiple
Number of Profiles=7
Profile Names=10-year,25-year,50-year,1pct_min,100-year,1pct_plu,500-year
River Rch & RM= Walnut50,Reach-1,3406
     290     375     442     259     518    1033     711
Boundary for River Rch & Prof#=Walnut50,Reach-1,1
Up Type=0
Dn Type=3
Dn Slope=0.005
Boundary for River Rch & Prof#=Walnut50,Reach-1,2
Up Type=0
Dn Type=3
Dn Slope=0.005
Boundary for River Rch & Prof#=Walnut50,Reach-1,3
Up Type=0
Dn Type=3
Dn Slope=0.005
Boundary for River Rch & Prof#=Walnut50,Reach-1,4
Up Type=0
Dn Type=3
Dn Slope=0.005
Boundary for River Rch & Prof#=Walnut50,Reach-1,5
Up Type=0
Dn Type=3
Dn Slope=0.005
Boundary for River Rch & Prof#=Walnut50,Reach-1,6
Up Type=0
Dn Type=3
Dn Slope=0.005
Boundary for River Rch & Prof#=Walnut50,Reach-1,7
Up Type=0
Dn Type=3
Dn Slope=0.005

--- Walnut50.g01 (geometry) ---

Geom Title=Existing Conditions

River Reach=Walnut50,Reach-1
Reach XY= 30
      2729426.00      6753811.00      2729475.66      6753750.34
      2729472.62      6753712.67      2729426.08      6753626.39
      2729517.93      6753464.31      2729476.14      6753376.41
      2729573.76      6753205.07      2729576.36      6753040.85
      2729528.27      6752955.06      2729523.73      6752816.94
      2729477.22      6752750.49      2729473.92      6752566.85
      2729383.08      6752460.99      2729572.39      6752259.50
      2729579.83      6752162.59      2729673.76      6752005.07
      2729676.34      6751835.78      2729667.91      6751814.35
      2729523.80      6751754.92      2729474.20      6751715.19
      2729423.13      6751705.17      2729384.84      6751667.95
      2729472.52      6751559.50      2729474.03      6751466.90
      2729381.85      6751363.29      2729317.82      6751204.94
      2729235.30      6751117.66      2729268.42      6751061.07
      2729229.98      6751009.64      2729226.00      6750961.00

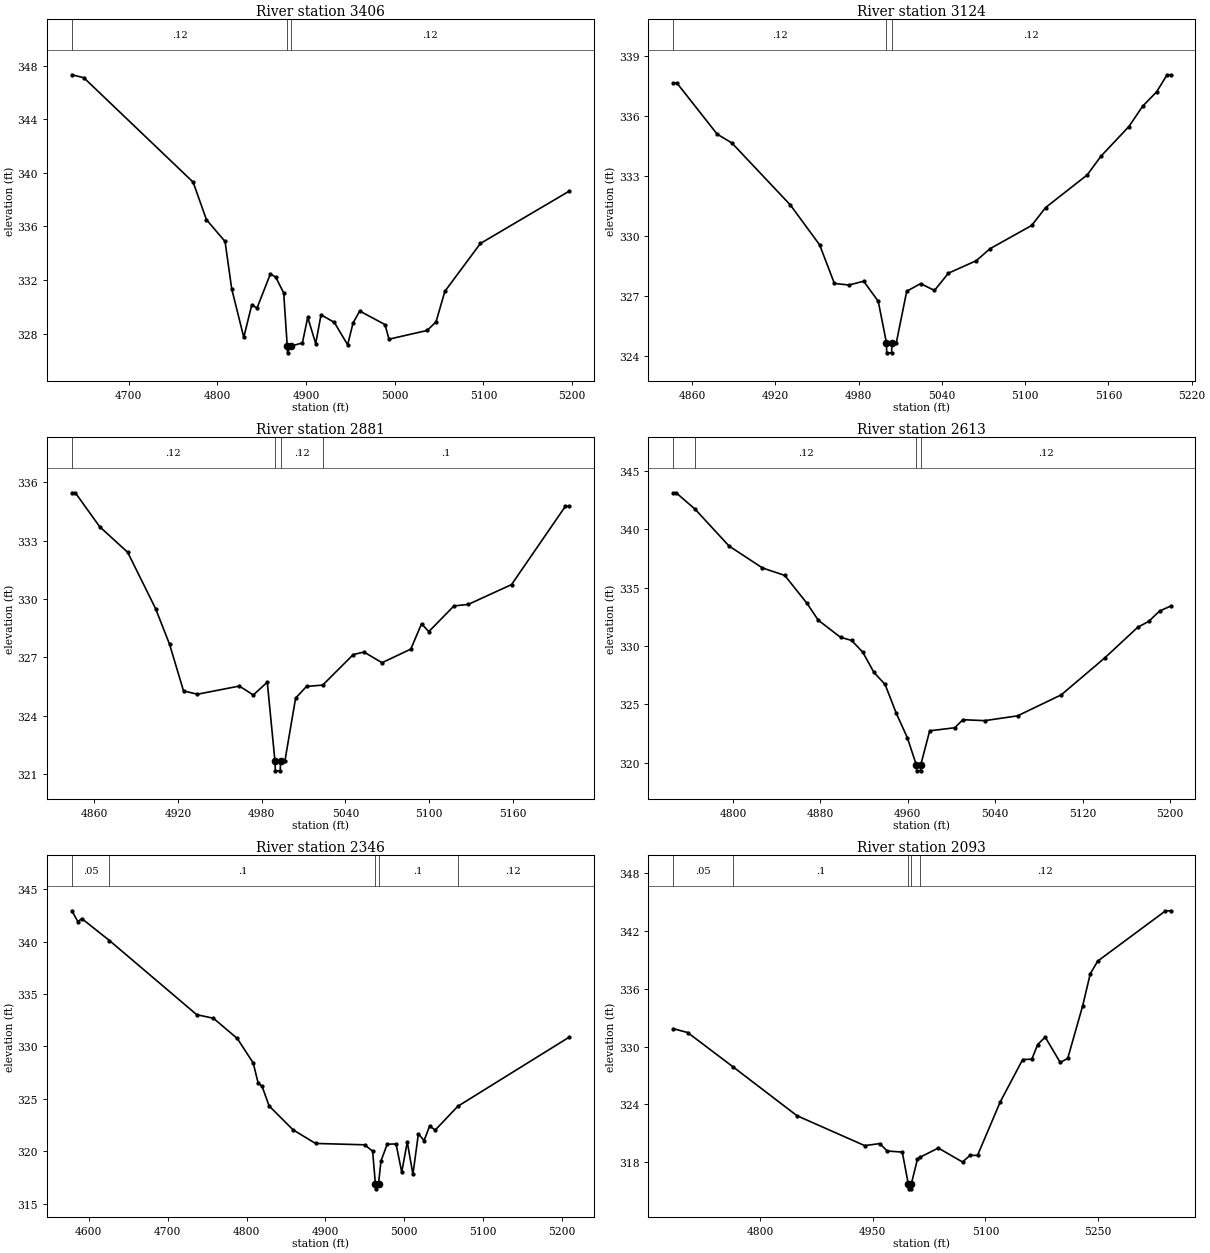
Type RM Length L Ch R = 1,3406,282,282,282
BEGIN DESCRIPTION:
Walnut50 9.0
END DESCRIPTION:
XS GIS Cut Line= 3
      2729775.97      6753960.98      2729476.00      6753761.00
      2729276.02      6753761.00
#Sta/Elev= 30
  4636.0  347.31  4649.5  347.09  4772.7  339.30  4787.7  336.50  4808.7  334.87
  4816.2  331.34  4829.8  327.72  4838.8  330.13  4844.8  329.91  4859.8  332.45
  4865.8  332.21  4874.8  331.03  4878.8  327.06  4879.1  326.56  4882.8  327.06
  4895.9  327.30  4901.9  329.21  4910.9  327.25  4916.9  329.40  4931.9  328.83
  4946.9  327.16  4953.0  328.79  4960.5  329.68  4989.0  328.67  4993.5  327.58
  5036.5  328.23  5046.5  328.87  5056.5  331.15  5096.5  334.72  5196.5  338.62
#Mann=3,-1,0
  4636.0    0.12       0  4878.8    0.07       0  4882.8    0.12       0
Bank Sta=4878.8,4882.8
Exp/Cntr=0.3,0.1

Type RM Length L Ch R = 1,3124,243,243,243
BEGIN DESCRIPTION:
Walnut50 8.0
END DESCRIPTION:
XS GIS Cut Line= 3
      2729626.02      6753561.01      2729476.00      6753511.00
      2729276.03      6753511.00
#Sta/Elev= 30
  4846.6  337.62  4849.3  337.62  4878.2  335.08  4888.8  334.64  4930.9  331.55
  4952.0  329.56  4962.6  327.64  4973.1  327.56  4983.7  327.75  4994.2  326.75
  5000.1  324.68  5000.3  324.18  5003.8  324.18  5004.1  324.68  5007.2  324.68
  5014.7  327.25  5024.7  327.63  5034.7  327.29  5044.7  328.15  5064.7  328.77
  5074.7  329.37  5104.7  330.53  5114.7  331.42  5144.7  333.05  5154.7  333.99
  5174.7  335.46  5184.7  336.48  5194.7  337.19  5202.2  338.04  5204.7  338.04
#Mann=3,-1,0
  4846.6    0.12       0  5000.1    0.07       0  5004.1    0.12       0
Bank Sta=5000.1,5004.1
Exp/Cntr=0.3,0.1

Type RM Length L Ch R = 1,2881,268,268,268
BEGIN DESCRIPTION:
Walnut50 7.0
END DESCRIPTION:
XS GIS Cut Line= 3
      2729676.04      6753311.00      2729526.00      6753311.00
      2729325.99      6753361.00
#Sta/Elev= 30
  4844.0  335.47  4846.5  335.47  4864.0  333.72  4884.0  332.41  4904.0  329.51
  4914.0  327.68  4924.0  325.28  4934.0  325.11  4964.0  325.53  4974.0  325.07
  4984.0  325.73  4989.5  321.67  4989.8  321.17  4993.3  321.17  4993.5  321.67
  4996.6  321.67  5004.3  324.91  5012.1  325.51  5023.7  325.58  5045.6  327.15
  5053.3  327.28  5066.2  326.73  5086.8  327.43  5094.5  328.73  5099.7  328.33
  5117.7  329.65  5128.0  329.73  5159.0  330.75  5197.6  334.78  5200.2  334.78
#Mann=4,-1,0
  4844.0    0.12       0  4989.5    0.07       0  4993.5    0.12       0
  5023.7     0.1       0
Bank Sta=4989.5,4993.5
Exp/Cntr=0.3,0.1

Type RM Length L Ch R = 1,2613,267,267,267
BEGIN DESCRIPTION:
Walnut50 6.0
END DESCRIPTION:
XS GIS Cut Line= 3
      2729826.05      6753111.01      2729576.00      6753061.00
      2729376.00      6753061.00
#Sta/Elev= 30
  4745.4  343.12  4748.0  343.12  4765.4  341.71  4796.4  338.56  4827.0  336.68
  4847.4  336.04  4867.8  333.64  4878.0  332.21  4898.4  330.74  4908.6  330.47
  4918.8  329.46  4929.0  327.73  4939.2  326.70  4949.4  324.24  4959.6  322.13
  4967.8  319.80  4968.1  319.30  4971.6  319.30  4971.8  319.80  4980.0  322.73
  5002.9  322.99  5010.4  323.68  5030.4  323.60  5060.4  324.01  5100.4  325.81
  5140.4  328.99  5170.4  331.60  5180.4  332.10  5190.4  332.99  5200.4  333.41
#Mann=4,-1,0
  4745.4    0.05       0  4765.4    0.12       0  4967.8    0.07       0
  4971.8    0.12       0
Bank Sta=4967.8,4971.8
Exp/Cntr=0.3,0.1

Type RM Length L Ch R = 1,2346,253,253,253
BEGIN DESCRIPTION:
Walnut50 5.0
END DESCRIPTION:
XS GIS Cut Line= 3
      2729933.80      6752744.34      2729534.37      6752798.11
      2729376.01      6752960.99
#Sta/Elev= 30
  4578.6  342.94  4586.2  341.91  4591.3  342.19  4626.3  340.10  4736.9  333.03
  4758.0  332.69  4788.3  330.76  4808.5  328.42  4814.7  326.51  4819.7  326.20
  4828.6  324.33  4858.9  322.05  4887.5  320.75  4949.7  320.62  4959.8  320.01
  4963.3  316.92  4963.6  316.42  4967.3  316.92  4970.4  319.08  4978.3  320.68
  4989.5  320.70  4996.7  318.01  5003.7  320.89  5010.9  317.80  5017.8  321.67
  5025.0  321.02  5032.0  322.40  5039.2  322.03  5067.7  324.29  5208.8  330.88
#Mann=5,-1,0
  4578.6    0.05       0  4626.3     0.1       0  4963.3    0.07       0
  4967.3     0.1       0  5067.7    0.12       0
Bank Sta=4963.3,4967.3
Exp/Cntr=0.3,0.1

Type RM Length L Ch R = 1,2093,285,285,285
BEGIN DESCRIPTION:
Walnut50 4.0
END DESCRIPTION:
XS GIS Cut Line= 3
      2729790.39      6752554.88      2729316.74      6752583.04
      2729129.14      6752585.58
#Sta/Elev= 30
  4684.3  331.85  4703.4  331.45  4763.9  327.89  4849.0  322.83  4939.1  319.73
  4959.2  319.94  4969.2  319.17  4989.2  319.06  4997.2  315.75  4997.5  315.25
  5001.0  315.25  5001.2  315.75  5009.3  318.30  5012.7  318.52  5037.2  319.48
  5069.4  318.03  5079.4  318.72  5089.4  318.72  5119.5  324.24  5149.5  328.65
  5161.7  328.69  5169.5  330.21  5179.5  330.98  5199.5  328.35  5209.5  328.77
  5229.5  334.25  5239.5  337.54  5249.5  338.86  5339.5  344.05  5346.4  344.07
#Mann=5,-1,0
  4684.3    0.05       0  4763.9     0.1       0  4997.2    0.07       0
  5001.2     0.1       0  5012.7    0.12       0
Bank Sta=4997.2,5001.2
Exp/Cntr=0.3,0.1

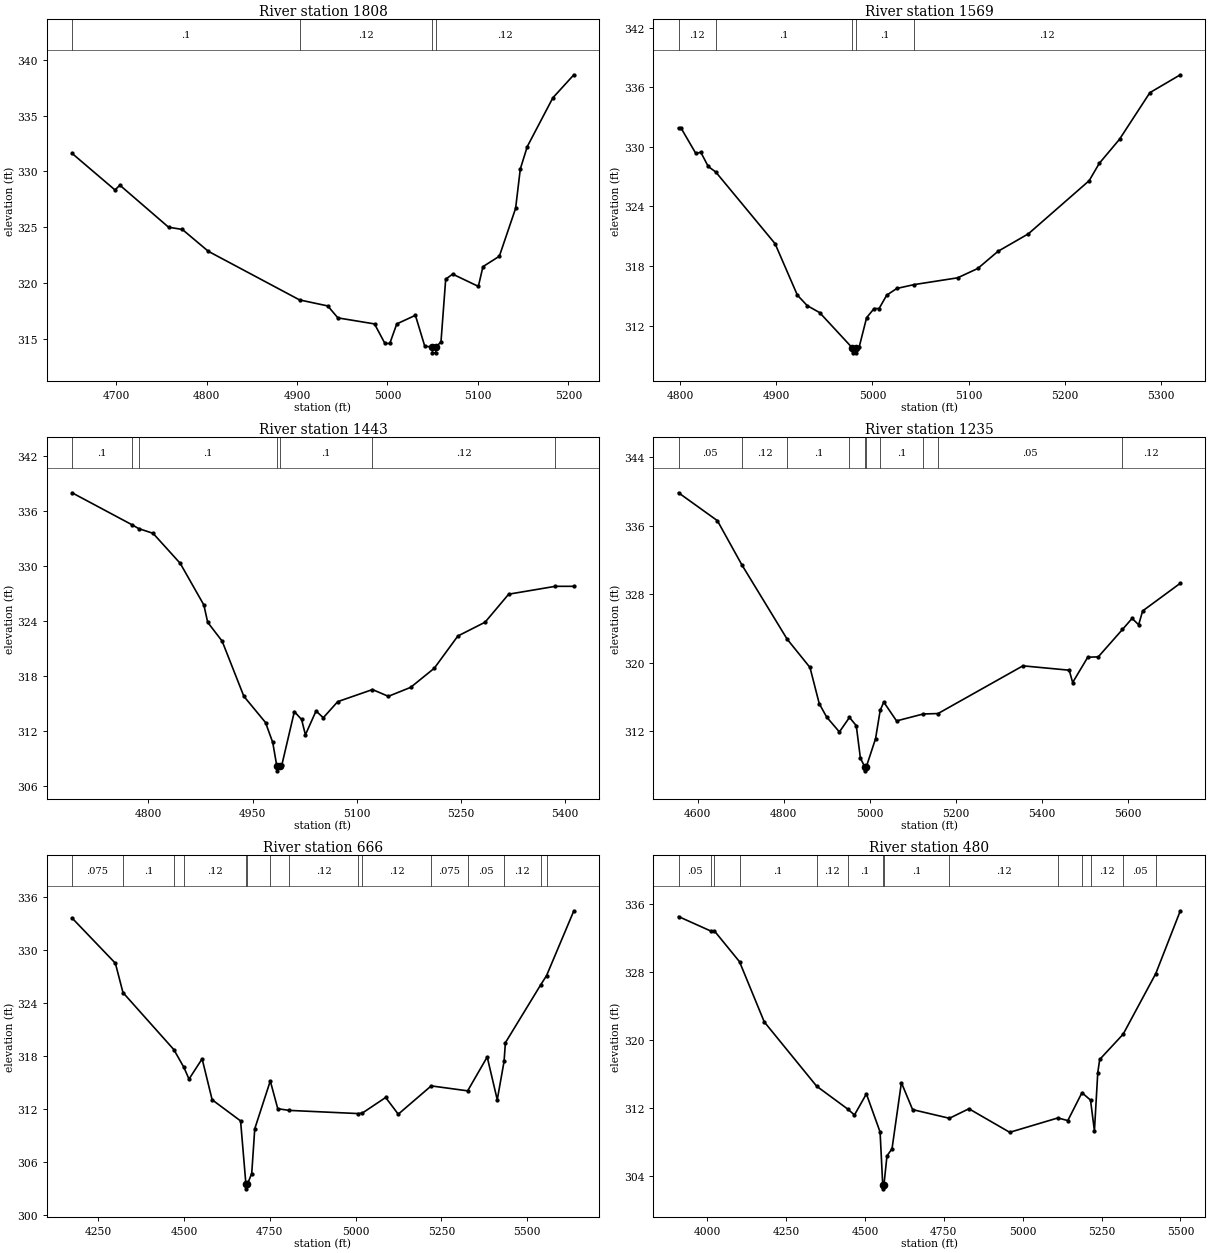
Type RM Length L Ch R = 1,1808,239,239,239
BEGIN DESCRIPTION:
Walnut50 3.0
END DESCRIPTION:
XS GIS Cut Line= 3
      2729792.98      6752506.24      2729476.00      6752361.00
      2729276.03      6752311.01
#Sta/Elev= 30
  4651.3  331.62  4698.7  328.35  4704.2  328.77  4758.0  325.01  4773.2  324.81
  4802.0  322.85  4902.8  318.50  4934.0  317.96  4945.2  316.89  4985.7  316.35
  4997.2  314.60  5002.6  314.60  5010.3  316.35  5030.9  317.12  5041.2  314.37
  5049.5  314.26  5049.8  313.76  5053.3  313.76  5053.5  314.26  5059.2  314.75
  5064.4  320.36  5072.1  320.81  5100.5  319.71  5105.6  321.48  5123.7  322.41
  5141.7  326.70  5146.9  330.23  5154.6  332.23  5182.9  336.60  5206.1  338.66
#Mann=4,-1,0
  4651.3     0.1       0  4902.8    0.12       0  5049.5    0.07       0
  5053.5    0.12       0
Bank Sta=5049.5,5053.5
Exp/Cntr=0.3,0.1

Type RM Length L Ch R = 1,1569,126,126,126
BEGIN DESCRIPTION:
Walnut50 2.0
END DESCRIPTION:
XS GIS Cut Line= 3
      2729775.98      6752210.99      2729576.00      6752161.00
      2729275.96      6752261.01
#Sta/Elev= 30
  4798.1  331.89  4800.7  331.89  4816.1  329.33  4821.3  329.45  4829.0  328.02
  4836.8  327.47  4898.6  320.25  4921.8  315.07  4932.1  314.01  4945.0  313.31
  4979.0  309.76  4979.3  309.26  4982.8  309.26  4983.0  309.76  4986.2  309.86
  4993.9  312.80  5001.7  313.72  5006.9  313.72  5014.8  315.06  5025.3  315.74
  5043.4  316.13  5088.6  316.81  5109.6  317.75  5130.7  319.48  5162.3  321.24
  5225.6  326.59  5236.1  328.33  5257.2  330.76  5288.8  335.45  5320.5  337.25
#Mann=5,-1,0
  4798.1    0.12       0  4836.8     0.1       0  4979.0    0.07       0
  4983.0     0.1       0  5043.4    0.12       0
Bank Sta=4979,4983
Exp/Cntr=0.3,0.1

Type RM Length L Ch R = 1,1443,208,208,208
BEGIN DESCRIPTION:
Walnut50 1.6
END DESCRIPTION:
XS GIS Cut Line= 2
      2729933.75      6752137.54      2729239.15      6751940.90
#Sta/Elev= 30
  4690.4  338.01  4776.5  334.52  4786.2  334.10  4806.9  333.58  4846.0  330.30
  4880.0  325.75  4885.5  323.86  4906.3  321.80  4937.5  315.78  4968.7  312.91
  4979.1  310.73  4985.0  308.13  4985.3  307.63  4989.0  308.13  4992.2  308.27
  5010.2  314.10  5020.6  313.24  5026.1  311.57  5041.4  314.17  5051.8  313.43
  5072.6  315.19  5122.6  316.51  5145.4  315.77  5177.5  316.75  5211.5  318.84
  5245.4  322.36  5284.6  323.87  5318.5  326.93  5385.6  327.79  5412.3  327.79
#Mann=7,-1,0
  4690.4     0.1       0  4776.5    0.12       0  4786.2     0.1       0
  4985.0    0.07       0  4989.0     0.1       0  5122.6    0.12       0
  5385.6    0.05       0
Bank Sta=4985,4989
Exp/Cntr=0.3,0.1

Type RM Length L Ch R = 1,1235,569,569,569
BEGIN DESCRIPTION:
Walnut50 1.3
END DESCRIPTION:
XS GIS Cut Line= 2
      2730089.96      6752022.33      2729005.92      6751595.36
#Sta/Elev= 30
  4555.7  339.87  4645.9  336.61  4702.5  331.46  4807.9  322.75  4860.9  319.44
  4882.4  315.21  4899.5  313.65  4929.2  311.90  4952.6  313.60  4968.4  312.63
  4978.0  308.82  4987.9  307.85  4988.1  307.35  4991.9  307.85  5013.2  311.12
  5023.9  314.42  5032.2  315.39  5061.9  313.19  5124.0  314.00  5158.2  314.05
  5355.3  319.63  5462.8  319.12  5470.8  317.68  5505.9  320.64  5530.3  320.68
  5586.5  323.89  5608.9  325.18  5624.0  324.43  5633.3  326.05  5720.8  329.29
#Mann=10,-1,0
  4555.7    0.05       0  4702.5    0.12       0  4807.9     0.1       0
  4952.6    0.05       0  4987.9    0.05       0  4991.9    0.05       0
  5023.9     0.1       0  5124.0    0.12       0  5158.2    0.05       0
  5586.5    0.12       0
Bank Sta=4987.9,4991.9
Exp/Cntr=0.3,0.1

Type RM Length L Ch R = 1,666,186,186,186
BEGIN DESCRIPTION:
Walnut50 1.0
END DESCRIPTION:
XS GIS Cut Line= 3
      2730202.60      6751899.43      2729908.18      6751694.61
      2728890.13      6751267.44
#Sta/Elev= 30
  4173.6  333.59  4299.8  328.48  4322.0  325.16  4470.3  318.71  4499.6  316.70
  4514.5  315.38  4552.7  317.67  4581.9  313.04  4664.8  310.65  4680.4  303.47
  4680.6  302.97  4684.4  303.47  4697.3  304.70  4706.1  309.76  4751.4  315.17
  4773.2  312.03  4806.4  311.84  5008.0  311.48  5019.8  311.54  5087.7  313.30
  5124.4  311.41  5220.5  314.61  5326.7  314.05  5383.7  317.88  5413.0  313.04
  5432.9  317.39  5436.7  319.49  5539.2  326.01  5556.7  327.08  5636.3  334.41
#Mann=15,-1,0
  4173.6   0.075       0  4322.0     0.1       0  4470.3   0.075       0
  4499.6    0.12       0  4680.4    0.07       0  4684.4    0.12       0
  4751.4     0.1       0  4806.4    0.12       0  5008.0   0.075       0
  5019.8    0.12       0  5220.5   0.075       0  5326.7    0.05       0
  5432.9    0.12       0  5539.2    0.05       0  5556.7    0.12       0
Bank Sta=4680.4,4684.4
Exp/Cntr=0.3,0.1

Type RM Length L Ch R = 1,480,0,0,0
BEGIN DESCRIPTION:
Walnut50 0.8
END DESCRIPTION:
XS GIS Cut Line= 3
      2730343.45      6751873.84      2729485.72      6751397.61
      2728907.68      6751205.78
#Sta/Elev= 30
  3909.4  334.50  4012.1  332.79  4023.3  332.80  4102.6  329.19  4181.0  322.11
  4347.2  314.54  4445.0  311.87  4466.9  311.16  4504.7  313.64  4548.1  309.15
  4556.4  302.97  4556.7  302.47  4560.4  302.97  4569.9  306.35  4585.9  307.18
  4615.6  314.96  4651.1  311.79  4767.8  310.77  4829.6  311.89  4958.9  309.12
  5111.5  310.81  5143.0  310.50  5187.8  313.78  5214.9  312.91  5227.3  309.29
  5237.9  316.14  5244.0  317.69  5318.3  320.66  5421.8  327.80  5499.5  335.18
#Mann=14,-1,0
  3909.4    0.05       0  4012.1   0.075       0  4023.3    0.05       0
  4102.6     0.1       0  4347.2    0.12       0  4445.0     0.1       0
  4556.4    0.07       0  4560.4     0.1       0  4767.8    0.12       0
  5111.5   0.075       0  5187.8     0.1       0  5214.9    0.12       0
  5318.3    0.05       0  5421.8    0.12       0
Bank Sta=4556.4,4560.4
Exp/Cntr=0.3,0.1

Chan Stop Cuts=-1