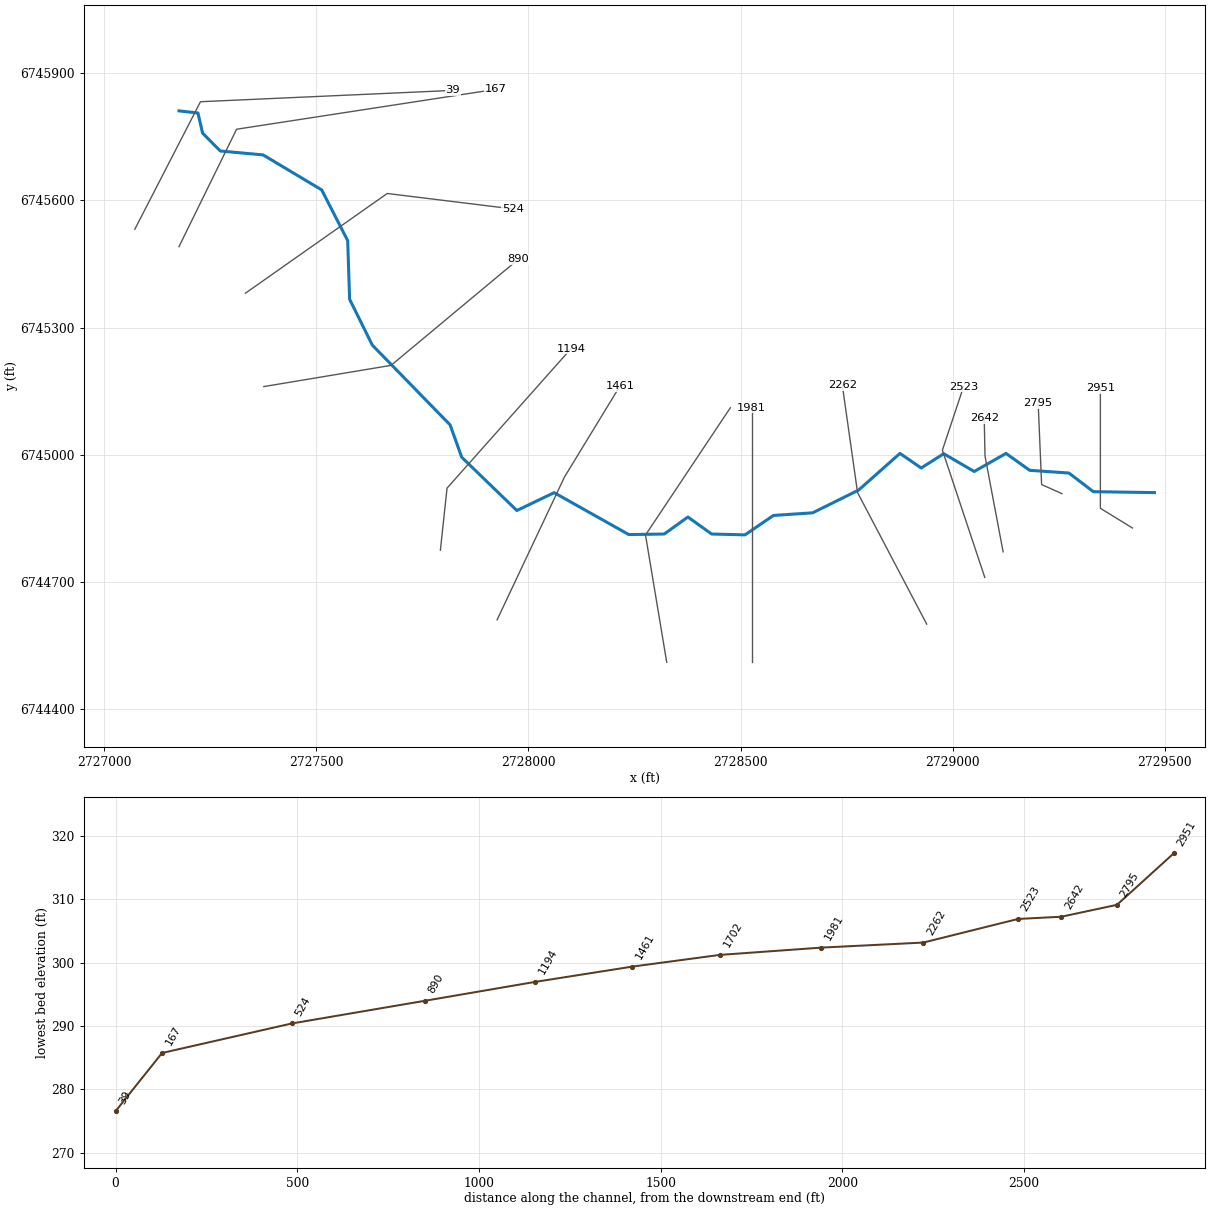
--- Walnut52.prj (project) ---

Proj Title=Walnut52 Base Level Engineering
Current Plan=p01
Default Exp/Contr=0.3,0.1
English Units
Geom File=g01
Flow File=f01
Plan File=p01
Y Axis Title=Elevation
X Axis Title(PF)=Main Channel Distance
X Axis Title(XS)=Station
BEGIN DESCRIPTION:
Walnut52
END DESCRIPTION:
DSS Export Rating Curves= 0
DSS Export Rating Curve Sorted= 0
DSS Export Volume Flow Curves= 0
DXF OffsetX= 0
DXF OffsetY= 0
DXF ScaleX= 1
DXF ScaleY= 10

--- Walnut52.p01 (plan) ---

Plan Title=Multiple Run
Program Version=4.10
Short Identifier=Multiple
Geom File=g01
Flow File=f01
Subcritical Flow
K Sum by GR= 0
Std Step Tol= 0.01
Critical Tol= 0.01
Num of Std Step Trials= 20
Max Error Tol= 0.3
Flow Tol Ratio= 0.001
Split Flow NTrial= 30
Split Flow Tol= 0.02
Split Flow Ratio= 0.02
Log Output Level= 0
Friction Slope Method= 1
Unsteady Friction Slope Method= 2
Unsteady Bridges Friction Slope Method= 1
Parabolic Critical Depth
Global Vel Dist= 1 , 1 , 1
Global Log Level= 0
CheckData=True
Encroach Param=-1 ,0,0, 0
BEGIN DESCRIPTION:
Multiple Run
END DESCRIPTION:
Computation Interval=1HOUR
Output Interval=1HOUR
Run HTab= 0
Run UNet= 0
Run PostProcess= 0
Run WQNet= 0
UNET Theta= 1
UNET Theta Warmup= 1
UNET ZTol= 0.02
UNET ZSATol= 0.05
UNET MxIter= 20
UNET MaxInSteps= 0
UNET DtIC= 0
UNET DtMin= 0
UNET MaxCRTS= 20
UNET WFStab= 2
UNET SFStab= 1
UNET WFX= 1
UNET SFX= 1
UNET DSS MLevel= 4
UNET DZMax Abort= 100
UNET Convert EG Bridges= 0
UNET Use Existing IB Tables=-1
UNET Froude Reduction=False
UNET Froude Limit= 1
UNET Froude Power= 10
UNET Time Slicing=0,0, 5
UNET Junction Losses=0
Instantaneous Interval=1HOUR
Write IC File= 0
Write IC File at Sim End=0
Echo Input=False
Echo Parameters=False
Echo Output=False
Write Detailed= 0
WQ AD Non Conservative
WQ ULTIMATE=-1
WQ Max Comp Step=1HOUR
WQ Output Interval=15MIN
WQ Output Selected Increments= 0
WQ Output face flow=0
WQ Output face velocity=0
WQ Output face area=0
WQ Output face dispersion=0
WQ Output cell volume=0
WQ Output cell surface area=0
WQ Output cell continuity=0
WQ Output cumulative cell continuity=0
WQ Output face conc=0
WQ Output face dconc_dx=0
WQ Output face courant=0
WQ Output face peclet=0
WQ Output face adv mass=0
WQ Output face disp mass=0
WQ Output cell mass=0
WQ Output cell source sink temp=0
WQ Output cell source sink nsm=0
WQ Output MaxMinRange=-1
WQ Daily Max Min Mean=-1
WQ Daily Range=0
WQ Daily Time=0
WQ Create Restart=0
WQ Fixed Restart=0
WQ System Summary=0
WQ Use Fixed Temperature=0
Sorting and Armoring Iterations= 10
XS Update Threshold= 0.02
Hydraulics Update Threshold= 0.02
Energy Slope Method= 1
Volume Change Method= 0
XS Weighting Method= 0
Number of US Weighted Cross Sections= 1
Number of DS Weighted Cross Sections= 1
Upstream XS Weight=0.25
Main XS Weight=0.5
Downstream XS Weight=0.25
Number of DS XS's Weighted with US Boundary= 1
Upstream Boundary Weight= 1
Weight of XSs Associated with US Boundary= 0
Number of US XS's Weighted with DS Boundary= 1
Downstream Boundary Weight= 0.5
Weight of XSs Associated with DS Boundary= 0.5
Sediment Output Level= 4
Mass or Volume Output= 0
Output Increment Type= 1
Profile and TS Output Increment= 10
XS Output Flag= 0
XS Output Increment= 10
Disregard all LS=0
Disregard all Conn=0
Disregard all Breaches=0
Disregard all Pumps=0

--- Walnut52.f01 (steady flow) ---

Flow Title=Multiple
Number of Profiles=7
Profile Names=10-year,25-year,50-year,1pct_min,100-year,1pct_plu,500-year
River Rch & RM= Walnut52,Reach-1,2951
     156     192     219     125     249     496     321
River Rch & RM= Walnut52,Reach-1,890
     223     283     329     191     381     761     512
Boundary for River Rch & Prof#=Walnut52,Reach-1,1
Up Type=0
Dn Type=3
Dn Slope=0.005
Boundary for River Rch & Prof#=Walnut52,Reach-1,2
Up Type=0
Dn Type=3
Dn Slope=0.005
Boundary for River Rch & Prof#=Walnut52,Reach-1,3
Up Type=0
Dn Type=3
Dn Slope=0.005
Boundary for River Rch & Prof#=Walnut52,Reach-1,4
Up Type=0
Dn Type=3
Dn Slope=0.005
Boundary for River Rch & Prof#=Walnut52,Reach-1,5
Up Type=0
Dn Type=3
Dn Slope=0.005
Boundary for River Rch & Prof#=Walnut52,Reach-1,6
Up Type=0
Dn Type=3
Dn Slope=0.005
Boundary for River Rch & Prof#=Walnut52,Reach-1,7
Up Type=0
Dn Type=3
Dn Slope=0.005

--- Walnut52.g01 (geometry) ---

Geom Title=Existing Conditions

River Reach=Walnut52,Reach-1
Reach XY= 30
      2729476.00      6744911.00      2729331.92      6744913.22
      2729274.40      6744957.15      2729181.89      6744963.55
      2729125.99      6745003.41      2729051.00      6744960.78
      2728979.23      6745002.69      2728926.00      6744969.04
      2728876.00      6745003.45      2728778.30      6744916.86
      2728670.03      6744863.33      2728577.60      6744857.14
      2728510.72      6744811.39      2728431.89      6744813.36
      2728376.00      6744853.43      2728320.11      6744813.36
      2728236.55      6744812.09      2728060.59      6744910.86
      2727972.59      6744868.82      2727842.65      6744994.32
      2727815.22      6745070.68      2727631.83      6745258.70
      2727578.25      6745366.93      2727573.75      6745505.07
      2727512.53      6745624.57      2727374.41      6745707.17
      2727273.33      6745716.42      2727231.58      6745758.54
      2727220.65      6745806.04      2727176.00      6745811.00

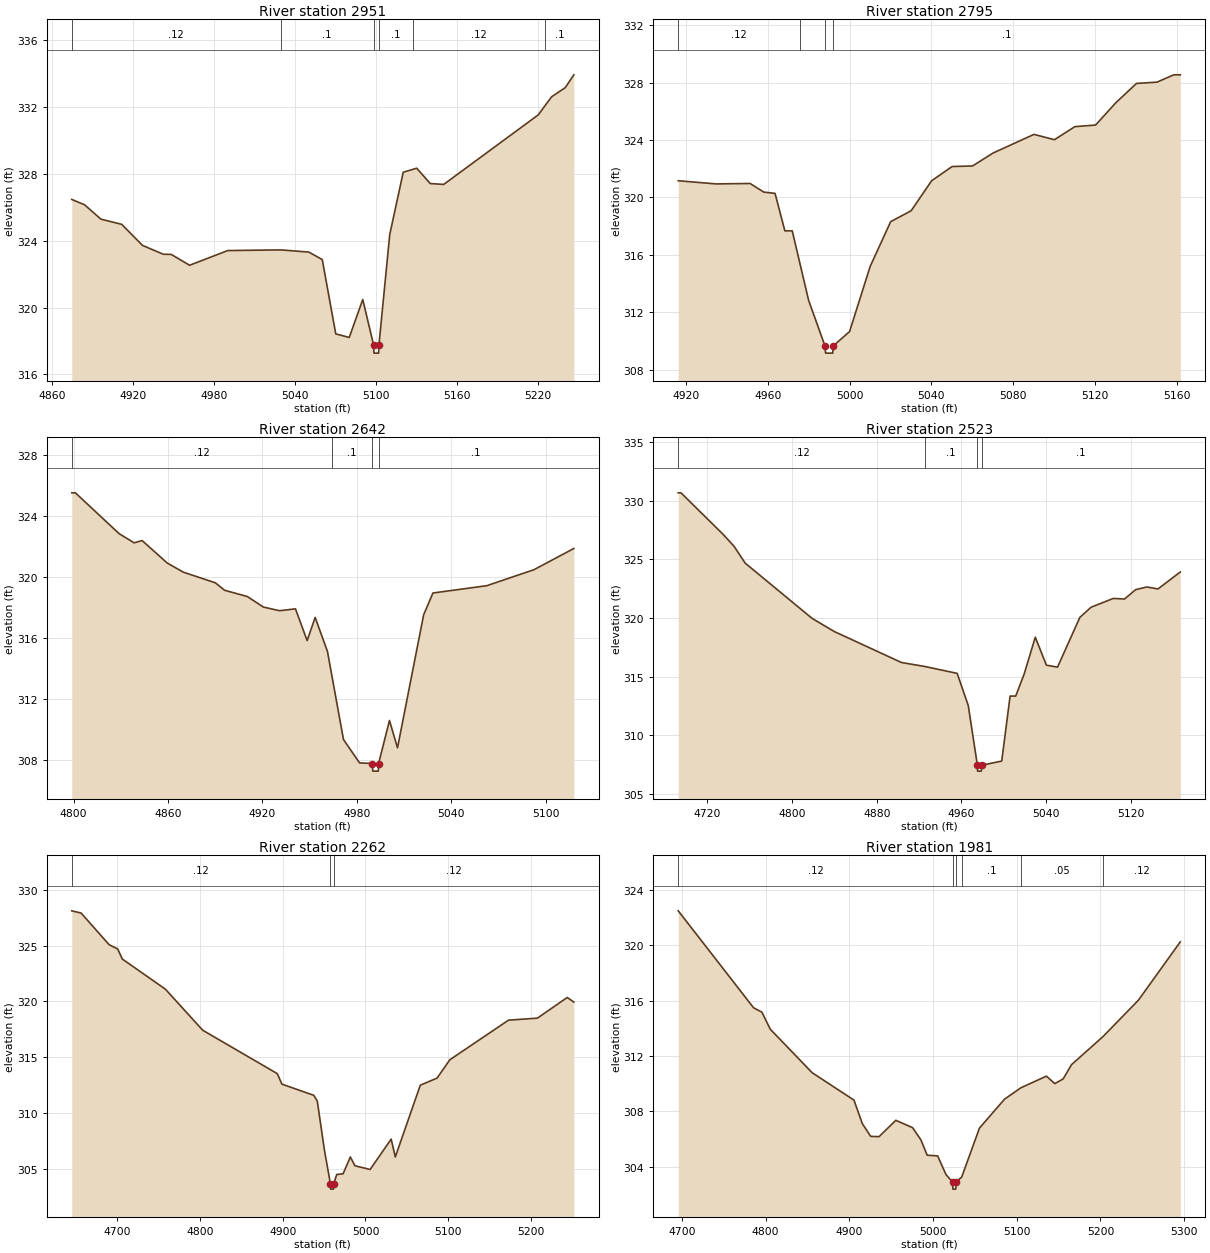
Type RM Length L Ch R = 1,2951,156,156,156
BEGIN DESCRIPTION:
Walnut52 10.0
END DESCRIPTION:
XS GIS Cut Line= 3
      2729424.10      6744827.59      2729348.53      6744874.09
      2729348.53      6745157.36
#Sta/Elev= 30
  4874.5  326.47  4884.0  326.15  4896.1  325.29  4911.5  324.98  4926.9  323.72
  4942.3  323.19  4948.2  323.18  4961.8  322.53  4990.1  323.41  5029.3  323.45
  5050.1  323.32  5060.1  322.87  5070.1  318.42  5080.1  318.21  5090.1  320.48
  5098.1  317.77  5098.4  317.27  5101.9  317.27  5102.1  317.77  5110.1  324.37
  5120.1  328.10  5127.2  328.27  5130.1  328.34  5140.1  327.42  5150.1  327.37
  5220.1  331.53  5225.2  332.09  5230.1  332.62  5240.1  333.16  5246.5  333.93
#Mann=6,-1,0
  4874.5    0.12       0  5029.3     0.1       0  5098.1    0.07       0
  5102.1     0.1       0  5127.2    0.12       0  5225.2     0.1       0
Bank Sta=5098.1,5102.1
Exp/Cntr=0.3,0.1

Type RM Length L Ch R = 1,2795,153,153,153
BEGIN DESCRIPTION:
Walnut52 9.0
END DESCRIPTION:
XS GIS Cut Line= 3
      2729258.07      6744908.53      2729209.99      6744929.90
      2729201.84      6745122.41
#Sta/Elev= 30
  4916.3  321.16  4934.8  320.94  4951.4  320.97  4958.1  320.37  4963.6  320.28
  4968.4  317.67  4972.0  317.67  4975.8  315.37  4980.0  312.83  4988.0  309.65
  4988.3  309.15  4991.8  309.15  4992.0  309.65  5000.0  310.65  5010.1  315.20
  5020.1  318.31  5030.1  319.07  5040.1  321.16  5050.1  322.15  5060.1  322.19
  5070.1  323.09  5090.1  324.39  5100.1  324.02  5110.1  324.93  5120.2  325.04
  5130.2  326.61  5140.2  327.94  5150.2  328.03  5158.4  328.54  5161.6  328.54
#Mann=4,-1,0
  4916.3    0.12       0  4975.8     0.1       0  4988.0    0.07       0
  4992.0     0.1       0
Bank Sta=4988,4992
Exp/Cntr=0.3,0.1

Type RM Length L Ch R = 1,2642,119,119,119
BEGIN DESCRIPTION:
Walnut52 8.5
END DESCRIPTION:
XS GIS Cut Line= 3
      2729119.19      6744771.41      2729076.45      6744997.56
      2729074.68      6745086.29
#Sta/Elev= 30
  4798.9  325.52  4801.2  325.52  4829.0  322.84  4838.5  322.24  4843.6  322.39
  4859.5  320.92  4869.7  320.32  4890.1  319.62  4896.0  319.13  4910.4  318.72
  4920.6  318.03  4930.8  317.79  4941.0  317.91  4948.4  315.83  4953.5  317.35
  4961.3  315.12  4964.3  313.42  4971.5  309.34  4981.7  307.81  4989.8  307.77
  4990.1  307.27  4993.6  307.27  4993.8  307.77  5000.7  310.59  5005.8  308.80
  5022.4  317.52  5028.3  318.95  5062.5  319.43  5092.5  320.48  5117.8  321.87
#Mann=4,-1,0
  4798.9    0.12       0  4964.3     0.1       0  4989.8    0.07       0
  4993.8     0.1       0
Bank Sta=4989.8,4993.8
Exp/Cntr=0.3,0.1

Type RM Length L Ch R = 1,2523,261,261,261
BEGIN DESCRIPTION:
Walnut52 8.0
END DESCRIPTION:
XS GIS Cut Line= 3
      2729075.98      6744711.05      2728976.00      6745011.00
      2729026.00      6745161.01
#Sta/Elev= 30
  4692.5  330.69  4695.1  330.69  4734.6  327.17  4745.2  326.13  4755.7  324.69
  4818.9  319.97  4840.0  318.84  4903.3  316.20  4925.3  315.86  4956.0  315.27
  4966.5  312.52  4975.1  307.42  4975.3  306.92  4978.8  306.92  4979.1  307.42
  4998.1  307.78  5006.0  313.33  5011.3  313.33  5019.2  315.19  5029.8  318.36
  5040.3  315.97  5050.8  315.80  5071.9  320.05  5082.5  320.92  5103.5  321.67
  5114.1  321.62  5124.6  322.42  5135.2  322.65  5145.7  322.48  5166.8  323.93
#Mann=4,-1,0
  4692.5    0.12       0  4925.3     0.1       0  4975.1    0.07       0
  4979.1     0.1       0
Bank Sta=4975.1,4979.1
Exp/Cntr=0.3,0.1

Type RM Length L Ch R = 1,2262,281,281,281
BEGIN DESCRIPTION:
Walnut52 7.0
END DESCRIPTION:
XS GIS Cut Line= 3
      2728938.96      6744601.02      2728776.00      6744911.00
      2728739.97      6745164.55
#Sta/Elev= 30
  4645.3  328.11  4656.6  327.91  4690.5  325.07  4700.7  324.70  4706.4  323.79
  4758.3  321.10  4803.4  317.42  4893.5  313.53  4899.1  312.59  4937.6  311.59
  4941.8  311.07  4950.3  306.73  4957.6  303.69  4957.9  303.19  4961.4  303.19
  4961.6  303.69  4965.3  304.50  4972.9  304.56  4981.7  306.07  4987.3  305.28
  5005.6  304.95  5031.0  307.67  5036.0  306.07  5066.2  312.50  5086.4  313.13
  5101.8  314.77  5172.7  318.32  5207.6  318.50  5243.6  320.35  5251.6  319.94
#Mann=3,-1,0
  4645.3    0.12       0  4957.6    0.07       0  4961.6    0.12       0
Bank Sta=4957.6,4961.6
Exp/Cntr=0.3,0.1

Type RM Length L Ch R = 1,1981,279,279,279
BEGIN DESCRIPTION:
Walnut52 6.0
END DESCRIPTION:
XS GIS Cut Line= 3
      2728526.00      6744511.01      2728526.00      6744811.00
      2728526.00      6745111.01
#Sta/Elev= 30
  4695.5  322.49  4785.5  315.49  4795.5  315.17  4805.5  313.94  4855.5  310.80
  4905.5  308.82  4915.5  307.12  4925.5  306.20  4935.5  306.18  4955.5  307.36
  4975.5  306.83  4985.5  305.95  4993.0  304.84  5005.5  304.79  5015.5  303.44
  5023.5  302.89  5023.7  302.39  5027.2  302.39  5027.5  302.89  5034.3  303.27
  5055.5  306.80  5085.5  308.89  5105.0  309.71  5135.5  310.55  5145.5  310.01
  5155.5  310.35  5165.5  311.38  5203.0  313.40  5245.5  316.04  5295.5  320.25
#Mann=6,-1,0
  4695.5    0.12       0  5023.5    0.07       0  5027.5    0.12       0
  5034.3     0.1       0  5105.0    0.05       0  5203.0    0.12       0
Bank Sta=5023.5,5027.5
Exp/Cntr=0.3,0.1

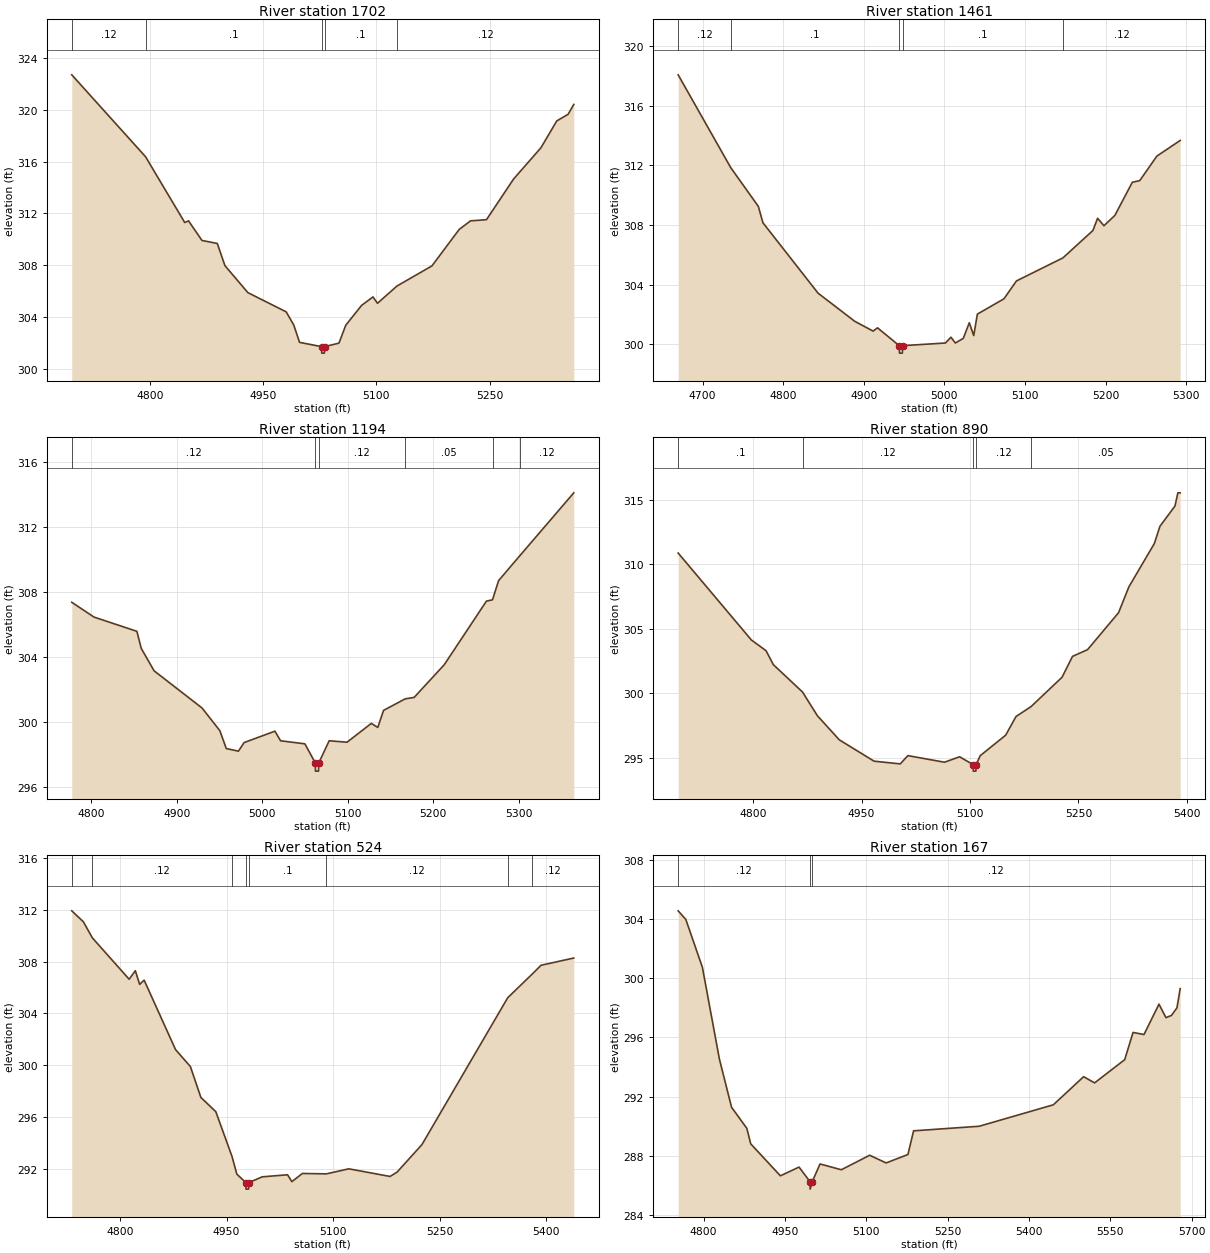
Type RM Length L Ch R = 1,1702,241,241,241
BEGIN DESCRIPTION:
Walnut52 5.0
END DESCRIPTION:
XS GIS Cut Line= 3
      2728326.01      6744510.96      2728276.00      6744811.00
      2728475.98      6745110.97
#Sta/Elev= 30
  4696.6  322.68  4794.3  316.37  4846.2  311.30  4851.2  311.43  4869.0  309.92
  4889.3  309.69  4899.4  307.98  4929.8  305.90  4980.5  304.42  4990.6  303.40
  4998.2  302.07  5027.3  301.74  5027.6  301.24  5031.1  301.24  5031.3  301.74
  5050.4  302.01  5059.4  303.39  5080.4  304.92  5095.4  305.57  5101.4  305.08
  5127.2  306.41  5173.5  307.96  5209.6  310.77  5224.6  311.43  5245.7  311.52
  5281.7  314.66  5317.8  317.06  5338.8  319.13  5353.8  319.64  5361.3  320.40
#Mann=5,-1,0
  4696.6    0.12       0  4794.3     0.1       0  5027.3    0.07       0
  5031.3     0.1       0  5127.2    0.12       0
Bank Sta=5027.3,5031.3
Exp/Cntr=0.3,0.1

Type RM Length L Ch R = 1,1461,267,267,267
BEGIN DESCRIPTION:
Walnut52 4.0
END DESCRIPTION:
XS GIS Cut Line= 3
      2727926.00      6744611.01      2728084.84      6744947.63
      2728215.40      6745161.75
#Sta/Elev= 30
  4669.6  318.09  4734.9  311.85  4769.1  309.25  4774.8  308.15  4843.2  303.42
  4888.7  301.53  4911.5  300.87  4917.0  301.09  4944.0  299.89  4944.3  299.39
  4947.8  299.39  4948.0  299.89  5001.3  300.07  5008.1  300.46  5013.6  300.07
  5023.4  300.38  5030.9  301.43  5036.4  300.57  5040.9  302.01  5073.9  303.04
  5089.4  304.24  5147.1  305.79  5184.3  307.63  5190.1  308.45  5198.0  307.95
  5211.5  308.64  5233.2  310.87  5242.4  310.98  5263.7  312.63  5292.6  313.68
#Mann=5,-1,0
  4669.6    0.12       0  4734.9     0.1       0  4944.0    0.07       0
  4948.0     0.1       0  5147.1    0.12       0
Bank Sta=4944,4948
Exp/Cntr=0.3,0.1

Type RM Length L Ch R = 1,1194,304,304,304
BEGIN DESCRIPTION:
Walnut52 3.0
END DESCRIPTION:
XS GIS Cut Line= 3
      2727792.32      6744775.25      2727807.99      6744921.51
      2728100.52      6745250.60
#Sta/Elev= 30
  4777.1  307.38  4803.0  306.47  4853.3  305.59  4858.4  304.54  4873.4  303.16
  4929.5  300.87  4950.4  299.47  4957.9  298.37  4972.1  298.21  4978.8  298.74
  5014.8  299.44  5021.4  298.85  5049.9  298.66  5062.1  297.48  5062.3  296.98
  5065.8  296.98  5066.1  297.48  5078.3  298.85  5099.2  298.76  5127.6  299.92
  5135.2  299.67  5141.9  300.72  5167.2  301.43  5177.7  301.52  5212.9  303.53
  5262.3  307.45  5269.4  307.53  5276.5  308.71  5301.1  310.23  5364.5  314.12
#Mann=6,-1,0
  4777.1    0.12       0  5062.1    0.07       0  5066.1    0.12       0
  5167.2    0.05       0  5269.4     0.1       0  5301.1    0.12       0
Bank Sta=5062.1,5066.1
Exp/Cntr=0.3,0.1

Type RM Length L Ch R = 1,890,366,366,366
BEGIN DESCRIPTION:
Walnut52 2.0
END DESCRIPTION:
XS GIS Cut Line= 3
      2727376.04      6745161.01      2727676.00      6745211.00
      2727975.99      6745461.00
#Sta/Elev= 30
  4696.2  310.87  4797.5  304.14  4817.8  303.31  4827.9  302.23  4868.3  300.11
  4888.8  298.28  4919.2  296.41  4967.3  294.76  5003.5  294.55  5014.0  295.19
  5064.7  294.68  5085.6  295.10  5104.4  294.49  5104.6  293.99  5108.1  293.99
  5108.4  294.49  5114.2  295.19  5149.3  296.77  5163.7  298.22  5184.4  298.98
  5227.4  301.26  5241.8  302.87  5262.6  303.39  5305.5  306.25  5319.9  308.26
  5355.0  311.60  5362.8  312.94  5383.6  314.51  5387.6  315.53  5390.8  315.53
#Mann=5,-1,0
  4696.2     0.1       0  4868.3    0.12       0  5104.4    0.07       0
  5108.4    0.12       0  5184.4    0.05       0
Bank Sta=5104.4,5108.4
Exp/Cntr=0.3,0.1

Type RM Length L Ch R = 1,524,357,357,357
BEGIN DESCRIPTION:
Walnut52 1.0
END DESCRIPTION:
XS GIS Cut Line= 3
      2727332.62      6745381.16      2727666.96      6745616.24
      2727962.82      6745579.91
#Sta/Elev= 30
  4732.0  311.93  4748.4  311.08  4761.0  309.84  4812.8  306.64  4821.5  307.30
  4827.6  306.24  4833.9  306.57  4878.1  301.20  4899.0  299.89  4913.8  297.50
  4934.8  296.40  4957.6  292.94  4964.4  291.57  4977.2  290.91  4977.4  290.41
  4980.9  290.41  4981.2  290.91  5000.1  291.36  5035.8  291.52  5041.9  290.99
  5056.7  291.62  5090.5  291.59  5122.1  291.98  5180.1  291.39  5190.1  291.73
  5225.1  293.86  5345.8  305.21  5379.9  307.02  5392.7  307.72  5438.8  308.28
#Mann=8,-1,0
  4732.0     0.1       0  4761.0    0.12       0  4957.6     0.1       0
  4977.2    0.07       0  4981.2     0.1       0  5090.5    0.12       0
  5345.8    0.05       0  5379.9    0.12       0
Bank Sta=4977.2,4981.2
Exp/Cntr=0.3,0.1

Type RM Length L Ch R = 1,167,128,128,128
BEGIN DESCRIPTION:
Walnut52 0.5
END DESCRIPTION:
XS GIS Cut Line= 3
      2727175.95      6745490.89      2727311.76      6745767.72
      2727921.93      6745861.59
#Sta/Elev= 30
  4753.2  304.56  4767.3  303.98  4797.9  300.74  4829.3  294.53  4851.7  291.28
  4879.8  289.86  4887.0  288.81  4941.7  286.65  4976.1  287.24  4996.4  286.25
  4996.6  285.75  5000.4  286.25  5014.8  287.45  5054.1  287.06  5106.3  288.04
  5136.7  287.52  5176.9  288.09  5187.3  289.69  5308.4  290.00  5445.0  291.45
  5500.9  293.35  5521.1  292.93  5576.6  294.50  5592.0  296.34  5612.2  296.20
  5639.8  298.25  5652.7  297.34  5662.8  297.49  5672.9  298.00  5678.9  299.30
#Mann=3,-1,0
  4753.2    0.12       0  4996.4    0.07       0  5000.4    0.12       0
Bank Sta=4996.4,5000.4
Exp/Cntr=0.3,0.1

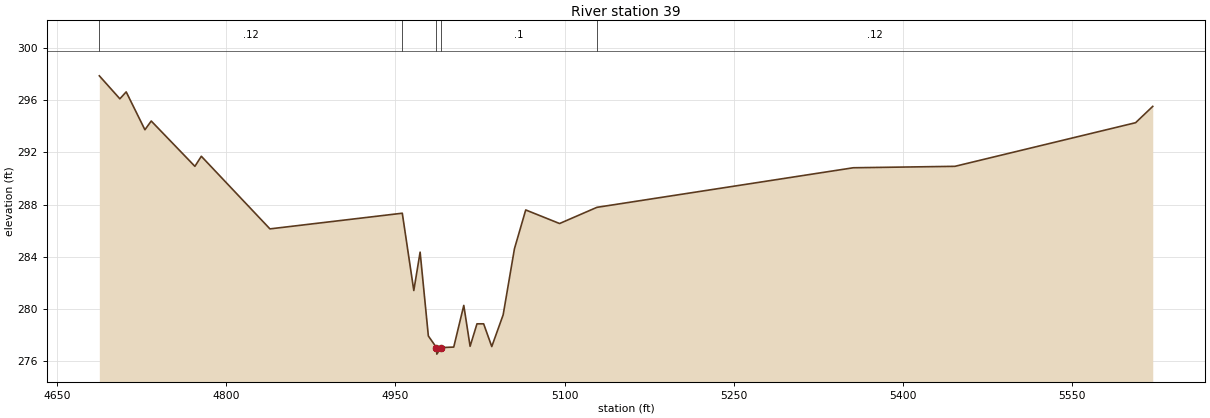
Type RM Length L Ch R = 1,39,0,0,0
BEGIN DESCRIPTION:
Walnut52 0.2
END DESCRIPTION:
XS GIS Cut Line= 3
      2727071.69      6745531.69      2727226.58      6745832.58
      2727821.17      6745859.28
#Sta/Elev= 30
  4687.7  297.86  4705.9  296.10  4711.5  296.63  4728.1  293.73  4733.7  294.40
  4772.4  290.93  4778.1  291.70  4838.9  286.14  4956.2  287.34  4966.4  281.42
  4972.0  284.36  4979.3  277.94  4986.5  277.05  4986.8  276.55  4990.5  277.05
  5001.8  277.09  5010.7  280.28  5016.3  277.15  5022.4  278.87  5028.3  278.87
  5035.5  277.13  5045.6  279.56  5055.6  284.62  5065.6  287.59  5095.6  286.55
  5128.7  287.79  5355.9  290.82  5446.0  290.93  5606.1  294.27  5621.3  295.52
#Mann=5,-1,0
  4687.7    0.12       0  4956.2     0.1       0  4986.5    0.07       0
  4990.5     0.1       0  5128.7    0.12       0
Bank Sta=4986.5,4990.5
Exp/Cntr=0.3,0.1

Chan Stop Cuts=-1