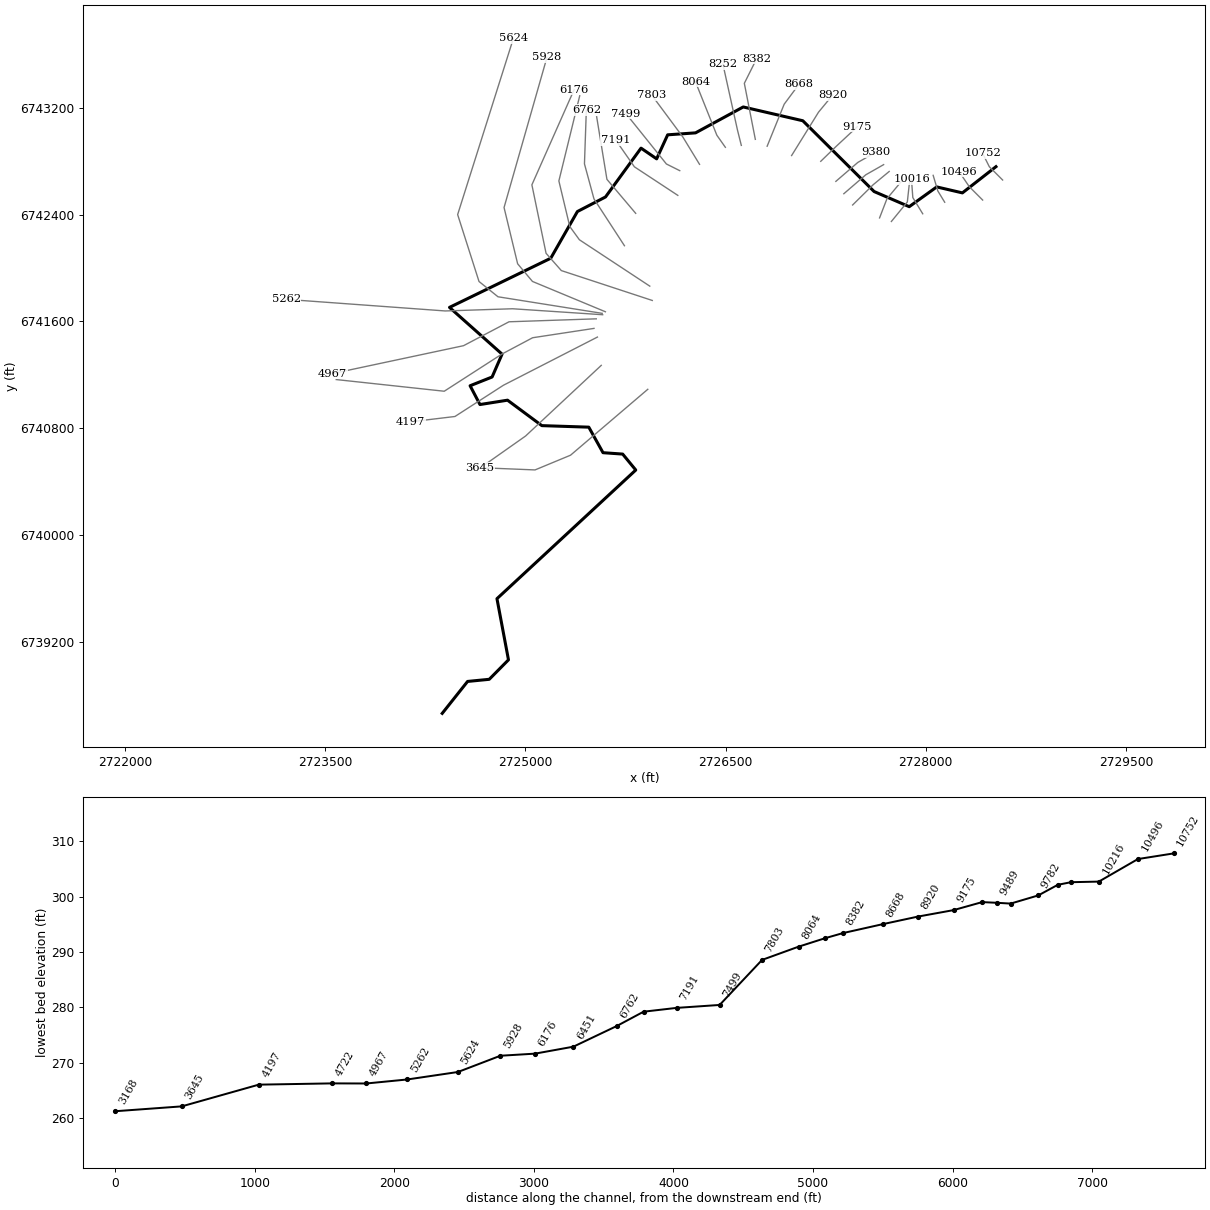
--- Walnut53.prj (project) ---

Proj Title=Walnut53 Base Level Engineering
Current Plan=p01
Default Exp/Contr=0.3,0.1
English Units
Geom File=g01
Flow File=f01
Plan File=p01
Y Axis Title=Elevation
X Axis Title(PF)=Main Channel Distance
X Axis Title(XS)=Station
BEGIN DESCRIPTION:
Walnut53
END DESCRIPTION:
DSS Export Rating Curves= 0
DSS Export Rating Curve Sorted= 0
DSS Export Volume Flow Curves= 0
DXF OffsetX= 0
DXF OffsetY= 0
DXF ScaleX= 1
DXF ScaleY= 10

--- Walnut53.p01 (plan) ---

Plan Title=Multiple Run
Program Version=4.10
Short Identifier=Multiple
Geom File=g01
Flow File=f01
Subcritical Flow
K Sum by GR= 0
Std Step Tol= 0.01
Critical Tol= 0.01
Num of Std Step Trials= 20
Max Error Tol= 0.3
Flow Tol Ratio= 0.001
Split Flow NTrial= 30
Split Flow Tol= 0.02
Split Flow Ratio= 0.02
Log Output Level= 0
Friction Slope Method= 1
Unsteady Friction Slope Method= 2
Unsteady Bridges Friction Slope Method= 1
Parabolic Critical Depth
Global Vel Dist= 1 , 1 , 1
Global Log Level= 0
CheckData=True
Encroach Param=-1 ,0,0, 0
BEGIN DESCRIPTION:
Multiple Run
END DESCRIPTION:
Computation Interval=1HOUR
Output Interval=1HOUR
Run HTab= 0
Run UNet= 0
Run PostProcess= 0
Run WQNet= 0
UNET Theta= 1
UNET Theta Warmup= 1
UNET ZTol= 0.02
UNET ZSATol= 0.05
UNET MxIter= 20
UNET MaxInSteps= 0
UNET DtIC= 0
UNET DtMin= 0
UNET MaxCRTS= 20
UNET WFStab= 2
UNET SFStab= 1
UNET WFX= 1
UNET SFX= 1
UNET DSS MLevel= 4
UNET DZMax Abort= 100
UNET Convert EG Bridges= 0
UNET Use Existing IB Tables=-1
UNET Froude Reduction=False
UNET Froude Limit= 1
UNET Froude Power= 10
UNET Time Slicing=0,0, 5
UNET Junction Losses=0
Instantaneous Interval=1HOUR
Write IC File= 0
Write IC File at Sim End=0
Echo Input=False
Echo Parameters=False
Echo Output=False
Write Detailed= 0
WQ AD Non Conservative
WQ ULTIMATE=-1
WQ Max Comp Step=1HOUR
WQ Output Interval=15MIN
WQ Output Selected Increments= 0
WQ Output face flow=0
WQ Output face velocity=0
WQ Output face area=0
WQ Output face dispersion=0
WQ Output cell volume=0
WQ Output cell surface area=0
WQ Output cell continuity=0
WQ Output cumulative cell continuity=0
WQ Output face conc=0
WQ Output face dconc_dx=0
WQ Output face courant=0
WQ Output face peclet=0
WQ Output face adv mass=0
WQ Output face disp mass=0
WQ Output cell mass=0
WQ Output cell source sink temp=0
WQ Output cell source sink nsm=0
WQ Output MaxMinRange=-1
WQ Daily Max Min Mean=-1
WQ Daily Range=0
WQ Daily Time=0
WQ Create Restart=0
WQ Fixed Restart=0
WQ System Summary=0
WQ Use Fixed Temperature=0
Sorting and Armoring Iterations= 10
XS Update Threshold= 0.02
Hydraulics Update Threshold= 0.02
Energy Slope Method= 1
Volume Change Method= 0
XS Weighting Method= 0
Number of US Weighted Cross Sections= 1
Number of DS Weighted Cross Sections= 1
Upstream XS Weight=0.25
Main XS Weight=0.5
Downstream XS Weight=0.25
Number of DS XS's Weighted with US Boundary= 1
Upstream Boundary Weight= 1
Weight of XSs Associated with US Boundary= 0
Number of US XS's Weighted with DS Boundary= 1
Downstream Boundary Weight= 0.5
Weight of XSs Associated with DS Boundary= 0.5
Sediment Output Level= 4
Mass or Volume Output= 0
Output Increment Type= 1
Profile and TS Output Increment= 10
XS Output Flag= 0
XS Output Increment= 10
Disregard all LS=0
Disregard all Conn=0
Disregard all Breaches=0
Disregard all Pumps=0

--- Walnut53.f01 (steady flow) ---

Flow Title=Multiple
Number of Profiles=7
Profile Names=10-year,25-year,50-year,1pct_min,100-year,1pct_plu,500-year
River Rch & RM= Walnut53,Reach-1,10752
     215     269     310     178     354     707     463
River Rch & RM= Walnut53,Reach-1,9922
     397     522     622     369     737    1470    1033
River Rch & RM= Walnut53,Reach-1,5262
     624     833    1001     597    1190    2375    1682
Boundary for River Rch & Prof#=Walnut53,Reach-1,1
Up Type=0
Dn Type=3
Dn Slope=0.005
Boundary for River Rch & Prof#=Walnut53,Reach-1,2
Up Type=0
Dn Type=3
Dn Slope=0.005
Boundary for River Rch & Prof#=Walnut53,Reach-1,3
Up Type=0
Dn Type=3
Dn Slope=0.005
Boundary for River Rch & Prof#=Walnut53,Reach-1,4
Up Type=0
Dn Type=3
Dn Slope=0.005
Boundary for River Rch & Prof#=Walnut53,Reach-1,5
Up Type=0
Dn Type=3
Dn Slope=0.005
Boundary for River Rch & Prof#=Walnut53,Reach-1,6
Up Type=0
Dn Type=3
Dn Slope=0.005
Boundary for River Rch & Prof#=Walnut53,Reach-1,7
Up Type=0
Dn Type=3
Dn Slope=0.005

--- Walnut53.g01 (geometry) ---

Geom Title=Existing Conditions

River Reach=Walnut53,Reach-1
Reach XY= 30
      2728526.00      6742761.00      2728274.50      6742564.47
      2728082.11      6742609.20      2727876.00      6742461.00
      2727612.67      6742574.65      2727078.42      6743105.46
      2726631.97      6743208.86      2726274.50      6743014.62
      2726065.63      6742999.92      2725982.99      6742819.83
      2725866.00      6742900.04      2725599.84      6742533.86
      2725389.26      6742424.66      2725189.34      6742074.36
      2724430.59      6741705.74      2724824.47      6741355.17
      2724749.90      6741183.72      2724584.97      6741118.06
      2724658.91      6740977.14      2724865.50      6741009.81
      2725122.66      6740818.99      2725474.55      6740807.47
      2725581.08      6740616.04      2725728.46      6740605.54
      2725826.59      6740486.00      2724786.30      6739521.11
      2724872.54      6739062.50      2724728.45      6738916.47
      2724566.20      6738900.52      2724376.00      6738661.00

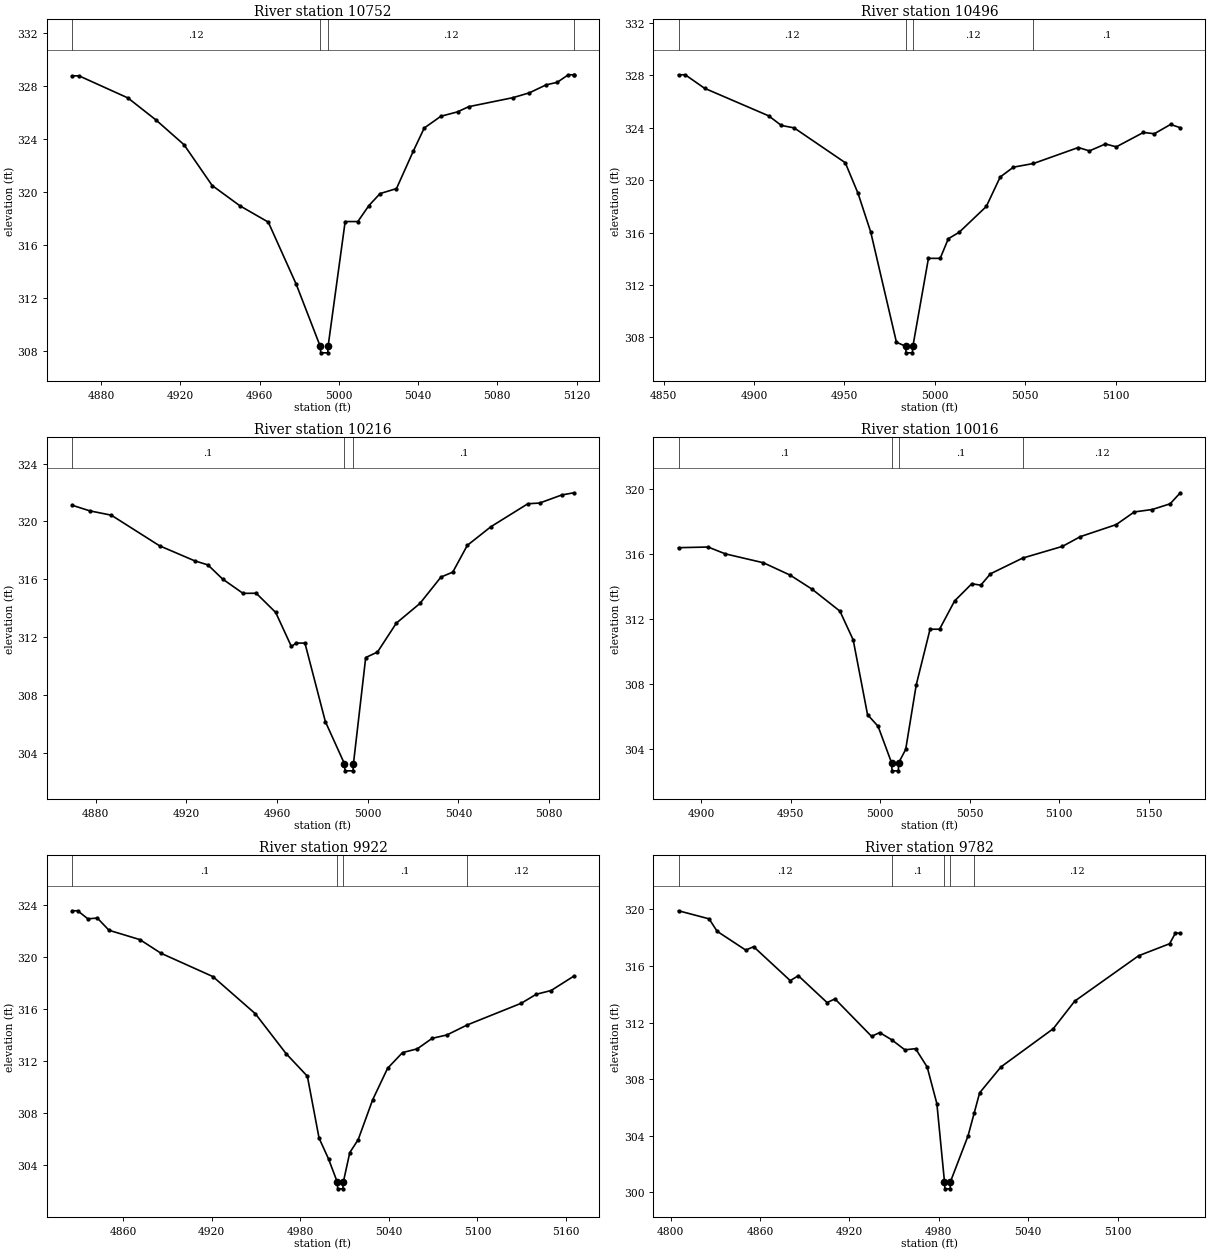
Type RM Length L Ch R = 1,10752,256,256,256
BEGIN DESCRIPTION:
Walnut53 19.0
END DESCRIPTION:
XS GIS Cut Line= 3
      2728575.97      6742661.03      2728476.00      6742761.00
      2728425.99      6742861.01
#Sta/Elev= 30
  4865.4  328.75  4868.9  328.75  4893.6  327.08  4907.8  325.41  4921.9  323.55
  4936.1  320.47  4950.2  318.93  4964.4  317.71  4978.5  313.02  4990.6  308.34
  4990.9  307.84  4994.4  307.84  4994.6  308.34  5003.2  317.75  5009.6  317.75
  5015.2  318.96  5020.8  319.86  5029.1  320.24  5037.5  323.04  5043.1  324.81
  5051.5  325.70  5059.9  326.03  5065.5  326.42  5087.8  327.10  5096.2  327.47
  5104.6  328.07  5110.2  328.26  5115.8  328.83  5118.5  328.83  5118.6  328.83
#Mann=4,-1,0
  4865.4    0.12       0  4990.6    0.07       0  4994.6    0.12       0
  5118.5     0.1       0
Bank Sta=4990.6,4994.6
Exp/Cntr=0.3,0.1

Type RM Length L Ch R = 1,10496,280,280,280
BEGIN DESCRIPTION:
Walnut53 18.0
END DESCRIPTION:
XS GIS Cut Line= 3
      2728426.16      6742510.76      2728326.00      6742611.00
      2728249.99      6742723.53
#Sta/Elev= 30
  4858.3  328.04  4862.0  328.04  4872.7  327.01  4908.1  324.91  4915.2  324.17
  4922.2  323.99  4950.5  321.33  4957.6  318.98  4964.6  316.03  4978.8  307.63
  4983.9  307.32  4984.1  306.82  4987.6  306.82  4987.9  307.32  4996.5  314.03
  5003.0  314.03  5007.5  315.53  5013.5  316.02  5028.5  317.99  5036.2  320.24
  5043.5  320.99  5054.6  321.27  5079.4  322.49  5085.5  322.23  5094.4  322.76
  5100.4  322.54  5115.4  323.64  5121.4  323.54  5130.4  324.25  5135.8  324.00
#Mann=4,-1,0
  4858.3    0.12       0  4983.9    0.07       0  4987.9    0.12       0
  5054.6     0.1       0
Bank Sta=4983.9,4987.9
Exp/Cntr=0.3,0.1

Type RM Length L Ch R = 1,10216,200,200,200
BEGIN DESCRIPTION:
Walnut53 17.0
END DESCRIPTION:
XS GIS Cut Line= 3
      2728141.86      6742494.32      2728090.38      6742578.76
      2728055.39      6742696.05
#Sta/Elev= 30
  4869.6  321.12  4877.4  320.73  4886.9  320.43  4908.2  318.31  4923.7  317.27
  4929.5  316.99  4936.0  316.01  4945.0  315.02  4950.8  315.03  4959.4  313.70
  4966.3  311.35  4968.5  311.58  4972.3  311.58  4981.3  306.15  4989.7  303.24
  4990.0  302.74  4993.5  302.74  4993.7  303.24  4999.1  310.58  5004.3  310.96
  5012.6  312.96  5023.0  314.32  5032.3  316.15  5037.5  316.49  5043.9  318.34
  5054.3  319.63  5070.6  321.22  5075.8  321.27  5085.6  321.83  5090.9  321.98
#Mann=3,-1,0
  4869.6     0.1       0  4989.7    0.07       0  4993.7     0.1       0
Bank Sta=4989.7,4993.7
Exp/Cntr=0.3,0.1

Type RM Length L Ch R = 1,10016,94,94,94
BEGIN DESCRIPTION:
Walnut53 16.5
END DESCRIPTION:
XS GIS Cut Line= 3
      2727977.08      6742407.78      2727902.92      6742529.32
      2727892.68      6742666.66
#Sta/Elev= 30
  4887.5  316.37  4904.0  316.41  4913.6  315.99  4934.9  315.44  4949.8  314.68
  4962.1  313.81  4977.6  312.46  4985.0  310.69  4993.0  306.09  4998.9  305.37
  5006.4  303.13  5006.7  302.63  5010.2  302.63  5010.4  303.13  5014.3  303.95
  5020.2  307.93  5027.9  311.35  5033.2  311.35  5041.6  313.09  5051.2  314.15
  5056.2  314.06  5061.6  314.76  5079.6  315.73  5101.8  316.45  5111.8  317.05
  5131.8  317.79  5141.9  318.57  5151.9  318.72  5161.9  319.07  5167.6  319.75
#Mann=4,-1,0
  4887.5     0.1       0  5006.4    0.07       0  5010.4     0.1       0
  5079.6    0.12       0
Bank Sta=5006.4,5010.4
Exp/Cntr=0.3,0.1

Type RM Length L Ch R = 1,9922,140,140,140
BEGIN DESCRIPTION:
Walnut53 16.3
END DESCRIPTION:
XS GIS Cut Line= 3
      2727742.27      6742350.13      2727861.73      6742496.36
      2727878.16      6742646.35
#Sta/Elev= 30
  4825.6  323.57  4829.4  323.57  4836.3  322.95  4842.7  323.01  4850.6  322.07
  4871.5  321.35  4885.8  320.30  4921.0  318.50  4949.7  315.64  4970.5  312.57
  4984.9  310.83  4992.8  306.07  4999.2  304.47  5005.2  302.66  5005.4  302.16
  5008.9  302.16  5009.2  302.66  5013.6  304.95  5019.3  305.95  5029.1  309.02
  5039.2  311.44  5049.3  312.65  5059.3  312.94  5069.4  313.75  5079.4  314.01
  5093.1  314.78  5129.7  316.45  5139.8  317.14  5149.9  317.43  5165.3  318.54
#Mann=4,-1,0
  4825.6     0.1       0  5005.2    0.07       0  5009.2     0.1       0
  5093.1    0.12       0
Bank Sta=5005.2,5009.2
Exp/Cntr=0.3,0.1

Type RM Length L Ch R = 1,9782,198,198,198
BEGIN DESCRIPTION:
Walnut53 16.0
END DESCRIPTION:
XS GIS Cut Line= 3
      2727653.66      6742376.85      2727709.29      6742521.08
      2727826.01      6742661.01
#Sta/Elev= 30
  4805.3  319.90  4825.8  319.33  4831.2  318.45  4850.4  317.12  4855.7  317.36
  4880.3  314.96  4885.7  315.31  4905.0  313.41  4910.3  313.67  4934.9  311.02
  4940.3  311.29  4948.5  310.77  4957.2  310.07  4964.4  310.15  4972.2  308.85
  4978.7  306.26  4983.8  300.74  4984.1  300.24  4987.6  300.24  4987.8  300.74
  4999.6  303.98  5003.8  305.62  5007.4  307.03  5021.7  308.86  5056.8  311.56
  5071.2  313.51  5114.1  316.72  5134.9  317.57  5138.8  318.32  5142.1  318.32
#Mann=5,-1,0
  4805.3    0.12       0  4948.5     0.1       0  4983.8    0.07       0
  4987.8     0.1       0  5003.8    0.12       0
Bank Sta=4983.8,4987.8
Exp/Cntr=0.3,0.1

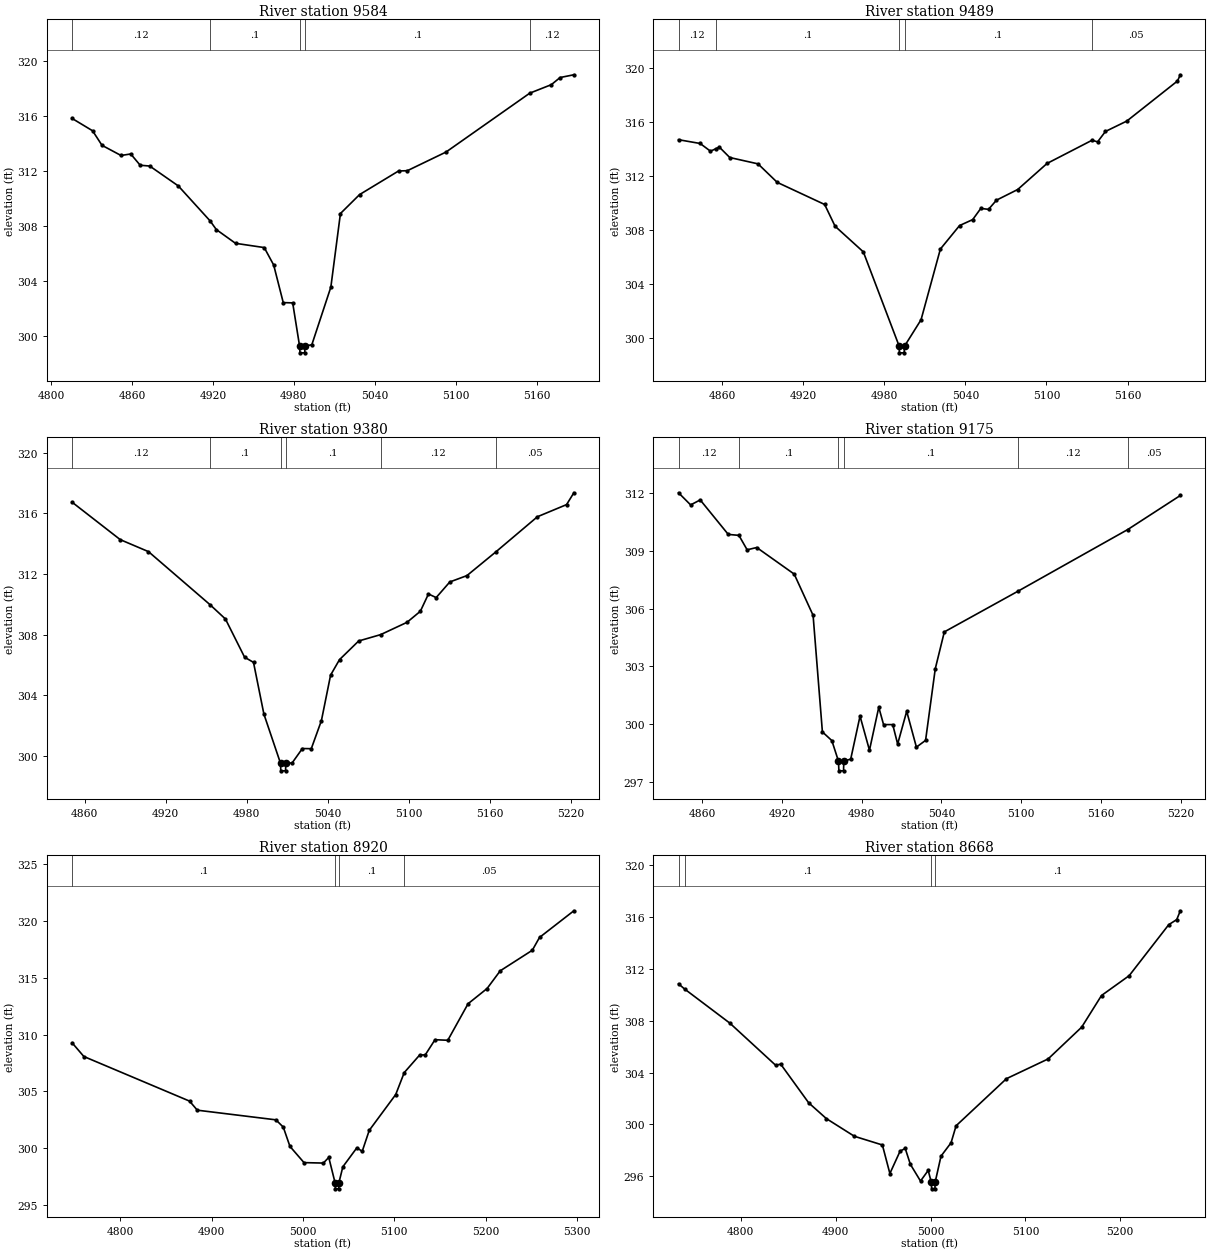
Type RM Length L Ch R = 1,9584,95,95,95
BEGIN DESCRIPTION:
Walnut53 15.6
END DESCRIPTION:
XS GIS Cut Line= 3
      2727451.84      6742473.74      2727606.30      6742626.13
      2727725.80      6742725.03
#Sta/Elev= 30
  4815.6  315.84  4830.8  314.94  4837.8  313.88  4851.9  313.14  4859.1  313.25
  4866.1  312.43  4873.2  312.37  4894.4  310.92  4917.9  308.38  4922.6  307.74
  4936.8  306.74  4958.1  306.43  4965.1  305.16  4972.2  302.42  4979.2  302.40
  4984.3  299.26  4984.6  298.76  4988.1  298.76  4988.3  299.26  4993.4  299.35
  5007.5  303.55  5014.6  308.91  5028.8  310.29  5057.7  312.01  5064.2  312.03
  5092.9  313.39  5155.0  317.68  5171.0  318.30  5177.5  318.82  5187.7  319.02
#Mann=5,-1,0
  4815.6    0.12       0  4917.9     0.1       0  4984.3    0.07       0
  4988.3     0.1       0  5155.0    0.12       0
Bank Sta=4984.3,4988.3
Exp/Cntr=0.3,0.1

Type RM Length L Ch R = 1,9489,109,109,109
BEGIN DESCRIPTION:
Walnut53 15.3
END DESCRIPTION:
XS GIS Cut Line= 3
      2727385.89      6742558.16      2727550.68      6742700.29
      2727684.15      6742776.27
#Sta/Elev= 30
  4827.8  314.69  4843.8  314.41  4851.4  313.84  4855.4  314.02  4858.0  314.14
  4865.7  313.37  4886.6  312.90  4900.8  311.53  4935.9  309.89  4943.6  308.28
  4964.5  306.38  4991.0  299.40  4991.2  298.90  4994.7  298.90  4995.0  299.40
  5007.2  301.35  5021.5  306.59  5035.7  308.33  5045.4  308.77  5051.4  309.60
  5057.1  309.53  5063.0  310.21  5078.7  311.00  5100.4  312.93  5133.7  314.65
  5137.8  314.53  5143.6  315.30  5159.4  316.07  5196.9  319.04  5199.0  319.50
#Mann=5,-1,0
  4827.8    0.12       0  4855.4     0.1       0  4991.0    0.07       0
  4995.0     0.1       0  5133.7    0.05       0
Bank Sta=4991,4995
Exp/Cntr=0.3,0.1

Type RM Length L Ch R = 1,9380,205,205,205
BEGIN DESCRIPTION:
Walnut53 15.0
END DESCRIPTION:
XS GIS Cut Line= 3
      2727326.13      6742650.83      2727490.94      6742792.99
      2727624.82      6742869.19
#Sta/Elev= 30
  4850.7  316.74  4886.4  314.27  4907.3  313.48  4952.8  309.99  4964.3  309.04
  4978.5  306.52  4985.1  306.18  4992.8  302.77  5005.1  299.53  5005.3  299.03
  5008.8  299.03  5009.1  299.53  5013.7  299.55  5021.3  300.50  5027.9  300.49
  5035.4  302.34  5042.2  305.34  5048.8  306.36  5063.0  307.59  5079.3  308.01
  5098.8  308.82  5108.7  309.55  5114.7  310.69  5120.4  310.45  5130.5  311.48
  5143.2  311.90  5164.7  313.47  5195.4  315.78  5217.0  316.58  5222.4  317.36
#Mann=6,-1,0
  4850.7    0.12       0  4952.8     0.1       0  5005.1    0.07       0
  5009.1     0.1       0  5079.3    0.12       0  5164.7    0.05       0
Bank Sta=5005.1,5009.1
Exp/Cntr=0.3,0.1

Type RM Length L Ch R = 1,9175,255,255,255
BEGIN DESCRIPTION:
Walnut53 14.0
END DESCRIPTION:
XS GIS Cut Line= 3
      2727212.83      6742801.20      2727326.00      6742911.00
      2727486.79      6743060.74
#Sta/Elev= 30
  4842.3  312.01  4851.4  311.38  4858.6  311.64  4879.7  309.85  4887.7  309.80
  4893.9  309.05  4901.1  309.17  4929.3  307.79  4943.5  305.65  4950.5  299.60
  4957.6  299.15  4962.6  298.08  4962.9  297.58  4966.4  297.58  4966.6  298.08
  4971.8  298.19  4978.8  300.42  4985.9  298.65  4992.9  300.88  4996.5  299.98
  5003.4  299.98  5007.1  298.97  5013.9  300.67  5021.2  298.81  5028.1  299.16
  5035.4  302.88  5042.2  304.79  5097.3  306.89  5180.1  310.10  5219.7  311.87
#Mann=6,-1,0
  4842.3    0.12       0  4887.7     0.1       0  4962.6    0.07       0
  4966.6     0.1       0  5097.3    0.12       0  5180.1    0.05       0
Bank Sta=4962.6,4966.6
Exp/Cntr=0.3,0.1

Type RM Length L Ch R = 1,8920,252,252,252
BEGIN DESCRIPTION:
Walnut53 13.5
END DESCRIPTION:
XS GIS Cut Line= 3
      2726994.53      6742844.52      2727196.38      6743169.95
      2727302.27      6743298.24
#Sta/Elev= 30
  4747.3  309.28  4760.2  308.07  4875.9  304.14  4884.4  303.34  4970.4  302.49
  4978.5  301.85  4985.8  300.15  5001.2  298.72  5022.4  298.68  5028.3  299.18
  5035.3  296.91  5035.6  296.41  5039.1  296.41  5039.3  296.91  5043.7  298.35
  5059.1  300.03  5064.9  299.71  5072.6  301.56  5101.6  304.72  5110.9  306.65
  5127.9  308.21  5133.9  308.21  5144.6  309.55  5158.6  309.50  5180.8  312.72
  5201.6  314.06  5216.0  315.62  5251.1  317.43  5259.0  318.56  5296.6  320.91
#Mann=4,-1,0
  4747.3     0.1       0  5035.3    0.07       0  5039.3     0.1       0
  5110.9    0.05       0
Bank Sta=5035.3,5039.3
Exp/Cntr=0.3,0.1

Type RM Length L Ch R = 1,8668,286,286,286
BEGIN DESCRIPTION:
Walnut53 13.0
END DESCRIPTION:
XS GIS Cut Line= 3
      2726811.19      6742914.54      2726938.89      6743229.69
      2727051.61      6743381.35
#Sta/Elev= 30
  4734.3  310.84  4740.7  310.44  4788.4  307.81  4836.6  304.57  4842.0  304.65
  4871.5  301.67  4890.2  300.45  4919.7  299.09  4949.2  298.42  4957.1  296.22
  4967.9  297.95  4973.3  298.15  4978.7  296.93  4989.4  295.64  4997.5  296.46
  5000.8  295.54  5001.1  295.04  5004.6  295.04  5004.8  295.54  5011.0  297.56
  5021.6  298.59  5026.9  299.90  5080.0  303.53  5123.9  305.05  5159.3  307.50
  5180.2  309.94  5209.4  311.47  5251.1  315.40  5259.5  315.79  5263.3  316.47
#Mann=4,-1,0
  4734.3    0.05       0  4740.7     0.1       0  5000.8    0.07       0
  5004.8     0.1       0
Bank Sta=5000.8,5004.8
Exp/Cntr=0.3,0.1

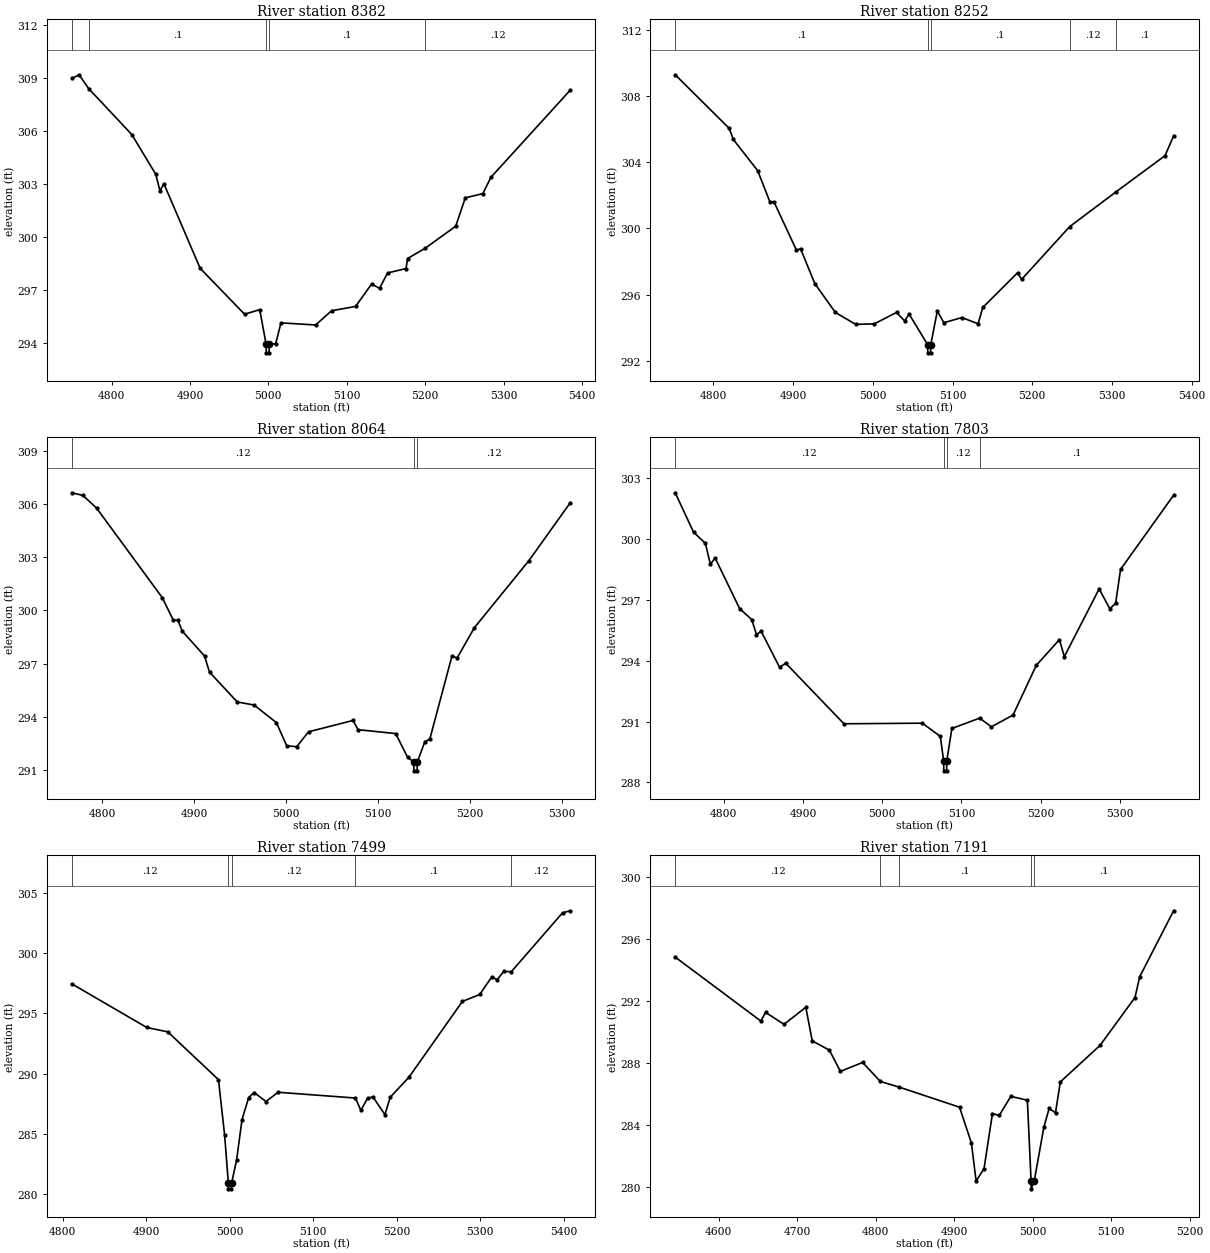
Type RM Length L Ch R = 1,8382,130,130,130
BEGIN DESCRIPTION:
Walnut53 12.0
END DESCRIPTION:
XS GIS Cut Line= 3
      2726722.60      6742966.02      2726640.20      6743386.24
      2726732.90      6743571.64
#Sta/Elev= 30
  4749.5  308.98  4758.7  309.19  4771.0  308.40  4825.9  305.80  4856.5  303.54
  4861.7  302.61  4866.8  303.01  4913.1  298.21  4969.7  295.61  4989.0  295.87
  4997.1  293.92  4997.4  293.42  5000.9  293.42  5001.1  293.92  5009.3  293.93
  5016.1  295.12  5060.3  295.00  5080.7  295.81  5111.2  296.05  5131.6  297.32
  5141.8  297.08  5152.0  297.95  5175.5  298.20  5177.6  298.77  5200.2  299.36
  5238.9  300.60  5251.1  302.21  5273.5  302.45  5283.7  303.37  5385.0  308.32
#Mann=5,-1,0
  4749.5    0.05       0  4771.0     0.1       0  4997.1    0.07       0
  5001.1     0.1       0  5200.2    0.12       0
Bank Sta=4997.1,5001.1
Exp/Cntr=0.3,0.1

Type RM Length L Ch R = 1,8252,188,188,188
BEGIN DESCRIPTION:
Walnut53 11.4
END DESCRIPTION:
XS GIS Cut Line= 3
      2726617.55      6742920.68      2726588.71      6743036.06
      2726479.53      6743530.42
#Sta/Elev= 30
  4752.1  309.28  4819.9  306.04  4825.0  305.37  4855.5  303.49  4871.0  301.59
  4876.1  301.59  4904.2  298.68  4909.3  298.77  4927.3  296.66  4953.0  294.92
  4978.5  294.20  5001.8  294.23  5029.7  294.92  5039.9  294.41  5045.5  294.82
  5068.7  292.98  5068.9  292.48  5072.4  292.48  5072.7  292.98  5080.9  295.01
  5089.1  294.30  5111.6  294.61  5132.1  294.24  5137.9  295.22  5181.6  297.32
  5186.7  296.92  5246.8  300.10  5304.6  302.19  5366.5  304.39  5377.3  305.59
#Mann=5,-1,0
  4752.1     0.1       0  5068.7    0.07       0  5072.7     0.1       0
  5246.8    0.12       0  5304.6     0.1       0
Bank Sta=5068.7,5072.7
Exp/Cntr=0.3,0.1

Type RM Length L Ch R = 1,8064,261,261,261
BEGIN DESCRIPTION:
Walnut53 11.0
END DESCRIPTION:
XS GIS Cut Line= 3
      2726498.05      6742906.31      2726434.21      6742996.92
      2726274.05      6743397.34
#Sta/Elev= 30
  4767.2  306.63  4779.2  306.48  4794.0  305.77  4865.5  300.72  4877.5  299.45
  4882.4  299.45  4887.3  298.83  4911.5  297.43  4916.9  296.52  4947.1  294.84
  4965.3  294.67  4989.6  293.68  5000.9  292.37  5011.7  292.32  5024.6  293.16
  5073.0  293.80  5078.4  293.28  5119.4  293.06  5132.3  291.73  5138.9  291.46
  5139.2  290.96  5142.7  290.96  5142.9  291.46  5151.1  292.60  5156.5  292.75
  5180.7  297.45  5186.1  297.31  5205.0  299.03  5264.2  302.80  5309.3  306.07
#Mann=3,-1,0
  4767.2    0.12       0  5138.9    0.07       0  5142.9    0.12       0
Bank Sta=5138.9,5142.9
Exp/Cntr=0.3,0.1

Type RM Length L Ch R = 1,7803,304,304,304
BEGIN DESCRIPTION:
Walnut53 10.0
END DESCRIPTION:
XS GIS Cut Line= 3
      2726304.43      6742778.58      2726178.79      6742984.56
      2725948.10      6743295.57
#Sta/Elev= 30
  4739.0  302.28  4762.1  300.34  4777.0  299.79  4783.4  298.75  4789.3  299.07
  4820.2  296.57  4835.5  296.03  4841.5  295.29  4847.4  295.45  4870.7  293.67
  4878.3  293.88  4951.8  290.89  5050.6  290.92  5073.3  290.27  5077.5  289.07
  5077.7  288.57  5081.2  288.57  5081.5  289.07  5087.9  290.66  5123.0  291.17
  5137.7  290.74  5165.0  291.32  5194.3  293.77  5223.5  295.04  5229.7  294.20
  5273.6  297.54  5287.1  296.56  5294.4  296.83  5300.6  298.50  5367.5  302.16
#Mann=4,-1,0
  4739.0    0.12       0  5077.5    0.07       0  5081.5    0.12       0
  5123.0     0.1       0
Bank Sta=5077.5,5081.5
Exp/Cntr=0.3,0.1

Type RM Length L Ch R = 1,7499,308,308,308
BEGIN DESCRIPTION:
Walnut53 9.0
END DESCRIPTION:
XS GIS Cut Line= 3
      2726156.11      6742731.20      2726056.13      6742781.19
      2725752.36      6743159.69
#Sta/Elev= 30
  4811.0  297.46  4900.6  293.84  4925.9  293.47  4986.6  289.50  4994.0  284.87
  4998.4  280.92  4998.6  280.42  5002.1  280.42  5002.4  280.92  5008.4  282.85
  5014.8  286.18  5022.8  288.01  5029.2  288.43  5043.6  287.68  5058.0  288.45
  5150.7  287.97  5157.2  286.94  5165.2  287.95  5171.6  288.07  5186.0  286.59
  5192.4  288.04  5214.8  289.70  5278.8  296.00  5299.6  296.58  5314.0  298.04
  5320.4  297.81  5328.4  298.50  5337.4  298.47  5398.8  303.37  5408.1  303.54
#Mann=5,-1,0
  4811.0    0.12       0  4998.4    0.07       0  5002.4    0.12       0
  5150.7     0.1       0  5337.4    0.12       0
Bank Sta=4998.4,5002.4
Exp/Cntr=0.3,0.1

Type RM Length L Ch R = 1,7191,237,237,237
BEGIN DESCRIPTION:
Walnut53 8.0
END DESCRIPTION:
XS GIS Cut Line= 3
      2726141.74      6742545.78      2725816.24      6742760.03
      2725676.02      6742960.96
#Sta/Elev= 30
  4544.6  294.85  4653.7  290.72  4659.7  291.28  4683.2  290.51  4710.9  291.61
  4719.1  289.44  4741.0  288.84  4755.0  287.47  4783.2  288.05  4805.9  286.82
  4830.2  286.45  4906.7  285.16  4921.8  282.85  4927.8  280.39  4937.9  281.20
  4948.6  284.75  4957.3  284.63  4972.0  285.86  4993.1  285.61  4997.8  280.39
  4998.0  279.89  5001.8  280.39  5014.0  283.85  5020.8  285.08  5028.9  284.80
  5035.0  286.79  5085.6  289.15  5130.1  292.24  5136.2  293.59  5179.3  297.84
#Mann=5,-1,0
  4544.6    0.12       0  4805.9    0.05       0  4830.2     0.1       0
  4997.8    0.07       0  5001.8     0.1       0
Bank Sta=4997.8,5001.8
Exp/Cntr=0.3,0.1

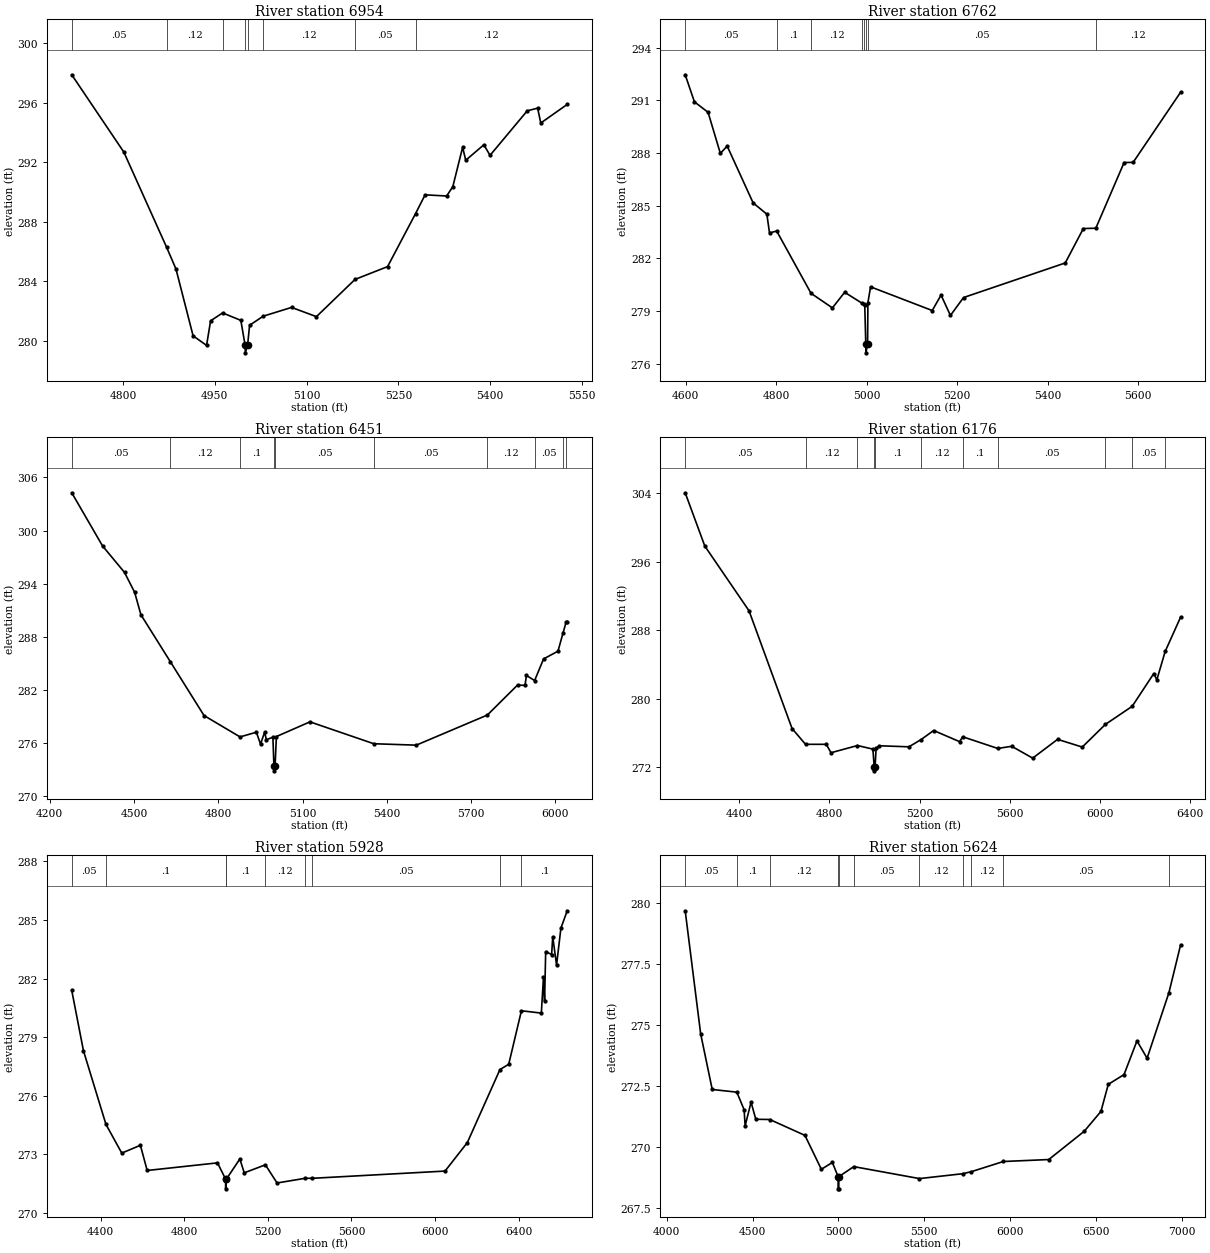
Type RM Length L Ch R = 1,6954,192,192,192
BEGIN DESCRIPTION:
Walnut53 7.0
END DESCRIPTION:
XS GIS Cut Line= 3
      2725826.00      6742411.00      2725610.50      6742665.82
      2725533.46      6743135.42
#Sta/Elev= 30
  4716.2  297.87  4801.3  292.68  4871.3  286.28  4886.5  284.83  4914.5  280.34
  4936.5  279.70  4943.1  281.35  4962.7  281.88  4992.5  281.38  4999.5  279.70
  4999.8  279.20  5003.5  279.70  5006.8  281.05  5029.0  281.66  5075.4  282.25
  5116.0  281.63  5179.1  284.13  5232.3  284.99  5278.0  288.55  5293.6  289.81
  5328.8  289.73  5338.9  290.36  5354.9  293.00  5360.0  292.13  5389.6  293.17
  5399.7  292.46  5460.5  295.45  5477.5  295.63  5482.6  294.63  5525.8  295.88
#Mann=8,-1,0
  4716.2    0.05       0  4871.3    0.12       0  4962.7     0.1       0
  4999.5    0.07       0  5003.5    0.12       0  5029.0    0.12       0
  5179.1    0.05       0  5278.0    0.12       0
Bank Sta=4999.5,5003.5
Exp/Cntr=0.3,0.1

Type RM Length L Ch R = 1,6762,311,311,311
BEGIN DESCRIPTION:
Walnut53 6.0
END DESCRIPTION:
XS GIS Cut Line= 4
      2725741.64      6742168.21      2725513.24      6742519.58
      2725442.00      6742781.97      2725456.09      6743185.96
#Sta/Elev= 30
  4599.0  292.45  4619.4  290.91  4649.6  290.31  4676.7  287.97  4691.8  288.39
  4749.2  285.15  4779.5  284.51  4785.4  283.44  4801.2  283.55  4877.2  280.00
  4924.4  279.17  4951.5  280.06  4989.7  279.44  4993.4  279.39  4995.9  279.36
  4998.2  277.11  4998.5  276.61  5002.2  277.11  5002.9  279.47  5008.8  280.37
  5145.1  279.02  5164.6  279.90  5185.3  278.74  5214.3  279.76  5439.1  281.73
  5479.1  283.69  5506.7  283.71  5569.2  287.45  5589.2  287.46  5694.2  291.46
#Mann=8,-1,0
  4599.0    0.05       0  4801.2     0.1       0  4877.2    0.12       0
  4989.7     0.1       0  4993.4    0.05       0  4998.2    0.04       0
  5002.2    0.05       0  5506.7    0.12       0
Bank Sta=4998.2,5002.2
Exp/Cntr=0.3,0.1

Type RM Length L Ch R = 1,6451,275,275,275
BEGIN DESCRIPTION:
Walnut53 5.0
END DESCRIPTION:
XS GIS Cut Line= 5
      2725931.56      6741865.10      2725404.07      6742212.87
      2725331.95      6742312.31      2725250.28      6742654.03
      2725406.46      6743292.82
#Sta/Elev= 30
  4278.2  304.26  4387.8  298.26  4466.0  295.27  4502.1  293.02  4524.4  290.49
  4629.7  285.16  4749.1  279.11  4877.3  276.70  4935.4  277.23  4950.1  275.89
  4964.8  277.23  4971.0  276.39  4994.2  276.66  4997.9  273.37  4998.1  272.87
  5001.9  273.37  5006.6  276.74  5126.1  278.40  5353.3  275.93  5504.6  275.77
  5757.6  279.17  5864.9  282.55  5891.6  282.52  5896.7  283.64  5925.8  283.06
  5957.6  285.50  6009.0  286.38  6027.2  288.46  6038.1  289.68  6041.8  289.70
#Mann=10,-1,0
  4278.2    0.05       0  4629.7    0.12       0  4877.3     0.1       0
  4997.9    0.07       0  5001.9    0.05       0  5353.3    0.05       0
  5757.6    0.12       0  5925.8    0.05       0  6027.2    0.12       0
  6038.1    0.05       0
Bank Sta=4997.9,5001.9
Exp/Cntr=0.3,0.1

Type RM Length L Ch R = 1,6176,248,248,248
BEGIN DESCRIPTION:
Walnut53 4.0
END DESCRIPTION:
XS GIS Cut Line= 5
      2725950.22      6741757.72      2725268.68      6741981.79
      2725154.29      6742111.39      2725048.02      6742624.80
      2725365.06      6743339.78
#Sta/Elev= 30
  4160.6  304.01  4247.6  297.80  4443.6  290.26  4634.4  276.54  4694.1  274.70
  4786.1  274.70  4807.2  273.72  4924.4  274.56  4992.9  274.14  4998.5  272.11
  4998.7  271.61  5002.5  272.11  5007.1  274.23  5021.3  274.53  5152.6  274.41
  5206.9  275.26  5262.2  276.31  5377.3  275.01  5391.0  275.58  5546.3  274.22
  5608.3  274.47  5701.4  273.09  5811.7  275.28  5921.1  274.38  6023.6  277.02
  6142.5  279.13  6238.3  282.95  6251.7  282.21  6288.7  285.52  6357.3  289.53
#Mann=11,-1,0
  4160.6    0.05       0  4694.1    0.12       0  4924.4     0.1       0
  4998.5    0.07       0  5002.5     0.1       0  5206.9    0.12       0
  5391.0     0.1       0  5546.3    0.05       0  6023.6    0.12       0
  6142.5    0.05       0  6288.7    0.12       0
Bank Sta=4998.5,5002.5
Exp/Cntr=0.3,0.1

Type RM Length L Ch R = 1,5928,304,304,304
BEGIN DESCRIPTION:
Walnut53 3.0
END DESCRIPTION:
XS GIS Cut Line= 5
      2725599.00      6741672.93      2725052.32      6741900.32
      2724941.22      6742032.66      2724839.43      6742454.61
      2725160.74      6743579.92
#Sta/Elev= 30
  4262.4  281.39  4318.4  278.30  4426.0  274.53  4501.6  273.06  4590.6  273.46
  4623.1  272.17  4959.3  272.56  4998.0  271.73  4998.3  271.23  5002.0  271.73
  5066.2  272.76  5087.3  272.05  5188.3  272.46  5244.1  271.53  5378.6  271.77
  5413.6  271.77  6047.5  272.14  6154.1  273.60  6310.1  277.34  6351.9  277.61
  6412.7  280.35  6507.9  280.23  6518.2  282.07  6523.4  280.85  6528.7  283.38
  6557.2  283.23  6562.4  284.14  6580.7  282.69  6601.5  284.58  6631.6  285.47
#Mann=9,-1,0
  4262.4    0.05       0  4426.0     0.1       0  4998.0    0.07       0
  5002.0     0.1       0  5188.3    0.12       0  5378.6     0.1       0
  5413.6    0.05       0  6310.1    0.12       0  6412.7     0.1       0
Bank Sta=4998,5002
Exp/Cntr=0.3,0.1

Type RM Length L Ch R = 1,5624,362,362,362
BEGIN DESCRIPTION:
Walnut53 2.5
END DESCRIPTION:
XS GIS Cut Line= 5
      2725575.02      6741660.98      2724794.08      6741785.30
      2724651.74      6741900.02      2724491.63      6742401.76
      2724909.52      6743723.52
#Sta/Elev= 30
  4107.0  279.68  4197.1  274.64  4264.5  272.36  4407.9  272.25  4450.3  271.53
  4456.2  270.87  4490.8  271.84  4518.3  271.14  4599.8  271.13  4804.7  270.48
  4900.3  269.09  4964.3  269.37  4998.0  268.79  4998.3  268.29  5001.8  268.29
  5002.0  268.79  5089.3  269.20  5471.6  268.71  5724.7  268.91  5772.5  268.99
  5961.0  269.41  6225.2  269.49  6432.1  270.65  6529.1  271.46  6571.9  272.57
  6663.6  272.97  6739.1  274.35  6798.1  273.64  6925.0  276.32  6993.5  278.29
#Mann=11,-1,0
  4107.0    0.05       0  4407.9     0.1       0  4599.8    0.12       0
  4998.0    0.07       0  5002.0    0.12       0  5089.3    0.05       0
  5471.6    0.12       0  5724.7    0.05       0  5772.5    0.12       0
  5961.0    0.05       0  6925.0    0.12       0
Bank Sta=4998,5002
Exp/Cntr=0.3,0.1

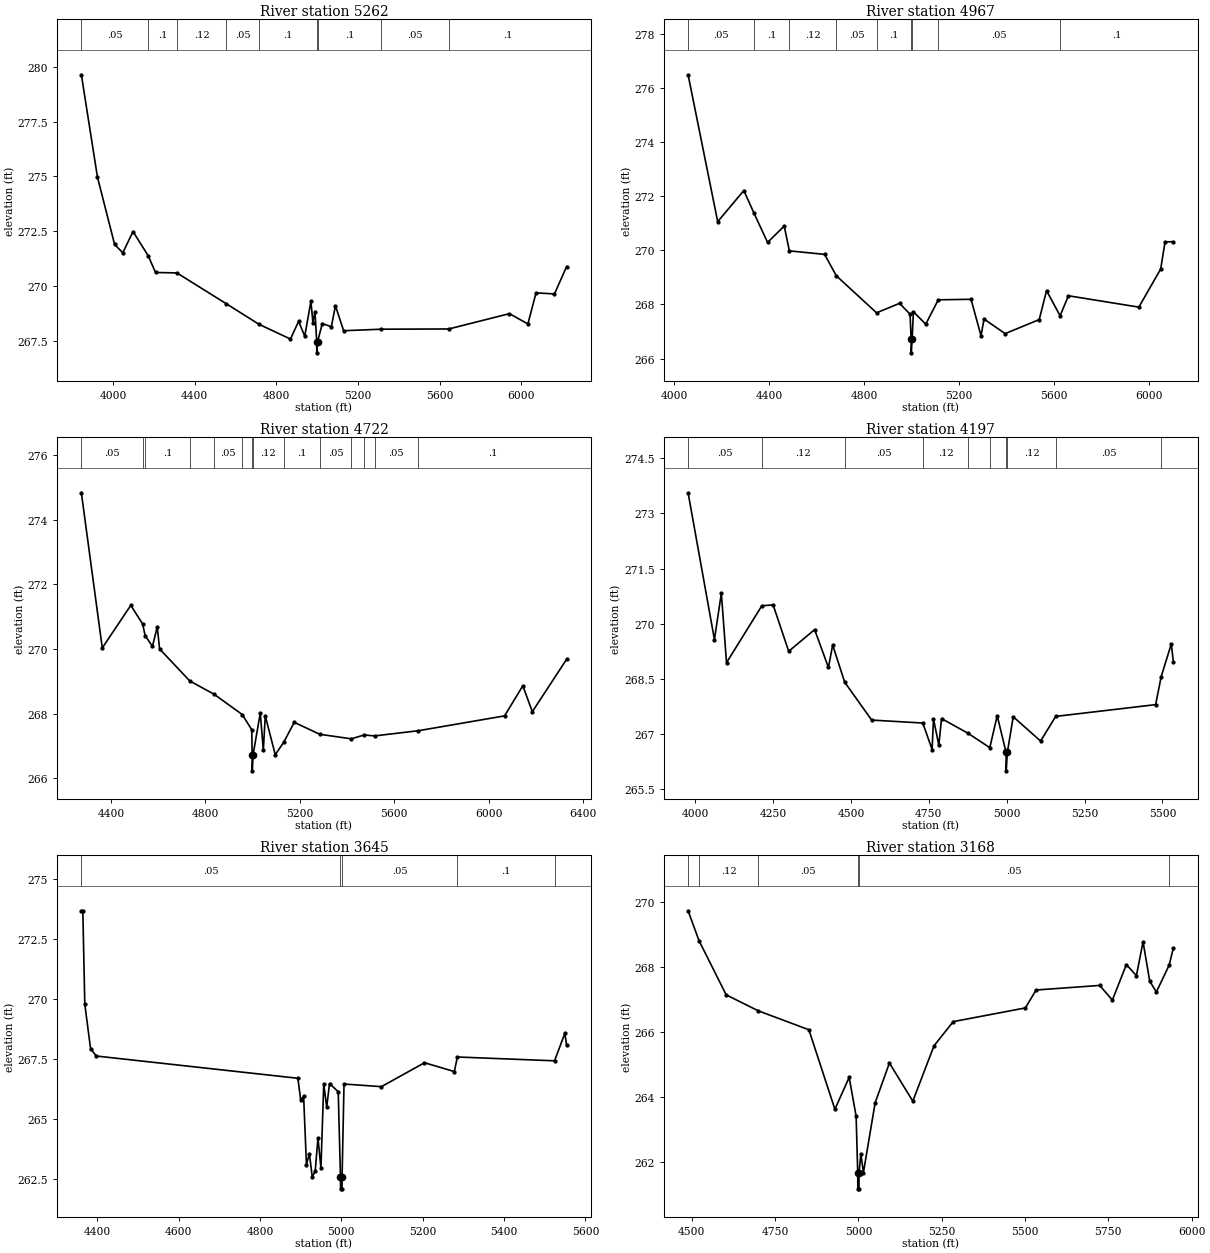
Type RM Length L Ch R = 1,5262,295,295,295
BEGIN DESCRIPTION:
Walnut53 2.0
END DESCRIPTION:
XS GIS Cut Line= 4
      2725578.44      6741650.72      2724903.18      6741695.46
      2724399.11      6741678.97      2723206.76      6741765.96
#Sta/Elev= 30
  3845.3  279.64  3924.0  274.97  4008.1  271.89  4048.2  271.51  4098.3  272.48
  4172.9  271.37  4208.5  270.61  4313.2  270.59  4553.9  269.19  4715.9  268.24
  4869.4  267.57  4909.4  268.38  4939.4  267.70  4969.5  269.29  4979.5  268.31
  4989.5  268.82  4998.0  267.44  4998.3  266.94  5002.0  267.44  5025.4  268.28
  5069.6  268.13  5089.7  269.09  5129.8  267.95  5314.5  268.02  5644.6  268.03
  5941.9  268.73  6032.2  268.26  6072.3  269.68  6162.5  269.63  6221.9  270.88
#Mann=9,-1,0
  3845.3    0.05       0  4172.9     0.1       0  4313.2    0.12       0
  4553.9    0.05       0  4715.9     0.1       0  4998.0    0.07       0
  5002.0     0.1       0  5314.5    0.05       0  5644.6     0.1       0
Bank Sta=4998,5002
Exp/Cntr=0.3,0.1

Type RM Length L Ch R = 1,4967,245,245,245
BEGIN DESCRIPTION:
Walnut53 1.9
END DESCRIPTION:
XS GIS Cut Line= 4
      2725530.59      6741619.95      2724876.63      6741597.77
      2724535.83      6741418.55      2723553.96      6741209.33
#Sta/Elev= 30
  4058.6  276.49  4183.3  271.06  4293.3  272.21  4336.3  271.37  4393.4  270.29
  4463.4  270.90  4485.0  269.98  4633.5  269.85  4682.7  269.06  4852.2  267.69
  4949.2  268.04  4993.2  267.64  4998.0  266.71  4998.3  266.21  5002.0  266.71
  5007.4  267.73  5059.4  267.27  5112.1  268.17  5250.1  268.19  5292.1  266.84
  5304.8  267.46  5393.7  266.92  5537.2  267.44  5568.1  268.51  5625.1  267.58
  5660.2  268.32  5956.7  267.90  6048.7  269.31  6067.0  270.31  6101.9  270.32
#Mann=9,-1,0
  4058.6    0.05       0  4336.3     0.1       0  4485.0    0.12       0
  4682.7    0.05       0  4852.2     0.1       0  4998.0    0.07       0
  5002.0     0.1       0  5112.1    0.05       0  5625.1     0.1       0
Bank Sta=4998,5002
Exp/Cntr=0.3,0.1

Type RM Length L Ch R = 1,4722,525,525,525
BEGIN DESCRIPTION:
Walnut53 1.8
END DESCRIPTION:
XS GIS Cut Line= 5
      2725513.53      6741548.16      2725053.59      6741478.13
      2724823.12      6741355.58      2724391.12      6741076.92
      2723581.78      6741164.43
#Sta/Elev= 30
  4274.9  274.83  4363.4  270.03  4484.2  271.35  4534.5  270.77  4544.9  270.41
  4575.9  270.08  4596.1  270.68  4606.2  270.00  4733.9  269.01  4836.6  268.60
  4956.2  267.97  4996.3  267.50  4998.0  266.73  4998.3  266.23  5002.0  266.73
  5032.4  268.02  5045.3  266.87  5053.5  267.93  5095.8  266.73  5131.4  267.11
  5176.2  267.73  5284.6  267.36  5417.9  267.22  5472.2  267.34  5516.1  267.31
  5700.8  267.47  6066.7  267.93  6144.0  268.86  6184.2  268.06  6329.3  269.68
#Mann=14,-1,0
  4274.9    0.05       0  4534.5    0.12       0  4544.9     0.1       0
  4733.9    0.12       0  4836.6    0.05       0  4956.2    0.12       0
  4998.0    0.07       0  5002.0    0.12       0  5131.4     0.1       0
  5284.6    0.05       0  5417.9     0.1       0  5472.2    0.12       0
  5516.1    0.05       0  5700.8     0.1       0
Bank Sta=4998,5002
Exp/Cntr=0.3,0.1

Type RM Length L Ch R = 1,4197,552,552,552
BEGIN DESCRIPTION:
Walnut53 1.4
END DESCRIPTION:
XS GIS Cut Line= 4
      2725539.11      6741483.18      2724834.97      6741121.97
      2724471.53      6740887.54      2724139.59      6740847.60
#Sta/Elev= 30
  3976.8  273.56  4061.4  269.57  4083.6  270.83  4100.2  268.94  4213.8  270.49
  4249.9  270.51  4299.9  269.25  4383.1  269.84  4427.5  268.81  4441.1  269.42
  4479.7  268.41  4566.3  267.38  4730.5  267.30  4760.4  266.58  4764.8  267.41
  4782.0  266.70  4790.7  267.42  4876.1  267.02  4945.7  266.63  4969.4  267.50
  4998.0  266.50  4998.3  266.00  5002.0  266.50  5020.9  267.47  5108.7  266.81
  5157.4  267.48  5478.2  267.80  5496.0  268.56  5528.5  269.45  5535.0  268.97
#Mann=10,-1,0
  3976.8    0.05       0  4213.8    0.12       0  4479.7    0.05       0
  4730.5    0.12       0  4876.1    0.05       0  4945.7    0.12       0
  4998.0    0.07       0  5002.0    0.12       0  5157.4    0.05       0
  5496.0     0.1       0
Bank Sta=4998,5002
Exp/Cntr=0.3,0.1

Type RM Length L Ch R = 1,3645,477,477,477
BEGIN DESCRIPTION:
Walnut53 1.2
END DESCRIPTION:
XS GIS Cut Line= 3
      2725567.96      6741270.96      2725000.86      6740741.10
      2724660.51      6740501.40
#Sta/Elev= 30
  4361.3  273.69  4364.9  273.69  4369.7  269.79  4383.9  267.93  4398.0  267.62
  4893.4  266.69  4900.2  265.79  4907.5  265.93  4914.4  263.08  4921.7  263.54
  4928.6  262.57  4935.9  262.80  4942.7  264.20  4950.0  262.94  4956.9  266.45
  4964.2  265.48  4971.1  266.47  4992.5  266.13  4998.0  262.57  4998.3  262.07
  5001.8  262.07  5002.0  262.57  5006.7  266.45  5098.6  266.34  5204.5  267.34
  5277.9  266.97  5285.2  267.58  5524.1  267.42  5549.4  268.57  5553.7  268.07
#Mann=5,-1,0
  4361.3    0.05       0  4998.0    0.05       0  5002.0    0.05       0
  5285.2     0.1       0  5524.1    0.12       0
Bank Sta=4998,5002
Exp/Cntr=0.3,0.1

Type RM Length L Ch R = 1,3168,475,475,475
BEGIN DESCRIPTION:
Walnut53 1.0
END DESCRIPTION:
XS GIS Cut Line= 4
      2725916.63      6741091.49      2725337.72      6740597.22
      2725071.63      6740486.80      2724665.26      6740503.30
#Sta/Elev= 30
  4489.0  269.72  4521.9  268.80  4603.4  267.14  4699.8  266.65  4851.5  266.07
  4929.5  263.63  4972.3  264.61  4993.2  263.42  4998.0  261.69  4998.3  261.19
  5001.8  261.19  5002.0  261.69  5007.4  262.26  5015.1  261.69  5050.3  263.83
  5093.1  265.05  5163.3  263.88  5227.0  265.58  5284.7  266.32  5501.1  266.74
  5533.2  267.29  5724.1  267.43  5762.1  266.98  5804.1  268.07  5834.2  267.73
  5854.2  268.77  5874.2  267.56  5894.2  267.23  5932.4  268.05  5945.0  268.57
#Mann=6,-1,0
  4489.0    0.05       0  4521.9    0.12       0  4699.8    0.05       0
  4998.0    0.04       0  5002.0    0.05       0  5932.4    0.12       0
Bank Sta=4998,5002
Exp/Cntr=0.3,0.1