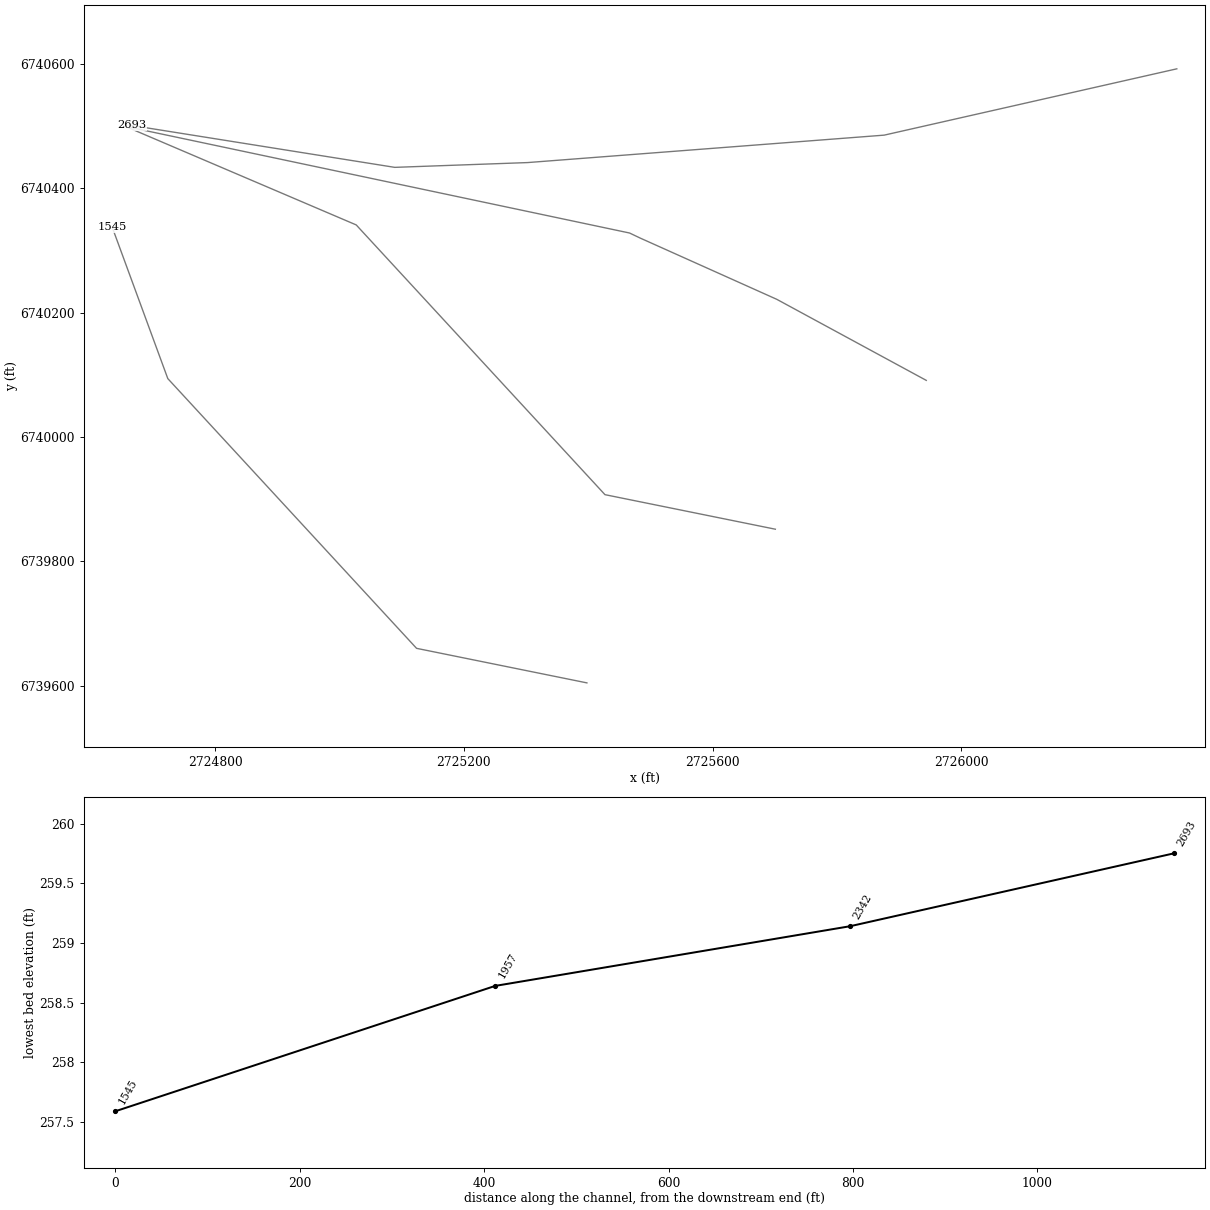
HEC-RAS study Walnut53.prj: Walnut53 Base Level Engineering

--- Walnut53.g01 (geometry) --- (continued)

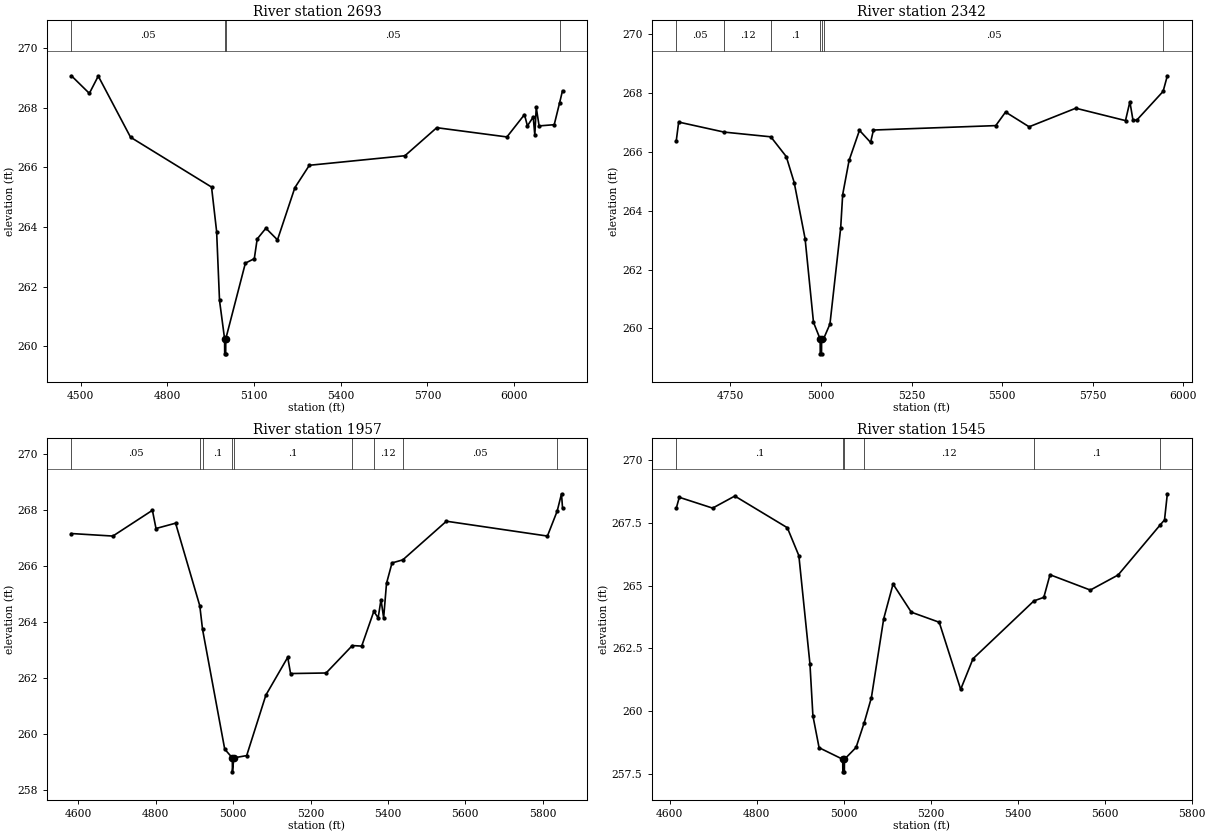
Type RM Length L Ch R = 1,2693,351,351,351
BEGIN DESCRIPTION:
Walnut53 0.7
END DESCRIPTION:
XS GIS Cut Line= 5
      2726346.61      6740592.14      2725876.02      6740485.50
      2725302.59      6740441.38      2725088.90      6740433.68
      2724666.01      6740501.05
#Sta/Elev= 30
  4467.8  269.07  4529.9  268.48  4560.7  269.06  4672.5  267.01  4952.8  265.34
  4970.4  263.85  4980.4  261.54  4998.0  260.25  4998.3  259.75  5001.8  259.75
  5002.0  260.25  5069.9  262.79  5100.8  262.94  5110.8  263.60  5140.9  263.96
  5181.0  263.57  5241.2  265.32  5291.3  266.07  5622.1  266.39  5732.2  267.33
  5975.1  267.02  6035.9  267.77  6046.0  267.39  6066.2  267.69  6071.6  267.08
  6076.6  268.01  6086.5  267.39  6138.8  267.43  6157.1  268.15  6167.5  268.57
#Mann=4,-1,0
  4467.8    0.05       0  4998.0    0.05       0  5002.0    0.05       0
  6157.1    0.12       0
Bank Sta=4998,5002
Exp/Cntr=0.3,0.1

Type RM Length L Ch R = 1,2342,385,385,385
BEGIN DESCRIPTION:
Walnut53 0.5
END DESCRIPTION:
XS GIS Cut Line= 5
      2725943.70      6740091.10      2725703.36      6740221.42
      2725483.64      6740319.96      2725466.51      6740328.10
      2724663.05      6740498.04
#Sta/Elev= 30
  4601.1  266.36  4607.8  267.00  4733.1  266.66  4861.9  266.50  4904.5  265.83
  4926.4  264.95  4956.4  263.05  4979.6  260.21  4998.0  259.64  4998.3  259.14
  5001.8  259.14  5002.0  259.64  5007.8  259.66  5025.0  260.15  5054.6  263.41
  5060.1  264.54  5077.8  265.70  5106.4  266.72  5137.1  266.31  5145.0  266.73
  5482.3  266.88  5509.3  267.34  5574.3  266.84  5703.0  267.47  5840.1  267.05
  5852.2  267.69  5860.5  267.08  5870.7  267.06  5943.8  268.04  5955.5  268.57
#Mann=7,-1,0
  4601.1    0.05       0  4733.1    0.12       0  4861.9     0.1       0
  4998.0    0.07       0  5002.0     0.1       0  5007.8    0.05       0
  5943.8    0.12       0
Bank Sta=4998,5002
Exp/Cntr=0.3,0.1

Type RM Length L Ch R = 1,1957,412,412,412
BEGIN DESCRIPTION:
Walnut53 0.3
END DESCRIPTION:
XS GIS Cut Line= 4
      2725701.00      6739851.75      2725426.99      6739907.31
      2725026.94      6740341.10      2724660.15      6740497.67
#Sta/Elev= 30
  4582.4  267.15  4689.5  267.06  4791.6  267.98  4800.9  267.33  4851.5  267.52
  4914.0  264.57  4921.1  263.73  4978.4  259.45  4998.0  259.14  4998.3  258.64
  5002.0  259.14  5035.1  259.22  5084.7  261.38  5141.1  262.73  5148.5  262.15
  5240.3  262.17  5308.0  263.15  5332.2  263.13  5363.5  264.37  5374.7  264.14
  5382.1  264.79  5388.9  264.14  5396.3  265.37  5410.5  266.10  5438.4  266.21
  5551.0  267.59  5811.9  267.06  5837.1  267.95  5848.3  268.57  5850.9  268.07
#Mann=9,-1,0
  4582.4    0.05       0  4914.0    0.12       0  4921.1     0.1       0
  4998.0    0.07       0  5002.0     0.1       0  5308.0    0.05       0
  5363.5    0.12       0  5438.4    0.05       0  5837.1    0.12       0
Bank Sta=4998,5002
Exp/Cntr=0.3,0.1

Type RM Length L Ch R = 1,1545,0,0,0
BEGIN DESCRIPTION:
Walnut53 0.1
END DESCRIPTION:
XS GIS Cut Line= 4
      2725397.96      6739604.61      2725123.98      6739660.17
      2724723.93      6740093.96      2724634.63      6740337.13
#Sta/Elev= 30
  4615.4  268.07  4622.4  268.51  4699.0  268.08  4750.0  268.56  4870.7  267.30
  4897.2  266.19  4922.7  261.88  4929.5  259.82  4943.7  258.55  4998.0  258.09
  4998.3  257.59  5001.8  257.59  5002.0  258.09  5028.7  258.56  5047.5  259.55
  5063.9  260.54  5092.2  263.68  5113.7  265.06  5155.7  263.94  5219.8  263.54
  5269.1  260.87  5297.5  262.09  5437.5  264.39  5460.2  264.53  5474.4  265.43
  5567.1  264.82  5631.0  265.42  5727.6  267.41  5737.6  267.61  5744.1  268.65
#Mann=6,-1,0
  4615.4     0.1       0  4998.0    0.07       0  5002.0     0.1       0
  5047.5    0.12       0  5437.5     0.1       0  5727.6    0.05       0
Bank Sta=4998,5002
Exp/Cntr=0.3,0.1

Chan Stop Cuts=-1