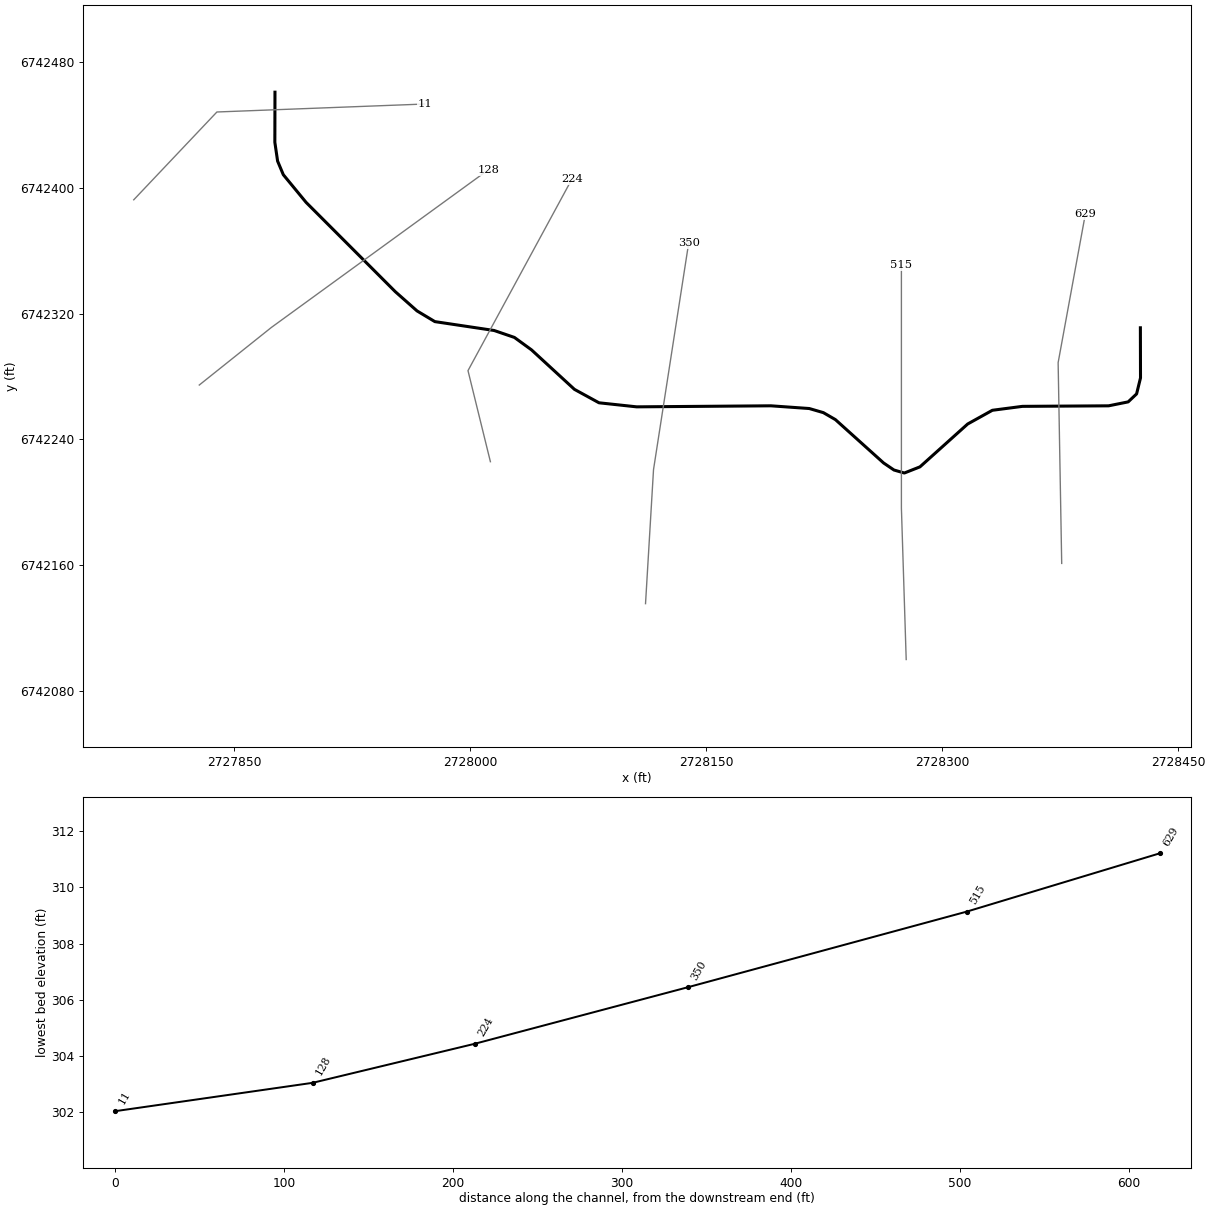
--- Walnut55.prj (project) ---

Proj Title=Walnut55 Base Level Engineering
Current Plan=p01
Default Exp/Contr=0.3,0.1
English Units
Geom File=g01
Flow File=f01
Plan File=p01
Y Axis Title=Elevation
X Axis Title(PF)=Main Channel Distance
X Axis Title(XS)=Station
BEGIN DESCRIPTION:
Walnut55
END DESCRIPTION:
DSS Export Rating Curves= 0
DSS Export Rating Curve Sorted= 0
DSS Export Volume Flow Curves= 0
DXF OffsetX= 0
DXF OffsetY= 0
DXF ScaleX= 1
DXF ScaleY= 10

--- Walnut55.p01 (plan) ---

Plan Title=Multiple Run
Program Version=4.10
Short Identifier=Multiple
Geom File=g01
Flow File=f01
Subcritical Flow
K Sum by GR= 0
Std Step Tol= 0.01
Critical Tol= 0.01
Num of Std Step Trials= 20
Max Error Tol= 0.3
Flow Tol Ratio= 0.001
Split Flow NTrial= 30
Split Flow Tol= 0.02
Split Flow Ratio= 0.02
Log Output Level= 0
Friction Slope Method= 1
Unsteady Friction Slope Method= 2
Unsteady Bridges Friction Slope Method= 1
Parabolic Critical Depth
Global Vel Dist= 1 , 1 , 1
Global Log Level= 0
CheckData=True
Encroach Param=-1 ,0,0, 0
BEGIN DESCRIPTION:
Multiple Run
END DESCRIPTION:
Computation Interval=1HOUR
Output Interval=1HOUR
Run HTab= 0
Run UNet= 0
Run PostProcess= 0
Run WQNet= 0
UNET Theta= 1
UNET Theta Warmup= 1
UNET ZTol= 0.02
UNET ZSATol= 0.05
UNET MxIter= 20
UNET MaxInSteps= 0
UNET DtIC= 0
UNET DtMin= 0
UNET MaxCRTS= 20
UNET WFStab= 2
UNET SFStab= 1
UNET WFX= 1
UNET SFX= 1
UNET DSS MLevel= 4
UNET DZMax Abort= 100
UNET Convert EG Bridges= 0
UNET Use Existing IB Tables=-1
UNET Froude Reduction=False
UNET Froude Limit= 1
UNET Froude Power= 10
UNET Time Slicing=0,0, 5
UNET Junction Losses=0
Instantaneous Interval=1HOUR
Write IC File= 0
Write IC File at Sim End=0
Echo Input=False
Echo Parameters=False
Echo Output=False
Write Detailed= 0
WQ AD Non Conservative
WQ ULTIMATE=-1
WQ Max Comp Step=1HOUR
WQ Output Interval=15MIN
WQ Output Selected Increments= 0
WQ Output face flow=0
WQ Output face velocity=0
WQ Output face area=0
WQ Output face dispersion=0
WQ Output cell volume=0
WQ Output cell surface area=0
WQ Output cell continuity=0
WQ Output cumulative cell continuity=0
WQ Output face conc=0
WQ Output face dconc_dx=0
WQ Output face courant=0
WQ Output face peclet=0
WQ Output face adv mass=0
WQ Output face disp mass=0
WQ Output cell mass=0
WQ Output cell source sink temp=0
WQ Output cell source sink nsm=0
WQ Output MaxMinRange=-1
WQ Daily Max Min Mean=-1
WQ Daily Range=0
WQ Daily Time=0
WQ Create Restart=0
WQ Fixed Restart=0
WQ System Summary=0
WQ Use Fixed Temperature=0
Sorting and Armoring Iterations= 10
XS Update Threshold= 0.02
Hydraulics Update Threshold= 0.02
Energy Slope Method= 1
Volume Change Method= 0
XS Weighting Method= 0
Number of US Weighted Cross Sections= 1
Number of DS Weighted Cross Sections= 1
Upstream XS Weight=0.25
Main XS Weight=0.5
Downstream XS Weight=0.25
Number of DS XS's Weighted with US Boundary= 1
Upstream Boundary Weight= 1
Weight of XSs Associated with US Boundary= 0
Number of US XS's Weighted with DS Boundary= 1
Downstream Boundary Weight= 0.5
Weight of XSs Associated with DS Boundary= 0.5
Sediment Output Level= 4
Mass or Volume Output= 0
Output Increment Type= 1
Profile and TS Output Increment= 10
XS Output Flag= 0
XS Output Increment= 10
Disregard all LS=0
Disregard all Conn=0
Disregard all Breaches=0
Disregard all Pumps=0

--- Walnut55.f01 (steady flow) ---

Flow Title=Multiple
Number of Profiles=7
Profile Names=10-year,25-year,50-year,1pct_min,100-year,1pct_plu,500-year
River Rch & RM= Walnut55,Reach-1,629
      75      87      96      53     106     212     128
River Rch & RM= Walnut55,Reach-1,11
     397     522     622     369     737    1470    1033
Boundary for River Rch & Prof#=Walnut55,Reach-1,1
Up Type=0
Dn Type=3
Dn Slope=0.009
Boundary for River Rch & Prof#=Walnut55,Reach-1,2
Up Type=0
Dn Type=3
Dn Slope=0.009
Boundary for River Rch & Prof#=Walnut55,Reach-1,3
Up Type=0
Dn Type=3
Dn Slope=0.009
Boundary for River Rch & Prof#=Walnut55,Reach-1,4
Up Type=0
Dn Type=3
Dn Slope=0.009
Boundary for River Rch & Prof#=Walnut55,Reach-1,5
Up Type=0
Dn Type=3
Dn Slope=0.009
Boundary for River Rch & Prof#=Walnut55,Reach-1,6
Up Type=0
Dn Type=3
Dn Slope=0.009
Boundary for River Rch & Prof#=Walnut55,Reach-1,7
Up Type=0
Dn Type=3
Dn Slope=0.009

--- Walnut55.g01 (geometry) ---

Geom Title=Existing Conditions
Program Version=4.10

River Reach=Walnut55        ,Reach-1
Reach XY= 30
        2728426.        6742311.      2728426.08       6742279.1
      2728423.59      6742268.91      2728418.24      6742263.83
       2728405.8      6742261.32      2728351.04      6742260.98
      2728331.93      6742258.48      2728316.24      6742249.75
      2728285.91      6742222.46        2728276.      6742218.55
       2728269.4      6742220.45      2728262.79      6742224.95
      2728232.18      6742252.54      2728224.53      6742256.98
      2728215.56       6742259.6      2728191.19      6742261.33
      2728105.86      6742260.67      2728081.93      6742263.25
      2728066.33       6742271.8      2728039.03      6742296.95
      2728028.17      6742304.86      2728015.29      6742309.28
      2727977.62      6742314.93      2727966.29      6742321.74
      2727952.49      6742333.97      2727895.76      6742390.86
       2727881.3      6742408.46      2727877.67      6742417.13
      2727875.92      6742429.11        2727876.        6742461.

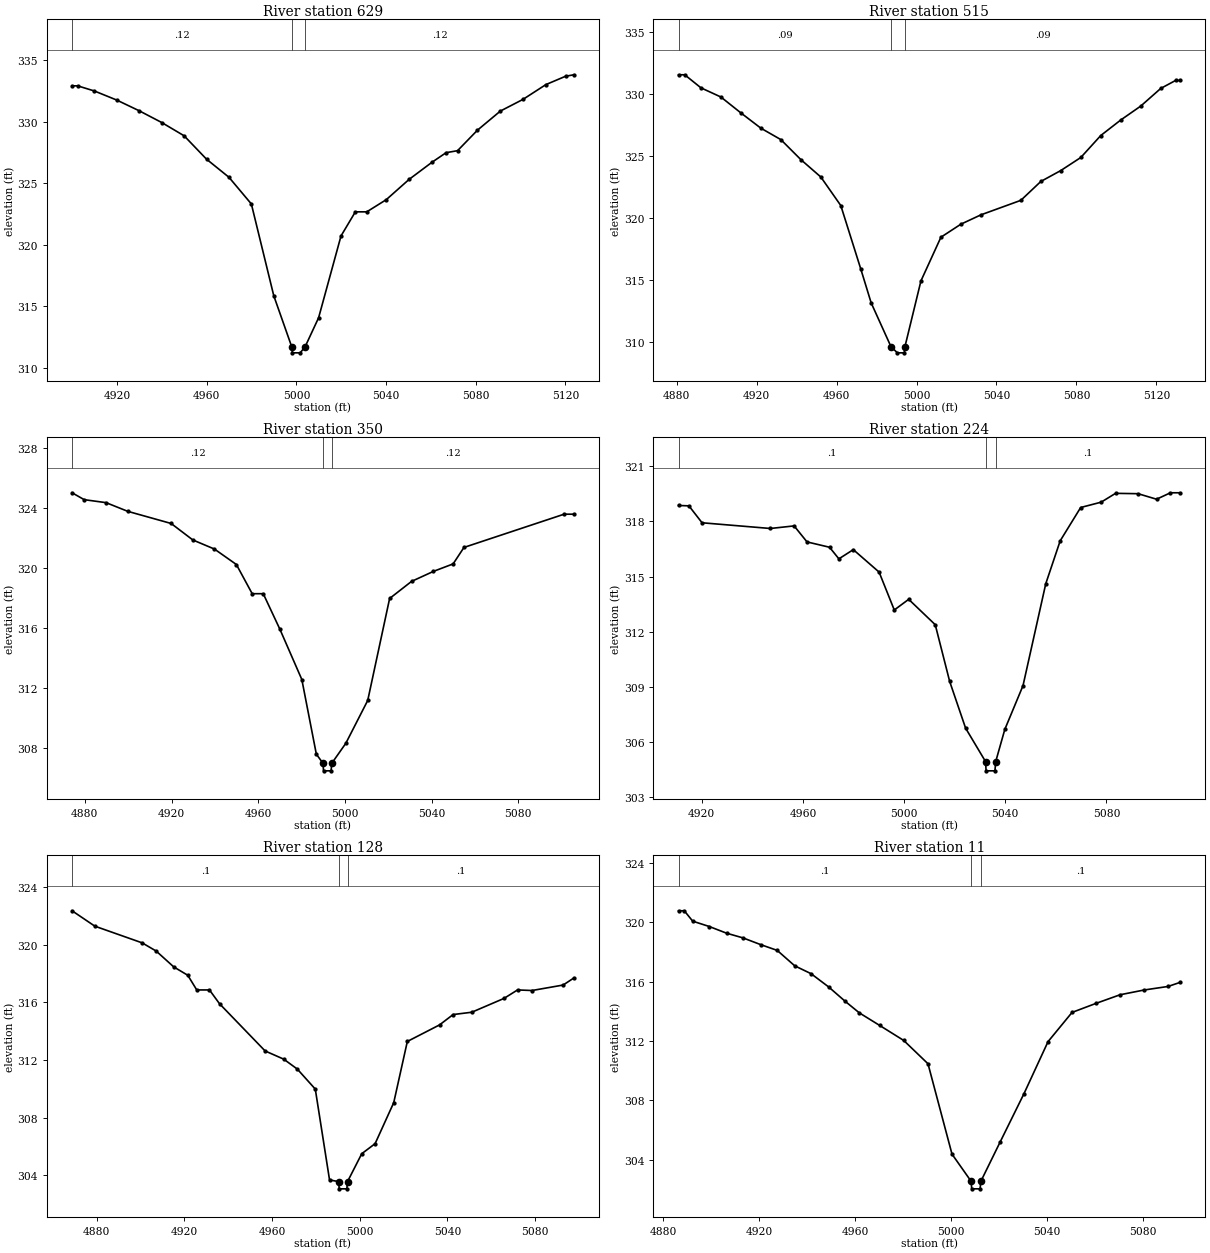
Type RM Length L Ch R = 1 ,629     ,114,114,114
BEGIN DESCRIPTION:
Walnut55 2.0
END DESCRIPTION:
XS GIS Cut Line= 3
        2728376.      6742160.99      2728373.73      6742288.81
      2728391.01      6742383.31
#Sta/Elev= 30
  4899.9  332.91  4902.4  332.91  4909.9  332.49  4919.9  331.75  4929.9  330.88
  4939.9  329.93  4949.9  328.85  4959.9  326.95  4969.9  325.48  4979.9  323.31
  4989.9  315.85  4997.9  311.71  4998.2  311.21  5001.7  311.21  5003.9  311.71
  5009.9  314.06  5019.9  320.71  5026.3  322.67  5031.4  322.67  5040.1  323.66
  5050.3  325.31  5060.5   326.7  5066.8  327.48  5071.9  327.64  5080.8  329.31
    5091  330.86  5101.1  331.81  5111.3  333.01  5120.1  333.69  5123.8  333.81
#Mann= 3 ,-1 , 0
  4899.9     .12       0  4997.9     .07       0  5003.9     .12       0
Bank Sta=4997.9,5003.9
XS Rating Curve= 0 ,0
Exp/Cntr=0.3,0.1

Type RM Length L Ch R = 1 ,515     ,165,165,165
BEGIN DESCRIPTION:
Walnut55 1.8
END DESCRIPTION:
XS GIS Cut Line= 3
      2728277.17       6742099.8      2728274.12      6742196.31
      2728274.12      6742350.85
#Sta/Elev= 30
  4880.9  331.53    4884  331.53  4892.1  330.48  4902.1  329.74  4912.1  328.46
  4922.1  327.23  4932.1  326.31  4942.1   324.7  4952.1   323.3  4962.1     321
  4972.1  315.89  4977.3  313.16  4987.2  309.64  4990.4  309.14  4993.9  309.14
  4994.2  309.64  5002.2  314.93  5012.2  318.45  5022.2   319.5  5032.2  320.25
  5052.2  321.42  5062.2  322.94  5072.2  323.82  5082.2  324.87  5092.2  326.64
  5102.2  327.89  5112.2  329.01  5122.2  330.43  5129.6  331.07    5132  331.07
#Mann= 3 ,-1 , 0
  4880.9     .09       0  4987.2     .07       0  4994.2     .09       0
Bank Sta=4987.2,4994.2
XS Rating Curve= 0 ,0
Exp/Cntr=0.3,0.1

Type RM Length L Ch R = 1 ,350     ,126,126,126
BEGIN DESCRIPTION:
Walnut55 1.6
END DESCRIPTION:
XS GIS Cut Line= 3
       2728111.5      6742135.37      2728116.58      6742220.71
      2728138.93        6742365.
#Sta/Elev= 26
  4874.1  325.02  4879.7  324.56  4889.8  324.36  4899.8  323.78  4919.8  322.97
  4929.8  321.87  4939.8  321.26  4949.9  320.23  4957.2  318.28  4962.3  318.28
    4970   315.9  4980.1  312.55  4986.8  307.56  4989.9  306.95  4990.1  306.45
  4993.6  306.45  4993.9  306.95  5000.4  308.29  5010.5  311.15  5020.6  317.96
  5030.7   319.1  5040.8  319.77  5049.9  320.27  5054.9  321.37  5101.1  323.59
  5105.6  323.59
#Mann= 3 ,-1 , 0
  4874.1     .12       0  4989.9     .07       0  4993.9     .12       0
Bank Sta=4989.9,4993.9
XS Rating Curve= 0 ,0
Exp/Cntr=0.3,0.1

Type RM Length L Ch R = 1 ,224     ,96,96,96
BEGIN DESCRIPTION:
Walnut55 1.4
END DESCRIPTION:
XS GIS Cut Line= 3
      2728012.91      6742225.75      2727998.67      6742283.72
      2728064.73      6742405.69
#Sta/Elev= 30
  4910.8  318.86  4914.9  318.84  4920.1  317.92  4947.1  317.61  4956.5  317.75
  4961.6  316.88  4970.5  316.59  4974.2  315.96  4979.9  316.46  4990.1  315.24
  4996.1  313.18  5001.8  313.76  5012.3  312.38    5018   309.3  5024.3  306.76
  5032.2  304.94  5032.4  304.44  5035.9  304.44  5036.2  304.94  5039.8  306.69
    5047  309.07    5056  314.61  5061.7  316.94  5069.8  318.75  5077.9  319.04
  5083.6  319.52  5092.5   319.5  5099.8   319.2  5105.3  319.55  5109.2  319.55
#Mann= 3 ,-1 , 0
  4910.8      .1       0  5032.2     .07       0  5036.2      .1       0
Bank Sta=5032.2,5036.2
XS Rating Curve= 0 ,0
Exp/Cntr=0.3,0.1

Type RM Length L Ch R = 1 ,128     ,117,117,117
BEGIN DESCRIPTION:
Walnut55 1.2
END DESCRIPTION:
XS GIS Cut Line= 3
      2727827.89      6742274.56      2727873.65      6742311.17
      2728011.41      6742411.45
#Sta/Elev= 30
  4868.7  322.37  4879.1   321.3  4900.7  320.14  4907.1  319.57  4915.1  318.47
  4921.5  317.89  4925.6  316.87  4931.4  316.87    4936  315.91  4956.8  312.63
  4965.3  312.06  4971.5  311.37  4979.7  309.98  4986.2  303.67  4990.4  303.55
  4990.6  303.05  4994.1  303.05  4994.4  303.55  5000.9  305.49    5007  306.19
  5015.5  309.04  5021.7  313.29  5036.4  314.44  5042.6  315.16  5051.1  315.32
  5065.8  316.28    5072  316.87  5078.6  316.83  5092.8  317.21  5097.7   317.7
#Mann= 3 ,-1 , 0
  4868.7      .1       0  4990.4     .07       0  4994.4      .1       0
Bank Sta=4990.4,4994.4
XS Rating Curve= 0 ,0
Exp/Cntr=0.3,0.1

Type RM Length L Ch R = 1 ,11      ,0,0,0
BEGIN DESCRIPTION:
Walnut55 1.0
END DESCRIPTION:
XS GIS Cut Line= 3
      2727786.25      6742392.49      2727839.09      6742448.39
      2727971.07      6742453.46
#Sta/Elev= 30
  4886.5  320.78  4888.9  320.78  4892.4  320.08  4899.3  319.72  4906.5  319.27
  4913.4  318.95  4920.7   318.5  4927.6  318.11  4934.9  317.07  4941.7  316.54
    4949  315.65  4955.9  314.68  4961.8   313.9  4970.3  313.05  4980.3  312.04
  4990.4  310.47  5000.4  304.38  5008.4  302.54  5008.6  302.04  5012.1  302.04
  5012.4  302.54  5020.4  305.18  5030.4  308.46  5040.4  311.96  5050.4  313.93
  5060.4  314.54  5070.4  315.12  5080.4  315.44  5090.4  315.68  5095.5  315.96
#Mann= 3 ,-1 , 0
  4886.5      .1       0  5008.4     .07       0  5012.4      .1       0
Bank Sta=5008.4,5012.4
XS Rating Curve= 0 ,0
Exp/Cntr=0.3,0.1

Chan Stop Cuts=-1
Use User Specified Reach Order=0
Composite Channel Slope=5