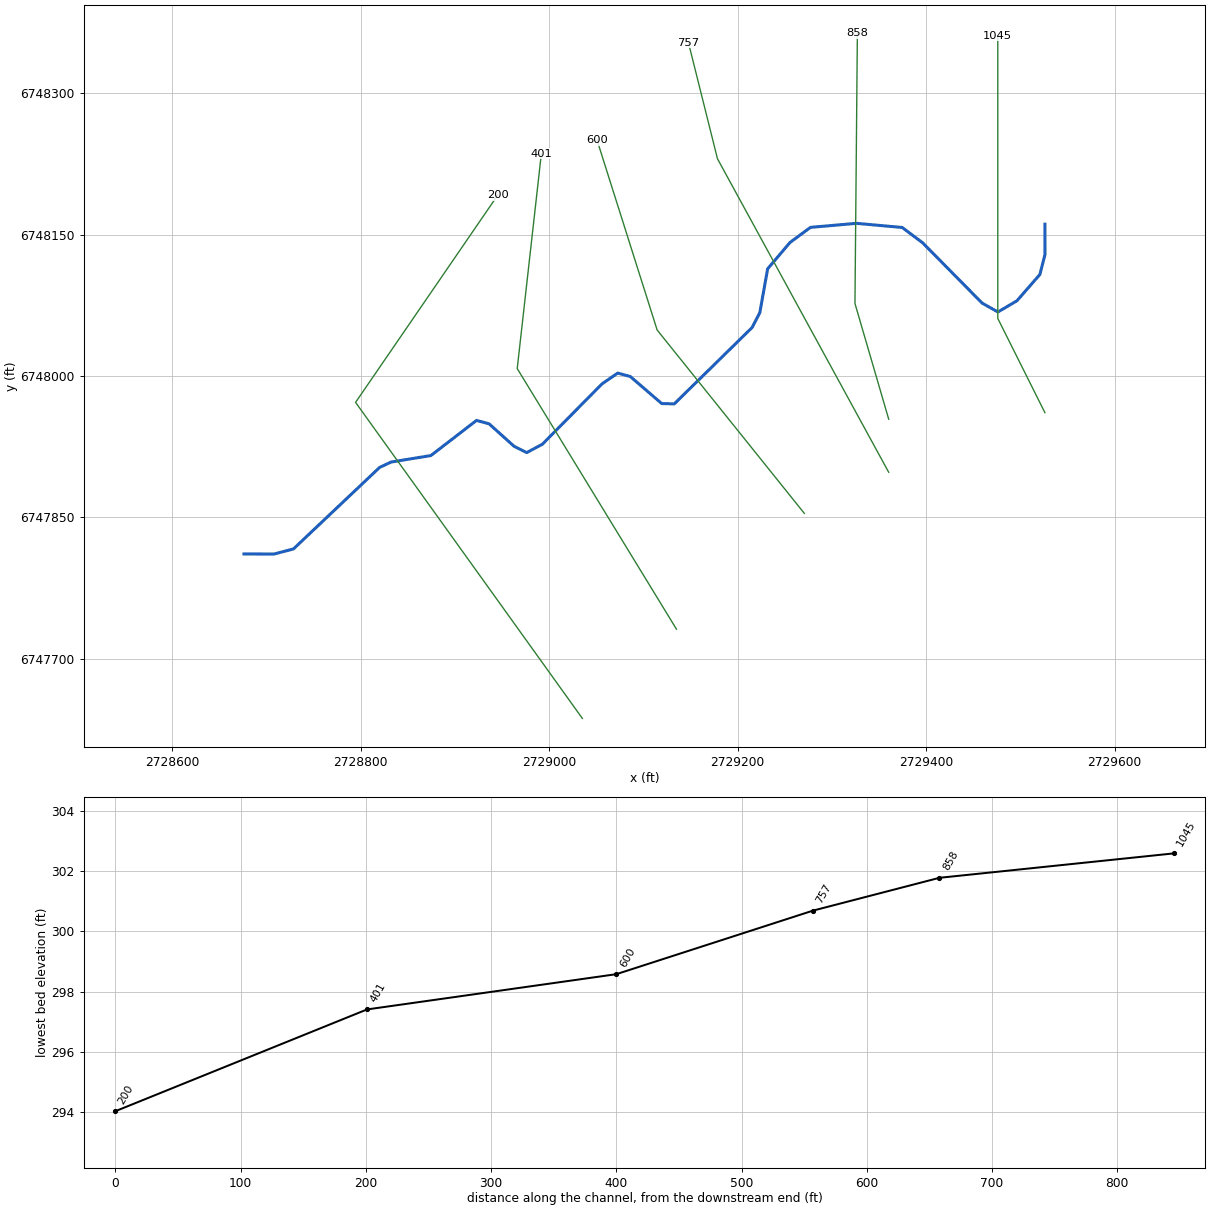
--- Walnut58.prj (project) ---

Proj Title=Walnut58 Base Level Engineering
Current Plan=p01
Default Exp/Contr=0.3,0.1
English Units
Geom File=g01
Flow File=f01
Plan File=p01
BEGIN DESCRIPTION:
Walnut58
END DESCRIPTION:

--- Walnut58.p01 (plan) ---

Plan Title=Multiple Run
Short Identifier=Multiple
Geom File=g01
Flow File=f01
Subcritical Flow
K Sum by GR= 0
Std Step Tol= 0.01
Critical Tol= 0.01
Num of Std Step Trials= 20
Max Error Tol= 0.3
Flow Tol Ratio= 0.001
Split Flow NTrial= 30
Split Flow Tol= 0.02
Split Flow Ratio= 0.02
Log Output Level= 0
Friction Slope Method= 1
Unsteady Friction Slope Method= 2
Unsteady Bridges Friction Slope Method= 1
Parabolic Critical Depth
Global Vel Dist=  1 , 1 , 1
Global Log Level= 0
CheckData=True
Encroach Param= -1, 0, 0, 0
BEGIN DESCRIPTION:
Multiple Run
END DESCRIPTION:

--- Walnut58.f01 (steady flow) ---

Flow Title=Multiple
Number of Profiles=7
Profile Names=10-year,25-year,50-year,1pct_min,100-year,1pct_plu,500-year
River Rch & RM= Walnut58,Reach-1,1045
     209     264     306     177     354     706     472
Boundary for River Rch & Prof#=Walnut58,Reach-1,1
Up Type=0
Dn Type=3
Dn Slope=0.005
Boundary for River Rch & Prof#=Walnut58,Reach-1,2
Up Type=0
Dn Type=3
Dn Slope=0.005
Boundary for River Rch & Prof#=Walnut58,Reach-1,3
Up Type=0
Dn Type=3
Dn Slope=0.005
Boundary for River Rch & Prof#=Walnut58,Reach-1,4
Up Type=0
Dn Type=3
Dn Slope=0.005
Boundary for River Rch & Prof#=Walnut58,Reach-1,5
Up Type=0
Dn Type=3
Dn Slope=0.005
Boundary for River Rch & Prof#=Walnut58,Reach-1,6
Up Type=0
Dn Type=3
Dn Slope=0.005
Boundary for River Rch & Prof#=Walnut58,Reach-1,7
Up Type=0
Dn Type=3
Dn Slope=0.005

--- Walnut58.g01 (geometry) ---

Geom Title=Existing Conditions

River Reach=Walnut58,Reach-1
Reach XY= 30
      2729526.00      6748161.00      2729526.07      6748128.73
      2729520.69      6748107.63      2729496.32      6748079.70
      2729476.17      6748067.83      2729459.42      6748077.19
      2729396.16      6748141.33      2729374.50      6748157.52
      2729325.97      6748161.89      2729277.28      6748157.63
      2729255.46      6748141.58      2729231.74      6748113.58
      2729223.45      6748067.07      2729215.21      6748051.29
      2729132.68      6747970.30      2729119.34      6747970.61
      2729086.00      6747999.28      2729072.67      6748002.97
      2729056.00      6747991.54      2728992.67      6747927.46
      2728976.00      6747918.57      2728962.68      6747925.24
      2728936.05      6747949.17      2728922.77      6747952.75
      2728874.35      6747915.44      2728832.05      6747908.54
      2728819.95      6747902.88      2728728.51      6747816.33
      2728707.88      6747810.93      2728676.00      6747811.00

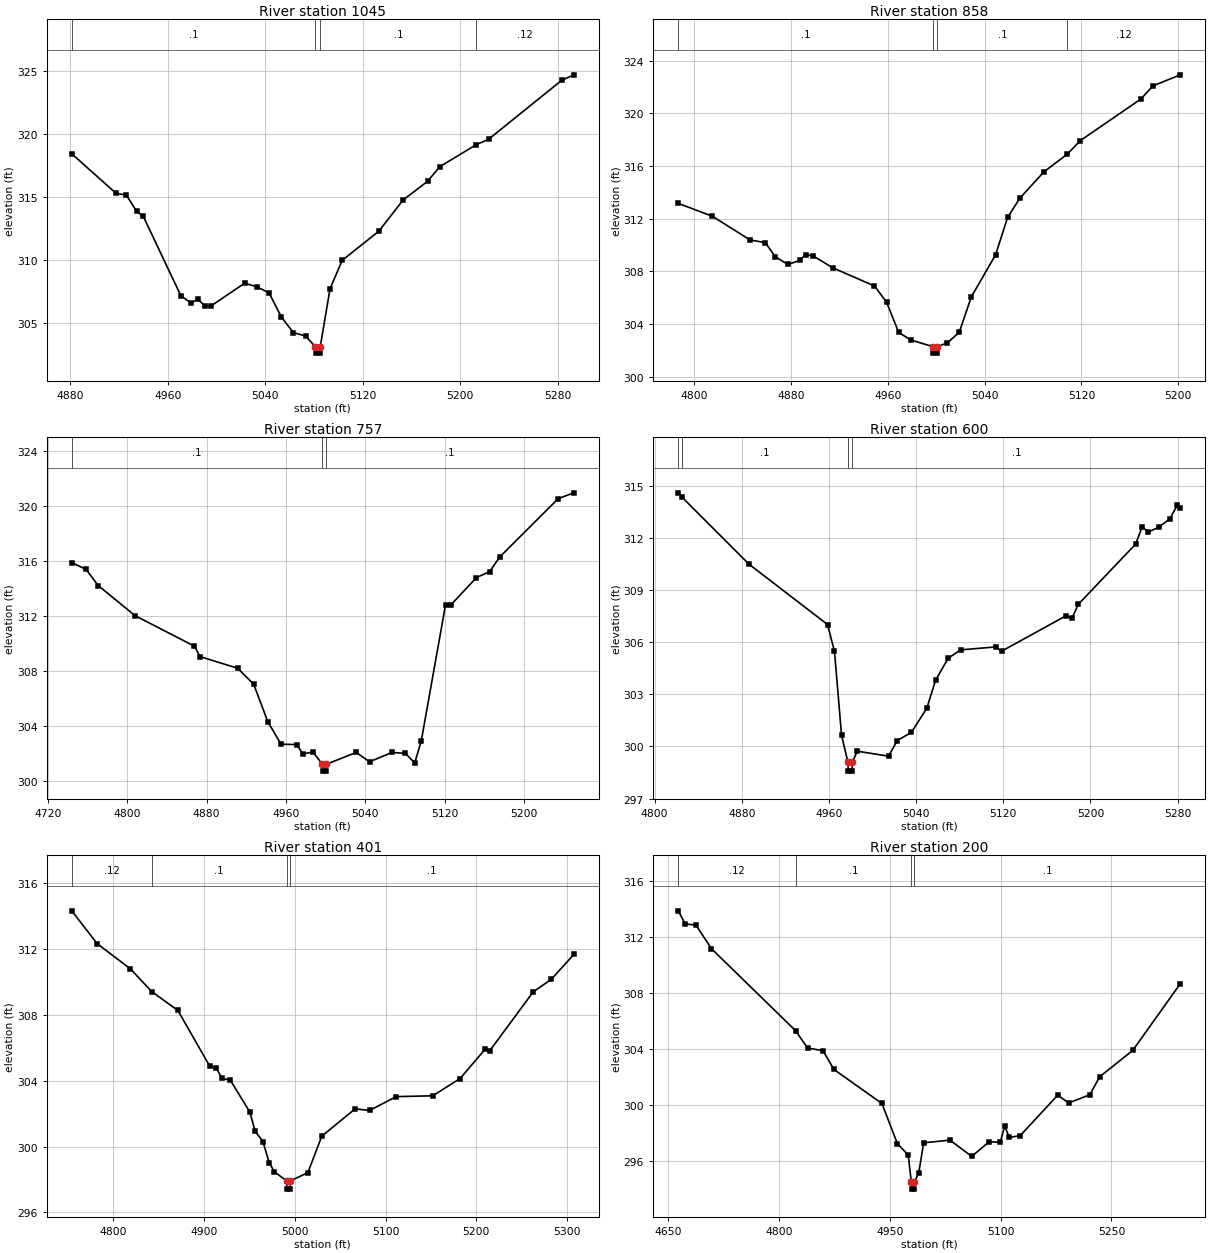
Type RM Length L Ch R = 1,1045,187,187,187
BEGIN DESCRIPTION:
Walnut58 4.0
END DESCRIPTION:
XS GIS Cut Line= 3
      2729526.02      6747960.97      2729476.00      6748061.00
      2729476.00      6748360.96
#Sta/Elev= 30
  4881.3  318.44  4917.7  315.29  4926.1  315.16  4934.4  313.88  4940.0  313.46
  4970.8  307.15  4979.2  306.57  4984.8  306.88  4990.3  306.35  4995.6  306.35
  5023.1  308.15  5033.1  307.86  5043.1  307.38  5053.1  305.48  5063.1  304.22
  5073.1  303.95  5081.1  303.09  5081.4  302.59  5084.9  302.59  5085.1  303.09
  5093.1  307.70  5103.1  309.97  5133.1  312.28  5153.1  314.77  5173.1  316.25
  5183.1  317.41  5213.1  319.17  5223.1  319.59  5283.1  324.28  5293.1  324.72
#Mann=4,-1,0
  4881.3     0.1       0  5081.1    0.07       0  5085.1     0.1       0
  5213.1    0.12       0
Bank Sta=5081.1,5085.1
Exp/Cntr=0.3,0.1

Type RM Length L Ch R = 1,858,101,101,101
BEGIN DESCRIPTION:
Walnut58 3.5
END DESCRIPTION:
XS GIS Cut Line= 3
      2729360.25      6747954.01      2729324.42      6748076.86
      2729326.98      6748363.58
#Sta/Elev= 30
  4787.0  313.16  4815.0  312.19  4846.4  310.38  4858.9  310.18  4867.2  309.10
  4877.6  308.52  4887.2  308.82  4892.4  309.27  4898.4  309.17  4914.5  308.27
  4949.1  306.88  4959.1  305.65  4969.1  303.35  4979.1  302.78  4997.1  302.28
  4997.4  301.78  5000.9  301.78  5001.1  302.28  5009.1  302.55  5019.1  303.36
  5029.1  306.06  5049.1  309.25  5059.1  312.10  5069.1  313.55  5089.1  315.56
  5108.3  316.90  5119.1  317.93  5169.1  321.09  5179.1  322.09  5201.7  322.93
#Mann=4,-1,0
  4787.0     0.1       0  4997.1    0.07       0  5001.1     0.1       0
  5108.3    0.12       0
Bank Sta=4997.1,5001.1
Exp/Cntr=0.3,0.1

Type RM Length L Ch R = 1,757,157,157,157
BEGIN DESCRIPTION:
Walnut58 3.0
END DESCRIPTION:
XS GIS Cut Line= 3
      2729360.24      6747897.68      2729178.48      6748230.48
      2729147.75      6748353.40
#Sta/Elev= 30
  4744.1  315.86  4758.5  315.36  4770.7  314.19  4807.8  312.00  4867.6  309.78
  4873.3  309.02  4911.3  308.17  4927.4  307.01  4941.6  304.29  4954.9  302.65
  4971.0  302.62  4976.7  301.94  4987.2  302.08  4996.6  301.19  4996.8  300.69
  5000.3  300.69  5000.6  301.19  5030.8  302.05  5044.1  301.37  5066.9  302.05
  5080.2  301.98  5089.7  301.29  5096.3  302.90  5120.7  312.78  5126.1  312.78
  5151.9  314.77  5165.1  315.19  5175.4  316.27  5234.3  320.51  5250.0  320.93
#Mann=3,-1,0
  4744.1     0.1       0  4996.6    0.07       0  5000.6     0.1       0
Bank Sta=4996.6,5000.6
Exp/Cntr=0.3,0.1

Type RM Length L Ch R = 1,600,199,199,199
BEGIN DESCRIPTION:
Walnut58 2.0
END DESCRIPTION:
XS GIS Cut Line= 3
      2729270.68      6747854.09      2729114.47      6748048.70
      2729050.74      6748250.11
#Sta/Elev= 30
  4821.7  314.60  4825.0  314.36  4886.7  310.49  4958.7  307.02  4965.1  305.47
  4971.6  300.64  4977.5  299.08  4977.7  298.58  4981.2  298.58  4981.5  299.08
  4985.9  299.73  5014.7  299.44  5022.7  300.34  5035.7  300.81  5049.9  302.21
  5057.9  303.82  5069.5  305.08  5080.8  305.56  5113.1  305.73  5118.4  305.48
  5177.8  307.53  5183.0  307.37  5189.0  308.19  5241.5  311.65  5247.6  312.66
  5252.9  312.33  5262.5  312.62  5272.9  313.10  5279.9  313.91  5282.5  313.75
#Mann=4,-1,0
  4821.7    0.12       0  4825.0     0.1       0  4977.5    0.07       0
  4981.5     0.1       0
Bank Sta=4977.5,4981.5
Exp/Cntr=0.3,0.1

Type RM Length L Ch R = 1,401,201,201,201
BEGIN DESCRIPTION:
Walnut58 1.5
END DESCRIPTION:
XS GIS Cut Line= 3
      2729134.97      6747731.20      2728965.98      6748007.74
      2728991.58      6748235.62
#Sta/Elev= 30
  4754.1  314.32  4782.0  312.33  4818.8  310.79  4842.3  309.41  4871.0  308.27
  4906.2  304.88  4913.6  304.74  4919.5  304.15  4929.0  304.02  4950.4  302.09
  4956.2  300.93  4964.8  300.30  4971.7  299.02  4977.5  298.46  4991.0  297.91
  4991.2  297.41  4994.7  297.41  4995.0  297.91  5014.3  298.41  5029.7  300.63
  5066.5  302.29  5082.3  302.19  5111.7  303.03  5151.9  303.08  5182.1  304.13
  5210.0  305.93  5215.0  305.83  5262.6  309.39  5282.7  310.16  5307.5  311.67
#Mann=4,-1,0
  4754.1    0.12       0  4842.3     0.1       0  4991.0    0.07       0
  4995.0     0.1       0
Bank Sta=4991,4995
Exp/Cntr=0.3,0.1

Type RM Length L Ch R = 1,200,0,0,0
BEGIN DESCRIPTION:
Walnut58 1.0
END DESCRIPTION:
XS GIS Cut Line= 3
      2729035.11      6747636.48      2728794.43      6747971.89
      2728945.47      6748192.04
#Sta/Elev= 30
  4663.5  313.85  4672.9  312.92  4687.6  312.83  4708.5  311.15  4822.3  305.32
  4838.6  304.08  4859.5  303.89  4874.3  302.55  4939.3  300.13  4960.2  297.27
  4974.9  296.46  4979.1  294.53  4979.4  294.03  4982.9  294.03  4983.1  294.53
  4989.1  295.17  4995.8  297.33  5031.4  297.52  5060.9  296.36  5084.6  297.41
  5099.5  297.36  5105.6  298.53  5111.6  297.71  5126.5  297.84  5177.3  300.72
  5192.2  300.17  5220.8  300.75  5234.1  302.03  5278.9  303.91  5343.3  308.66
#Mann=4,-1,0
  4663.5    0.12       0  4822.3     0.1       0  4979.1    0.07       0
  4983.1     0.1       0
Bank Sta=4979.1,4983.1
Exp/Cntr=0.3,0.1

Chan Stop Cuts=-1