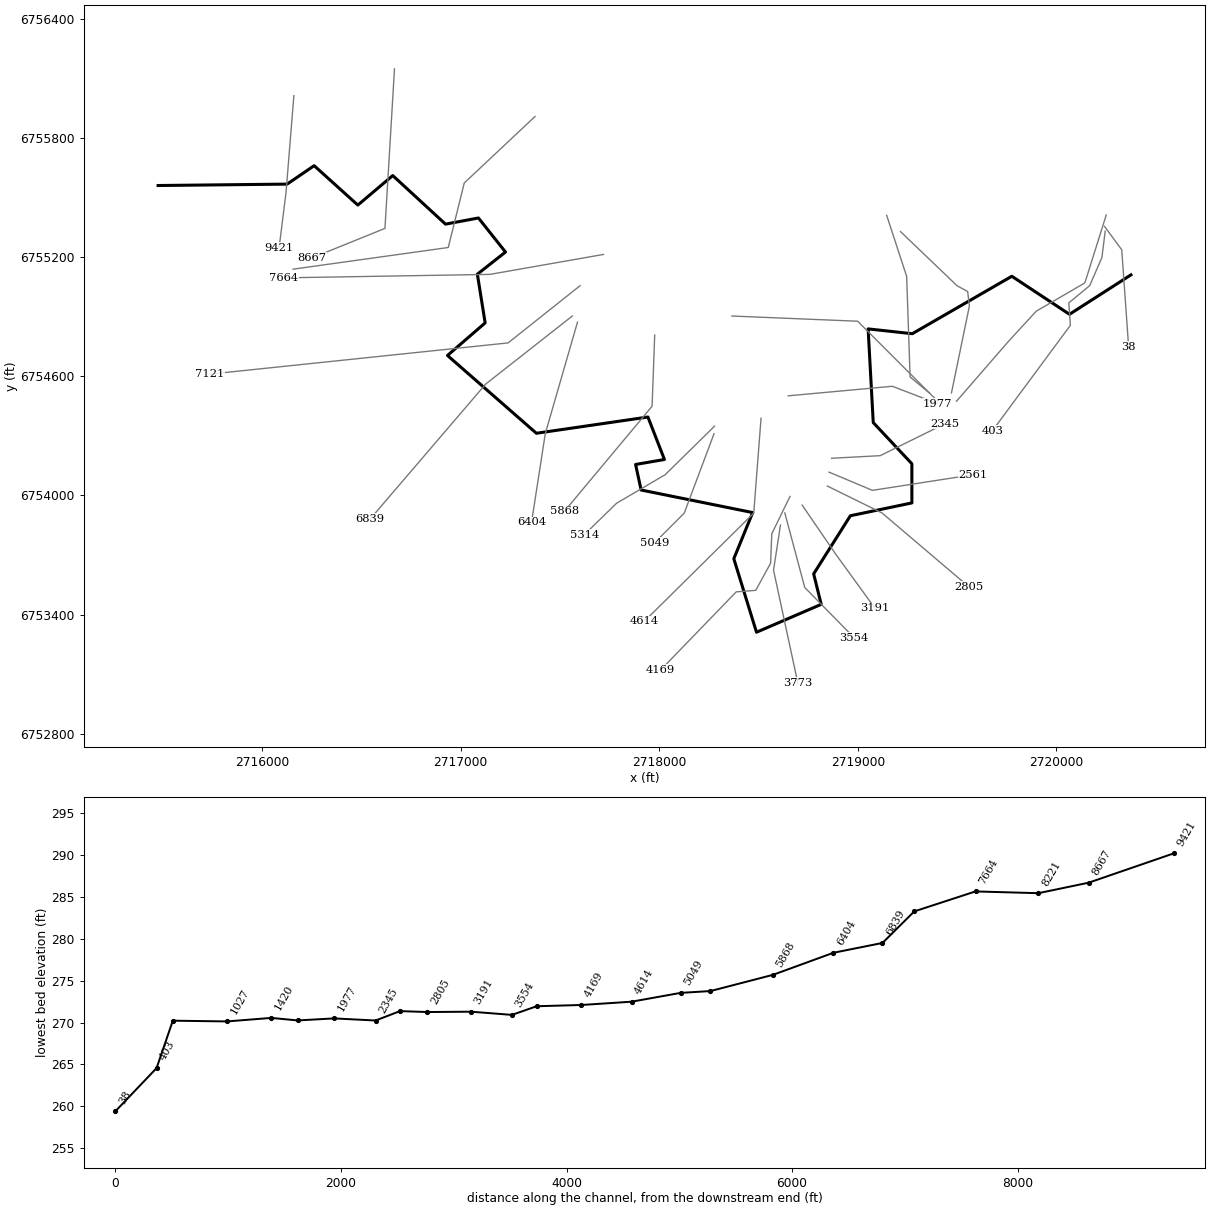
--- Walnut6.prj (project) ---

Proj Title=Walnut6 Base Level Engineering
Current Plan=p01
Default Exp/Contr=0.3,0.1
English Units
Geom File=g01
Flow File=f01
Plan File=p01
Y Axis Title=Elevation
X Axis Title(PF)=Main Channel Distance
X Axis Title(XS)=Station
BEGIN DESCRIPTION:
Walnut6
END DESCRIPTION:
DSS Export Rating Curves= 0
DSS Export Rating Curve Sorted= 0
DSS Export Volume Flow Curves= 0
DXF OffsetX= 0
DXF OffsetY= 0
DXF ScaleX= 1
DXF ScaleY= 10

--- Walnut6.p01 (plan) ---

Plan Title=Multiple Run
Program Version=4.10
Short Identifier=Multiple
Geom File=g01
Flow File=f01
Subcritical Flow
K Sum by GR= 0
Std Step Tol= 0.01
Critical Tol= 0.01
Num of Std Step Trials= 20
Max Error Tol= 0.3
Flow Tol Ratio= 0.001
Split Flow NTrial= 30
Split Flow Tol= 0.02
Split Flow Ratio= 0.02
Log Output Level= 0
Friction Slope Method= 1
Unsteady Friction Slope Method= 2
Unsteady Bridges Friction Slope Method= 1
Parabolic Critical Depth
Global Vel Dist= 1 , 1 , 1
Global Log Level= 0
CheckData=True
Encroach Param=-1 ,0,0, 0
BEGIN DESCRIPTION:
Multiple Run
END DESCRIPTION:
Computation Interval=1HOUR
Output Interval=1HOUR
Run HTab= 0
Run UNet= 0
Run PostProcess= 0
Run WQNet= 0
UNET Theta= 1
UNET Theta Warmup= 1
UNET ZTol= 0.02
UNET ZSATol= 0.05
UNET MxIter= 20
UNET MaxInSteps= 0
UNET DtIC= 0
UNET DtMin= 0
UNET MaxCRTS= 20
UNET WFStab= 2
UNET SFStab= 1
UNET WFX= 1
UNET SFX= 1
UNET DSS MLevel= 4
UNET DZMax Abort= 100
UNET Convert EG Bridges= 0
UNET Use Existing IB Tables=-1
UNET Froude Reduction=False
UNET Froude Limit= 1
UNET Froude Power= 10
UNET Time Slicing=0,0, 5
UNET Junction Losses=0
Instantaneous Interval=1HOUR
Write IC File= 0
Write IC File at Sim End=0
Echo Input=False
Echo Parameters=False
Echo Output=False
Write Detailed= 0
WQ AD Non Conservative
WQ ULTIMATE=-1
WQ Max Comp Step=1HOUR
WQ Output Interval=15MIN
WQ Output Selected Increments= 0
WQ Output face flow=0
WQ Output face velocity=0
WQ Output face area=0
WQ Output face dispersion=0
WQ Output cell volume=0
WQ Output cell surface area=0
WQ Output cell continuity=0
WQ Output cumulative cell continuity=0
WQ Output face conc=0
WQ Output face dconc_dx=0
WQ Output face courant=0
WQ Output face peclet=0
WQ Output face adv mass=0
WQ Output face disp mass=0
WQ Output cell mass=0
WQ Output cell source sink temp=0
WQ Output cell source sink nsm=0
WQ Output MaxMinRange=-1
WQ Daily Max Min Mean=-1
WQ Daily Range=0
WQ Daily Time=0
WQ Create Restart=0
WQ Fixed Restart=0
WQ System Summary=0
WQ Use Fixed Temperature=0
Sorting and Armoring Iterations= 10
XS Update Threshold= 0.02
Hydraulics Update Threshold= 0.02
Energy Slope Method= 1
Volume Change Method= 0
XS Weighting Method= 0
Number of US Weighted Cross Sections= 1
Number of DS Weighted Cross Sections= 1
Upstream XS Weight=0.25
Main XS Weight=0.5
Downstream XS Weight=0.25
Number of DS XS's Weighted with US Boundary= 1
Upstream Boundary Weight= 1
Weight of XSs Associated with US Boundary= 0
Number of US XS's Weighted with DS Boundary= 1
Downstream Boundary Weight= 0.5
Weight of XSs Associated with DS Boundary= 0.5
Sediment Output Level= 4
Mass or Volume Output= 0
Output Increment Type= 1
Profile and TS Output Increment= 10
XS Output Flag= 0
XS Output Increment= 10
Disregard all LS=0
Disregard all Conn=0
Disregard all Breaches=0
Disregard all Pumps=0

--- Walnut6.f01 (steady flow) ---

Flow Title=Multiple
Number of Profiles=7
Profile Names=10-year,25-year,50-year,1pct_min,100-year,1pct_plu,500-year
River Rch & RM= Walnut6,Reach-1,9421
     509     664     784     460     917    1829    1252
River Rch & RM= Walnut6,Reach-1,7664
     696     926    1108     656    1310    2613    1831
Boundary for River Rch & Prof#=Walnut6,Reach-1,1
Up Type=0
Dn Type=3
Dn Slope=0.014
Boundary for River Rch & Prof#=Walnut6,Reach-1,2
Up Type=0
Dn Type=3
Dn Slope=0.014
Boundary for River Rch & Prof#=Walnut6,Reach-1,3
Up Type=0
Dn Type=3
Dn Slope=0.014
Boundary for River Rch & Prof#=Walnut6,Reach-1,4
Up Type=0
Dn Type=3
Dn Slope=0.014
Boundary for River Rch & Prof#=Walnut6,Reach-1,5
Up Type=0
Dn Type=3
Dn Slope=0.014
Boundary for River Rch & Prof#=Walnut6,Reach-1,6
Up Type=0
Dn Type=3
Dn Slope=0.014
Boundary for River Rch & Prof#=Walnut6,Reach-1,7
Up Type=0
Dn Type=3
Dn Slope=0.014

--- Walnut6.g01 (geometry) ---

Geom Title=Existing Conditions

River Reach=Walnut6,Reach-1
Reach XY= 30
      2715476.00      6755561.00      2716125.79      6755568.03
      2716261.88      6755660.83      2716481.92      6755462.43
      2716657.81      6755611.11      2716923.57      6755366.40
      2717089.38      6755397.47      2717225.61      6755225.91
      2717083.98      6755114.35      2717123.16      6754869.01
      2716933.45      6754704.94      2717381.26      6754313.09
      2717943.06      6754394.94      2718026.22      6754181.01
      2717880.93      6754155.95      2717908.77      6754027.28
      2718470.72      6753913.71      2718375.64      6753681.21
      2718489.89      6753311.03      2718815.82      6753451.29
      2718777.82      6753604.88      2718962.70      6753897.66
      2719272.55      6753962.25      2719272.47      6754159.54
      2719077.96      6754366.89      2719052.12      6754838.75
      2719274.53      6754814.54      2719776.01      6755103.92
      2720066.32      6754912.24      2720376.00      6755111.00

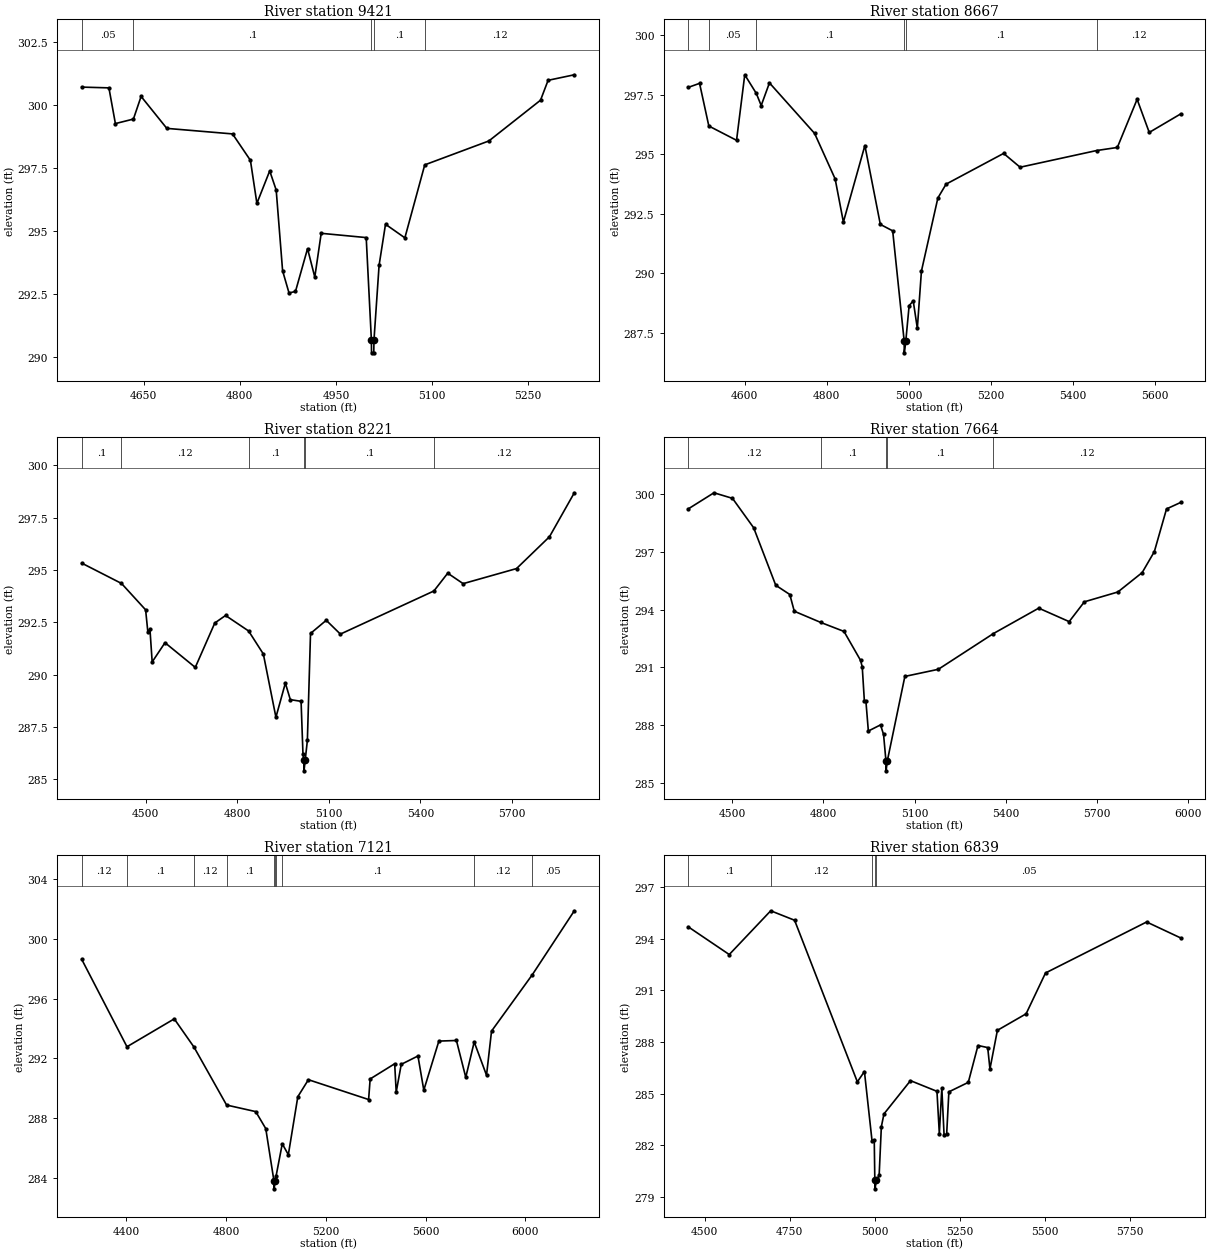
Type RM Length L Ch R = 1,9421,754,754,754
BEGIN DESCRIPTION:
Walnut6 17.0
END DESCRIPTION:
XS GIS Cut Line= 3
      2716159.77      6756013.28      2716120.46      6755528.38
      2716085.50      6755248.75
#Sta/Elev= 30
  4553.6  300.71  4596.0  300.68  4606.1  299.26  4634.2  299.44  4646.2  300.34
  4686.3  299.07  4788.8  298.85  4816.7  297.80  4826.8  296.09  4846.8  297.38
  4856.9  296.62  4866.9  293.41  4876.9  292.53  4887.0  292.59  4905.8  294.29
  4917.1  293.16  4927.1  294.90  4997.3  294.73  5005.4  290.65  5005.6  290.15
  5009.1  290.15  5009.4  290.65  5017.4  293.63  5027.4  295.26  5057.6  294.72
  5088.6  297.62  5188.6  298.57  5269.2  300.19  5281.0  300.98  5321.9  301.20
#Mann=5,-1,0
  4553.6    0.05       0  4634.2     0.1       0  5005.4    0.07       0
  5009.4     0.1       0  5088.6    0.12       0
Bank Sta=5005.4,5009.4
Exp/Cntr=0.3,0.1

Type RM Length L Ch R = 1,8667,446,446,446
BEGIN DESCRIPTION:
Walnut6 16.0
END DESCRIPTION:
XS GIS Cut Line= 3
      2716666.55      6756148.70      2716618.49      6755344.90
      2716251.55      6755196.37
#Sta/Elev= 30
  4462.2  297.80  4489.9  297.97  4512.5  296.18  4580.1  295.58  4600.1  298.33
  4628.2  297.55  4640.2  297.04  4660.3  297.99  4770.4  295.87  4820.5  293.96
  4840.6  292.15  4893.0  295.36  4930.7  292.05  4960.8  291.78  4988.8  287.16
  4989.1  286.66  4992.8  287.16  5000.9  288.64  5010.9  288.84  5020.9  287.69
  5030.9  290.09  5071.0  293.16  5091.0  293.74  5231.3  295.03  5271.5  294.45
  5457.9  295.15  5508.6  295.28  5556.8  297.30  5586.4  295.91  5663.3  296.69
#Mann=6,-1,0
  4462.2    0.12       0  4512.5    0.05       0  4628.2     0.1       0
  4988.8    0.07       0  4992.8     0.1       0  5457.9    0.12       0
Bank Sta=4988.8,4992.8
Exp/Cntr=0.3,0.1

Type RM Length L Ch R = 1,8221,557,557,557
BEGIN DESCRIPTION:
Walnut6 15.0
END DESCRIPTION:
XS GIS Cut Line= 4
      2717374.32      6755908.49      2717017.99      6755573.76
      2716937.41      6755248.78      2716155.41      6755139.57
#Sta/Elev= 30
  4291.1  295.33  4421.3  294.36  4500.3  293.10  4507.6  292.05  4514.5  292.18
  4521.8  290.61  4563.8  291.53  4663.0  290.35  4726.9  292.47  4762.1  292.83
  4837.6  292.09  4885.9  290.99  4927.1  287.97  4958.0  289.60  4974.3  288.81
  5009.5  288.73  5015.7  286.20  5018.9  285.91  5019.1  285.41  5022.9  285.91
  5030.1  286.86  5040.4  291.97  5091.9  292.60  5138.2  291.94  5444.5  294.00
  5489.8  294.85  5540.3  294.35  5715.1  295.07  5823.0  296.59  5904.4  298.69
#Mann=6,-1,0
  4291.1     0.1       0  4421.3    0.12       0  4837.6     0.1       0
  5018.9    0.07       0  5022.9     0.1       0  5444.5    0.12       0
Bank Sta=5018.9,5022.9
Exp/Cntr=0.3,0.1

Type RM Length L Ch R = 1,7664,543,543,543
BEGIN DESCRIPTION:
Walnut6 14.0
END DESCRIPTION:
XS GIS Cut Line= 3
      2717719.44      6755213.84      2717147.11      6755113.35
      2716109.14      6755095.91
#Sta/Elev= 30
  4355.5  299.24  4440.2  300.08  4501.1  299.79  4570.7  298.26  4643.3  295.27
  4689.5  294.79  4704.2  293.92  4790.8  293.34  4867.6  292.87  4921.9  291.37
  4927.6  291.03  4934.6  289.25  4939.6  289.25  4947.7  287.69  4987.7  288.01
  4997.7  287.51  5005.6  286.12  5006.0  285.62  5009.8  286.12  5067.7  290.53
  5177.7  290.90  5358.9  292.76  5507.8  294.08  5607.8  293.38  5657.8  294.41
  5767.8  294.92  5847.8  295.93  5887.8  297.02  5927.8  299.24  5974.7  299.58
#Mann=5,-1,0
  4355.5    0.12       0  4790.8     0.1       0  5005.6    0.07       0
  5009.8     0.1       0  5358.9    0.12       0
Bank Sta=5005.6,5009.8
Exp/Cntr=0.3,0.1

Type RM Length L Ch R = 1,7121,282,282,282
BEGIN DESCRIPTION:
Walnut6 13.5
END DESCRIPTION:
XS GIS Cut Line= 3
      2717601.45      6755056.56      2717238.85      6754768.22
      2715736.02      6754610.95
#Sta/Elev= 30
  4221.6  298.63  4402.9  292.77  4592.4  294.64  4671.8  292.74  4802.2  288.86
  4919.0  288.42  4959.2  287.28  4992.3  283.74  4992.7  283.24  4996.5  283.74
  5000.7  284.11  5025.3  286.26  5049.7  285.53  5087.7  289.42  5130.1  290.56
  5371.4  289.23  5377.6  290.61  5475.9  291.63  5482.0  289.73  5502.2  291.59
  5569.2  292.15  5592.6  289.86  5653.0  293.15  5723.4  293.19  5760.8  290.72
  5794.6  293.09  5844.0  290.86  5864.1  293.82  6027.9  297.61  6195.9  301.89
#Mann=10,-1,0
  4221.6    0.12       0  4402.9     0.1       0  4671.8    0.12       0
  4802.2     0.1       0  4992.3    0.07       0  4996.5     0.1       0
  5000.7    0.12       0  5025.3     0.1       0  5794.6    0.12       0
  6027.9    0.05       0
Bank Sta=4992.3,4996.5
Exp/Cntr=0.3,0.1

Type RM Length L Ch R = 1,6839,435,435,435
BEGIN DESCRIPTION:
Walnut6 13.0
END DESCRIPTION:
XS GIS Cut Line= 3
      2717562.12      6754903.64      2717126.00      6754561.00
      2716544.19      6753881.33
#Sta/Elev= 30
  4451.1  294.69  4571.9  293.08  4693.9  295.62  4764.1  295.07  4948.8  285.69
  4969.6  286.29  4991.9  282.28  4998.5  282.32  5000.2  279.98  5000.7  279.48
  5004.9  279.98  5012.9  280.26  5019.4  283.09  5027.1  283.83  5105.1  285.76
  5183.0  285.14  5190.0  282.68  5197.3  285.33  5203.9  282.62  5211.5  282.64
  5218.1  285.11  5275.2  285.66  5303.7  287.80  5332.3  287.68  5338.9  286.44
  5360.8  288.68  5445.3  289.64  5502.4  292.01  5799.9  294.97  5900.4  294.04
#Mann=5,-1,0
  4451.1     0.1       0  4693.9    0.12       0  4991.9    0.05       0
  5000.2    0.04       0  5004.9    0.05       0
Bank Sta=5000.2,5004.9
Exp/Cntr=0.3,0.1

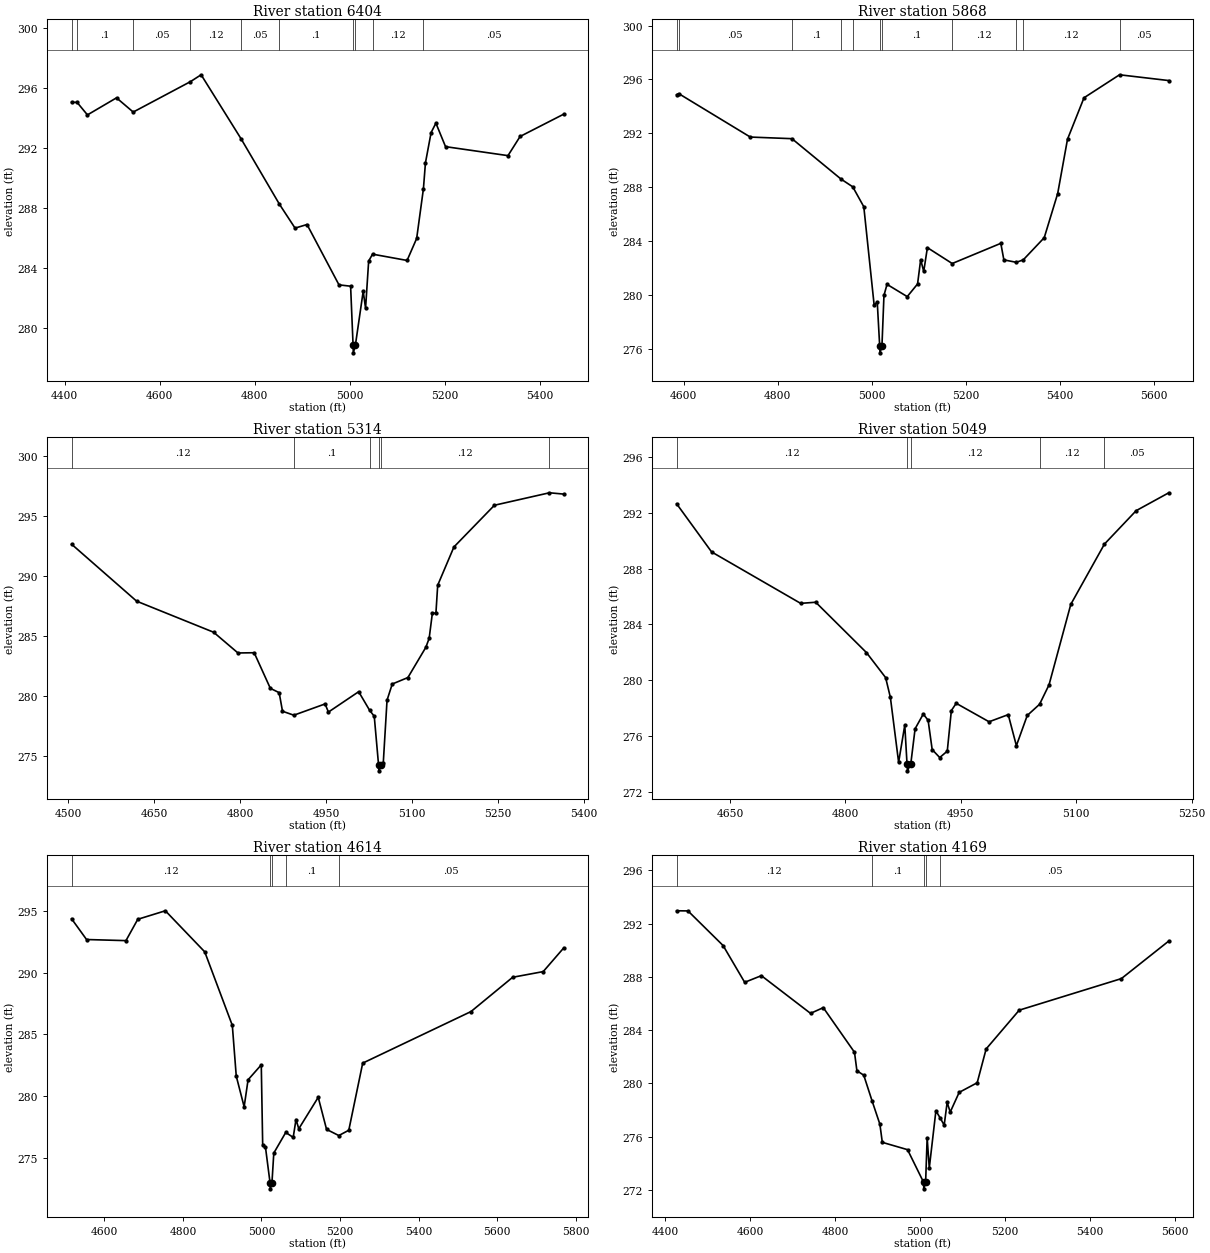
Type RM Length L Ch R = 1,6404,536,536,536
BEGIN DESCRIPTION:
Walnut6 12.0
END DESCRIPTION:
XS GIS Cut Line= 3
      2717588.36      6754873.10      2717426.00      6754311.00
      2717356.98      6753864.99
#Sta/Elev= 30
  4414.5  295.04  4426.0  295.04  4447.9  294.20  4509.1  295.34  4544.3  294.39
  4664.7  296.42  4687.3  296.88  4771.7  292.59  4852.3  288.23  4885.1  286.64
  4910.3  286.88  4977.6  282.85  5002.1  282.76  5007.3  278.81  5007.8  278.31
  5012.1  278.81  5028.6  282.42  5033.6  281.29  5040.1  284.44  5048.3  284.90
  5121.0  284.48  5141.2  285.95  5155.4  289.26  5159.7  291.00  5171.6  293.02
  5181.7  293.65  5202.0  292.08  5333.5  291.48  5359.0  292.76  5450.9  294.25
#Mann=10,-1,0
  4414.5    0.12       0  4426.0     0.1       0  4544.3    0.05       0
  4664.7    0.12       0  4771.7    0.05       0  4852.3     0.1       0
  5007.3    0.07       0  5012.1     0.1       0  5048.3    0.12       0
  5155.4    0.05       0
Bank Sta=5007.3,5012.1
Exp/Cntr=0.3,0.1

Type RM Length L Ch R = 1,5868,554,554,554
BEGIN DESCRIPTION:
Walnut6 11.0
END DESCRIPTION:
XS GIS Cut Line= 3
      2717977.17      6754807.56      2717964.06      6754449.30
      2717522.80      6753920.66
#Sta/Elev= 30
  4585.4  294.87  4589.8  294.95  4742.1  291.72  4830.7  291.60  4935.0  288.60
  4960.1  288.02  4983.6  286.54  5005.7  279.20  5012.2  279.47  5017.4  276.18
  5018.0  275.68  5022.2  276.18  5026.5  279.95  5033.0  280.77  5076.0  279.86
  5098.0  280.80  5104.6  282.61  5111.1  281.73  5118.9  283.50  5171.7  282.32
  5275.1  283.82  5281.6  282.59  5308.1  282.41  5322.8  282.59  5367.5  284.24
  5396.1  287.52  5417.0  291.56  5452.1  294.64  5527.7  296.35  5632.5  295.92
#Mann=11,-1,0
  4585.4    0.12       0  4589.8    0.05       0  4830.7     0.1       0
  4935.0    0.12       0  4960.1     0.1       0  5017.4    0.07       0
  5022.2     0.1       0  5171.7    0.12       0  5308.1     0.1       0
  5322.8    0.12       0  5527.7    0.05       0
Bank Sta=5017.4,5022.2
Exp/Cntr=0.3,0.1

Type RM Length L Ch R = 1,5314,265,265,265
BEGIN DESCRIPTION:
Walnut6 10.5
END DESCRIPTION:
XS GIS Cut Line= 4
      2718278.64      6754348.85      2718029.59      6754104.17
      2717784.73      6753960.37      2717623.32      6753802.75
#Sta/Elev= 30
  4506.2  292.65  4619.7  287.90  4754.0  285.31  4796.5  283.58  4824.8  283.60
  4853.0  280.63  4868.4  280.27  4874.2  278.72  4894.0  278.39  4948.5  279.33
  4954.3  278.65  5007.1  280.35  5026.2  278.80  5034.3  278.30  5041.8  274.25
  5042.4  273.75  5046.7  274.25  5050.0  274.38  5056.6  279.64  5065.7  280.99
  5093.0  281.53  5124.3  284.05  5130.1  284.80  5135.7  286.90  5141.9  286.90
  5145.0  289.23  5173.3  292.42  5244.0  295.90  5340.0  296.94  5364.9  296.83
#Mann=6,-1,0
  4506.2    0.12       0  4894.0     0.1       0  5026.2    0.12       0
  5041.8    0.07       0  5046.7    0.12       0  5340.0    0.05       0
Bank Sta=5041.8,5046.7
Exp/Cntr=0.3,0.1

Type RM Length L Ch R = 1,5049,435,435,435
BEGIN DESCRIPTION:
Walnut6 10.0
END DESCRIPTION:
XS GIS Cut Line= 3
      2718276.02      6754311.04      2718126.00      6753911.00
      2717975.98      6753760.98
#Sta/Elev= 30
  4580.8  292.63  4626.2  289.19  4741.9  285.51  4761.5  285.59  4827.4  281.99
  4852.3  280.20  4858.5  278.78  4869.2  274.14  4877.2  276.80  4880.1  274.03
  4880.7  273.53  4885.0  274.03  4890.6  276.54  4901.2  277.59  4907.5  277.15
  4912.8  275.05  4922.6  274.48  4932.4  274.94  4937.7  277.84  4944.0  278.36
  4986.7  277.04  5011.6  277.55  5022.2  275.33  5036.3  277.49  5052.3  278.29
  5064.6  279.68  5092.9  285.44  5136.6  289.75  5177.8  292.14  5220.2  293.42
#Mann=5,-1,0
  4580.8    0.12       0  4880.1    0.07       0  4885.0    0.12       0
  5052.3    0.12       0  5136.6    0.05       0
Bank Sta=4880.1,4885
Exp/Cntr=0.3,0.1

Type RM Length L Ch R = 1,4614,445,445,445
BEGIN DESCRIPTION:
Walnut6 9.0
END DESCRIPTION:
XS GIS Cut Line= 3
      2718512.75      6754389.00      2718476.00      6753911.00
      2717926.09      6753367.05
#Sta/Elev= 30
  4516.6  294.37  4554.7  292.69  4655.0  292.60  4685.1  294.33  4755.3  295.02
  4855.6  291.69  4925.8  285.73  4935.8  281.62  4955.9  279.13  4965.9  281.32
  4999.5  282.53  5003.1  276.03  5010.1  275.88  5021.8  272.98  5022.4  272.48
  5026.7  272.98  5031.4  275.38  5061.8  277.05  5080.8  276.65  5087.9  278.10
  5095.0  277.35  5144.5  279.90  5165.7  277.30  5196.9  276.80  5222.3  277.23
  5257.7  282.67  5533.4  286.85  5639.5  289.63  5717.3  290.09  5769.5  292.01
#Mann=5,-1,0
  4516.6    0.12       0  5021.8    0.07       0  5026.7    0.12       0
  5061.8     0.1       0  5196.9    0.05       0
Bank Sta=5021.8,5026.7
Exp/Cntr=0.3,0.1

Type RM Length L Ch R = 1,4169,396,396,396
BEGIN DESCRIPTION:
Walnut6 8.5
END DESCRIPTION:
XS GIS Cut Line= 6
      2718658.70      6753994.97      2718566.95      6753807.10
      2718560.83      6753658.46      2718486.15      6753521.92
      2718387.83      6753514.38      2718007.77      6753121.23
#Sta/Elev= 30
  4426.3  292.96  4453.0  292.95  4535.7  290.35  4586.5  287.59  4625.8  288.09
  4741.6  285.26  4771.6  285.69  4845.1  282.34  4850.8  280.95  4866.9  280.62
  4886.5  278.69  4904.9  276.94  4910.6  275.58  4970.0  275.03  5007.7  272.59
  5008.3  272.09  5012.6  272.59  5016.2  275.93  5021.2  273.65  5036.8  277.95
  5047.0  277.40  5056.3  276.87  5063.3  278.58  5070.5  277.85  5091.6  279.33
  5134.0  280.05  5155.1  282.59  5233.0  285.50  5473.6  287.87  5585.2  290.69
#Mann=5,-1,0
  4426.3    0.12       0  4886.5     0.1       0  5007.7    0.07       0
  5012.6     0.1       0  5047.0    0.05       0
Bank Sta=5007.7,5012.6
Exp/Cntr=0.3,0.1

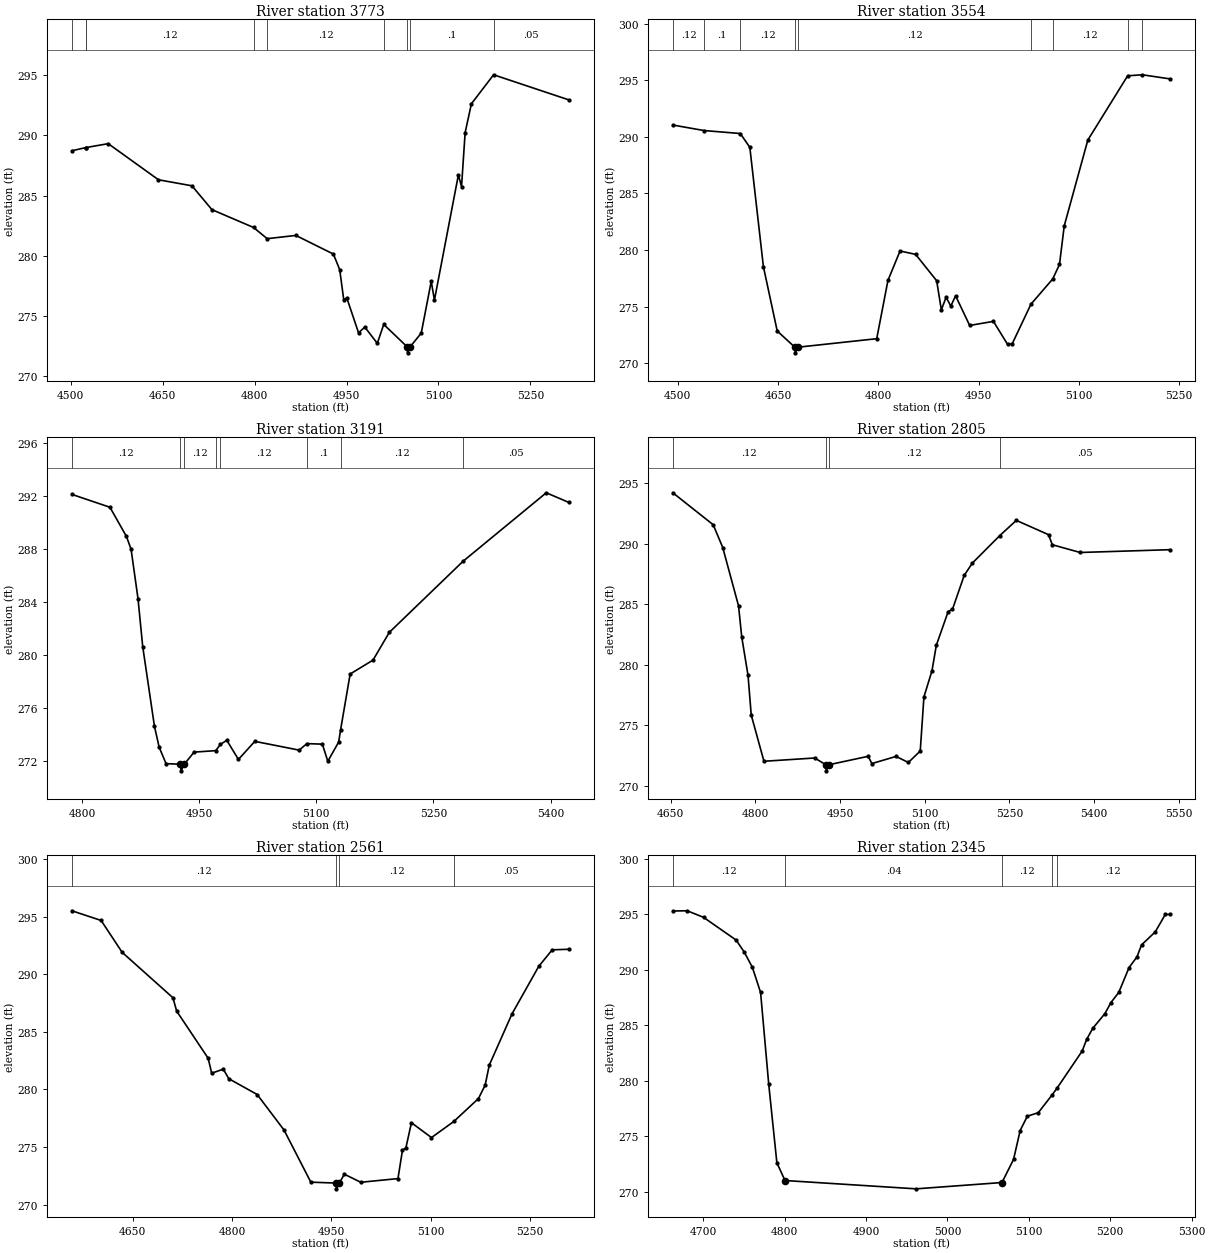
Type RM Length L Ch R = 1,3773,219,219,219
BEGIN DESCRIPTION:
Walnut6 8.0
END DESCRIPTION:
XS GIS Cut Line= 3
      2718610.63      6753850.75      2718575.69      6753623.61
      2718697.97      6753055.84
#Sta/Elev= 30
  4501.8  288.72  4525.2  288.99  4525.3  288.99  4561.2  289.31  4643.2  286.31
  4697.8  285.81  4730.4  283.83  4798.3  282.35  4820.5  281.42  4867.3  281.69
  4928.6  280.14  4938.9  278.84  4945.4  276.36  4950.5  276.49  4969.6  273.60
  4979.8  274.08  5000.2  272.73  5010.7  274.30  5048.9  272.44  5049.5  271.94
  5053.8  272.44  5071.9  273.58  5088.2  277.88  5093.4  276.32  5132.5  286.72
  5137.6  285.74  5143.5  290.23  5153.7  292.62  5189.9  295.03  5312.4  292.95
#Mann=9,-1,0
  4501.8    0.12       0  4525.2     0.1       0  4525.3    0.12       0
  4798.3     0.1       0  4820.5    0.12       0  5010.7     0.1       0
  5048.9    0.07       0  5053.8     0.1       0  5189.9    0.05       0
Bank Sta=5048.9,5053.8
Exp/Cntr=0.3,0.1

Type RM Length L Ch R = 1,3554,363,363,363
BEGIN DESCRIPTION:
Walnut6 7.5
END DESCRIPTION:
XS GIS Cut Line= 3
      2718632.48      6753911.94      2718732.96      6753536.24
      2718981.51      6753283.33
#Sta/Elev= 30
  4492.5  291.04  4539.4  290.55  4593.4  290.29  4607.7  289.07  4628.0  278.53
  4648.7  272.84  4675.0  271.41  4675.6  270.91  4680.0  271.41  4797.6  272.16
  4814.4  277.31  4832.5  279.91  4855.8  279.61  4887.3  277.28  4894.3  274.71
  4901.4  275.82  4908.5  275.04  4915.6  275.95  4936.7  273.33  4972.2  273.69
  4993.3  271.67  5000.5  271.73  5028.4  275.21  5061.0  277.44  5071.1  278.72
  5078.2  282.13  5113.5  289.71  5173.1  295.39  5195.2  295.48  5236.0  295.12
#Mann=9,-1,0
  4492.5    0.12       0  4539.4     0.1       0  4593.4    0.12       0
  4675.0    0.07       0  4680.0    0.12       0  5028.4     0.1       0
  5061.0    0.12       0  5173.1    0.05       0  5195.2     0.1       0
Bank Sta=4675,4680
Exp/Cntr=0.3,0.1

Type RM Length L Ch R = 1,3191,386,386,386
BEGIN DESCRIPTION:
Walnut6 7.0
END DESCRIPTION:
XS GIS Cut Line= 3
      2718719.88      6753951.24      2718890.24      6753702.25
      2719086.84      6753431.37
#Sta/Elev= 30
  4786.8  292.11  4835.6  291.14  4856.7  288.95  4862.7  287.98  4871.6  284.25
  4877.6  280.65  4892.6  274.66  4898.6  273.08  4907.5  271.83  4925.9  271.79
  4926.6  271.29  4930.9  271.79  4943.4  272.70  4971.1  272.81  4977.1  273.28
  4985.3  273.59  5000.2  272.15  5021.2  273.51  5078.0  272.85  5087.9  273.34
  5107.7  273.30  5114.7  272.01  5128.6  273.46  5131.1  274.39  5143.3  278.58
  5172.6  279.63  5193.5  281.72  5287.9  287.07  5394.5  292.23  5423.2  291.51
#Mann=8,-1,0
  4786.8    0.12       0  4925.9    0.07       0  4930.9    0.12       0
  4971.1     0.1       0  4977.1    0.12       0  5087.9     0.1       0
  5131.1    0.12       0  5287.9    0.05       0
Bank Sta=4925.9,4930.9
Exp/Cntr=0.3,0.1

Type RM Length L Ch R = 1,2805,244,244,244
BEGIN DESCRIPTION:
Walnut6 6.5
END DESCRIPTION:
XS GIS Cut Line= 3
      2718846.50      6754047.40      2719121.78      6753911.95
      2719558.68      6753540.59
#Sta/Elev= 30
  4653.7  294.21  4725.2  291.57  4742.1  289.69  4770.1  284.87  4775.7  282.32
  4786.9  279.13  4792.6  275.85  4815.1  272.04  4905.0  272.31  4924.9  271.75
  4925.6  271.25  4929.9  271.75  4999.7  272.45  5006.3  271.85  5049.1  272.44
  5071.0  271.94  5092.0  272.89  5098.5  277.35  5112.8  279.52  5120.5  281.62
  5141.4  284.39  5149.1  284.59  5169.9  287.39  5184.2  288.40  5232.8  290.67
  5262.2  291.93  5319.3  290.75  5325.9  289.92  5375.3  289.28  5533.9  289.51
#Mann=4,-1,0
  4653.7    0.12       0  4924.9    0.07       0  4929.9    0.12       0
  5232.8    0.05       0
Bank Sta=4924.9,4929.9
Exp/Cntr=0.3,0.1

Type RM Length L Ch R = 1,2561,216,216,216
BEGIN DESCRIPTION:
Walnut6 6.0
END DESCRIPTION:
XS GIS Cut Line= 3
      2718855.28      6754117.28      2719073.72      6754025.54
      2719580.53      6754104.18
#Sta/Elev= 30
  4558.2  295.50  4602.4  294.66  4634.2  291.89  4710.8  287.95  4716.4  286.79
  4763.9  282.70  4769.3  281.40  4786.8  281.75  4795.1  280.92  4837.9  279.55
  4878.4  276.47  4918.9  271.94  4956.8  271.86  4957.5  271.36  4961.8  271.86
  4969.5  272.63  4994.3  271.93  5050.4  272.25  5057.2  274.72  5062.3  274.90
  5070.7  277.10  5101.0  275.81  5134.7  277.21  5171.9  279.20  5182.0  280.37
  5188.2  282.10  5222.5  286.55  5262.9  290.68  5283.2  292.11  5308.0  292.16
#Mann=4,-1,0
  4558.2    0.12       0  4956.8    0.07       0  4961.8    0.12       0
  5134.7    0.05       0
Bank Sta=4956.8,4961.8
Exp/Cntr=0.3,0.1

Type RM Length L Ch R = 1,2345,368,368,368
BEGIN DESCRIPTION:
Walnut6 5.0
END DESCRIPTION:
XS GIS Cut Line= 3
      2718868.39      6754187.18      2719113.04      6754200.29
      2719440.73      6754361.95
#Sta/Elev= 30
  4662.6  295.30  4680.2  295.32  4700.3  294.73  4740.3  292.68  4750.3  291.60
  4760.3  290.22  4770.4  287.95  4780.4  279.67  4790.4  272.59  4800.4  270.99
  4961.5  270.24  5067.0  270.81  5081.2  272.90  5089.3  275.50  5098.1  276.79
  5111.6  277.11  5128.5  278.71  5134.5  279.31  5165.5  282.67  5171.0  283.72
  5178.5  284.72  5193.5  286.05  5200.8  287.04  5210.4  287.95  5223.1  290.20
  5232.8  291.16  5238.4  292.24  5255.3  293.42  5267.6  294.99  5273.0  294.99
#Mann=5,-1,0
  4662.6    0.12       0  4800.4    0.04       0  5067.0    0.12       0
  5128.5    0.05       0  5134.5    0.12       0
Bank Sta=4800.4,5067
Exp/Cntr=0.3,0.1

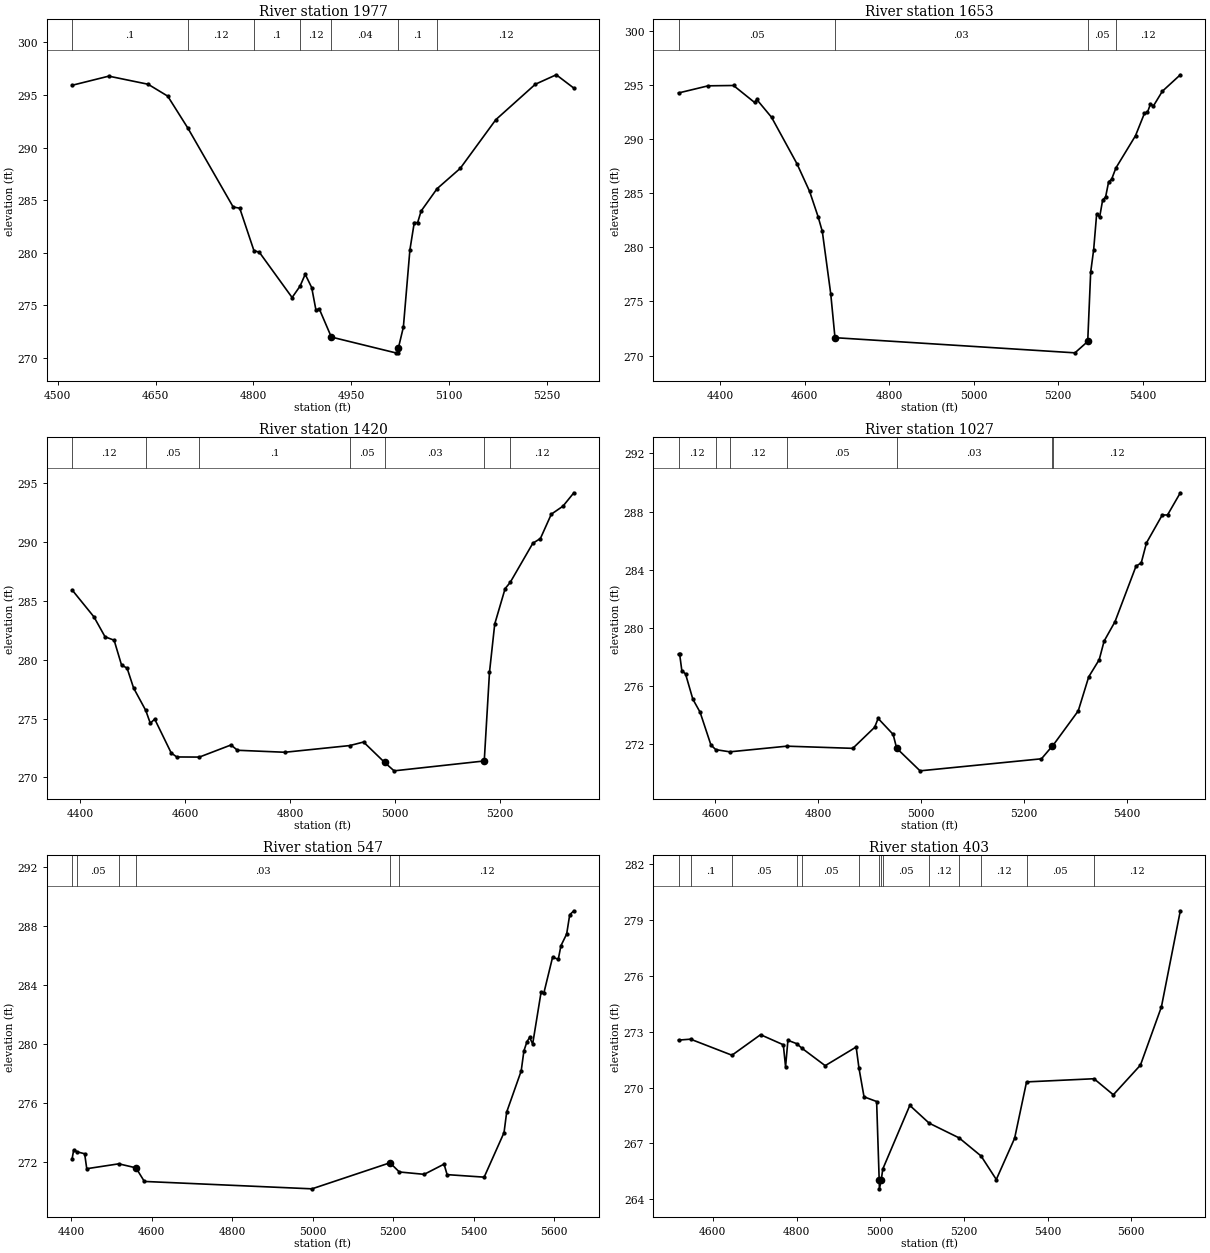
Type RM Length L Ch R = 1,1977,324,324,324
BEGIN DESCRIPTION:
Walnut6 4.0
END DESCRIPTION:
XS GIS Cut Line= 3
      2718649.92      6754501.73      2719174.20      6754549.79
      2719401.21      6754462.48
#Sta/Elev= 30
  4522.0  295.93  4578.3  296.80  4638.6  296.03  4668.7  294.90  4699.8  291.84
  4769.1  284.36  4779.2  284.24  4800.9  280.22  4809.3  280.05  4859.5  275.75
  4871.7  276.83  4879.6  277.96  4889.6  276.69  4896.1  274.55  4901.1  274.68
  4919.7  271.99  5018.3  270.49  5022.1  270.49  5022.7  270.99  5030.2  272.94
  5040.2  280.28  5046.9  282.88  5052.1  282.88  5057.4  283.97  5081.9  286.10
  5117.4  288.03  5172.0  292.66  5232.6  296.03  5264.7  296.93  5291.7  295.66
#Mann=7,-1,0
  4522.0     0.1       0  4699.8    0.12       0  4800.9     0.1       0
  4871.7    0.12       0  4919.7    0.04       0  5022.7     0.1       0
  5081.9    0.12       0
Bank Sta=4919.7,5022.7
Exp/Cntr=0.3,0.1

Type RM Length L Ch R = 1,1653,233,233,233
BEGIN DESCRIPTION:
Walnut6 3.0
END DESCRIPTION:
XS GIS Cut Line= 3
      2718365.99      6754903.65      2718999.45      6754877.44
      2719390.97      6754485.92
#Sta/Elev= 30
  4301.3  294.26  4371.4  294.92  4431.4  294.95  4481.4  293.38  4486.4  293.66
  4521.5  292.01  4581.6  287.72  4611.6  285.16  4631.6  282.83  4641.6  281.47
  4661.6  275.69  4671.6  271.65  5239.6  270.25  5269.8  271.30  5276.8  277.70
  5283.9  279.79  5291.0  283.10  5298.0  282.78  5305.1  284.36  5312.2  284.66
  5319.3  286.05  5326.3  286.28  5336.5  287.33  5382.9  290.31  5404.1  292.38
  5411.2  292.47  5418.3  293.24  5425.3  293.06  5446.5  294.42  5489.0  295.94
#Mann=4,-1,0
  4301.3    0.05       0  4671.6    0.03       0  5269.8    0.05       0
  5336.5    0.12       0
Bank Sta=4671.6,5269.8
Exp/Cntr=0.3,0.1

Type RM Length L Ch R = 1,1420,393,393,393
BEGIN DESCRIPTION:
Walnut6 2.0
END DESCRIPTION:
XS GIS Cut Line= 4
      2719145.53      6755410.73      2719246.23      6755103.43
      2719263.59      6754596.48      2719361.10      6754516.08
#Sta/Elev= 30
  4384.0  285.94  4425.8  283.64  4446.9  281.95  4464.2  281.66  4478.4  279.54
  4488.9  279.29  4501.3  277.60  4524.5  275.69  4533.2  274.60  4541.6  274.95
  4573.1  272.07  4583.7  271.73  4626.8  271.72  4687.1  272.75  4699.4  272.30
  4789.9  272.13  4913.7  272.70  4939.9  273.00  4980.0  271.27  4998.1  270.55
  5170.1  271.39  5180.1  278.94  5190.1  283.04  5209.9  286.05  5219.5  286.57
  5262.8  289.91  5277.2  290.31  5298.0  292.38  5320.2  293.06  5341.0  294.20
#Mann=7,-1,0
  4384.0    0.12       0  4524.5    0.05       0  4626.8     0.1       0
  4913.7    0.05       0  4980.0    0.03       0  5170.1    0.05       0
  5219.5    0.12       0
Bank Sta=4980,5170.1
Exp/Cntr=0.3,0.1

Type RM Length L Ch R = 1,1027,480,480,480
BEGIN DESCRIPTION:
Walnut6 1.6
END DESCRIPTION:
XS GIS Cut Line= 5
      2719214.99      6755329.11      2719499.70      6755056.55
      2719553.52      6755027.04      2719562.20      6754954.12
      2719471.92      6754516.60
#Sta/Elev= 30
  4528.5  278.16  4530.7  278.16  4534.9  277.04  4542.1  276.81  4556.3  275.07
  4570.4  274.17  4591.5  271.91  4600.9  271.59  4628.3  271.44  4739.1  271.83
  4867.3  271.68  4909.8  273.13  4916.6  273.74  4945.8  272.64  4952.6  271.69
  4998.1  270.13  5234.2  270.96  5254.6  271.81  5257.0  271.90  5305.7  274.26
  5326.1  276.61  5346.5  277.79  5356.0  279.07  5377.2  280.41  5418.0  284.23
  5428.2  284.46  5438.4  285.84  5469.1  287.76  5479.3  287.76  5504.2  289.29
#Mann=7,-1,0
  4528.5    0.12       0  4600.9    0.05       0  4628.3    0.12       0
  4739.1    0.05       0  4952.6    0.03       0  5254.6    0.05       0
  5257.0    0.12       0
Bank Sta=4952.6,5254.6
Exp/Cntr=0.3,0.1

Type RM Length L Ch R = 1,547,144,144,144
BEGIN DESCRIPTION:
Walnut6 1.4
END DESCRIPTION:
XS GIS Cut Line= 5
      2720251.44      6755412.46      2720143.80      6755070.44
      2719899.01      6754928.08      2719758.38      6754775.30
      2719497.44      6754474.62
#Sta/Elev= 30
  4401.7  272.24  4405.8  272.85  4414.3  272.72  4433.0  272.59  4438.2  271.58
  4517.8  271.91  4560.5  271.64  4581.4  270.72  4998.1  270.22  5192.0  271.98
  5215.3  271.36  5277.1  271.20  5326.5  271.89  5334.1  271.18  5426.2  271.01
  5475.6  274.02  5482.2  275.41  5518.3  278.19  5525.0  279.54  5532.6  280.16
  5539.2  280.45  5546.8  280.01  5567.7  283.51  5574.5  283.44  5596.2  285.86
  5610.5  285.74  5617.1  286.65  5631.3  287.44  5638.9  288.74  5649.2  289.01
#Mann=6,-1,0
  4401.7    0.12       0  4414.3    0.05       0  4517.8     0.1       0
  4560.5    0.03       0  5192.0    0.05       0  5215.3    0.12       0
Bank Sta=4560.5,5192
Exp/Cntr=0.3,0.1

Type RM Length L Ch R = 1,403,365,365,365
BEGIN DESCRIPTION:
Walnut6 1.2
END DESCRIPTION:
XS GIS Cut Line= 6
      2720246.22      6755330.81      2720229.72      6755198.54
      2720168.10      6755056.55      2720062.89      6754969.80
      2720070.89      6754856.90      2719677.56      6754324.96
#Sta/Elev= 30
  4518.0  272.54  4546.7  272.59  4645.7  271.73  4714.0  272.83  4768.4  272.29
  4773.8  271.11  4779.4  272.53  4800.3  272.35  4812.6  272.11  4868.5  271.17
  4942.5  272.17  4949.2  271.04  4961.3  269.50  4991.4  269.25  4997.5  265.07
  4998.1  264.57  5002.6  265.07  5006.1  265.63  5070.7  269.04  5116.9  268.09
  5188.5  267.30  5241.0  266.33  5277.4  265.07  5321.2  267.28  5349.7  270.30
  5510.9  270.47  5557.1  269.61  5621.9  271.20  5672.0  274.32  5717.2  279.47
#Mann=14,-1,0
  4518.0    0.05       0  4546.7     0.1       0  4645.7    0.05       0
  4800.3    0.12       0  4812.6    0.05       0  4949.2    0.12       0
  4997.5    0.07       0  5002.6    0.12       0  5006.1    0.05       0
  5116.9    0.12       0  5188.5    0.05       0  5241.0    0.12       0
  5349.7    0.05       0  5510.9    0.12       0
Bank Sta=4997.5,5002.6
Exp/Cntr=0.3,0.1

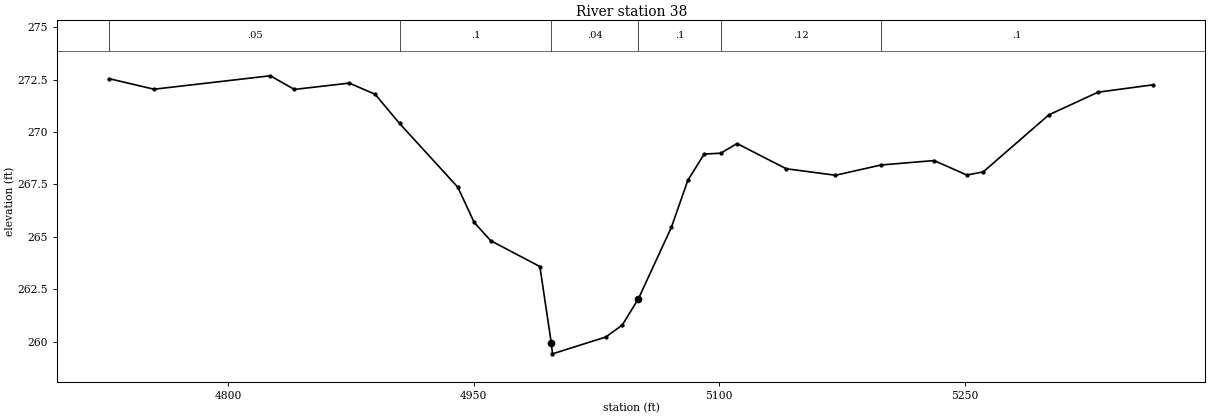
Type RM Length L Ch R = 1,38,0,0,0
BEGIN DESCRIPTION:
Walnut6 1.0
END DESCRIPTION:
XS GIS Cut Line= 3
      2720242.75      6755355.18      2720329.56      6755237.11
      2720364.29      6754747.49
#Sta/Elev= 30
  4727.5  272.54  4754.8  272.04  4825.8  272.68  4840.5  272.03  4874.0  272.33
  4889.8  271.80  4904.7  270.41  4940.3  267.37  4950.3  265.69  4960.4  264.82
  4990.4  263.59  4997.4  259.93  4998.1  259.43  5030.6  260.23  5040.7  260.80
  5050.6  262.06  5070.7  265.46  5080.7  267.69  5090.7  268.95  5100.8  268.99
  5110.8  269.45  5140.8  268.25  5170.9  267.94  5198.8  268.43  5231.1  268.64
  5251.1  267.95  5261.1  268.10  5301.2  270.82  5331.3  271.90  5364.9  272.25
#Mann=6,-1,0
  4727.5    0.05       0  4904.7     0.1       0  4997.4    0.04       0
  5050.6     0.1       0  5100.8    0.12       0  5198.8     0.1       0
Bank Sta=4997.4,5050.6
Exp/Cntr=0.3,0.1

Chan Stop Cuts=-1