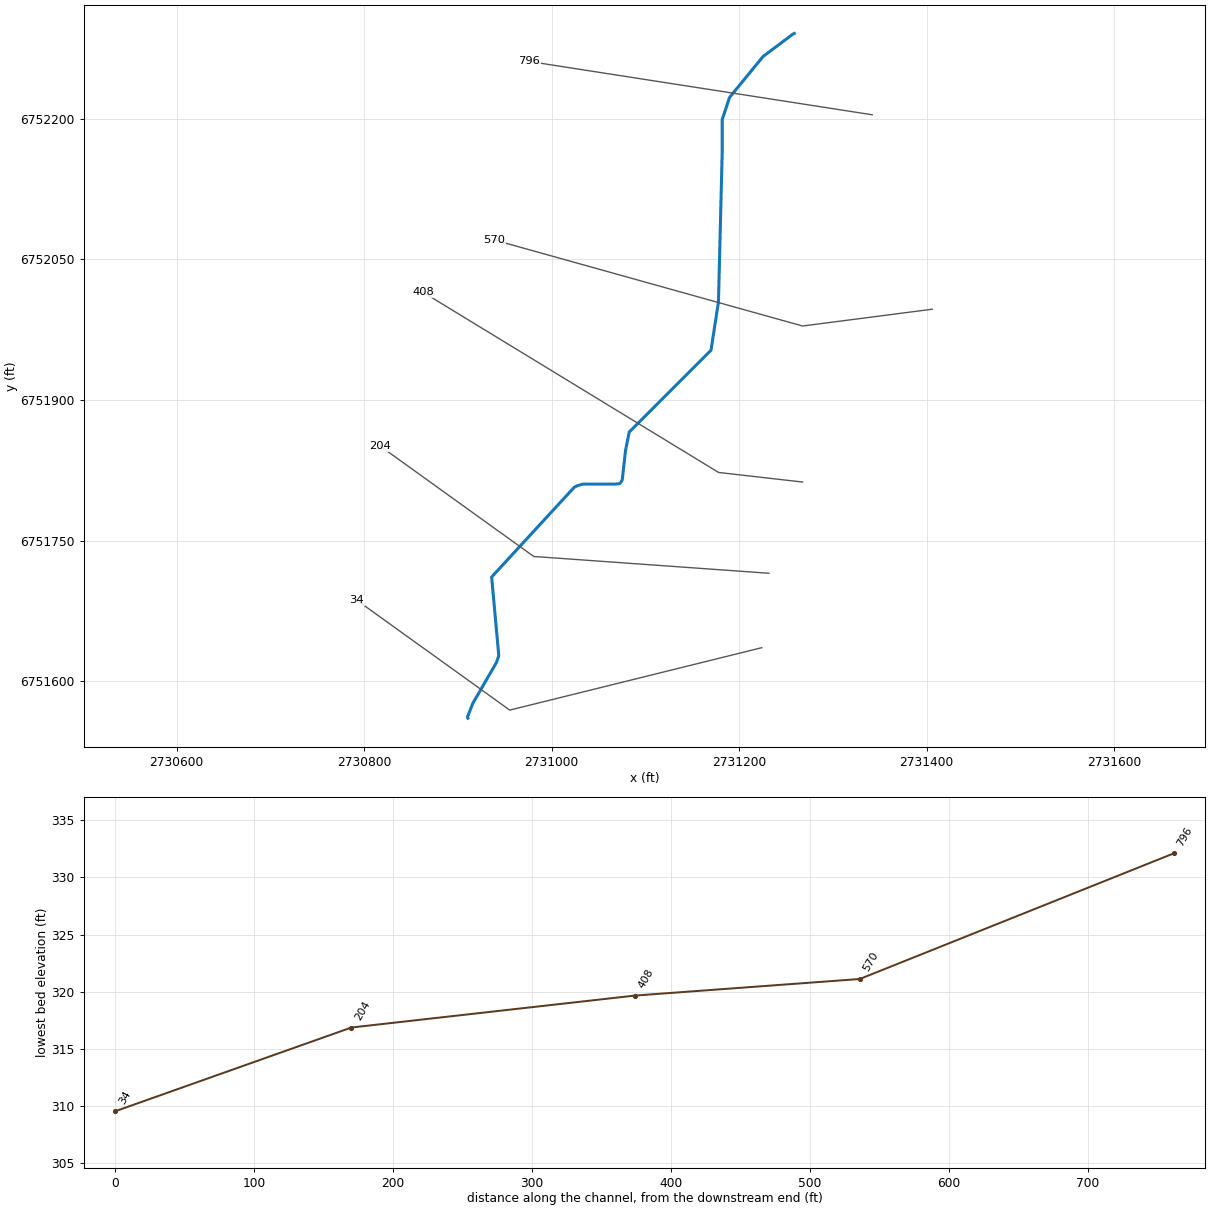
--- Walnut60.prj (project) ---

Proj Title=Walnut60 Base Level Engineering
Current Plan=p01
Default Exp/Contr=0.3,0.1
English Units
Geom File=g01
Flow File=f01
Plan File=p01
Y Axis Title=Elevation
X Axis Title(PF)=Main Channel Distance
X Axis Title(XS)=Station
BEGIN DESCRIPTION:
Walnut60
END DESCRIPTION:
DSS Export Rating Curves= 0
DSS Export Rating Curve Sorted= 0
DSS Export Volume Flow Curves= 0
DXF OffsetX= 0
DXF OffsetY= 0
DXF ScaleX= 1
DXF ScaleY= 10

--- Walnut60.p01 (plan) ---

Plan Title=Multiple Run
Program Version=4.10
Short Identifier=Multiple
Geom File=g01
Flow File=f01
Subcritical Flow
K Sum by GR= 0
Std Step Tol= 0.01
Critical Tol= 0.01
Num of Std Step Trials= 20
Max Error Tol= 0.3
Flow Tol Ratio= 0.001
Split Flow NTrial= 30
Split Flow Tol= 0.02
Split Flow Ratio= 0.02
Log Output Level= 0
Friction Slope Method= 1
Unsteady Friction Slope Method= 2
Unsteady Bridges Friction Slope Method= 1
Parabolic Critical Depth
Global Vel Dist= 1 , 1 , 1
Global Log Level= 0
CheckData=True
Encroach Param=-1 ,0,0, 0
BEGIN DESCRIPTION:
Multiple Run
END DESCRIPTION:
Computation Interval=1HOUR
Output Interval=1HOUR
Run HTab= 0
Run UNet= 0
Run PostProcess= 0
Run WQNet= 0
UNET Theta= 1
UNET Theta Warmup= 1
UNET ZTol= 0.02
UNET ZSATol= 0.05
UNET MxIter= 20
UNET MaxInSteps= 0
UNET DtIC= 0
UNET DtMin= 0
UNET MaxCRTS= 20
UNET WFStab= 2
UNET SFStab= 1
UNET WFX= 1
UNET SFX= 1
UNET DSS MLevel= 4
UNET DZMax Abort= 100
UNET Convert EG Bridges= 0
UNET Use Existing IB Tables=-1
UNET Froude Reduction=False
UNET Froude Limit= 1
UNET Froude Power= 10
UNET Time Slicing=0,0, 5
UNET Junction Losses=0
Instantaneous Interval=1HOUR
Write IC File= 0
Write IC File at Sim End=0
Echo Input=False
Echo Parameters=False
Echo Output=False
Write Detailed= 0
WQ AD Non Conservative
WQ ULTIMATE=-1
WQ Max Comp Step=1HOUR
WQ Output Interval=15MIN
WQ Output Selected Increments= 0
WQ Output face flow=0
WQ Output face velocity=0
WQ Output face area=0
WQ Output face dispersion=0
WQ Output cell volume=0
WQ Output cell surface area=0
WQ Output cell continuity=0
WQ Output cumulative cell continuity=0
WQ Output face conc=0
WQ Output face dconc_dx=0
WQ Output face courant=0
WQ Output face peclet=0
WQ Output face adv mass=0
WQ Output face disp mass=0
WQ Output cell mass=0
WQ Output cell source sink temp=0
WQ Output cell source sink nsm=0
WQ Output MaxMinRange=-1
WQ Daily Max Min Mean=-1
WQ Daily Range=0
WQ Daily Time=0
WQ Create Restart=0
WQ Fixed Restart=0
WQ System Summary=0
WQ Use Fixed Temperature=0
Sorting and Armoring Iterations= 10
XS Update Threshold= 0.02
Hydraulics Update Threshold= 0.02
Energy Slope Method= 1
Volume Change Method= 0
XS Weighting Method= 0
Number of US Weighted Cross Sections= 1
Number of DS Weighted Cross Sections= 1
Upstream XS Weight=0.25
Main XS Weight=0.5
Downstream XS Weight=0.25
Number of DS XS's Weighted with US Boundary= 1
Upstream Boundary Weight= 1
Weight of XSs Associated with US Boundary= 0
Number of US XS's Weighted with DS Boundary= 1
Downstream Boundary Weight= 0.5
Weight of XSs Associated with DS Boundary= 0.5
Sediment Output Level= 4
Mass or Volume Output= 0
Output Increment Type= 1
Profile and TS Output Increment= 10
XS Output Flag= 0
XS Output Increment= 10
Disregard all LS=0
Disregard all Conn=0
Disregard all Breaches=0
Disregard all Pumps=0

--- Walnut60.f01 (steady flow) ---

Flow Title=Multiple
Program Version=4.10
Number of Profiles= 7
Profile Names=10-year,25-year,50-year,1pct_min,100-year,1pct_plu,500-year
River Rch & RM=Walnut60,Reach-1         ,796
      67      78      85      47      93     186     111
River Rch & RM=Walnut60,Reach-1         ,34
     614     806     957     562    1122    2239    1547
Boundary for River Rch & Prof#=Walnut60,Reach-1         , 1
Up Type= 0
Dn Type= 3
Dn Slope=0.04
Boundary for River Rch & Prof#=Walnut60,Reach-1         , 2
Up Type= 0
Dn Type= 3
Dn Slope=0.04
Boundary for River Rch & Prof#=Walnut60,Reach-1         , 3
Up Type= 0
Dn Type= 3
Dn Slope=0.04
Boundary for River Rch & Prof#=Walnut60,Reach-1         , 4
Up Type= 0
Dn Type= 3
Dn Slope=0.04
Boundary for River Rch & Prof#=Walnut60,Reach-1         , 5
Up Type= 0
Dn Type= 3
Dn Slope=0.04
Boundary for River Rch & Prof#=Walnut60,Reach-1         , 6
Up Type= 0
Dn Type= 3
Dn Slope=0.04
Boundary for River Rch & Prof#=Walnut60,Reach-1         , 7
Up Type= 0
Dn Type= 3
Dn Slope=0.04
DSS Import GetInterval= 0
DSS Import GetPeak= 0
DSS Import FillOption= 0

--- Walnut60.g01 (geometry) ---

Geom Title=Existing Conditions

River Reach=Walnut60,Reach-1
Reach XY= 23
      2731258.81      6752290.80      2731257.30      6752290.10
      2731225.58      6752266.31      2731189.88      6752222.68
      2731181.95      6752198.88      2731181.95      6752163.19
      2731177.98      6752004.55      2731170.05      6751952.99
      2731082.80      6751865.73      2731078.83      6751845.90
      2731075.36      6751814.67      2731073.77      6751811.95
      2731072.68      6751810.65      2731068.03      6751810.21
      2731033.26      6751810.21      2731026.90      6751808.26
      2731024.10      6751806.76      2730936.05      6751711.06
      2730943.67      6751627.25      2730941.29      6751620.12
      2730915.93      6751576.24      2730910.20      6751561.52
      2730910.80      6751560.50

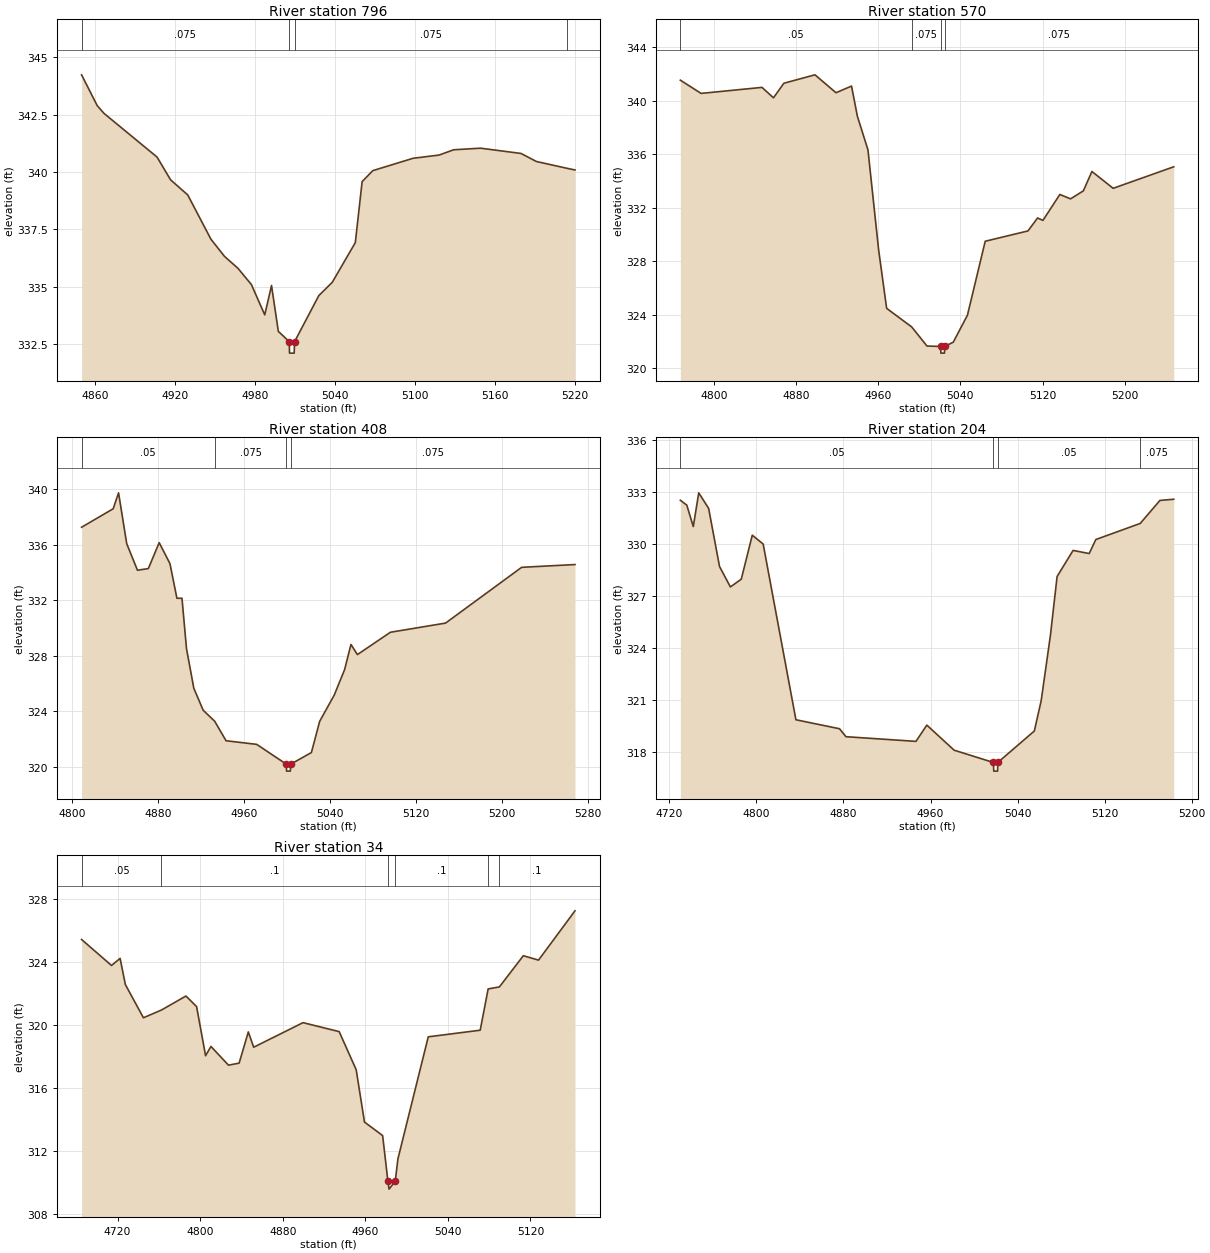
Type RM Length L Ch R = 1,796,226,226,226
BEGIN DESCRIPTION:
Walnut60 3.0
END DESCRIPTION:
XS GIS Cut Line= 2
      2731341.98      6752204.11      2730975.98      6752261.00
#Sta/Elev= 30
  4849.8  344.24  4861.5  342.90  4866.6  342.56  4906.5  340.65  4916.6  339.66
  4929.5  339.00  4946.9  337.07  4957.1  336.32  4967.2  335.80  4977.3  335.09
  4987.3  333.77  4992.4  335.05  4997.5  333.05  5005.7  332.60  5005.9  332.10
  5009.4  332.10  5009.7  332.60  5027.9  334.61  5038.0  335.19  5055.3  336.92
  5060.4  339.58  5068.4  340.06  5098.7  340.60  5118.2  340.74  5129.1  340.97
  5149.3  341.04  5179.7  340.81  5191.2  340.46  5214.4  340.16  5220.2  340.09
#Mann=4,-1,0
  4849.8   0.075       0  5005.7    0.07       0  5009.7   0.075       0
  5214.4    0.05       0
Bank Sta=5005.7,5009.7
Exp/Cntr=0.3,0.1

Type RM Length L Ch R = 1,570,162,162,162
BEGIN DESCRIPTION:
Walnut60 2.5
END DESCRIPTION:
XS GIS Cut Line= 3
      2731405.99      6751996.73      2731267.71      6751978.81
      2730939.20      6752070.48
#Sta/Elev= 30
  4767.3  341.54  4787.5  340.55  4846.8  341.00  4858.0  340.22  4868.1  341.31
  4898.4  341.94  4918.9  340.60  4934.0  341.10  4939.7  338.84  4950.0  336.33
  4960.4  328.84  4968.2  324.47  4992.6  323.08  5007.5  321.65  5020.7  321.62
  5021.0  321.12  5024.5  321.12  5024.7  321.62  5033.1  321.94  5046.9  323.96
  5064.2  329.49  5105.8  330.26  5115.2  331.23  5120.4  331.05  5136.9  332.99
  5147.3  332.66  5159.8  333.26  5168.1  334.71  5188.8  333.45  5247.8  335.06
#Mann=4,-1,0
  4767.3    0.05       0  4992.6   0.075       0  5020.7    0.07       0
  5024.7   0.075       0
Bank Sta=5020.7,5024.7
Exp/Cntr=0.3,0.1

Type RM Length L Ch R = 1,408,204,204,204
BEGIN DESCRIPTION:
Walnut60 2.0
END DESCRIPTION:
XS GIS Cut Line= 3
      2731267.71      6751812.39      2731178.10      6751822.63
      2730863.21      6752014.63
#Sta/Elev= 30
  4809.1  337.25  4838.5  338.58  4843.5  339.73  4851.1  336.06  4861.1  334.15
  4871.2  334.27  4881.3  336.14  4891.3  334.63  4897.8  332.13  4902.5  332.13
  4906.7  328.50  4913.5  325.65  4922.2  324.06  4932.9  323.27  4943.5  321.86
  4972.0  321.60  4999.6  320.17  4999.8  319.67  5003.3  319.67  5003.6  320.17
  5022.9  321.01  5030.6  323.26  5044.2  325.16  5053.8  326.99  5059.7  328.80
  5065.7  328.07  5096.4  329.68  5147.7  330.34  5218.5  334.36  5268.1  334.56
#Mann=4,-1,0
  4809.1    0.05       0  4932.9   0.075       0  4999.6    0.07       0
  5003.6   0.075       0
Bank Sta=4999.6,5003.6
Exp/Cntr=0.3,0.1

Type RM Length L Ch R = 1,204,170,170,170
BEGIN DESCRIPTION:
Walnut60 1.5
END DESCRIPTION:
XS GIS Cut Line= 3
      2731231.90      6751715.09      2730980.95      6751733.01
      2730817.08      6751850.80
#Sta/Elev= 30
  4730.1  332.54  4736.0  332.26  4742.0  331.02  4747.0  332.97  4756.1  332.07
  4766.1  328.71  4776.1  327.53  4786.1  327.98  4796.2  330.52  4806.2  330.01
  4836.3  319.85  4876.4  319.33  4882.3  318.87  4946.6  318.60  4956.6  319.54
  4981.7  318.09  5017.8  317.38  5018.1  316.88  5021.6  316.88  5021.8  317.38
  5055.4  319.20  5061.7  320.96  5070.2  324.74  5076.3  328.13  5091.0  329.64
  5105.8  329.46  5111.9  330.27  5152.7  331.20  5170.8  332.53  5183.5  332.60
#Mann=4,-1,0
  4730.1    0.05       0  5017.8    0.05       0  5021.8    0.05       0
  5152.7   0.075       0
Bank Sta=5017.8,5021.8
Exp/Cntr=0.3,0.1

Type RM Length L Ch R = 1,34,0,0,0
BEGIN DESCRIPTION:
Walnut60 1.0
END DESCRIPTION:
XS GIS Cut Line= 3
      2731224.17      6751635.72      2730955.35      6751569.15
      2730792.16      6751686.44
#Sta/Elev= 30
  4685.2  325.41  4714.2  323.76  4722.5  324.21  4727.6  322.55  4745.1  320.44
  4762.5  320.93  4786.3  321.82  4796.6  321.15  4805.3  318.03  4810.5  318.62
  4827.5  317.43  4837.8  317.56  4846.7  319.54  4851.9  318.57  4899.7  320.13
  4934.7  319.56  4951.2  317.14  4959.2  313.82  4976.8  312.96  4981.9  310.06
  4983.0  309.56  4989.0  310.06  4991.6  311.48  5021.0  319.23  5071.3  319.65
  5079.0  322.27  5089.9  322.40  5113.1  324.38  5127.8  324.10  5163.1  327.23
#Mann=6,-1,0
  4685.2    0.05       0  4762.5     0.1       0  4981.9    0.07       0
  4989.0     0.1       0  5079.0    0.05       0  5089.9     0.1       0
Bank Sta=4981.9,4989
Exp/Cntr=0.3,0.1

Chan Stop Cuts=-1