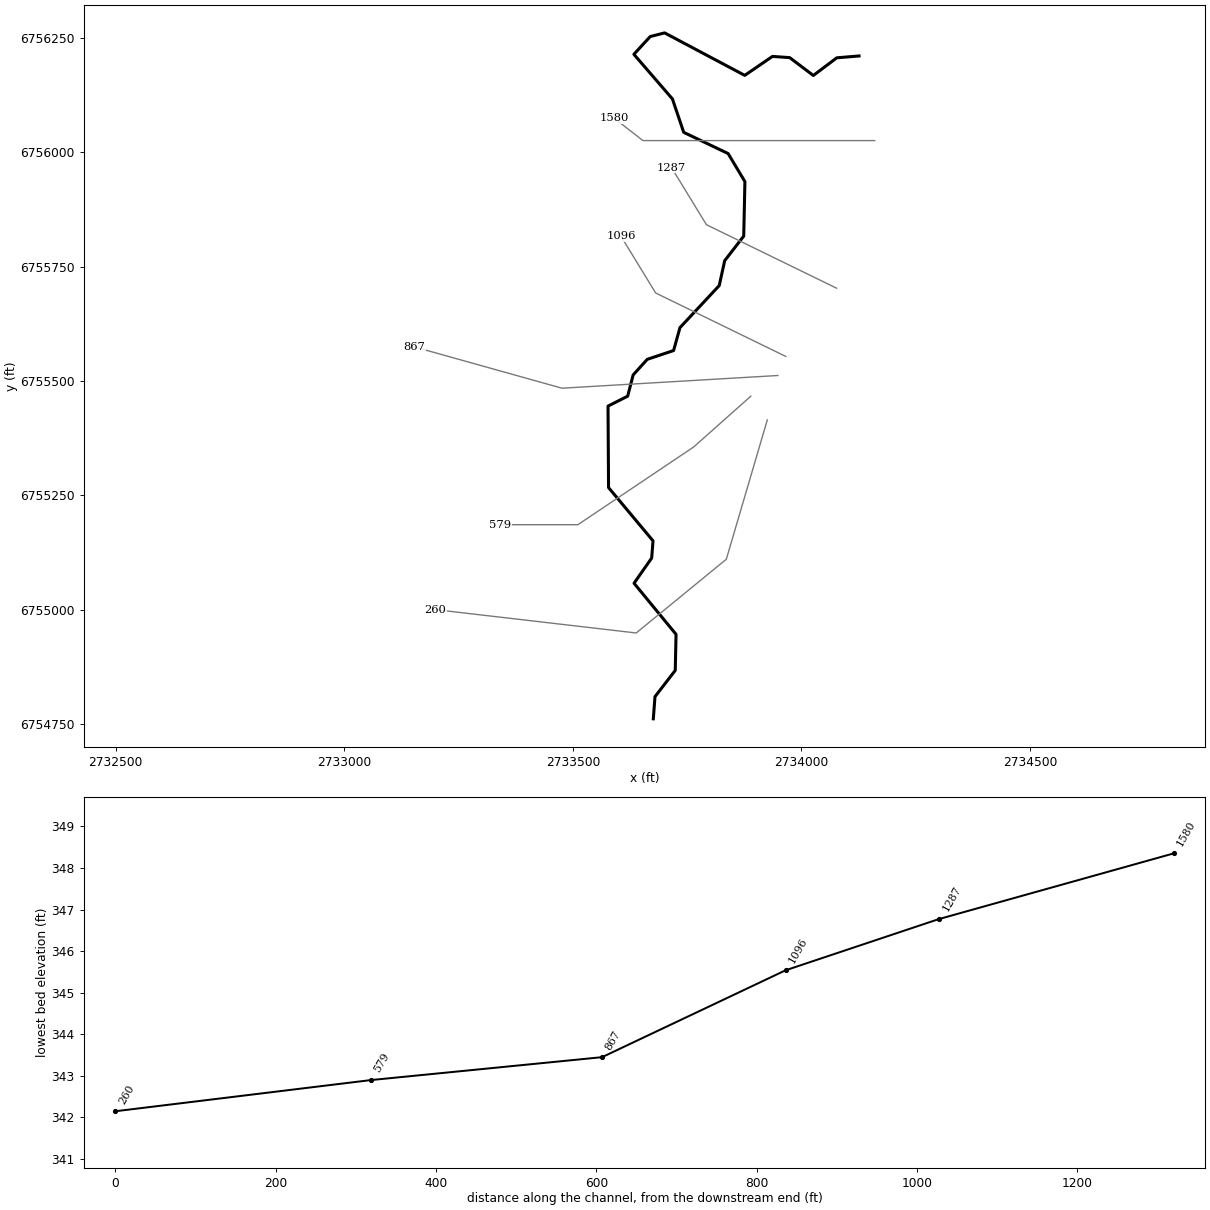
--- Walnut63.prj (project) ---

Proj Title=Walnut63 Base Level Engineering
Current Plan=p01
Default Exp/Contr=0.3,0.1
English Units
Geom File=g01
Flow File=f01
Plan File=p01
BEGIN DESCRIPTION:
Walnut63
END DESCRIPTION:

--- Walnut63.p01 (plan) ---

Plan Title=Multiple Run
Short Identifier=Multiple
Geom File=g01
Flow File=f01
Subcritical Flow
K Sum by GR= 0
Std Step Tol= 0.01
Critical Tol= 0.01
Num of Std Step Trials= 20
Max Error Tol= 0.3
Flow Tol Ratio= 0.001
Split Flow NTrial= 30
Split Flow Tol= 0.02
Split Flow Ratio= 0.02
Log Output Level= 0
Friction Slope Method= 1
Unsteady Friction Slope Method= 2
Unsteady Bridges Friction Slope Method= 1
Parabolic Critical Depth
Global Vel Dist=  1 , 1 , 1
Global Log Level= 0
CheckData=True
Encroach Param= -1, 0, 0, 0
BEGIN DESCRIPTION:
Multiple Run
END DESCRIPTION:

--- Walnut63.f01 (steady flow) ---

Flow Title=Multiple
Number of Profiles=7
Profile Names=10-year,25-year,50-year,1pct_min,100-year,1pct_plu,500-year
River Rch & RM= Walnut63,Reach-1,1580
     129     156     175      98     196     392     246
Boundary for River Rch & Prof#=Walnut63,Reach-1,1
Up Type=0
Dn Type=3
Dn Slope=0.005
Boundary for River Rch & Prof#=Walnut63,Reach-1,2
Up Type=0
Dn Type=3
Dn Slope=0.005
Boundary for River Rch & Prof#=Walnut63,Reach-1,3
Up Type=0
Dn Type=3
Dn Slope=0.005
Boundary for River Rch & Prof#=Walnut63,Reach-1,4
Up Type=0
Dn Type=3
Dn Slope=0.005
Boundary for River Rch & Prof#=Walnut63,Reach-1,5
Up Type=0
Dn Type=3
Dn Slope=0.005
Boundary for River Rch & Prof#=Walnut63,Reach-1,6
Up Type=0
Dn Type=3
Dn Slope=0.005
Boundary for River Rch & Prof#=Walnut63,Reach-1,7
Up Type=0
Dn Type=3
Dn Slope=0.005

--- Walnut63.g01 (geometry) ---

Geom Title=Existing Conditions

River Reach=Walnut63,Reach-1
Reach XY= 30
      2734126.00      6756211.00      2734077.36      6756207.00
      2734026.03      6756168.35      2733974.35      6756207.38
      2733936.64      6756210.02      2733876.00      6756168.56
      2733700.78      6756261.51      2733669.28      6756253.52
      2733633.49      6756214.66      2733717.79      6756117.03
      2733742.50      6756043.95      2733839.62      6755997.54
      2733876.36      6755936.20      2733873.77      6755816.93
      2733832.14      6755763.17      2733820.16      6755708.71
      2733734.30      6755616.74      2733720.35      6755566.63
      2733662.69      6755547.36      2733631.86      6755513.22
      2733619.93      6755466.83      2733576.91      6755445.06
      2733578.07      6755266.86      2733675.35      6755150.36
      2733672.41      6755112.65      2733633.84      6755057.60
      2733725.75      6754945.79      2733723.98      6754866.92
      2733679.65      6754809.49      2733676.00      6754761.00

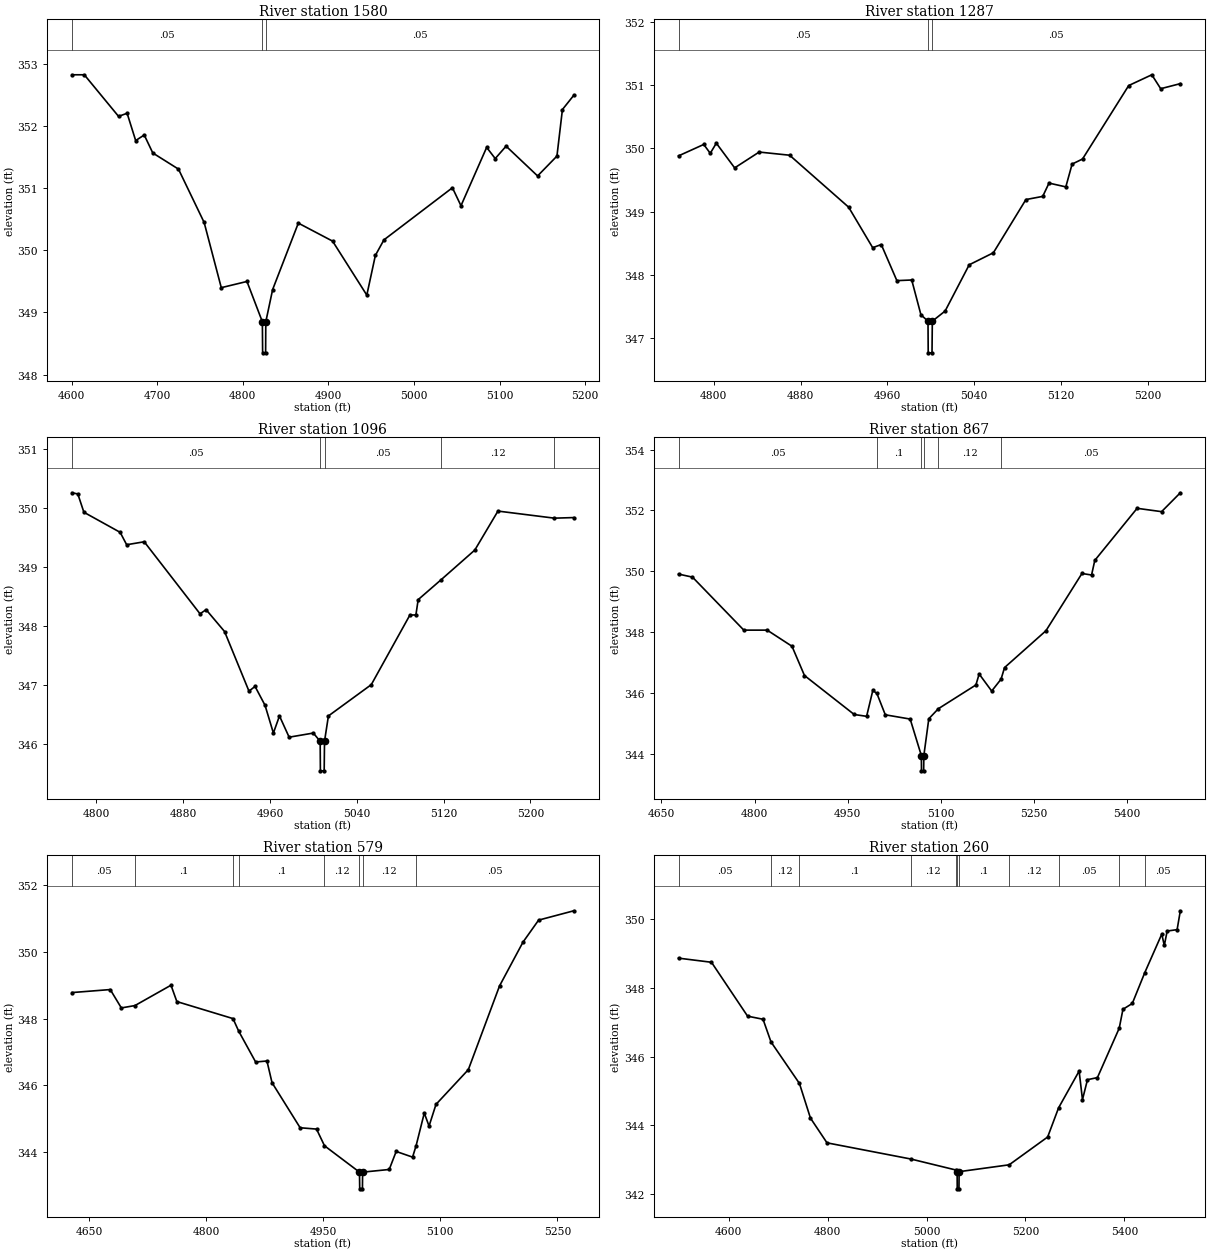
Type RM Length L Ch R = 1,1580,293,293,293
BEGIN DESCRIPTION:
Walnut63 2.0
END DESCRIPTION:
XS GIS Cut Line= 3
      2734160.30      6756025.91      2733653.31      6756025.91
      2733590.87      6756074.48
#Sta/Elev= 30
  4600.5  352.83  4614.8  352.83  4654.8  352.16  4664.8  352.21  4674.8  351.77
  4684.8  351.86  4694.8  351.57  4724.8  351.31  4754.8  350.45  4774.8  349.40
  4804.8  349.50  4822.8  348.85  4823.1  348.35  4826.6  348.35  4826.8  348.85
  4834.8  349.37  4864.8  350.44  4904.8  350.15  4944.8  349.28  4954.8  349.92
  4964.8  350.17  5044.8  351.01  5054.8  350.72  5084.8  351.66  5094.8  351.48
  5107.5  351.68  5144.3  351.20  5166.9  351.52  5173.3  352.27  5186.6  352.50
#Mann=3,-1,0
  4600.5    0.05       0  4822.8    0.04       0  4826.8    0.05       0
Bank Sta=4822.8,4826.8
Exp/Cntr=0.3,0.1

Type RM Length L Ch R = 1,1287,191,191,191
BEGIN DESCRIPTION:
Walnut63 1.8
END DESCRIPTION:
XS GIS Cut Line= 3
      2734076.89      6755703.01      2733792.20      6755841.89
      2733716.10      6755966.42
#Sta/Elev= 30
  4767.5  349.88  4790.7  350.06  4796.7  349.92  4802.3  350.08  4819.2  349.69
  4841.8  349.94  4869.9  349.89  4924.3  349.07  4946.5  348.43  4954.4  348.48
  4968.8  347.91  4982.5  347.92  4991.0  347.37  4997.5  347.27  4997.7  346.77
  5001.2  346.77  5001.5  347.27  5013.3  347.43  5035.5  348.16  5057.8  348.35
  5087.8  349.19  5103.3  349.24  5109.1  349.45  5124.6  349.39  5130.4  349.75
  5140.0  349.83  5182.6  350.99  5203.9  351.16  5212.1  350.94  5230.2  351.02
#Mann=3,-1,0
  4767.5    0.05       0  4997.5    0.04       0  5001.5    0.05       0
Bank Sta=4997.5,5001.5
Exp/Cntr=0.3,0.1

Type RM Length L Ch R = 1,1096,229,229,229
BEGIN DESCRIPTION:
Walnut63 1.6
END DESCRIPTION:
XS GIS Cut Line= 3
      2733965.79      6755553.70      2733681.09      6755692.58
      2733605.20      6755816.77
#Sta/Elev= 30
  4777.7  350.25  4783.0  350.23  4788.6  349.92  4822.0  349.58  4828.0  349.37
  4844.2  349.42  4895.6  348.20  4901.2  348.27  4918.2  347.90  4940.7  346.89
  4946.3  346.97  4955.5  346.65  4963.2  346.18  4968.8  346.47  4977.7  346.11
  5000.0  346.18  5006.3  346.04  5006.5  345.54  5010.0  345.54  5010.3  346.04
  5013.9  346.47  5053.4  347.00  5089.0  348.18  5094.5  348.18  5096.6  348.44
  5117.3  348.77  5148.8  349.28  5170.1  349.94  5222.1  349.82  5240.0  349.83
#Mann=5,-1,0
  4777.7    0.05       0  5006.3    0.04       0  5010.3    0.05       0
  5117.3    0.12       0  5222.1    0.05       0
Bank Sta=5006.3,5010.3
Exp/Cntr=0.3,0.1

Type RM Length L Ch R = 1,867,288,288,288
BEGIN DESCRIPTION:
Walnut63 1.4
END DESCRIPTION:
XS GIS Cut Line= 3
      2733948.41      6755512.02      2733476.23      6755484.25
      2733153.31      6755574.53
#Sta/Elev= 30
  4677.6  349.91  4700.0  349.81  4782.7  348.07  4820.3  348.07  4860.3  347.54
  4880.4  346.58  4960.5  345.30  4980.5  345.24  4990.5  346.09  4997.1  345.99
  5010.6  345.29  5050.7  345.15  5068.7  343.95  5068.9  343.45  5072.4  343.45
  5072.7  343.95  5080.7  345.16  5096.1  345.49  5156.6  346.27  5161.8  346.63
  5182.0  346.07  5197.1  346.46  5202.7  346.84  5269.4  348.05  5327.4  349.93
  5342.9  349.88  5348.1  350.36  5416.3  352.07  5455.7  351.96  5485.9  352.58
#Mann=6,-1,0
  4677.6    0.05       0  4997.1     0.1       0  5068.7    0.07       0
  5072.7     0.1       0  5096.1    0.12       0  5197.1    0.05       0
Bank Sta=5068.7,5072.7
Exp/Cntr=0.3,0.1

Type RM Length L Ch R = 1,579,319,319,319
BEGIN DESCRIPTION:
Walnut63 1.2
END DESCRIPTION:
XS GIS Cut Line= 4
      2733889.41      6755466.88      2733764.42      6755355.78
      2733510.95      6755185.64      2733340.86      6755185.64
#Sta/Elev= 30
  4628.4  348.78  4677.3  348.87  4691.5  348.32  4708.9  348.39  4755.1  349.00
  4762.6  348.51  4834.5  348.00  4841.9  347.62  4863.5  346.70  4878.0  346.73
  4884.5  346.08  4920.5  344.73  4941.5  344.69  4951.7  344.19  4996.5  343.40
  4996.8  342.90  5000.3  342.90  5000.5  343.40  5034.6  343.48  5043.5  344.02
  5064.5  343.85  5069.0  344.19  5079.5  345.17  5085.6  344.78  5094.5  345.43
  5135.9  346.47  5175.9  348.98  5205.9  350.29  5225.9  350.95  5271.0  351.23
#Mann=8,-1,0
  4628.4    0.05       0  4708.9     0.1       0  4834.5    0.12       0
  4841.9     0.1       0  4951.7    0.12       0  4996.5    0.07       0
  5000.5    0.12       0  5069.0    0.05       0
Bank Sta=4996.5,5000.5
Exp/Cntr=0.3,0.1

Type RM Length L Ch R = 1,260,0,0,0
BEGIN DESCRIPTION:
Walnut63 1.0
END DESCRIPTION:
XS GIS Cut Line= 4
      2733925.34      6755414.78      2733835.72      6755110.09
      2733638.58      6754948.79      2733199.56      6754999.84
#Sta/Elev= 30
  4498.8  348.87  4565.3  348.75  4638.3  347.18  4669.5  347.09  4685.6  346.43
  4743.1  345.22  4765.4  344.21  4798.8  343.49  4967.9  343.02  5059.0  342.70
  5061.9  342.65  5062.1  342.15  5065.6  342.15  5065.9  342.65  5167.1  342.85
  5244.9  343.66  5267.0  344.51  5308.5  345.58  5315.3  344.75  5325.4  345.33
  5345.5  345.39  5389.6  346.83  5397.1  347.38  5416.0  347.55  5441.3  348.45
  5475.6  349.57  5480.7  349.24  5486.5  349.66  5506.6  349.70  5513.1  350.25
#Mann=11,-1,0
  4498.8    0.05       0  4685.6    0.12       0  4743.1     0.1       0
  4967.9    0.12       0  5059.0     0.1       0  5061.9    0.07       0
  5065.9     0.1       0  5167.1    0.12       0  5267.0    0.05       0
  5389.6    0.12       0  5441.3    0.05       0
Bank Sta=5061.9,5065.9
Exp/Cntr=0.3,0.1

Chan Stop Cuts=-1