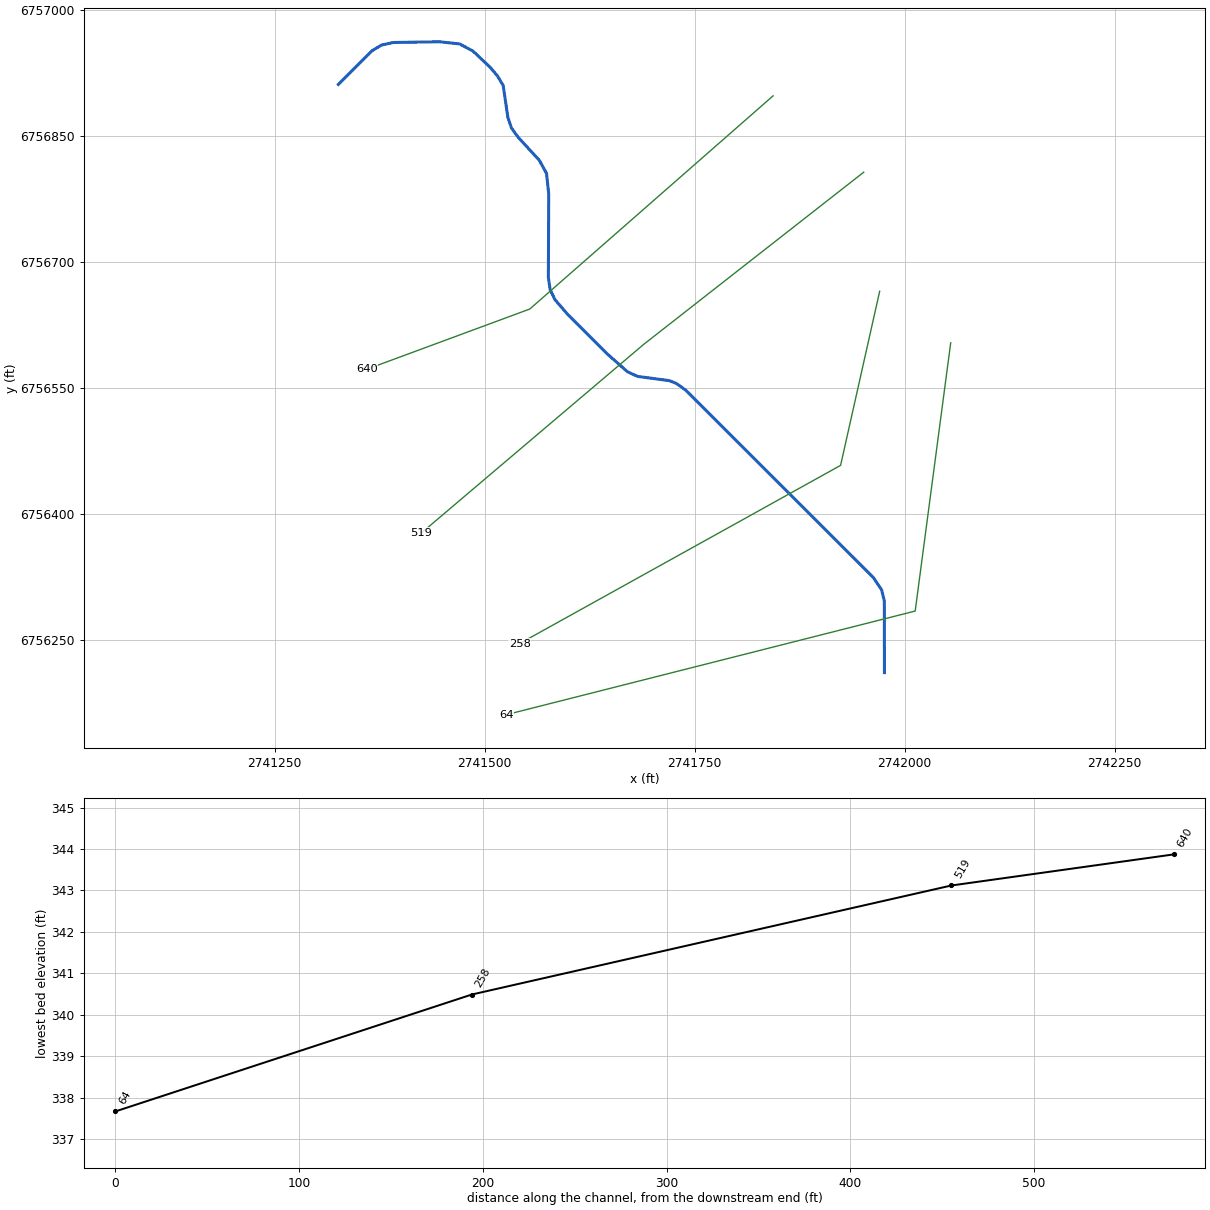
--- Walnut65.prj (project) ---

Proj Title=Walnut65 Base Level Engineering
Current Plan=p01
Default Exp/Contr=0.3,0.1
English Units
Geom File=g01
Flow File=f01
Plan File=p01
Y Axis Title=Elevation
X Axis Title(PF)=Main Channel Distance
X Axis Title(XS)=Station
BEGIN DESCRIPTION:
Walnut65
END DESCRIPTION:
DSS Export Rating Curves= 0
DSS Export Rating Curve Sorted= 0
DSS Export Volume Flow Curves= 0
DXF OffsetX= 0
DXF OffsetY= 0
DXF ScaleX= 1
DXF ScaleY= 10

--- Walnut65.p01 (plan) ---

Plan Title=Multiple Run
Program Version=4.10
Short Identifier=Multiple
Geom File=g01
Flow File=f01
Subcritical Flow
K Sum by GR= 0
Std Step Tol= 0.01
Critical Tol= 0.01
Num of Std Step Trials= 20
Max Error Tol= 0.3
Flow Tol Ratio= 0.001
Split Flow NTrial= 30
Split Flow Tol= 0.02
Split Flow Ratio= 0.02
Log Output Level= 0
Friction Slope Method= 1
Unsteady Friction Slope Method= 2
Unsteady Bridges Friction Slope Method= 1
Parabolic Critical Depth
Global Vel Dist= 1 , 1 , 1
Global Log Level= 0
CheckData=True
Encroach Param=-1 ,0,0, 0
BEGIN DESCRIPTION:
Multiple Run
END DESCRIPTION:
Computation Interval=1HOUR
Output Interval=1HOUR
Run HTab= 0
Run UNet= 0
Run PostProcess= 0
Run WQNet= 0
UNET Theta= 1
UNET Theta Warmup= 1
UNET ZTol= 0.02
UNET ZSATol= 0.05
UNET MxIter= 20
UNET MaxInSteps= 0
UNET DtIC= 0
UNET DtMin= 0
UNET MaxCRTS= 20
UNET WFStab= 2
UNET SFStab= 1
UNET WFX= 1
UNET SFX= 1
UNET DSS MLevel= 4
UNET DZMax Abort= 100
UNET Convert EG Bridges= 0
UNET Use Existing IB Tables=-1
UNET Froude Reduction=False
UNET Froude Limit= 1
UNET Froude Power= 10
UNET Time Slicing=0,0, 5
UNET Junction Losses=0
Instantaneous Interval=1HOUR
Write IC File= 0
Write IC File at Sim End=0
Echo Input=False
Echo Parameters=False
Echo Output=False
Write Detailed= 0
WQ AD Non Conservative
WQ ULTIMATE=-1
WQ Max Comp Step=1HOUR
WQ Output Interval=15MIN
WQ Output Selected Increments= 0
WQ Output face flow=0
WQ Output face velocity=0
WQ Output face area=0
WQ Output face dispersion=0
WQ Output cell volume=0
WQ Output cell surface area=0
WQ Output cell continuity=0
WQ Output cumulative cell continuity=0
WQ Output face conc=0
WQ Output face dconc_dx=0
WQ Output face courant=0
WQ Output face peclet=0
WQ Output face adv mass=0
WQ Output face disp mass=0
WQ Output cell mass=0
WQ Output cell source sink temp=0
WQ Output cell source sink nsm=0
WQ Output MaxMinRange=-1
WQ Daily Max Min Mean=-1
WQ Daily Range=0
WQ Daily Time=0
WQ Create Restart=0
WQ Fixed Restart=0
WQ System Summary=0
WQ Use Fixed Temperature=0
Sorting and Armoring Iterations= 10
XS Update Threshold= 0.02
Hydraulics Update Threshold= 0.02
Energy Slope Method= 1
Volume Change Method= 0
XS Weighting Method= 0
Number of US Weighted Cross Sections= 1
Number of DS Weighted Cross Sections= 1
Upstream XS Weight=0.25
Main XS Weight=0.5
Downstream XS Weight=0.25
Number of DS XS's Weighted with US Boundary= 1
Upstream Boundary Weight= 1
Weight of XSs Associated with US Boundary= 0
Number of US XS's Weighted with DS Boundary= 1
Downstream Boundary Weight= 0.5
Weight of XSs Associated with DS Boundary= 0.5
Sediment Output Level= 4
Mass or Volume Output= 0
Output Increment Type= 1
Profile and TS Output Increment= 10
XS Output Flag= 0
XS Output Increment= 10
Disregard all LS=0
Disregard all Conn=0
Disregard all Breaches=0
Disregard all Pumps=0

--- Walnut65.f01 (steady flow) ---

Flow Title=Multiple
Number of Profiles=7
Profile Names=10-year,25-year,50-year,1pct_min,100-year,1pct_plu,500-year
River Rch & RM= Walnut65,Reach-1,640
     173     216     249     143     286     570     375
River Rch & RM= Walnut65,Reach-1,64
     549     734     884     529    1055    2104    1505
Boundary for River Rch & Prof#=Walnut65,Reach-1,1
Up Type=0
Dn Type=3
Dn Slope=0.02
Boundary for River Rch & Prof#=Walnut65,Reach-1,2
Up Type=0
Dn Type=3
Dn Slope=0.02
Boundary for River Rch & Prof#=Walnut65,Reach-1,3
Up Type=0
Dn Type=3
Dn Slope=0.02
Boundary for River Rch & Prof#=Walnut65,Reach-1,4
Up Type=0
Dn Type=3
Dn Slope=0.02
Boundary for River Rch & Prof#=Walnut65,Reach-1,5
Up Type=0
Dn Type=3
Dn Slope=0.02
Boundary for River Rch & Prof#=Walnut65,Reach-1,6
Up Type=0
Dn Type=3
Dn Slope=0.02
Boundary for River Rch & Prof#=Walnut65,Reach-1,7
Up Type=0
Dn Type=3
Dn Slope=0.02

--- Walnut65.g01 (geometry) ---

Geom Title=Existing Conditions

River Reach=Walnut65,Reach-1
Reach XY= 30
      2741326.00      6756911.00      2741366.05      6756951.01
      2741377.41      6756957.82      2741391.23      6756960.82
      2741446.18      6756961.72      2741470.31      6756959.13
      2741486.11      6756950.70      2741506.42      6756931.59
      2741515.39      6756921.07      2741522.16      6756909.61
      2741527.74      6756871.76      2741532.15      6756858.86
      2741540.06      6756847.98      2741565.20      6756820.67
      2741573.75      6756805.07      2741576.33      6756781.14
      2741575.98      6756680.99      2741578.06      6756666.85
      2741583.81      6756654.79      2741598.84      6756637.42
      2741645.76      6756590.58      2741669.93      6756569.15
      2741682.04      6756563.53      2741719.95      6756558.46
      2741728.29      6756555.14      2741739.21      6756547.37
      2741962.65      6756324.33      2741972.62      6756309.60
      2741975.88      6756295.95      2741976.00      6756211.00

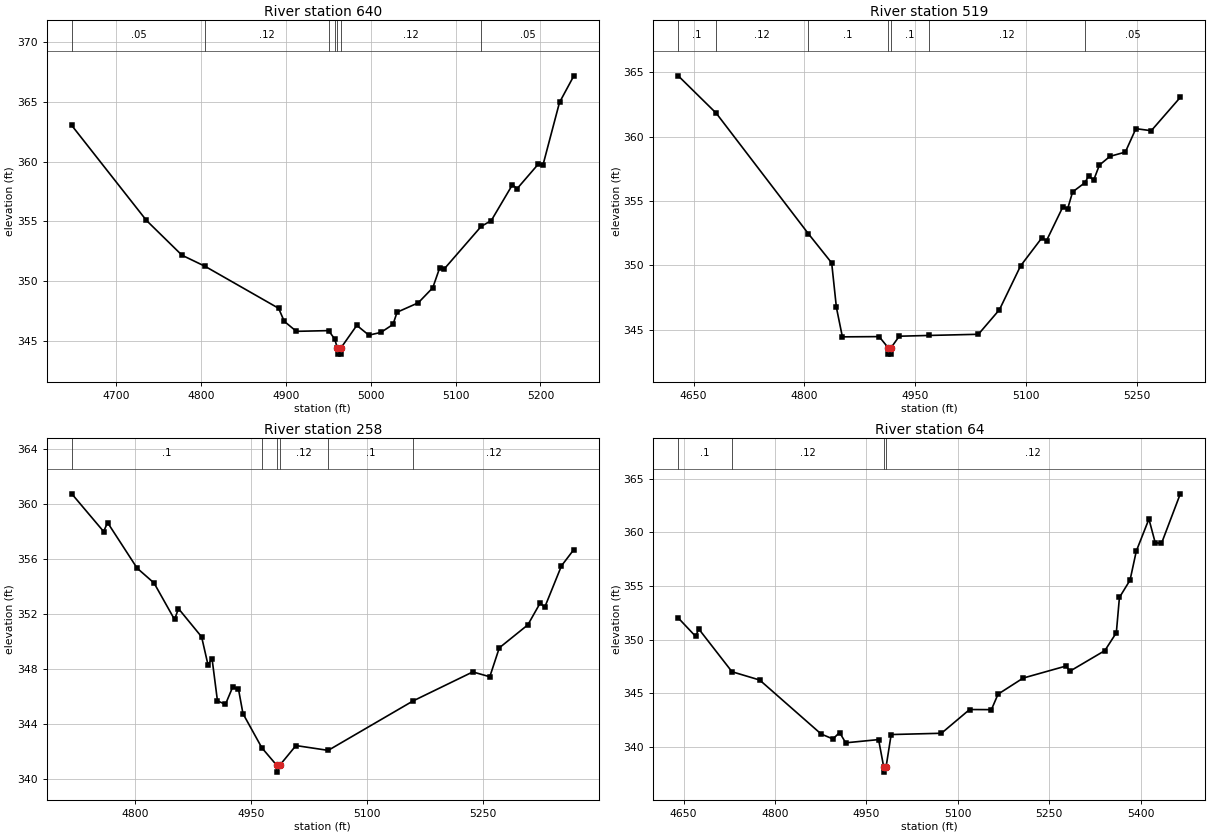
Type RM Length L Ch R = 1,640,121,121,121
BEGIN DESCRIPTION:
Walnut65 3.0
END DESCRIPTION:
XS GIS Cut Line= 3
      2741843.43      6756897.35      2741553.83      6756643.68
      2741360.12      6756572.10
#Sta/Elev= 30
  4647.9  363.03  4735.9  355.07  4777.7  352.16  4804.9  351.23  4891.6  347.71
  4898.2  346.62  4912.5  345.78  4950.5  345.84  4957.7  345.13  4960.8  344.37
  4961.0  343.87  4964.5  343.87  4964.8  344.37  4983.7  346.28  4997.9  345.46
  5012.1  345.69  5026.4  346.36  5031.1  347.38  5056.1  348.17  5073.2  349.43
  5081.2  351.07  5086.6  351.00  5130.2  354.57  5142.1  355.06  5167.1  358.07
  5172.5  357.73  5197.6  359.80  5202.9  359.68  5222.5  364.96  5239.4  367.19
#Mann=7,-1,0
  4647.9    0.05       0  4804.9    0.12       0  4950.5    0.05       0
  4957.7    0.12       0  4960.8    0.07       0  4964.8    0.12       0
  5130.2    0.05       0
Bank Sta=4960.8,4964.8
Exp/Cntr=0.3,0.1

Type RM Length L Ch R = 1,519,261,261,261
BEGIN DESCRIPTION:
Walnut65 2.0
END DESCRIPTION:
XS GIS Cut Line= 3
      2741951.30      6756806.48      2741689.13      6756601.40
      2741424.90      6756377.33
#Sta/Elev= 30
  4629.2  364.72  4680.6  361.82  4805.2  352.47  4836.8  350.20  4843.2  346.74
  4851.3  344.46  4901.0  344.48  4913.2  343.62  4913.5  343.12  4917.0  343.12
  4917.2  343.62  4928.2  344.51  4968.6  344.57  5035.3  344.66  5063.8  346.57
  5092.4  349.97  5121.0  352.13  5127.5  351.93  5149.6  354.55  5156.1  354.41
  5162.8  355.71  5179.3  356.42  5184.7  356.96  5191.2  356.61  5199.0  357.79
  5213.3  358.47  5234.1  358.80  5248.4  360.62  5269.2  360.46  5308.5  363.05
#Mann=7,-1,0
  4629.2     0.1       0  4680.6    0.12       0  4805.2     0.1       0
  4913.2    0.07       0  4917.2     0.1       0  4968.6    0.12       0
  5179.3    0.05       0
Bank Sta=4913.2,4917.2
Exp/Cntr=0.3,0.1

Type RM Length L Ch R = 1,258,194,194,194
BEGIN DESCRIPTION:
Walnut65 1.5
END DESCRIPTION:
XS GIS Cut Line= 3
      2741970.31      6756664.84      2741923.79      6756457.64
      2741541.74      6756245.62
#Sta/Elev= 30
  4718.2  360.71  4759.4  357.97  4764.5  358.62  4802.7  355.31  4824.6  354.23
  4851.1  351.58  4856.2  352.37  4886.1  350.32  4894.4  348.28  4899.6  348.74
  4906.6  345.67  4916.9  345.41  4926.3  346.67  4933.8  346.52  4939.6  344.74
  4964.1  342.25  4983.2  340.99  4983.5  340.49  4987.2  340.99  5008.1  342.42
  5049.8  342.07  5159.5  345.66  5236.8  347.77  5258.8  347.42  5271.1  349.52
  5308.0  351.19  5324.0  352.78  5329.8  352.46  5351.5  355.48  5367.5  356.66
#Mann=6,-1,0
  4718.2     0.1       0  4964.1    0.12       0  4983.2    0.07       0
  4987.2    0.12       0  5049.8     0.1       0  5159.5    0.12       0
Bank Sta=4983.2,4987.2
Exp/Cntr=0.3,0.1

Type RM Length L Ch R = 1,64,0,0,0
BEGIN DESCRIPTION:
Walnut65 1.0
END DESCRIPTION:
XS GIS Cut Line= 3
      2742054.86      6756603.47      2742012.59      6756284.29
      2741526.03      6756161.01
#Sta/Elev= 30
  4641.1  352.03  4669.7  350.31  4674.7  351.01  4729.3  347.02  4774.7  346.25
  4875.6  341.22  4894.9  340.76  4905.9  341.36  4915.9  340.40  4969.9  340.70
  4978.2  338.17  4978.4  337.67  4982.2  338.17  4990.5  341.17  5073.0  341.29
  5119.2  343.50  5155.0  343.49  5165.9  344.93  5207.1  346.43  5278.0  347.56
  5283.2  347.05  5341.2  348.99  5360.0  350.65  5365.1  353.94  5382.5  355.55
  5392.8  358.26  5413.5  361.24  5423.8  359.04  5434.1  358.97  5465.0  363.59
#Mann=4,-1,0
  4641.1     0.1       0  4729.3    0.12       0  4978.2    0.07       0
  4982.2    0.12       0
Bank Sta=4978.2,4982.2
Exp/Cntr=0.3,0.1

Chan Stop Cuts=-1