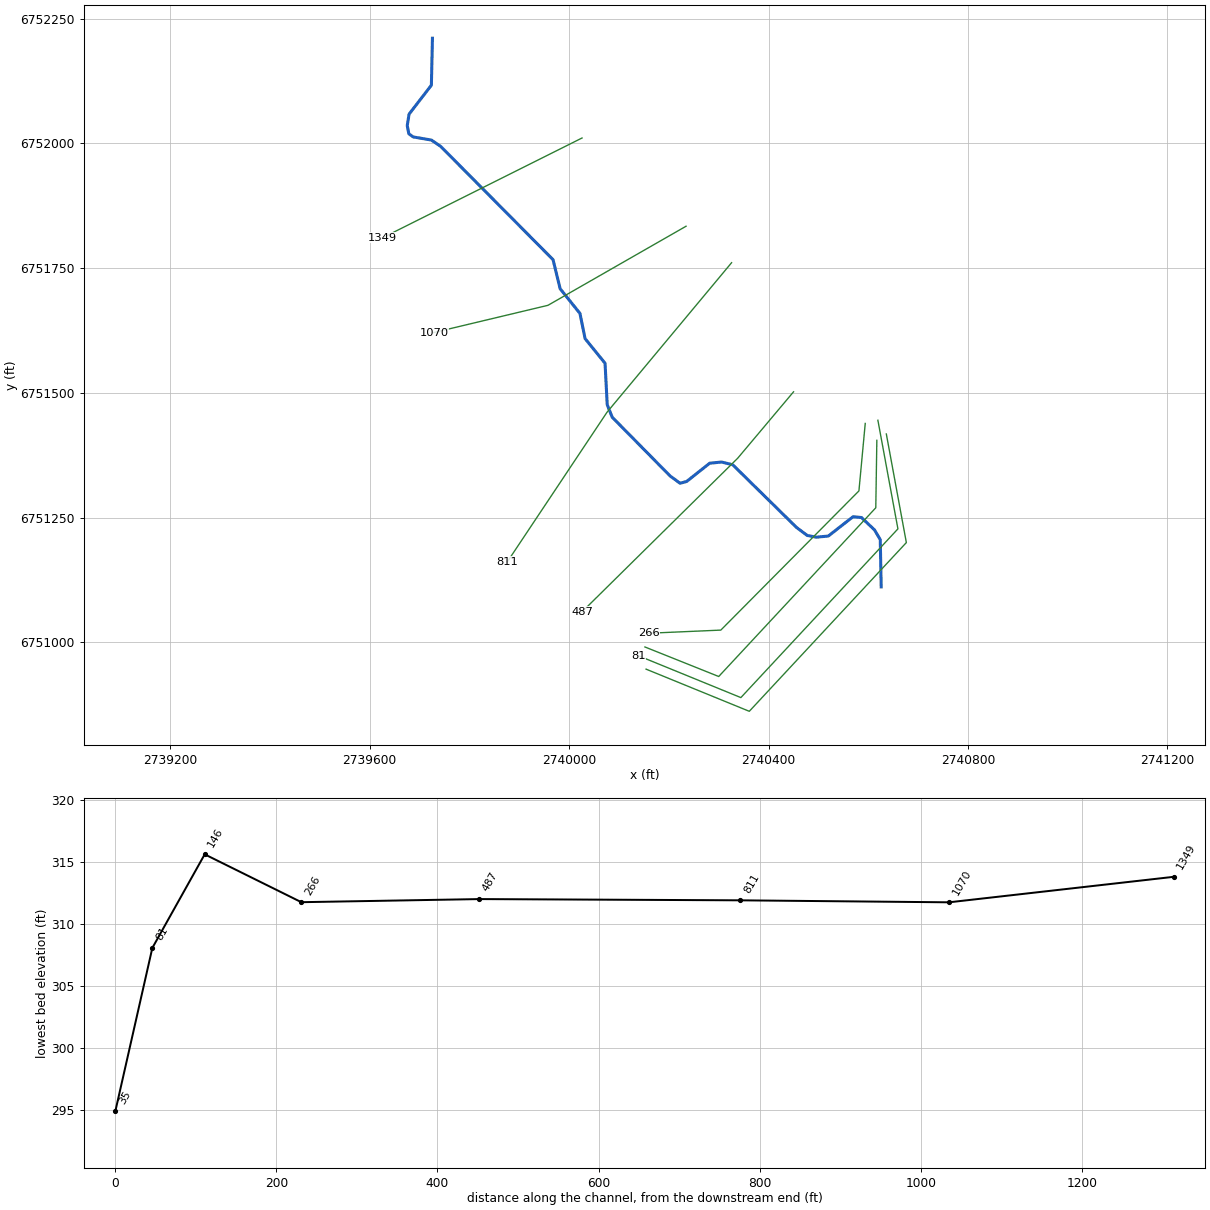
--- Walnut67.prj (project) ---

Proj Title=Walnut67 Base Level Engineering
Current Plan=p01
Default Exp/Contr=0.3,0.1
English Units
Geom File=g01
Flow File=f01
Plan File=p01
Y Axis Title=Elevation
X Axis Title(PF)=Main Channel Distance
X Axis Title(XS)=Station
BEGIN DESCRIPTION:
Walnut67
END DESCRIPTION:
DSS Export Rating Curves= 0
DSS Export Rating Curve Sorted= 0
DSS Export Volume Flow Curves= 0
DXF OffsetX= 0
DXF OffsetY= 0
DXF ScaleX= 1
DXF ScaleY= 10

--- Walnut67.p01 (plan) ---

Plan Title=Multiple Run
Program Version=4.10
Short Identifier=Multiple
Geom File=g01
Flow File=f01
Subcritical Flow
K Sum by GR= 0
Std Step Tol= 0.01
Critical Tol= 0.01
Num of Std Step Trials= 20
Max Error Tol= 0.3
Flow Tol Ratio= 0.001
Split Flow NTrial= 30
Split Flow Tol= 0.02
Split Flow Ratio= 0.02
Log Output Level= 0
Friction Slope Method= 1
Unsteady Friction Slope Method= 2
Unsteady Bridges Friction Slope Method= 1
Parabolic Critical Depth
Global Vel Dist= 1 , 1 , 1
Global Log Level= 0
CheckData=True
Encroach Param=-1 ,0,0, 0
BEGIN DESCRIPTION:
Multiple Run
END DESCRIPTION:
Computation Interval=1HOUR
Output Interval=1HOUR
Run HTab= 0
Run UNet= 0
Run PostProcess= 0
Run WQNet= 0
UNET Theta= 1
UNET Theta Warmup= 1
UNET ZTol= 0.02
UNET ZSATol= 0.05
UNET MxIter= 20
UNET MaxInSteps= 0
UNET DtIC= 0
UNET DtMin= 0
UNET MaxCRTS= 20
UNET WFStab= 2
UNET SFStab= 1
UNET WFX= 1
UNET SFX= 1
UNET DSS MLevel= 4
UNET DZMax Abort= 100
UNET Convert EG Bridges= 0
UNET Use Existing IB Tables=-1
UNET Froude Reduction=False
UNET Froude Limit= 1
UNET Froude Power= 10
UNET Time Slicing=0,0, 5
UNET Junction Losses=0
Instantaneous Interval=1HOUR
Write IC File= 0
Write IC File at Sim End=0
Echo Input=False
Echo Parameters=False
Echo Output=False
Write Detailed= 0
WQ AD Non Conservative
WQ ULTIMATE=-1
WQ Max Comp Step=1HOUR
WQ Output Interval=15MIN
WQ Output Selected Increments= 0
WQ Output face flow=0
WQ Output face velocity=0
WQ Output face area=0
WQ Output face dispersion=0
WQ Output cell volume=0
WQ Output cell surface area=0
WQ Output cell continuity=0
WQ Output cumulative cell continuity=0
WQ Output face conc=0
WQ Output face dconc_dx=0
WQ Output face courant=0
WQ Output face peclet=0
WQ Output face adv mass=0
WQ Output face disp mass=0
WQ Output cell mass=0
WQ Output cell source sink temp=0
WQ Output cell source sink nsm=0
WQ Output MaxMinRange=-1
WQ Daily Max Min Mean=-1
WQ Daily Range=0
WQ Daily Time=0
WQ Create Restart=0
WQ Fixed Restart=0
WQ System Summary=0
WQ Use Fixed Temperature=0
Sorting and Armoring Iterations= 10
XS Update Threshold= 0.02
Hydraulics Update Threshold= 0.02
Energy Slope Method= 1
Volume Change Method= 0
XS Weighting Method= 0
Number of US Weighted Cross Sections= 1
Number of DS Weighted Cross Sections= 1
Upstream XS Weight=0.25
Main XS Weight=0.5
Downstream XS Weight=0.25
Number of DS XS's Weighted with US Boundary= 1
Upstream Boundary Weight= 1
Weight of XSs Associated with US Boundary= 0
Number of US XS's Weighted with DS Boundary= 1
Downstream Boundary Weight= 0.5
Weight of XSs Associated with DS Boundary= 0.5
Sediment Output Level= 4
Mass or Volume Output= 0
Output Increment Type= 1
Profile and TS Output Increment= 10
XS Output Flag= 0
XS Output Increment= 10
Disregard all LS=0
Disregard all Conn=0
Disregard all Breaches=0
Disregard all Pumps=0

--- Walnut67.f01 (steady flow) ---

Flow Title=Multiple
Number of Profiles=7
Profile Names=10-year,25-year,50-year,1pct_min,100-year,1pct_plu,500-year
River Rch & RM= Walnut67,Reach-1,1349
     178     224     259     150     299     598     399
River Rch & RM= Walnut67,Reach-1,35
     799    1083    1315     791    1579    3150    2284
Boundary for River Rch & Prof#=Walnut67,Reach-1,1
Up Type=0
Dn Type=3
Dn Slope=0.005
Boundary for River Rch & Prof#=Walnut67,Reach-1,2
Up Type=0
Dn Type=3
Dn Slope=0.005
Boundary for River Rch & Prof#=Walnut67,Reach-1,3
Up Type=0
Dn Type=3
Dn Slope=0.005
Boundary for River Rch & Prof#=Walnut67,Reach-1,4
Up Type=0
Dn Type=3
Dn Slope=0.005
Boundary for River Rch & Prof#=Walnut67,Reach-1,5
Up Type=0
Dn Type=3
Dn Slope=0.005
Boundary for River Rch & Prof#=Walnut67,Reach-1,6
Up Type=0
Dn Type=3
Dn Slope=0.005
Boundary for River Rch & Prof#=Walnut67,Reach-1,7
Up Type=0
Dn Type=3
Dn Slope=0.005

--- Walnut67.g01 (geometry) ---

Geom Title=Existing Conditions

River Reach=Walnut67,Reach-1
Reach XY= 30
      2739726.00      6752211.00      2739723.86      6752116.83
      2739679.15      6752058.89      2739675.45      6752035.87
      2739678.63      6752019.48      2739687.36      6752013.12
      2739723.84      6752006.87      2739742.42      6751994.27
      2739967.86      6751767.06      2739982.10      6751708.81
      2740021.84      6751659.28      2740032.12      6751608.82
      2740072.17      6751559.41      2740076.52      6751476.22
      2740086.52      6751451.21      2740202.64      6751333.46
      2740222.59      6751318.82      2740235.87      6751322.39
      2740282.05      6751359.01      2740305.84      6751361.32
      2740328.29      6751355.88      2740455.91      6751230.44
      2740477.65      6751214.16      2740496.16      6751210.68
      2740519.96      6751212.99      2740569.62      6751251.75
      2740586.41      6751250.10      2740612.66      6751225.23
      2740624.15      6751205.71      2740626.00      6751111.00

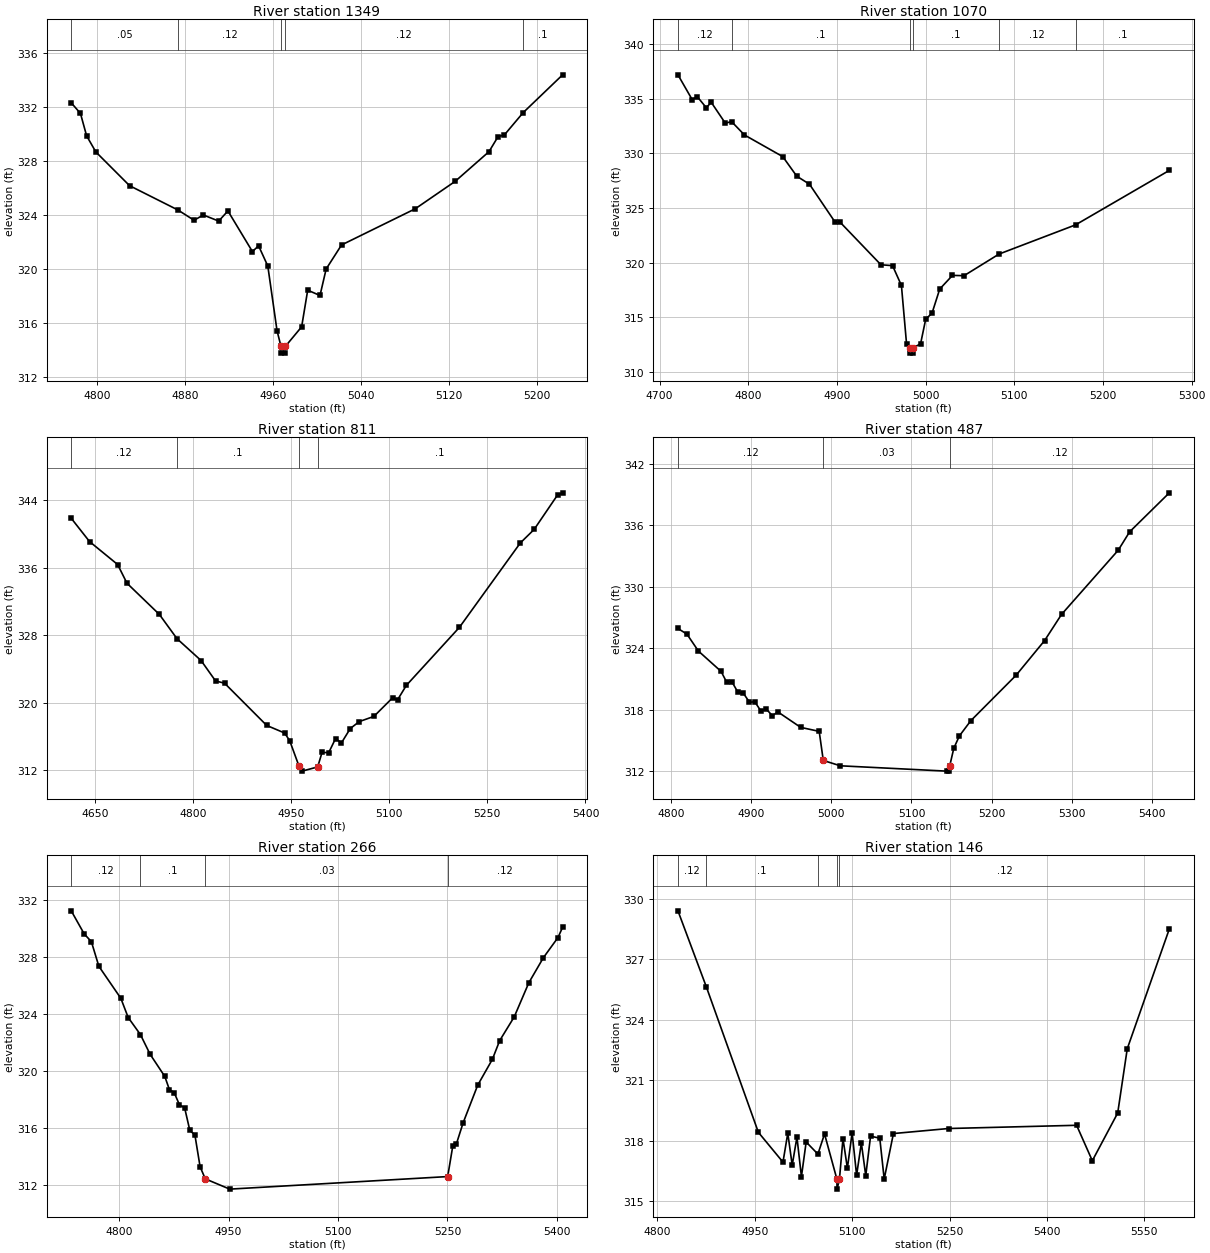
Type RM Length L Ch R = 1,1349,279,279,279
BEGIN DESCRIPTION:
Walnut67 5.0
END DESCRIPTION:
XS GIS Cut Line= 3
      2740026.02      6752011.01      2739826.00      6751911.00
      2739626.04      6751811.02
#Sta/Elev= 30
  4776.4  332.32  4784.8  331.53  4790.4  329.87  4798.8  328.68  4829.5  326.18
  4873.5  324.38  4888.2  323.62  4896.6  324.01  4910.6  323.56  4919.0  324.31
  4941.3  321.30  4946.9  321.73  4955.3  320.23  4963.7  315.44  4967.3  314.28
  4967.5  313.78  4971.0  313.78  4971.3  314.28  4986.1  315.73  4991.6  318.44
  5002.8  318.05  5008.4  320.01  5022.4  321.79  5089.5  324.47  5125.8  326.50
  5156.6  328.70  5164.9  329.82  5170.5  329.93  5187.7  331.59  5223.6  334.39
#Mann=5,-1,0
  4776.4    0.05       0  4873.5    0.12       0  4967.3    0.07       0
  4971.3    0.12       0  5187.7     0.1       0
Bank Sta=4967.3,4971.3
Exp/Cntr=0.3,0.1

Type RM Length L Ch R = 1,1070,259,259,259
BEGIN DESCRIPTION:
Walnut67 4.0
END DESCRIPTION:
XS GIS Cut Line= 3
      2740234.66      6751834.11      2739957.68      6751675.54
      2739729.15      6751621.03
#Sta/Elev= 30
  4720.7  337.18  4736.7  334.92  4742.5  335.18  4752.6  334.18  4758.3  334.66
  4774.1  332.76  4781.2  332.90  4795.7  331.68  4838.9  329.70  4854.7  327.91
  4869.0  327.18  4897.9  323.71  4903.7  323.69  4949.6  319.81  4962.7  319.73
  4972.7  317.92  4978.5  312.57  4982.2  312.23  4982.5  311.73  4986.0  311.73
  4986.2  312.23  4994.3  312.58  5000.1  314.84  5007.2  315.38  5015.9  317.59
  5030.3  318.84  5043.3  318.81  5082.8  320.79  5169.1  323.46  5274.8  328.44
#Mann=6,-1,0
  4720.7    0.12       0  4781.2     0.1       0  4982.2    0.07       0
  4986.2     0.1       0  5082.8    0.12       0  5169.1     0.1       0
Bank Sta=4982.2,4986.2
Exp/Cntr=0.3,0.1

Type RM Length L Ch R = 1,811,324,324,324
BEGIN DESCRIPTION:
Walnut67 3.0
END DESCRIPTION:
XS GIS Cut Line= 3
      2740325.98      6751760.98      2740076.00      6751461.00
      2739876.02      6751161.04
#Sta/Elev= 30
  4614.1  341.87  4642.1  339.11  4685.0  336.39  4699.3  334.17  4748.8  330.47
  4775.8  327.59  4812.6  325.00  4834.7  322.58  4848.4  322.32  4912.8  317.31
  4940.2  316.41  4948.0  315.50  4962.3  312.46  4967.0  311.89  4990.8  312.39
  4997.4  314.11  5007.6  314.08  5018.1  315.75  5027.1  315.24  5040.6  316.94
  5054.2  317.76  5076.7  318.38  5105.2  320.58  5112.8  320.34  5126.3  322.06
  5207.4  328.94  5300.5  338.95  5321.6  340.55  5357.6  344.66  5365.1  344.89
#Mann=4,-1,0
  4614.1    0.12       0  4775.8     0.1       0  4962.3    0.04       0
  4990.8     0.1       0
Bank Sta=4962.3,4990.8
Exp/Cntr=0.3,0.1

Type RM Length L Ch R = 1,487,221,221,221
BEGIN DESCRIPTION:
Walnut67 2.0
END DESCRIPTION:
XS GIS Cut Line= 3
      2740450.24      6751502.15      2740338.22      6751368.99
      2740025.99      6751060.99
#Sta/Elev= 30
  4808.9  325.91  4820.1  325.36  4834.4  323.71  4862.7  321.72  4869.5  320.69
  4876.1  320.72  4883.8  319.67  4890.4  319.60  4898.1  318.71  4904.7  318.76
  4912.4  317.85  4919.0  318.05  4926.7  317.39  4933.3  317.78  4961.9  316.26
  4985.0  315.87  4990.1  313.03  5011.4  312.51  5143.9  311.99  5147.4  311.99
  5147.7  312.49  5152.8  314.22  5159.8  315.43  5174.0  316.91  5230.5  321.35
  5266.0  324.73  5287.1  327.28  5357.8  333.55  5372.0  335.34  5421.5  339.15
#Mann=3,-1,0
  4808.9    0.12       0  4990.1    0.03       0  5147.7    0.12       0
Bank Sta=4990.1,5147.7
Exp/Cntr=0.3,0.1

Type RM Length L Ch R = 1,266,120,120,120
BEGIN DESCRIPTION:
Walnut67 0.5
END DESCRIPTION:
XS GIS Cut Line= 4
      2740594.02      6751438.72      2740581.34      6751303.45
      2740304.39      6751024.39      2740159.75      6751018.10
#Sta/Elev= 30
  4734.2  331.25  4752.0  329.63  4761.8  329.09  4772.1  327.36  4802.2  325.12
  4812.3  323.77  4829.0  322.58  4842.4  321.19  4862.5  319.64  4868.8  318.72
  4875.5  318.49  4882.6  317.65  4889.7  317.44  4896.8  315.86  4903.8  315.53
  4910.9  313.31  4918.0  312.46  4951.6  311.74  5250.4  312.62  5257.4  314.76
  5262.1  314.87  5271.6  316.39  5291.6  319.03  5311.7  320.84  5321.7  322.15
  5341.7  323.82  5361.7  326.21  5381.7  327.97  5401.7  329.38  5408.0  330.10
#Mann=4,-1,0
  4734.2    0.12       0  4829.0     0.1       0  4918.0    0.03       0
  5250.4    0.12       0
Bank Sta=4918,5250.4
Exp/Cntr=0.3,0.1

Type RM Length L Ch R = 1,146,65,65,65
BEGIN DESCRIPTION:
Walnut67 0.3
END DESCRIPTION:
XS GIS Cut Line= 4
      2740617.28      6751404.90      2740615.16      6751269.63
      2740300.16      6750931.37      2740152.17      6750990.57
#Sta/Elev= 30
  4831.6  329.41  4875.5  325.62  4955.5  318.41  4993.4  316.93  5000.8  318.37
  5007.6  316.78  5014.9  318.17  5021.8  316.21  5029.1  317.93  5047.2  317.33
  5057.4  318.33  5076.4  316.09  5076.7  315.59  5080.4  316.09  5085.8  318.10
  5092.6  316.63  5099.9  318.39  5106.8  316.28  5114.1  317.88  5120.9  316.26
  5128.3  318.22  5142.5  318.12  5149.3  316.09  5163.5  318.35  5248.5  318.60
  5445.7  318.76  5469.9  317.00  5509.0  319.37  5523.7  322.56  5588.5  328.51
#Mann=5,-1,0
  4831.6    0.12       0  4875.5     0.1       0  5047.2    0.12       0
  5076.4    0.07       0  5080.4    0.12       0
Bank Sta=5076.4,5080.4
Exp/Cntr=0.3,0.1

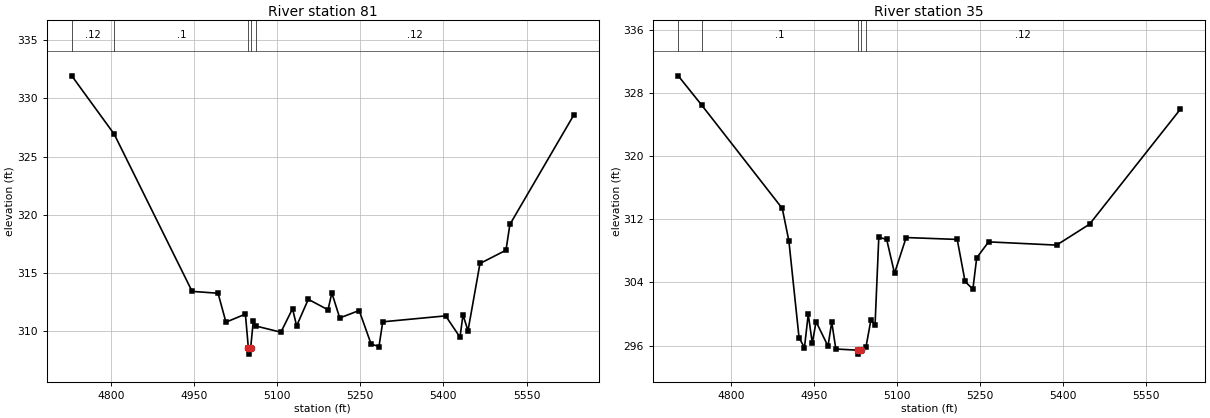
Type RM Length L Ch R = 1,81,46,46,46
BEGIN DESCRIPTION:
Walnut67 0.2
END DESCRIPTION:
XS GIS Cut Line= 4
      2740619.39      6751445.09      2740659.56      6751227.35
      2740344.56      6750889.09      2740139.23      6750972.90
#Sta/Elev= 30
  4729.8  331.92  4806.3  326.92  4946.8  313.44  4993.6  313.28  5007.8  310.80
  5042.9  311.49  5048.3  308.56  5048.5  308.06  5052.3  308.56  5057.1  310.86
  5061.8  310.47  5106.9  309.94  5127.9  311.95  5135.3  310.48  5156.3  312.76
  5191.9  311.86  5198.8  313.31  5213.0  311.16  5248.1  311.80  5269.6  308.92
  5283.8  308.71  5290.6  310.83  5404.0  311.34  5429.9  309.51  5435.3  311.43
  5444.3  310.06  5465.9  315.83  5512.8  316.97  5519.9  319.18  5635.2  328.57
#Mann=5,-1,0
  4729.8    0.12       0  4806.3     0.1       0  5048.3    0.07       0
  5052.3     0.1       0  5061.8    0.12       0
Bank Sta=5048.3,5052.3
Exp/Cntr=0.3,0.1

Type RM Length L Ch R = 1,35,0,0,0
BEGIN DESCRIPTION:
Walnut67 0.1
END DESCRIPTION:
XS GIS Cut Line= 4
      2740636.31      6751417.60      2740676.47      6751199.86
      2740361.47      6750861.61      2740154.47      6750946.10
#Sta/Elev= 30
  4705.2  330.19  4747.9  326.45  4893.2  313.38  4905.1  309.27  4923.5  296.99
  4933.3  295.74  4940.1  299.98  4947.4  296.31  4954.3  299.02  4975.8  295.92
  4982.6  298.98  4989.9  295.56  5029.2  295.41  5030.3  294.91  5035.6  295.41
  5044.4  295.80  5053.4  299.27  5060.8  298.58  5067.6  309.72  5081.8  309.46
  5096.0  305.16  5117.0  309.69  5209.3  309.45  5223.5  304.12  5237.6  303.14
  5244.5  307.12  5266.0  309.14  5388.8  308.73  5448.4  311.38  5612.4  325.95
#Mann=5,-1,0
  4705.2    0.12       0  4747.9     0.1       0  5029.2    0.07       0
  5035.6     0.1       0  5044.4    0.12       0
Bank Sta=5029.2,5035.6
Exp/Cntr=0.3,0.1

Chan Stop Cuts=-1