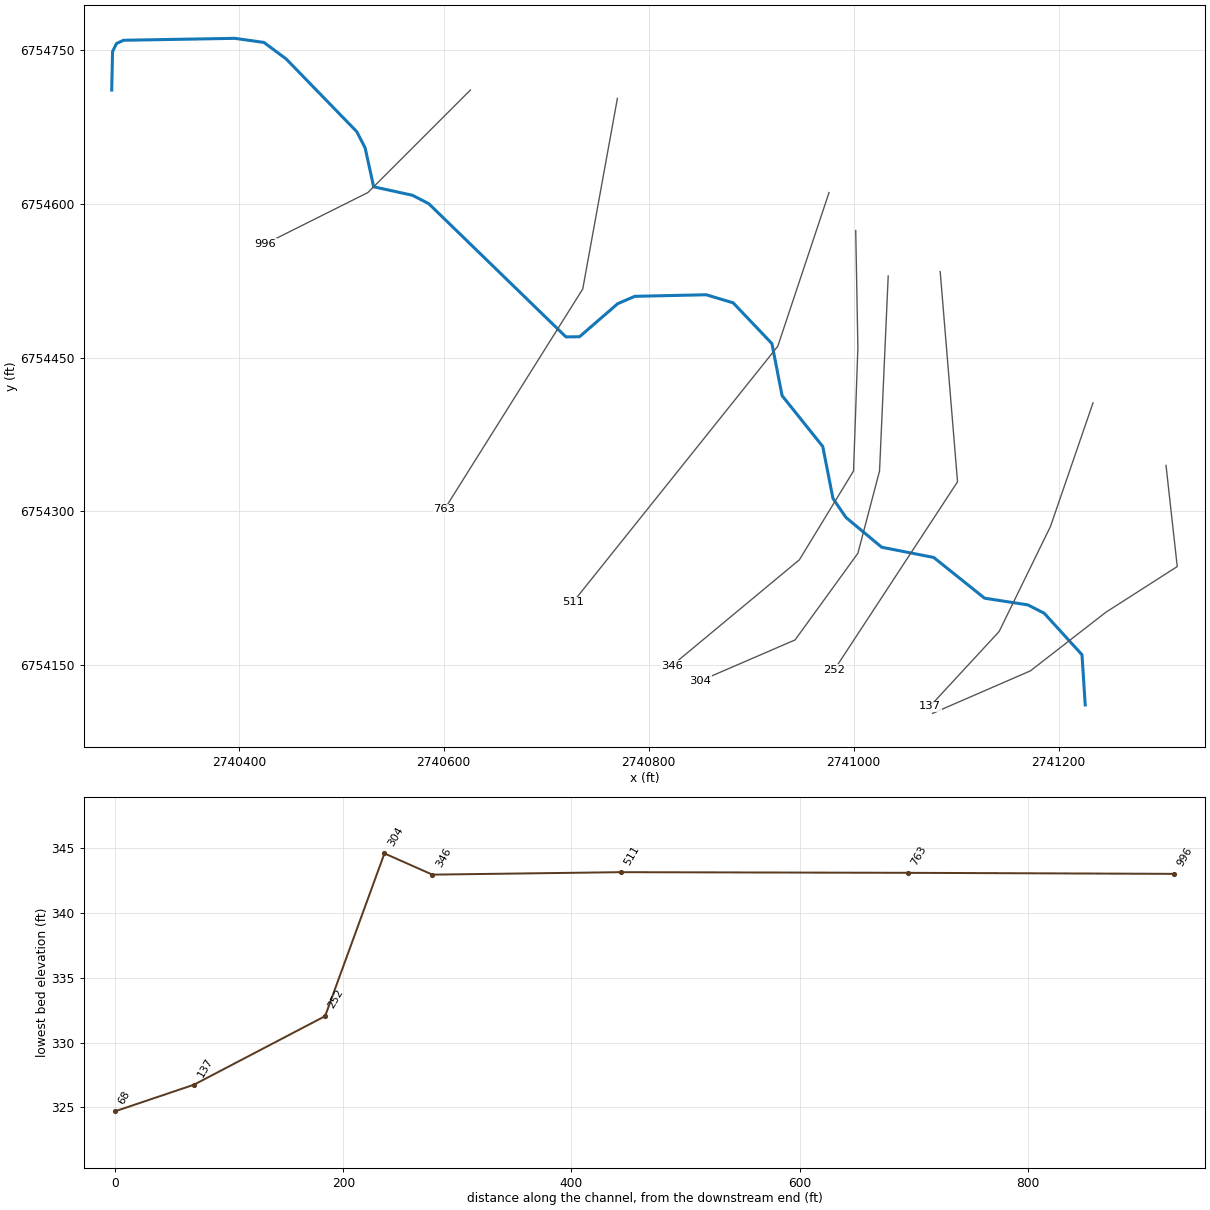
--- Walnut69.prj (project) ---

Proj Title=Walnut69 Base Level Engineering
Current Plan=p01
Default Exp/Contr=0.3,0.1
English Units
Geom File=g01
Flow File=f01
Plan File=p01
Y Axis Title=Elevation
X Axis Title(PF)=Main Channel Distance
X Axis Title(XS)=Station
BEGIN DESCRIPTION:
Walnut69
END DESCRIPTION:
DSS Export Rating Curves= 0
DSS Export Rating Curve Sorted= 0
DSS Export Volume Flow Curves= 0
DXF OffsetX= 0
DXF OffsetY= 0
DXF ScaleX= 1
DXF ScaleY= 10

--- Walnut69.p01 (plan) ---

Plan Title=Multiple Run
Program Version=4.10
Short Identifier=Multiple
Geom File=g01
Flow File=f01
Subcritical Flow
K Sum by GR= 0
Std Step Tol= 0.01
Critical Tol= 0.01
Num of Std Step Trials= 20
Max Error Tol= 0.3
Flow Tol Ratio= 0.001
Split Flow NTrial= 30
Split Flow Tol= 0.02
Split Flow Ratio= 0.02
Log Output Level= 0
Friction Slope Method= 1
Unsteady Friction Slope Method= 2
Unsteady Bridges Friction Slope Method= 1
Parabolic Critical Depth
Global Vel Dist= 1 , 1 , 1
Global Log Level= 0
CheckData=True
Encroach Param=-1 ,0,0, 0
BEGIN DESCRIPTION:
Multiple Run
END DESCRIPTION:
Computation Interval=1HOUR
Output Interval=1HOUR
Run HTab= 0
Run UNet= 0
Run PostProcess= 0
Run WQNet= 0
UNET Theta= 1
UNET Theta Warmup= 1
UNET ZTol= 0.02
UNET ZSATol= 0.05
UNET MxIter= 20
UNET MaxInSteps= 0
UNET DtIC= 0
UNET DtMin= 0
UNET MaxCRTS= 20
UNET WFStab= 2
UNET SFStab= 1
UNET WFX= 1
UNET SFX= 1
UNET DSS MLevel= 4
UNET DZMax Abort= 100
UNET Convert EG Bridges= 0
UNET Use Existing IB Tables=-1
UNET Froude Reduction=False
UNET Froude Limit= 1
UNET Froude Power= 10
UNET Time Slicing=0,0, 5
UNET Junction Losses=0
Instantaneous Interval=1HOUR
Write IC File= 0
Write IC File at Sim End=0
Echo Input=False
Echo Parameters=False
Echo Output=False
Write Detailed= 0
WQ AD Non Conservative
WQ ULTIMATE=-1
WQ Max Comp Step=1HOUR
WQ Output Interval=15MIN
WQ Output Selected Increments= 0
WQ Output face flow=0
WQ Output face velocity=0
WQ Output face area=0
WQ Output face dispersion=0
WQ Output cell volume=0
WQ Output cell surface area=0
WQ Output cell continuity=0
WQ Output cumulative cell continuity=0
WQ Output face conc=0
WQ Output face dconc_dx=0
WQ Output face courant=0
WQ Output face peclet=0
WQ Output face adv mass=0
WQ Output face disp mass=0
WQ Output cell mass=0
WQ Output cell source sink temp=0
WQ Output cell source sink nsm=0
WQ Output MaxMinRange=-1
WQ Daily Max Min Mean=-1
WQ Daily Range=0
WQ Daily Time=0
WQ Create Restart=0
WQ Fixed Restart=0
WQ System Summary=0
WQ Use Fixed Temperature=0
Sorting and Armoring Iterations= 10
XS Update Threshold= 0.02
Hydraulics Update Threshold= 0.02
Energy Slope Method= 1
Volume Change Method= 0
XS Weighting Method= 0
Number of US Weighted Cross Sections= 1
Number of DS Weighted Cross Sections= 1
Upstream XS Weight=0.25
Main XS Weight=0.5
Downstream XS Weight=0.25
Number of DS XS's Weighted with US Boundary= 1
Upstream Boundary Weight= 1
Weight of XSs Associated with US Boundary= 0
Number of US XS's Weighted with DS Boundary= 1
Downstream Boundary Weight= 0.5
Weight of XSs Associated with DS Boundary= 0.5
Sediment Output Level= 4
Mass or Volume Output= 0
Output Increment Type= 1
Profile and TS Output Increment= 10
XS Output Flag= 0
XS Output Increment= 10
Disregard all LS=0
Disregard all Conn=0
Disregard all Breaches=0
Disregard all Pumps=0

--- Walnut69.f01 (steady flow) ---

Flow Title=Multiple
Number of Profiles=7
Profile Names=10-year,25-year,50-year,1pct_min,100-year,1pct_plu,500-year
River Rch & RM= Walnut69,Reach-1,996
     126     154     175     100     199     397     256
River Rch & RM= Walnut69,Reach-1,68
     622     838    1014     609    1216    2426    1752
Boundary for River Rch & Prof#=Walnut69,Reach-1,1
Up Type=0
Dn Type=3
Dn Slope=0.03
Boundary for River Rch & Prof#=Walnut69,Reach-1,2
Up Type=0
Dn Type=3
Dn Slope=0.03
Boundary for River Rch & Prof#=Walnut69,Reach-1,3
Up Type=0
Dn Type=3
Dn Slope=0.03
Boundary for River Rch & Prof#=Walnut69,Reach-1,4
Up Type=0
Dn Type=3
Dn Slope=0.03
Boundary for River Rch & Prof#=Walnut69,Reach-1,5
Up Type=0
Dn Type=3
Dn Slope=0.03
Boundary for River Rch & Prof#=Walnut69,Reach-1,6
Up Type=0
Dn Type=3
Dn Slope=0.03
Boundary for River Rch & Prof#=Walnut69,Reach-1,7
Up Type=0
Dn Type=3
Dn Slope=0.03

--- Walnut69.g01 (geometry) ---

Geom Title=Existing Conditions

River Reach=Walnut69,Reach-1
Reach XY= 30
      2740276.00      6754711.00      2740276.84      6754748.57
      2740280.63      6754756.38      2740287.44      6754759.59
      2740396.16      6754761.48      2740424.54      6754757.48
      2740446.20      6754741.41      2740515.12      6754670.44
      2740523.31      6754654.58      2740531.62      6754616.62
      2740569.57      6754608.31      2740585.42      6754600.11
      2740719.26      6754470.13      2740732.53      6754470.29
      2740769.83      6754502.58      2740786.49      6754509.73
      2740856.05      6754511.25      2740882.46      6754503.36
      2740920.28      6754463.59      2740930.20      6754412.77
      2740969.89      6754363.16      2740979.86      6754312.42
      2740992.49      6754293.95      2741027.42      6754264.86
      2741078.16      6754254.89      2741127.75      6754215.17
      2741170.11      6754208.58      2741185.98      6754200.45
      2741222.86      6754159.97      2741226.00      6754111.00

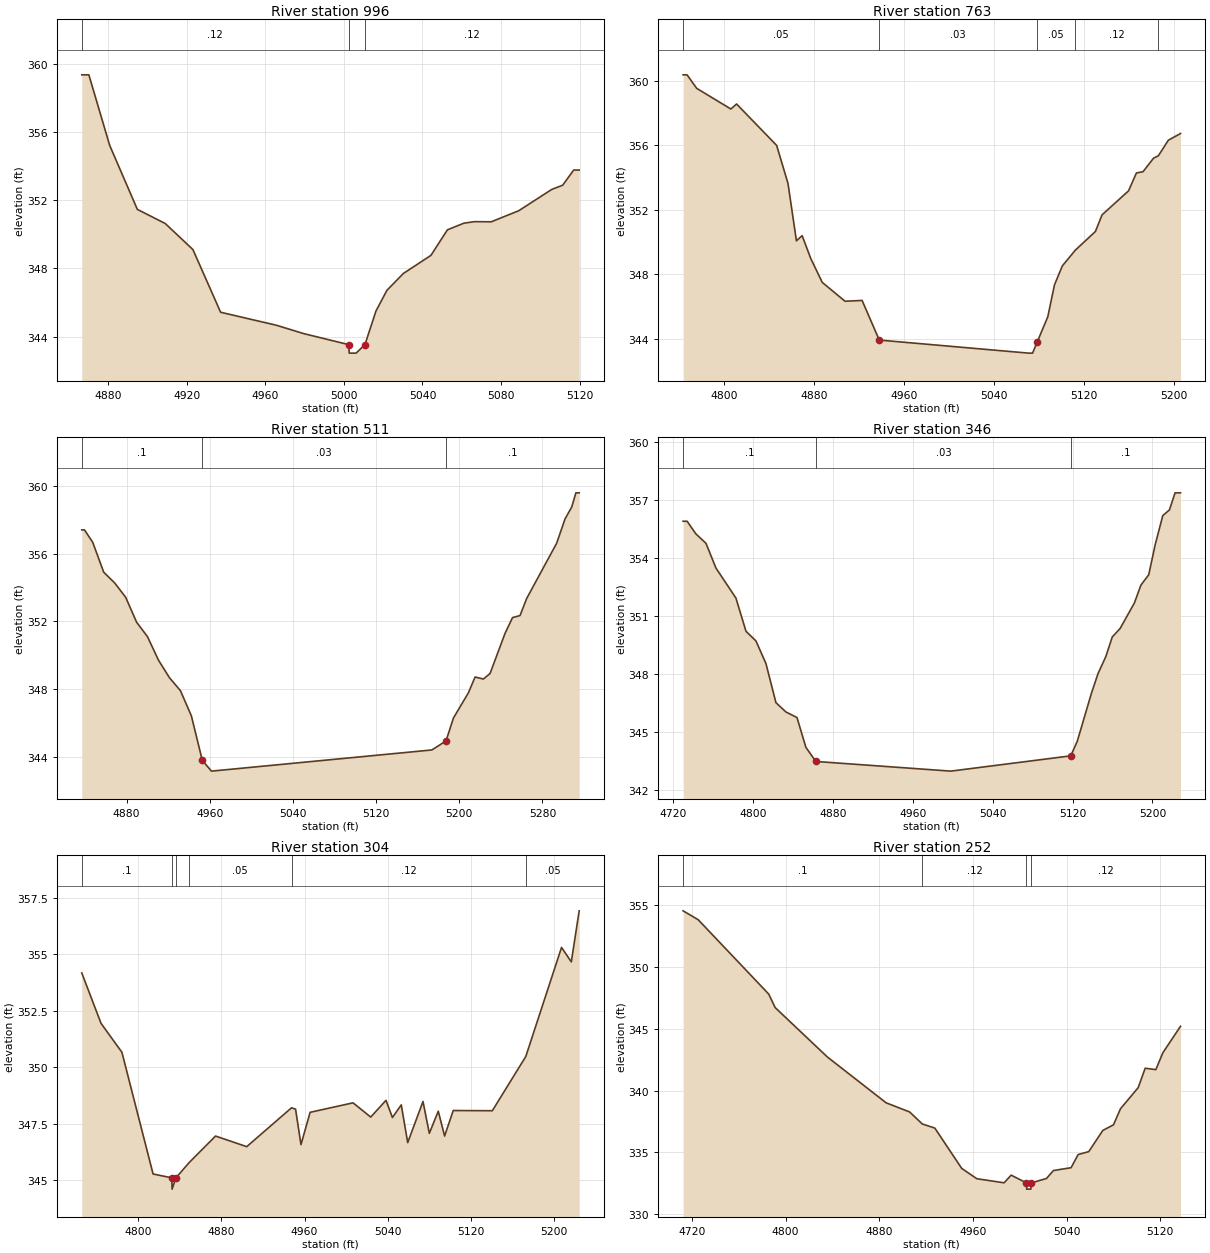
Type RM Length L Ch R = 1,996,233,233,233
BEGIN DESCRIPTION:
Walnut69 4.0
END DESCRIPTION:
XS GIS Cut Line= 3
      2740626.02      6754711.02      2740526.00      6754611.00
      2740425.96      6754560.98
#Sta/Elev= 26
  4866.5  359.37  4870.1  359.37  4880.7  355.23  4894.8  351.47  4909.0  350.64
  4923.1  349.11  4937.2  345.43  4965.5  344.67  4979.7  344.17  5002.4  343.53
  5002.7  343.03  5006.2  343.03  5010.7  343.53  5016.3  345.50  5021.9  346.72
  5030.3  347.71  5044.3  348.77  5052.7  350.27  5061.1  350.66  5066.6  350.75
  5075.0  350.74  5089.0  351.39  5105.8  352.64  5111.4  352.89  5117.0  353.78
  5119.8  353.78
#Mann=3,-1,0
  4866.5    0.12       0  5002.4    0.04       0  5010.7    0.12       0
Bank Sta=5002.4,5010.7
Exp/Cntr=0.3,0.1

Type RM Length L Ch R = 1,763,252,252,252
BEGIN DESCRIPTION:
Walnut69 3.0
END DESCRIPTION:
XS GIS Cut Line= 3
      2740769.49      6754702.91      2740735.67      6754516.89
      2740600.70      6754301.79
#Sta/Elev= 30
  4763.2  360.38  4766.7  360.38  4775.3  359.54  4805.7  358.26  4810.8  358.57
  4846.5  356.00  4856.6  353.64  4864.1  350.08  4869.2  350.40  4876.9  348.98
  4887.1  347.50  4907.4  346.33  4922.6  346.38  4937.9  343.92  5070.9  343.11
  5074.4  343.11  5078.6  343.81  5088.0  345.37  5093.9  347.34  5100.9  348.52
  5112.5  349.50  5130.4  350.66  5136.3  351.69  5159.9  353.18  5166.9  354.29
  5172.8  354.37  5182.2  355.21  5186.5  355.36  5195.3  356.32  5206.2  356.74
#Mann=5,-1,0
  4763.2    0.05       0  4937.9    0.03       0  5078.6    0.05       0
  5112.5    0.12       0  5186.5    0.05       0
Bank Sta=4937.9,5078.6
Exp/Cntr=0.3,0.1

Type RM Length L Ch R = 1,511,165,165,165
BEGIN DESCRIPTION:
Walnut69 2.0
END DESCRIPTION:
XS GIS Cut Line= 3
      2740976.00      6754610.99      2740926.00      6754461.00
      2740725.97      6754210.97
#Sta/Elev= 30
  4837.0  357.41  4839.6  357.41  4847.5  356.68  4858.1  354.91  4868.6  354.28
  4879.2  353.43  4889.7  351.96  4900.2  351.10  4910.8  349.71  4921.3  348.68
  4931.9  347.91  4942.4  346.42  4952.9  343.79  4961.7  343.16  5173.6  344.41
  5187.2  344.94  5194.4  346.30  5208.8  347.79  5215.2  348.72  5223.2  348.60
  5229.6  348.93  5244.0  351.30  5251.2  352.23  5258.4  352.35  5264.8  353.36
  5293.6  356.62  5301.7  358.06  5308.1  358.76  5312.1  359.60  5315.3  359.60
#Mann=3,-1,0
  4837.0     0.1       0  4952.9    0.03       0  5187.2     0.1       0
Bank Sta=4952.9,5187.2
Exp/Cntr=0.3,0.1

Type RM Length L Ch R = 1,346,42,42,42
BEGIN DESCRIPTION:
Walnut69 1.7
END DESCRIPTION:
XS GIS Cut Line= 5
      2741002.05      6754573.94      2741004.16      6754459.81
      2740999.93      6754339.31      2740947.08      6754252.63
      2740822.33      6754149.03
#Sta/Elev= 30
  4729.8  355.89  4733.8  355.89  4742.7  355.23  4752.7  354.75  4762.7  353.47
  4782.7  351.92  4792.8  350.20  4802.8  349.70  4812.8  348.53  4822.8  346.51
  4832.8  346.03  4843.9  345.74  4852.8  344.20  4862.8  343.47  4998.0  342.97
  5118.2  343.76  5124.7  344.51  5139.0  347.01  5145.5  348.01  5153.3  348.89
  5159.8  349.91  5167.6  350.34  5182.0  351.67  5188.5  352.59  5196.3  353.12
  5202.8  354.68  5210.4  356.18  5217.1  356.48  5222.7  357.36  5228.2  357.36
#Mann=3,-1,0
  4729.8     0.1       0  4862.8    0.03       0  5118.2     0.1       0
Bank Sta=4862.8,5118.2
Exp/Cntr=0.3,0.1

Type RM Length L Ch R = 1,304,52,52,52
BEGIN DESCRIPTION:
Walnut69 1.5
END DESCRIPTION:
XS GIS Cut Line= 5
      2741033.75      6754529.53      2741025.30      6754339.31
      2741004.16      6754258.97      2740942.85      6754174.41
      2740850.43      6754134.50
#Sta/Elev= 30
  4745.6  354.18  4764.1  351.95  4784.2  350.67  4814.2  345.28  4832.2  345.11
  4832.5  344.61  4836.2  345.11  4848.8  345.78  4874.3  346.96  4904.3  346.49
  4947.4  348.21  4951.3  348.15  4956.5  346.58  4965.3  348.01  5006.6  348.43
  5023.6  347.80  5038.3  348.54  5044.5  347.78  5053.0  348.34  5059.2  346.67
  5073.9  348.49  5080.0  347.08  5088.6  348.06  5094.7  346.96  5103.0  348.09
  5140.6  348.08  5172.8  350.48  5207.2  355.31  5216.6  354.67  5224.2  356.93
#Mann=6,-1,0
  4745.6     0.1       0  4832.2    0.07       0  4836.2     0.1       0
  4848.8    0.05       0  4947.4    0.12       0  5172.8    0.05       0
Bank Sta=4832.2,4836.2
Exp/Cntr=0.3,0.1

Type RM Length L Ch R = 1,252,115,115,115
BEGIN DESCRIPTION:
Walnut69 1.3
END DESCRIPTION:
XS GIS Cut Line= 3
      2741084.49      6754533.82      2741101.41      6754328.74
      2740981.33      6754145.46
#Sta/Elev= 30
  4712.5  354.51  4725.4  353.79  4785.6  347.79  4791.1  346.70  4835.7  342.71
  4885.9  339.01  4906.0  338.27  4916.8  337.30  4927.5  336.97  4950.5  333.71
  4963.4  332.88  4986.7  332.55  4992.7  333.17  5005.8  332.54  5006.0  332.04
  5009.5  332.04  5009.8  332.54  5022.9  332.90  5028.8  333.54  5043.9  333.77
  5049.9  334.83  5059.0  335.07  5071.0  336.78  5080.1  337.23  5086.1  338.53
  5101.2  340.23  5107.2  341.80  5116.3  341.69  5122.3  343.05  5137.4  345.19
#Mann=4,-1,0
  4712.5     0.1       0  4916.8    0.12       0  5005.8    0.07       0
  5009.8    0.12       0
Bank Sta=5005.8,5009.8
Exp/Cntr=0.3,0.1

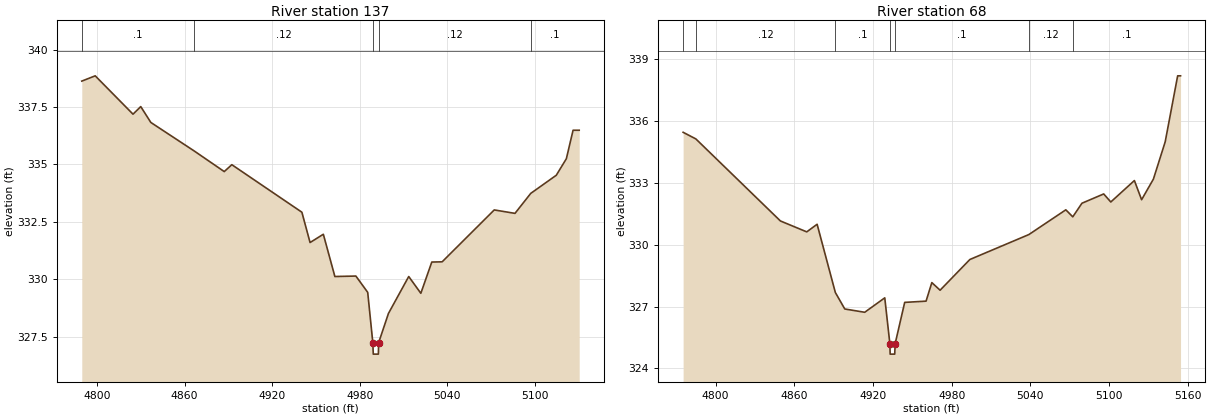
Type RM Length L Ch R = 1,137,69,69,69
BEGIN DESCRIPTION:
Walnut69 1.0
END DESCRIPTION:
XS GIS Cut Line= 4
      2741233.61      6754405.75      2741192.11      6754285.17
      2741142.00      6754182.61      2741074.70      6754109.82
#Sta/Elev= 30
  4789.6  338.63  4798.8  338.86  4824.7  337.19  4830.0  337.52  4836.9  336.83
  4866.8  335.58  4887.2  334.69  4892.4  334.99  4940.4  332.92  4946.0  331.60
  4955.1  331.96  4963.0  330.12  4977.4  330.14  4985.5  329.43  4989.0  327.24
  4989.3  326.74  4992.8  326.74  4993.0  327.24  4999.7  328.51  5013.6  330.12
  5021.9  329.39  5029.4  330.75  5036.5  330.76  5072.2  333.02  5086.4  332.87
  5097.2  333.74  5114.7  334.53  5121.6  335.25  5126.2  336.49  5130.4  336.49
#Mann=5,-1,0
  4789.6     0.1       0  4866.8    0.12       0  4989.0    0.07       0
  4993.0    0.12       0  5097.2     0.1       0
Bank Sta=4989,4993
Exp/Cntr=0.3,0.1

Type RM Length L Ch R = 1,68,0,0,0
BEGIN DESCRIPTION:
Walnut69 0.3
END DESCRIPTION:
XS GIS Cut Line= 5
      2741304.85      6754344.73      2741315.82      6754246.02
      2741246.14      6754201.40      2741172.54      6754144.24
      2741077.01      6754102.74
#Sta/Elev= 30
  4775.2  335.45  4784.9  335.13  4849.4  331.15  4869.5  330.62  4877.4  330.99
  4891.3  327.68  4898.5  326.88  4913.7  326.72  4929.0  327.42  4932.9  325.19
  4933.1  324.69  4936.6  324.69  4936.9  325.19  4944.2  327.20  4960.5  327.26
  4964.9  328.16  4971.2  327.79  4993.9  329.28  5038.9  330.49  5067.1  331.69
  5072.4  331.35  5079.4  332.01  5096.0  332.46  5101.4  332.07  5119.4  333.11
  5124.9  332.18  5133.9  333.18  5142.9  334.99  5152.4  338.19  5154.6  338.19
#Mann=7,-1,0
  4775.2    0.05       0  4784.9    0.12       0  4891.3     0.1       0
  4932.9    0.07       0  4936.9     0.1       0  5038.9    0.12       0
  5072.4     0.1       0
Bank Sta=4932.9,4936.9
Exp/Cntr=0.3,0.1

Chan Stop Cuts=-1