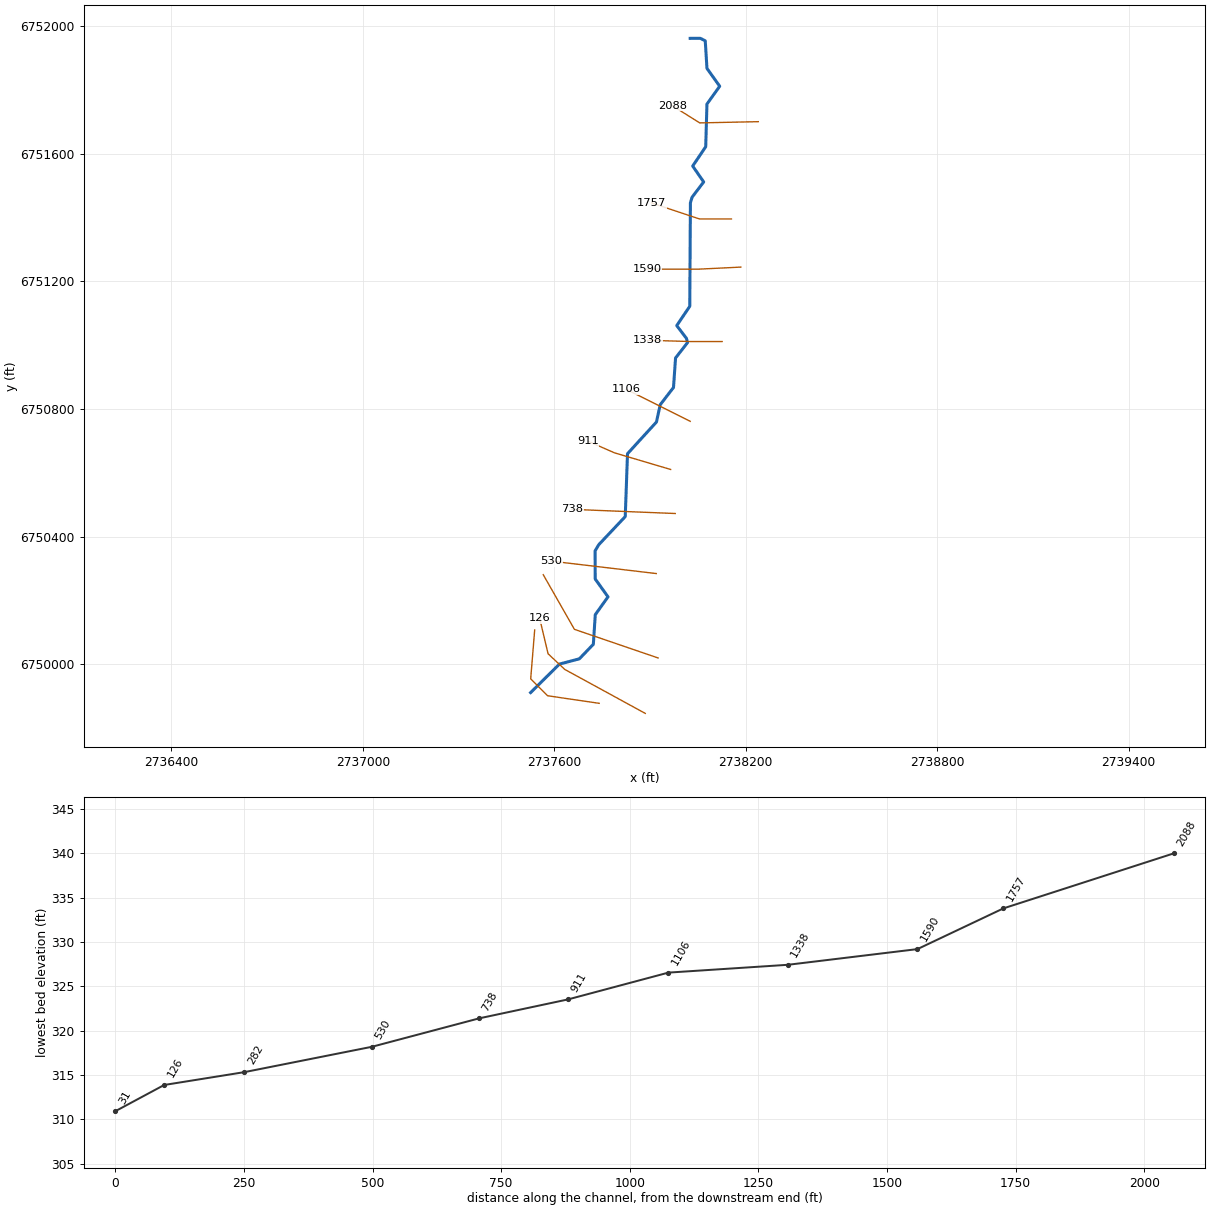
--- Walnut71.prj (project) ---

Proj Title=Walnut71 Base Level Engineering
Current Plan=p01
Default Exp/Contr=0.3,0.1
English Units
Geom File=g01
Flow File=f01
Plan File=p01
Y Axis Title=Elevation
X Axis Title(PF)=Main Channel Distance
X Axis Title(XS)=Station
BEGIN DESCRIPTION:
Walnut71
END DESCRIPTION:
DSS Export Rating Curves= 0
DSS Export Rating Curve Sorted= 0
DSS Export Volume Flow Curves= 0
DXF OffsetX= 0
DXF OffsetY= 0
DXF ScaleX= 1
DXF ScaleY= 10

--- Walnut71.p01 (plan) ---

Plan Title=Multiple Run
Program Version=4.10
Short Identifier=Multiple
Geom File=g01
Flow File=f01
Subcritical Flow
K Sum by GR= 0
Std Step Tol= 0.01
Critical Tol= 0.01
Num of Std Step Trials= 20
Max Error Tol= 0.3
Flow Tol Ratio= 0.001
Split Flow NTrial= 30
Split Flow Tol= 0.02
Split Flow Ratio= 0.02
Log Output Level= 0
Friction Slope Method= 1
Unsteady Friction Slope Method= 2
Unsteady Bridges Friction Slope Method= 1
Parabolic Critical Depth
Global Vel Dist= 1 , 1 , 1
Global Log Level= 0
CheckData=True
Encroach Param=-1 ,0,0, 0
BEGIN DESCRIPTION:
Multiple Run
END DESCRIPTION:
Computation Interval=1HOUR
Output Interval=1HOUR
Run HTab= 0
Run UNet= 0
Run PostProcess= 0
Run WQNet= 0
UNET Theta= 1
UNET Theta Warmup= 1
UNET ZTol= 0.02
UNET ZSATol= 0.05
UNET MxIter= 20
UNET MaxInSteps= 0
UNET DtIC= 0
UNET DtMin= 0
UNET MaxCRTS= 20
UNET WFStab= 2
UNET SFStab= 1
UNET WFX= 1
UNET SFX= 1
UNET DSS MLevel= 4
UNET DZMax Abort= 100
UNET Convert EG Bridges= 0
UNET Use Existing IB Tables=-1
UNET Froude Reduction=False
UNET Froude Limit= 1
UNET Froude Power= 10
UNET Time Slicing=0,0, 5
UNET Junction Losses=0
Instantaneous Interval=1HOUR
Write IC File= 0
Write IC File at Sim End=0
Echo Input=False
Echo Parameters=False
Echo Output=False
Write Detailed= 0
WQ AD Non Conservative
WQ ULTIMATE=-1
WQ Max Comp Step=1HOUR
WQ Output Interval=15MIN
WQ Output Selected Increments= 0
WQ Output face flow=0
WQ Output face velocity=0
WQ Output face area=0
WQ Output face dispersion=0
WQ Output cell volume=0
WQ Output cell surface area=0
WQ Output cell continuity=0
WQ Output cumulative cell continuity=0
WQ Output face conc=0
WQ Output face dconc_dx=0
WQ Output face courant=0
WQ Output face peclet=0
WQ Output face adv mass=0
WQ Output face disp mass=0
WQ Output cell mass=0
WQ Output cell source sink temp=0
WQ Output cell source sink nsm=0
WQ Output MaxMinRange=-1
WQ Daily Max Min Mean=-1
WQ Daily Range=0
WQ Daily Time=0
WQ Create Restart=0
WQ Fixed Restart=0
WQ System Summary=0
WQ Use Fixed Temperature=0
Sorting and Armoring Iterations= 10
XS Update Threshold= 0.02
Hydraulics Update Threshold= 0.02
Energy Slope Method= 1
Volume Change Method= 0
XS Weighting Method= 0
Number of US Weighted Cross Sections= 1
Number of DS Weighted Cross Sections= 1
Upstream XS Weight=0.25
Main XS Weight=0.5
Downstream XS Weight=0.25
Number of DS XS's Weighted with US Boundary= 1
Upstream Boundary Weight= 1
Weight of XSs Associated with US Boundary= 0
Number of US XS's Weighted with DS Boundary= 1
Downstream Boundary Weight= 0.5
Weight of XSs Associated with DS Boundary= 0.5
Sediment Output Level= 4
Mass or Volume Output= 0
Output Increment Type= 1
Profile and TS Output Increment= 10
XS Output Flag= 0
XS Output Increment= 10
Disregard all LS=0
Disregard all Conn=0
Disregard all Breaches=0
Disregard all Pumps=0

--- Walnut71.f01 (steady flow) ---

Flow Title=Multiple
Program Version=4.10
Number of Profiles= 7
Profile Names=10-year,25-year,50-year,1pct_min,100-year,1pct_plu,500-year
River Rch & RM=Walnut71,Reach-1         ,2088
     133     164     186     106     212     423     273
River Rch & RM=Walnut71,Reach-1         ,31
     297     385     453     266     531    1060     730
Boundary for River Rch & Prof#=Walnut71,Reach-1         , 1
Up Type= 0
Dn Type= 3
Dn Slope=0.03
Boundary for River Rch & Prof#=Walnut71,Reach-1         , 2
Up Type= 0
Dn Type= 3
Dn Slope=0.03
Boundary for River Rch & Prof#=Walnut71,Reach-1         , 3
Up Type= 0
Dn Type= 3
Dn Slope=0.03
Boundary for River Rch & Prof#=Walnut71,Reach-1         , 4
Up Type= 0
Dn Type= 3
Dn Slope=0.03
Boundary for River Rch & Prof#=Walnut71,Reach-1         , 5
Up Type= 0
Dn Type= 3
Dn Slope=0.03
Boundary for River Rch & Prof#=Walnut71,Reach-1         , 6
Up Type= 0
Dn Type= 3
Dn Slope=0.03
Boundary for River Rch & Prof#=Walnut71,Reach-1         , 7
Up Type= 0
Dn Type= 3
Dn Slope=0.03
DSS Import GetInterval= 0
DSS Import GetPeak= 0
DSS Import FillOption= 0

--- Walnut71.g01 (geometry) ---

Geom Title=Existing Conditions
Program Version=4.10

River Reach=Walnut71        ,Reach-1
Reach XY= 30
        2738026.        6751961.       2738057.9      6751961.08
      2738073.17      6751953.24      2738078.52      6751866.93
      2738118.45        6751811.      2738078.47      6751755.14
      2738074.61      6751621.44      2738033.79       6751560.9
      2738068.21       6751511.1        2738032.      6751463.45
      2738026.65      6751445.84      2738024.62      6751121.43
      2737983.79       6751060.9      2738014.17      6751021.05
      2738017.72      6751007.78      2737980.08       6750959.5
      2737973.67      6750866.97      2737932.14      6750813.17
      2737920.15      6750758.71      2737829.55      6750659.53
      2737822.45      6750462.47      2737739.37      6750374.29
      2737727.98       6750355.1      2737728.36       6750266.9
      2737768.44        6750211.      2737728.56       6750155.1
      2737722.48      6750062.28      2737678.58      6750016.73
      2737616.31      6750000.28        2737526.        6749911.

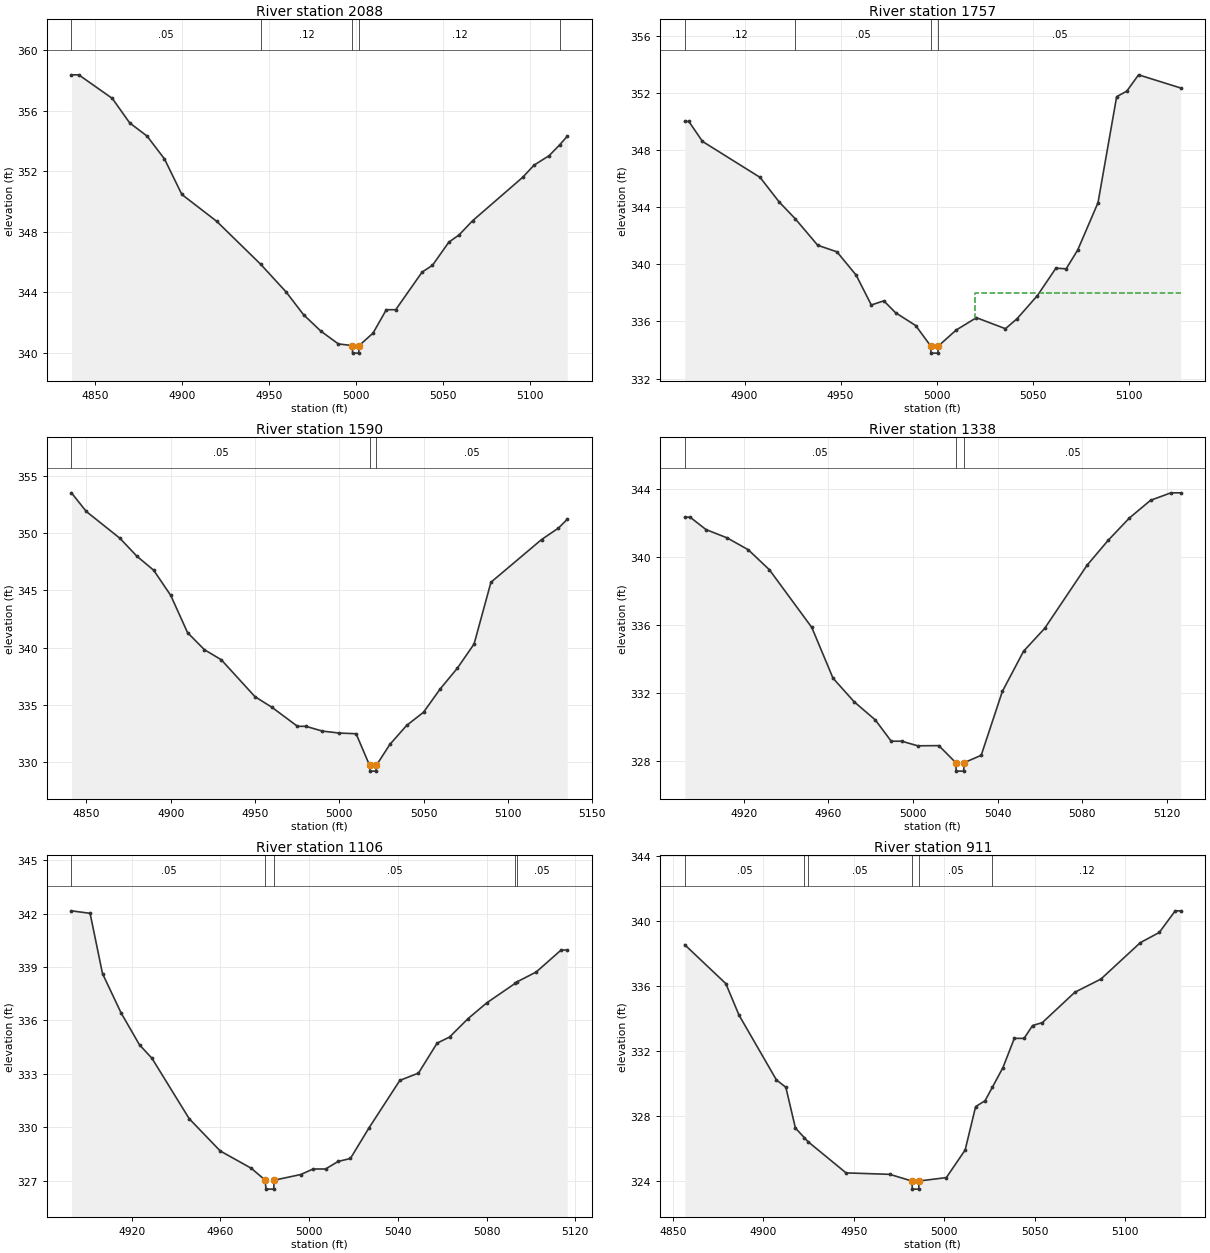
Type RM Length L Ch R = 1 ,2088    ,331,331,331
BEGIN DESCRIPTION:
Walnut71 8.0
END DESCRIPTION:
XS GIS Cut Line= 3
      2738239.45      6751699.98      2738055.87      6751696.08
      2737969.81      6751750.03
#Sta/Elev= 30
  4836.4  358.38  4840.6  358.38  4859.9  356.82  4869.9   355.2  4879.9  354.33
  4889.9  352.82  4899.9  350.47  4919.9   348.7  4945.2  345.86  4959.9  344.02
  4969.9  342.52  4979.9  341.43  4989.9  340.59  4997.9  340.48  4998.1  339.98
  5001.6  339.98  5001.9  340.48  5009.9  341.31  5017.5  342.85  5022.9  342.85
  5038.1  345.34    5044  345.78  5053.5  347.32  5059.4   347.8  5067.1  348.73
  5095.9   351.6  5102.5  352.41  5111.2  353.04  5117.2  353.75  5121.6  354.32
#Mann= 5 ,-1 , 0
  4836.4     .05       0  4945.2     .12       0  4997.9     .07       0
  5001.9     .12       0  5117.2     .05       0
Bank Sta=4997.9,5001.9
XS Rating Curve= 0 ,0
Exp/Cntr=0.3,0.1

Type RM Length L Ch R = 1 ,1757    ,167,167,167
BEGIN DESCRIPTION:
Walnut71 7.0
END DESCRIPTION:
XS GIS Cut Line= 3
      2738155.18      6751395.11      2738055.17      6751395.11
       2737905.2       6751445.1
#Sta/Elev= 30
  4868.9     350    4871     350  4878.1   348.6  4908.1  346.08  4918.1  344.35
  4926.3   343.2  4938.1  341.33  4948.1  340.87  4958.1  339.24    4966  337.15
  4972.5  337.44  4978.6  336.61  4989.1  335.71  4996.9  334.28  4997.1  333.78
  5000.6  333.78  5000.9  334.28  5010.2   335.4  5020.7  336.26  5035.8  335.49
  5041.8  336.18  5052.4   337.8  5062.1  339.73  5067.4  339.68  5073.4  340.99
    5084  344.31  5093.7  351.73    5099  352.12  5105.1  353.26    5127  352.34
#Mann= 4 ,-1 , 0
  4868.9     .12       0  4926.3     .05       0  4996.9     .04       0
  5000.9     .05       0
#XS Ineff= 2 , 0
       0                    5020       0     338
Permanent Ineff=
       F       F
Bank Sta=4996.9,5000.9
XS Rating Curve= 0 ,0
Exp/Cntr=0.3,0.1

Type RM Length L Ch R = 1 ,1590    ,252,252,252
BEGIN DESCRIPTION:
Walnut71 6.0
END DESCRIPTION:
XS GIS Cut Line= 3
      2738184.79      6751244.25      2738050.66      6751237.74
      2737890.75      6751237.74
#Sta/Elev= 30
  4841.1  353.53  4849.9   351.9  4869.9  349.55  4879.9  347.99  4889.9  346.76
    4900  344.56    4910   341.3    4920  339.81    4930  338.93    4950   335.7
    4960  334.78  4975.2  333.11  4980.2  333.11    4990  332.69    5000  332.52
    5010  332.46    5018  329.69  5018.3  329.19  5021.8  329.19    5022  329.69
    5030  331.52    5040  333.19    5050  334.34    5060   336.4    5070  338.18
    5080  340.31    5090  345.71    5120  349.44    5130  350.44  5135.3  351.22
#Mann= 3 ,-1 , 0
  4841.1     .05       0    5018     .04       0    5022     .05       0
Bank Sta=5018,5022
XS Rating Curve= 0 ,0
Exp/Cntr=0.3,0.1

Type RM Length L Ch R = 1 ,1338    ,232,232,232
BEGIN DESCRIPTION:
Walnut71 5.0
END DESCRIPTION:
XS GIS Cut Line= 3
      2738125.98        6751011.        2738026.        6751011.
      2737891.84      6751015.09
#Sta/Elev= 28
  4892.2  342.36  4894.7  342.36  4902.2  341.63  4912.2  341.14  4922.2  340.44
  4932.2  339.26  4952.2  335.87  4962.2  332.89  4972.2   331.5  4982.2  330.43
  4989.7  329.18  4994.7  329.18  5002.2  328.91  5012.2  328.92  5020.2  327.92
  5020.4  327.42  5023.9  327.42  5024.2  327.92  5032.2  328.35  5042.2  332.11
  5052.2  334.47  5062.2  335.82  5082.2  339.53  5092.2     341  5102.2  342.31
  5112.2  343.35  5121.8  343.79  5126.4  343.79
#Mann= 3 ,-1 , 0
  4892.2     .05       0  5020.2     .04       0  5024.2     .05       0
Bank Sta=5020.2,5024.2
XS Rating Curve= 0 ,0
Exp/Cntr=0.3,0.1

Type RM Length L Ch R = 1 ,1106    ,195,195,195
BEGIN DESCRIPTION:
Walnut71 4.0
END DESCRIPTION:
XS GIS Cut Line= 3
        2738026.        6750761.        2737926.        6750811.
        2737826.        6750861.
#Sta/Elev= 30
  4892.8  342.15  4901.2  342.01  4906.8  338.63  4915.2  336.42  4923.5  334.63
  4929.1  333.88  4945.9  330.49  4959.9  328.68  4973.9  327.71  4980.2  327.04
  4980.5  326.54    4984  326.54  4984.2  327.04  4996.2  327.36  5001.8  327.67
  5007.4  327.67    5013  328.09  5018.6  328.26    5027  329.98  5040.9  332.64
  5049.3  333.05  5057.7  334.73  5063.3  335.07  5071.7  336.11  5080.1  336.99
    5093  338.09  5093.8  338.17  5102.4  338.72  5113.6  339.95  5116.4  339.95
#Mann= 5 ,-1 , 0
  4892.8     .05       0  4980.2     .04       0  4984.2     .05       0
    5093     .12       0  5093.8     .05       0
Bank Sta=4980.2,4984.2
XS Rating Curve= 0 ,0
Exp/Cntr=0.3,0.1

Type RM Length L Ch R = 1 ,911     ,173,173,173
BEGIN DESCRIPTION:
Walnut71 3.0
END DESCRIPTION:
XS GIS Cut Line= 3
      2737964.72      6750610.14      2737788.94      6750662.22
       2737705.6      6750698.69
#Sta/Elev= 30
  4856.5  338.56  4879.2  336.17  4886.5  334.23  4907.2  330.24  4912.4  329.79
  4917.7  327.28  4922.7  326.68  4924.8  326.43  4945.7  324.52  4969.9  324.43
  4982.1  324.02  4982.4  323.52  4985.9  323.52  4986.1  324.02  5001.2  324.23
  5011.6  325.93  5017.4   328.6  5022.6  328.96  5026.6  329.78  5032.5     331
  5038.8   332.8  5044.2   332.8  5048.9  333.59  5054.3  333.77  5072.3  335.64
  5086.7  336.45  5108.5  338.69    5119  339.32  5127.8  340.65  5130.8  340.65
#Mann= 6 ,-1 , 0
  4856.5     .05       0  4922.7     .12       0  4924.8     .05       0
  4982.1     .04       0  4986.1     .05       0  5026.6     .12       0
Bank Sta=4982.1,4986.1
XS Rating Curve= 0 ,0
Exp/Cntr=0.3,0.1

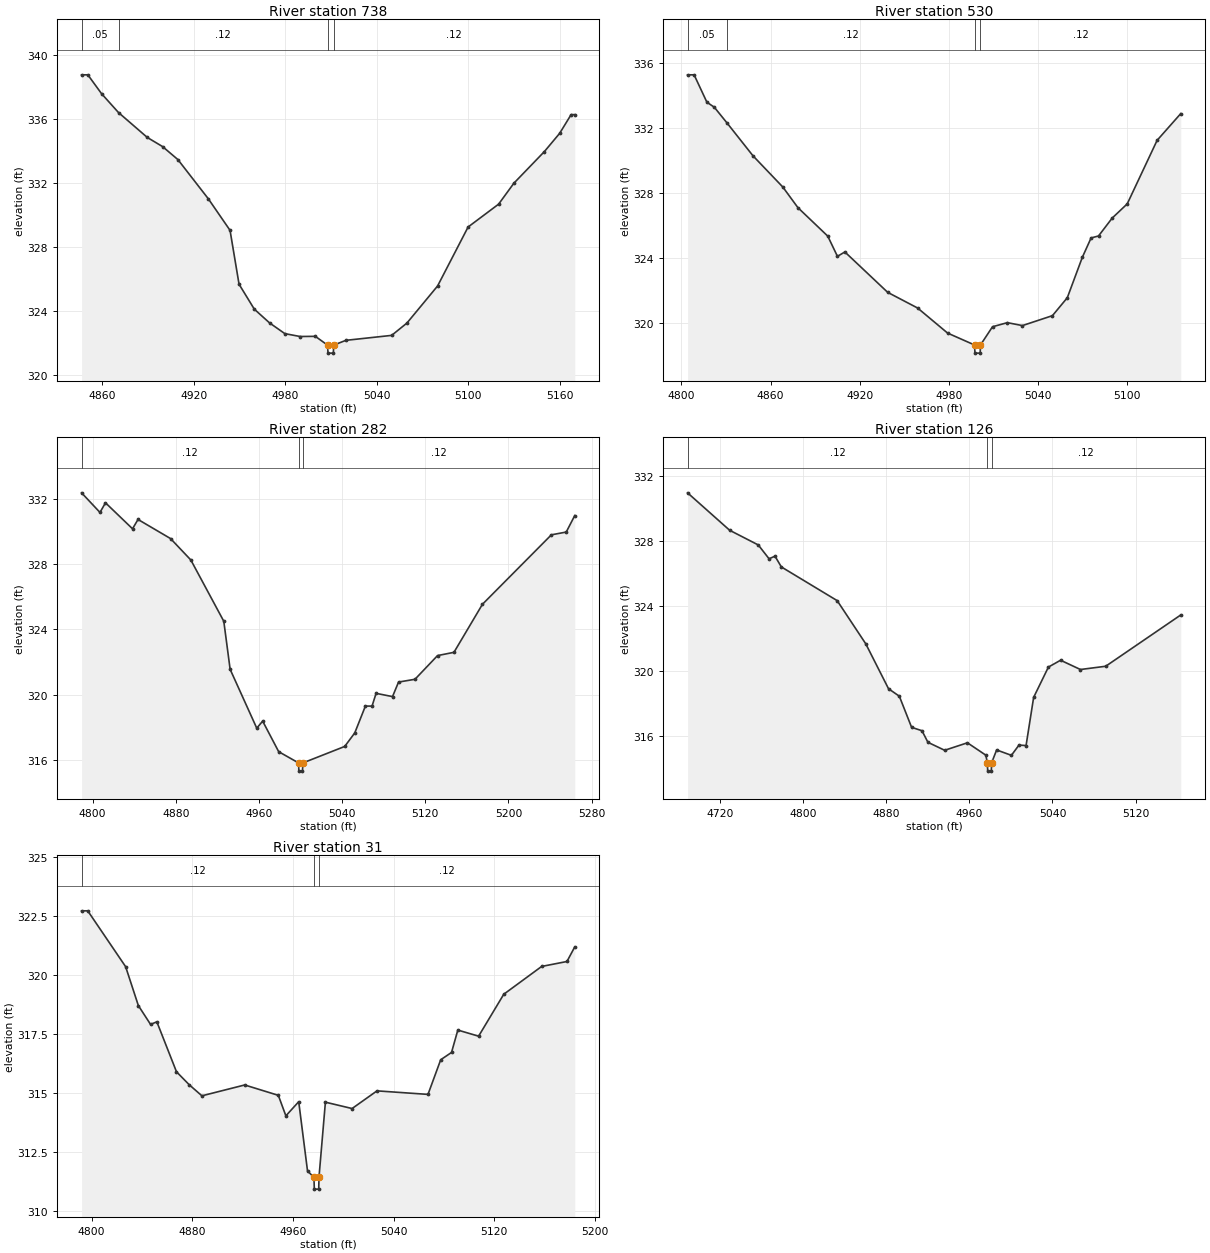
Type RM Length L Ch R = 1 ,738     ,208,208,208
BEGIN DESCRIPTION:
Walnut71 2.5
END DESCRIPTION:
XS GIS Cut Line= 2
      2737979.08      6750472.12      2737656.14      6750485.14
#Sta/Elev= 30
  4846.6  338.79  4850.7  338.79  4859.7  337.61  4870.8  336.43  4889.7  334.87
  4899.7   334.3  4909.7  333.49  4929.7  331.03  4943.9  329.06  4949.8  325.69
  4959.8  324.13  4969.8  323.27  4979.8   322.6  4989.8  322.42  4999.8  322.43
  5007.8  321.88  5008.1  321.38  5011.6  321.38  5011.8  321.88  5019.8  322.18
  5049.8  322.49  5059.8  323.26  5079.9  325.58  5099.9  329.27  5119.9   330.7
  5129.9  332.01  5149.9  333.99  5159.9  335.13  5167.4   336.3  5169.8   336.3
#Mann= 4 ,-1 , 0
  4846.6     .05       0  4870.8     .12       0  5007.8     .07       0
  5011.8     .12       0
Bank Sta=5007.8,5011.8
XS Rating Curve= 0 ,0
Exp/Cntr=0.3,0.1

Type RM Length L Ch R = 1 ,530     ,248,248,248
BEGIN DESCRIPTION:
Walnut71 2.0
END DESCRIPTION:
XS GIS Cut Line= 2
      2737919.65      6750283.98      2737590.26        6750323.
#Sta/Elev= 30
  4804.2  335.26  4808.6  335.26  4817.2  333.58  4822.2  333.27  4830.7  332.31
  4848.2  330.29  4868.3  328.37  4878.4  327.11  4898.5  325.36    4905  324.12
    4910  324.39  4938.8  321.91  4958.9  320.95  4979.1  319.41  4997.2  318.68
  4997.5  318.18    5001  318.18  5001.2  318.68  5009.3   319.8  5019.3  320.05
  5029.4  319.87  5049.6  320.48  5059.6  321.58  5069.7  324.06  5075.6  325.25
  5080.6  325.37  5089.8  326.47  5099.9  327.34    5120  331.24  5135.9  332.88
#Mann= 4 ,-1 , 0
  4804.2     .05       0  4830.7     .12       0  4997.2     .07       0
  5001.2     .12       0
Bank Sta=4997.2,5001.2
XS Rating Curve= 0 ,0
Exp/Cntr=0.3,0.1

Type RM Length L Ch R = 1 ,282     ,156,156,156
BEGIN DESCRIPTION:
Walnut71 1.5
END DESCRIPTION:
XS GIS Cut Line= 3
      2737925.44      6750019.47       2737663.2      6750109.19
      2737565.46      6750280.51
#Sta/Elev= 30
  4789.4  332.35  4807.1  331.15  4812.4  331.74  4838.4  330.15  4843.7  330.72
    4875  329.55  4894.5  328.24  4926.2  324.49  4932.3  321.55  4957.9  317.95
  4963.6  318.38    4979  316.51  4998.2  315.82  4998.4  315.32  5001.9  315.32
  5002.2  315.82  5042.5  316.83  5052.2  317.66  5062.4   319.3  5068.8   319.3
  5072.7  320.08  5088.5  319.88  5094.3  320.77  5110.1  320.94  5131.8  322.39
  5147.6  322.59    5175  325.53  5241.3  329.78  5255.6  329.95  5263.8  330.96
#Mann= 3 ,-1 , 0
  4789.4     .12       0  4998.2     .07       0  5002.2     .12       0
Bank Sta=4998.2,5002.2
XS Rating Curve= 0 ,0
Exp/Cntr=0.3,0.1

Type RM Length L Ch R = 1 ,126     ,95,95,95
BEGIN DESCRIPTION:
Walnut71 1.0
END DESCRIPTION:
XS GIS Cut Line= 4
      2737885.13      6749845.85      2737633.28      6749983.35
      2737580.63      6750032.63      2737553.95      6750144.85
#Sta/Elev= 30
    4689  330.96  4729.5  328.66    4757  327.76  4767.4  326.91  4773.1  327.07
  4779.2  326.41  4832.9  324.34  4860.4  321.69  4882.3  318.93  4892.7  318.47
  4904.5  316.56  4914.5  316.35  4920.2  315.64  4936.3  315.15  4958.2  315.61
  4975.9  314.85  4977.4  314.37  4977.7  313.87  4981.2  313.87  4981.4  314.37
  4986.3  315.17  5000.5  314.84  5007.8  315.47  5014.6  315.44  5021.9   318.4
  5036.1  320.26  5047.8  320.68  5066.9  320.11  5091.2  320.31  5163.4  323.46
#Mann= 3 ,-1 , 0
    4689     .12       0  4977.4     .07       0  4981.4     .12       0
Bank Sta=4977.4,4981.4
XS Rating Curve= 0 ,0
Exp/Cntr=0.3,0.1

Type RM Length L Ch R = 1 ,31      ,0,0,0
BEGIN DESCRIPTION:
Walnut71 0.5
END DESCRIPTION:
XS GIS Cut Line= 4
      2737740.62      6749877.37      2737579.05      6749901.09
      2737526.15      6749953.99      2737538.68      6750107.17
#Sta/Elev= 30
  4792.1  322.72    4797  322.72  4827.1  320.35  4837.2   318.7  4846.9   317.9
  4851.9  318.01  4867.5  315.89  4877.6  315.34  4887.7  314.87  4921.7  315.33
  4948.4  314.89  4954.4  314.02  4964.6  314.62  4971.6  311.68  4976.7  311.41
    4977  310.91  4980.5  310.91  4980.7  311.41  4985.8   314.6    5007  314.33
  5026.8  315.08  5067.3  314.93  5077.4   316.4    5086  316.71    5091  317.66
  5107.5   317.4  5127.5  319.18  5157.6  320.36  5177.7  320.57  5183.9  321.19
#Mann= 3 ,-1 , 0
  4792.1     .12       0  4976.7     .07       0  4980.7     .12       0
Bank Sta=4976.7,4980.7
XS Rating Curve= 0 ,0
Exp/Cntr=0.3,0.1

Chan Stop Cuts=-1
Use User Specified Reach Order=0
Composite Channel Slope=5