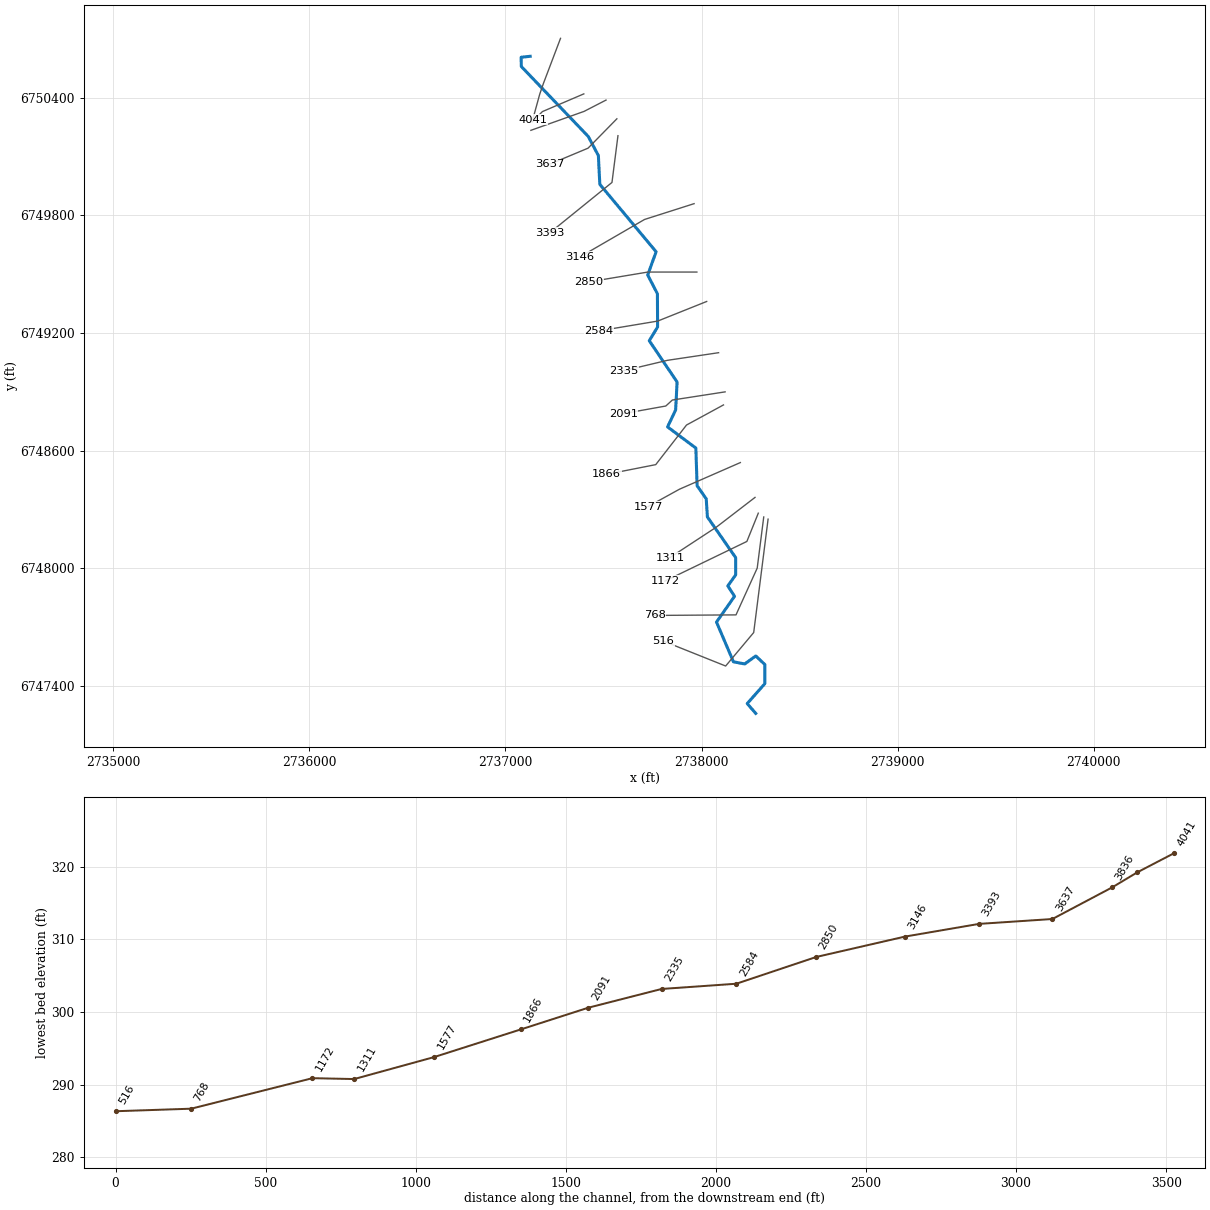
--- Walnut72.prj (project) ---

Proj Title=Walnut72 Base Level Engineering
Current Plan=p01
Default Exp/Contr=0.3,0.1
English Units
Geom File=g01
Flow File=f01
Plan File=p01
Y Axis Title=Elevation
X Axis Title(PF)=Main Channel Distance
X Axis Title(XS)=Station
BEGIN DESCRIPTION:
Walnut72
END DESCRIPTION:
DSS Export Rating Curves= 0
DSS Export Rating Curve Sorted= 0
DSS Export Volume Flow Curves= 0
DXF OffsetX= 0
DXF OffsetY= 0
DXF ScaleX= 1
DXF ScaleY= 10

--- Walnut72.p01 (plan) ---

Plan Title=Multiple Run
Program Version=4.10
Short Identifier=Multiple
Geom File=g01
Flow File=f01
Subcritical Flow
K Sum by GR= 0
Std Step Tol= 0.01
Critical Tol= 0.01
Num of Std Step Trials= 20
Max Error Tol= 0.3
Flow Tol Ratio= 0.001
Split Flow NTrial= 30
Split Flow Tol= 0.02
Split Flow Ratio= 0.02
Log Output Level= 0
Friction Slope Method= 1
Unsteady Friction Slope Method= 2
Unsteady Bridges Friction Slope Method= 1
Parabolic Critical Depth
Global Vel Dist= 1 , 1 , 1
Global Log Level= 0
CheckData=True
Encroach Param=-1 ,0,0, 0
BEGIN DESCRIPTION:
Multiple Run
END DESCRIPTION:
Computation Interval=1HOUR
Output Interval=1HOUR
Run HTab= 0
Run UNet= 0
Run PostProcess= 0
Run WQNet= 0
UNET Theta= 1
UNET Theta Warmup= 1
UNET ZTol= 0.02
UNET ZSATol= 0.05
UNET MxIter= 20
UNET MaxInSteps= 0
UNET DtIC= 0
UNET DtMin= 0
UNET MaxCRTS= 20
UNET WFStab= 2
UNET SFStab= 1
UNET WFX= 1
UNET SFX= 1
UNET DSS MLevel= 4
UNET DZMax Abort= 100
UNET Convert EG Bridges= 0
UNET Use Existing IB Tables=-1
UNET Froude Reduction=False
UNET Froude Limit= 1
UNET Froude Power= 10
UNET Time Slicing=0,0, 5
UNET Junction Losses=0
Instantaneous Interval=1HOUR
Write IC File= 0
Write IC File at Sim End=0
Echo Input=False
Echo Parameters=False
Echo Output=False
Write Detailed= 0
WQ AD Non Conservative
WQ ULTIMATE=-1
WQ Max Comp Step=1HOUR
WQ Output Interval=15MIN
WQ Output Selected Increments= 0
WQ Output face flow=0
WQ Output face velocity=0
WQ Output face area=0
WQ Output face dispersion=0
WQ Output cell volume=0
WQ Output cell surface area=0
WQ Output cell continuity=0
WQ Output cumulative cell continuity=0
WQ Output face conc=0
WQ Output face dconc_dx=0
WQ Output face courant=0
WQ Output face peclet=0
WQ Output face adv mass=0
WQ Output face disp mass=0
WQ Output cell mass=0
WQ Output cell source sink temp=0
WQ Output cell source sink nsm=0
WQ Output MaxMinRange=-1
WQ Daily Max Min Mean=-1
WQ Daily Range=0
WQ Daily Time=0
WQ Create Restart=0
WQ Fixed Restart=0
WQ System Summary=0
WQ Use Fixed Temperature=0
Sorting and Armoring Iterations= 10
XS Update Threshold= 0.02
Hydraulics Update Threshold= 0.02
Energy Slope Method= 1
Volume Change Method= 0
XS Weighting Method= 0
Number of US Weighted Cross Sections= 1
Number of DS Weighted Cross Sections= 1
Upstream XS Weight=0.25
Main XS Weight=0.5
Downstream XS Weight=0.25
Number of DS XS's Weighted with US Boundary= 1
Upstream Boundary Weight= 1
Weight of XSs Associated with US Boundary= 0
Number of US XS's Weighted with DS Boundary= 1
Downstream Boundary Weight= 0.5
Weight of XSs Associated with DS Boundary= 0.5
Sediment Output Level= 4
Mass or Volume Output= 0
Output Increment Type= 1
Profile and TS Output Increment= 10
XS Output Flag= 0
XS Output Increment= 10
Disregard all LS=0
Disregard all Conn=0
Disregard all Breaches=0
Disregard all Pumps=0

--- Walnut72.f01 (steady flow) ---

Flow Title=Multiple
Number of Profiles=7
Profile Names=10-year,25-year,50-year,1pct_min,100-year,1pct_plu,500-year
River Rch & RM= Walnut72,Reach-1,4041
     183     230     266     154     306     611     406
River Rch & RM= Walnut72,Reach-1,3393
     297     385     453     266     531    1060     730
Boundary for River Rch & Prof#=Walnut72,Reach-1,1
Up Type=0
Dn Type=3
Dn Slope=0.005
Boundary for River Rch & Prof#=Walnut72,Reach-1,2
Up Type=0
Dn Type=3
Dn Slope=0.005
Boundary for River Rch & Prof#=Walnut72,Reach-1,3
Up Type=0
Dn Type=3
Dn Slope=0.005
Boundary for River Rch & Prof#=Walnut72,Reach-1,4
Up Type=0
Dn Type=3
Dn Slope=0.005
Boundary for River Rch & Prof#=Walnut72,Reach-1,5
Up Type=0
Dn Type=3
Dn Slope=0.005
Boundary for River Rch & Prof#=Walnut72,Reach-1,6
Up Type=0
Dn Type=3
Dn Slope=0.005
Boundary for River Rch & Prof#=Walnut72,Reach-1,7
Up Type=0
Dn Type=3
Dn Slope=0.005

--- Walnut72.g01 (geometry) ---

Geom Title=Existing Conditions
Program Version=4.10

River Reach=Walnut72        ,Reach-1
Reach XY= 30
        2737126.        6750611.      2737079.93      6750606.08
      2737080.98      6750558.87      2737422.16      6750202.38
      2737473.77      6750105.09      2737481.15      6749958.42
       2737768.2      6749614.42      2737725.31      6749495.94
      2737774.78       6749400.5      2737775.81      6749230.98
      2737733.33       6749160.9      2737875.21       6748950.3
      2737867.68      6748807.76      2737826.58      6748721.49
      2737970.64       6748613.7      2737977.22       6748421.5
      2738023.64      6748355.02      2738029.62       6748262.5
      2738173.85      6748055.03      2738173.65      6747966.89
      2738133.81       6747910.9      2738167.99      6747857.67
      2738076.03      6747726.42      2738162.37      6747523.96
      2738219.92      6747512.98      2738276.34      6747553.75
      2738322.55      6747509.98      2738322.53       6747412.5
      2738232.59      6747310.99        2738276.        6747261.

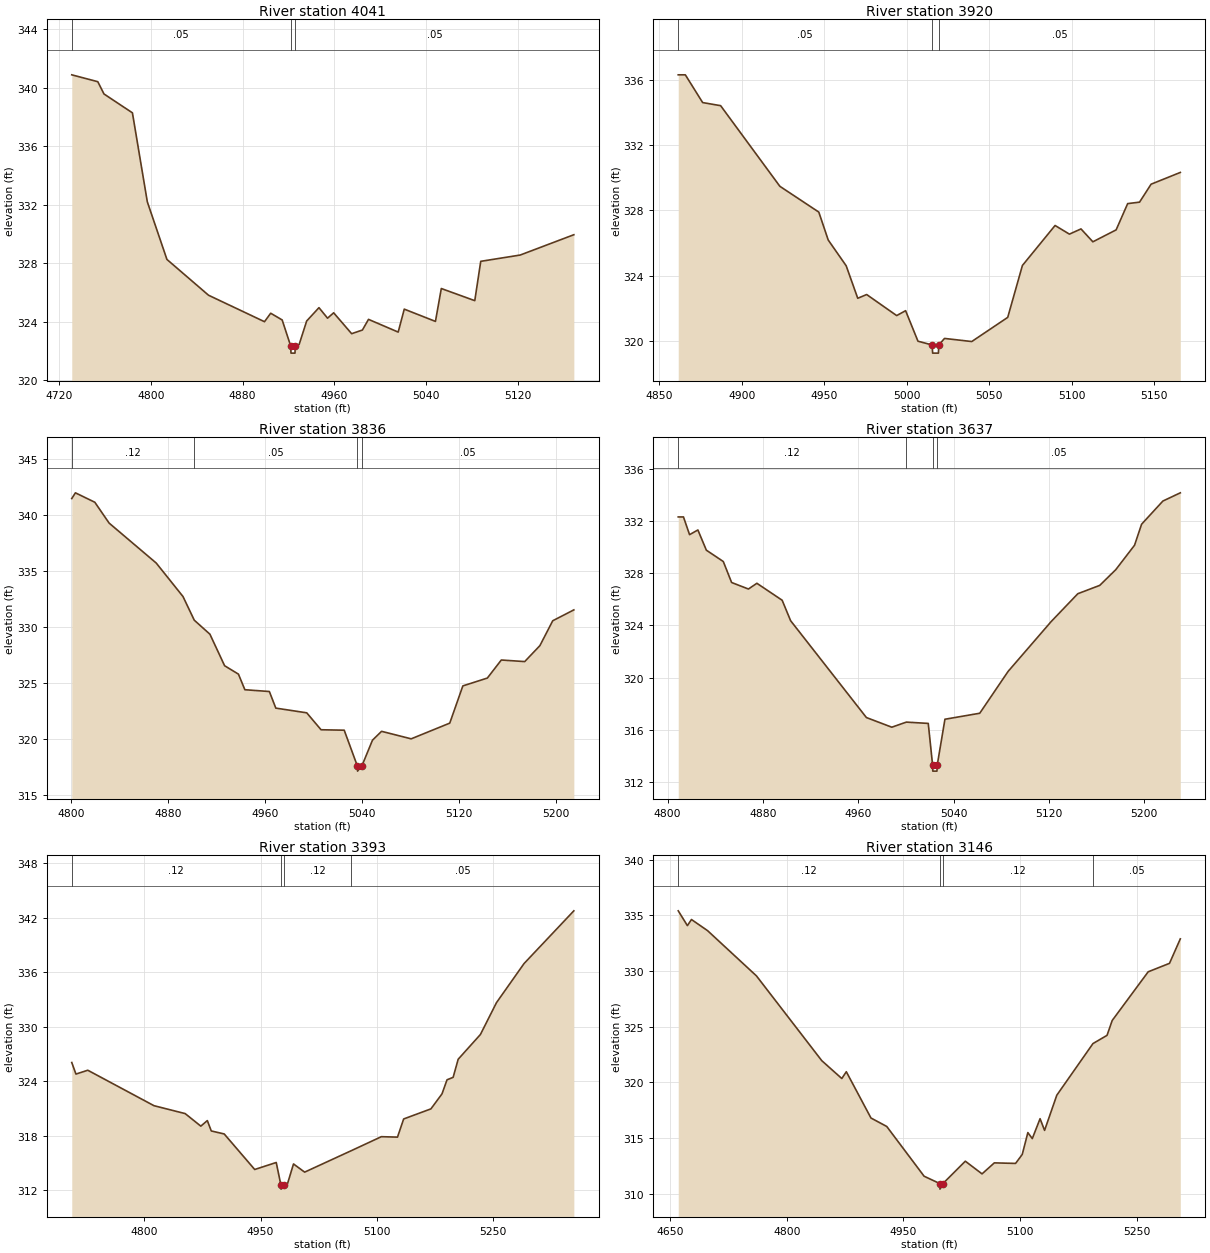
Type RM Length L Ch R = 1 ,4041    ,121,121,121
BEGIN DESCRIPTION:
Walnut72 14.0
END DESCRIPTION:
XS GIS Cut Line= 4
      2737280.84      6750702.59       2737193.7      6750472.75
      2737174.84      6750418.03      2737139.22      6750288.62
#Sta/Elev= 30
    4731  340.89  4753.7  340.42  4759.1  339.58  4783.9  338.29  4796.9   332.2
    4814  328.26  4850.3  325.81  4899.1     324  4904.5  324.58  4914.5  324.12
  4921.9  322.35  4922.2  321.85  4925.7  321.85  4925.9  322.35  4929.3  322.44
  4935.9  324.05  4946.6  324.96  4954.1  324.24  4959.4  324.61  4975.1  323.18
  4984.5  323.43  4989.8  324.16  5015.7  323.29    5021  324.86  5048.2  324.02
  5053.3  326.27  5082.5  325.44  5087.7  328.13  5122.1  328.56  5168.9  329.95
#Mann= 3 ,-1 , 0
    4731     .05       0  4921.9     .05       0  4925.9     .05       0
Bank Sta=4921.9,4925.9
XS Rating Curve= 0 ,0
Exp/Cntr=0.3,0.1

Type RM Length L Ch R = 1 ,3920    ,84,84,84
BEGIN DESCRIPTION:
Walnut72 13.0
END DESCRIPTION:
XS GIS Cut Line= 3
      2737399.59      6750419.38      2737188.25      6750328.97
      2737136.16      6750275.79
#Sta/Elev= 30
  4861.4   336.3  4865.7   336.3  4876.2   334.6  4887.1  334.41    4923  329.47
  4946.6  327.89  4952.3  326.18  4963.2   324.6  4970.2  322.61  4975.6  322.84
  4993.8  321.55  4999.2  321.85  5006.7  319.98  5015.3  319.75  5015.6  319.25
  5019.1  319.25  5019.3  319.75  5022.8  320.15  5039.3  319.96  5061.1  321.44
    5070  324.62  5089.8  327.07  5098.5  326.54  5105.5  326.86  5112.7  326.07
  5126.8   326.8  5133.8  328.41    5141   328.5    5148   329.6  5165.7  330.32
#Mann= 3 ,-1 , 0
  4861.4     .05       0  5015.3     .05       0  5019.3     .05       0
Bank Sta=5015.3,5019.3
XS Rating Curve= 0 ,0
Exp/Cntr=0.3,0.1

Type RM Length L Ch R = 1 ,3836    ,199,199,199
BEGIN DESCRIPTION:
Walnut72 12.5
END DESCRIPTION:
XS GIS Cut Line= 3
      2737512.88       6750387.8      2737400.65      6750330.06
      2737129.63      6750233.57
#Sta/Elev= 30
  4800.7  341.48  4803.7  341.99  4819.7  341.15  4831.5  339.29  4870.3  335.73
  4892.4  332.74  4901.7  330.63  4914.6  329.38  4926.7  326.57  4938.1  325.82
  4943.4  324.43  4963.6  324.27  4968.9  322.79  4994.4  322.37  5006.2  320.86
  5025.3  320.82    5036  317.67  5036.3  317.17    5040  317.67  5048.6  319.93
  5056.1  320.72  5080.5  320.05  5112.3  321.45  5123.1  324.77  5143.3  325.47
  5154.8  327.08  5174.1  326.94  5186.6  328.36  5197.2  330.58  5214.6  331.55
#Mann= 4 ,-1 , 0
  4800.7     .12       0  4901.7     .05       0    5036     .03       0
    5040     .05       0
Bank Sta=5036,5040
XS Rating Curve= 0 ,0
Exp/Cntr=0.3,0.1

Type RM Length L Ch R = 1 ,3637    ,244,244,244
BEGIN DESCRIPTION:
Walnut72 12.0
END DESCRIPTION:
XS GIS Cut Line= 3
      2737568.08       6750292.3      2737421.13      6750142.57
      2737225.99        6750061.
#Sta/Elev= 30
  4808.9  332.32  4813.3  332.32  4818.4  330.96  4825.4  331.32  4832.5  329.77
  4846.7   328.9  4853.7  327.29  4867.8  326.79  4874.9  327.23  4896.1  325.93
  4903.2  324.36  4966.8  316.93  4988.1  316.19  5000.3  316.58  5018.7  316.48
  5022.3  313.32  5022.5  312.82    5026  312.82  5026.3  313.32  5032.7   316.8
  5061.9  317.26  5085.7  320.47  5121.8  324.29  5144.2  326.43  5162.6  327.07
    5176  328.27  5191.8  330.15  5197.7  331.76  5215.6  333.54  5230.2  334.17
#Mann= 4 ,-1 , 0
  4808.9     .12       0  5000.3     .05       0  5022.3     .07       0
  5026.3     .05       0
Bank Sta=5022.3,5026.3
XS Rating Curve= 0 ,0
Exp/Cntr=0.3,0.1

Type RM Length L Ch R = 1 ,3393    ,247,247,247
BEGIN DESCRIPTION:
Walnut72 11.0
END DESCRIPTION:
XS GIS Cut Line= 3
      2737573.65      6750206.32      2737543.15      6749967.86
      2737226.01      6749711.01
#Sta/Elev= 30
  4706.2  326.08  4711.6  324.81  4726.9  325.23  4812.4  321.33  4852.7  320.46
  4872.9  319.08  4881.3  319.69  4886.4  318.55  4903.1  318.22  4942.5  314.31
  4970.3  315.08  4976.2  312.65  4976.5  312.15  4980.2  312.65  4984.7   312.7
  4992.6  314.92    5007  314.02    5067  316.37  5106.1  317.92  5126.9  317.87
  5134.9  319.87  5170.1  320.98  5184.4  322.63  5190.9  324.18  5198.8  324.45
  5205.3  326.44    5234  329.16  5254.8  332.67  5290.4  336.97  5354.7  342.77
#Mann= 4 ,-1 , 0
  4706.2     .12       0  4976.2     .07       0  4980.2     .12       0
    5067     .05       0
Bank Sta=4976.2,4980.2
XS Rating Curve= 0 ,0
Exp/Cntr=0.3,0.1

Type RM Length L Ch R = 1 ,3146    ,296,296,296
BEGIN DESCRIPTION:
Walnut72 10.0
END DESCRIPTION:
XS GIS Cut Line= 3
      2737961.87       6749859.7      2737709.54      6749779.28
      2737380.23      6749588.34
#Sta/Elev= 30
  4660.5  335.41  4672.3  334.08  4677.5  334.63  4698.2  333.63  4761.1  329.56
  4845.1  321.94  4870.8  320.34  4876.6  320.95  4908.3  316.79  4928.6  316.03
  4976.6  311.56  4996.8   310.9    4997   310.4  5000.8   310.9  5029.6  312.91
  5051.1  311.77  5066.9  312.76  5094.2  312.71  5102.8  313.52    5110  315.48
  5115.7  314.94  5125.7  316.73  5131.5  315.68  5147.2  318.84  5193.7  323.48
  5211.8  324.22  5218.4  325.55  5264.7  329.93  5292.1  330.69    5306  332.89
#Mann= 4 ,-1 , 0
  4660.5     .12       0  4996.8     .07       0  5000.8     .12       0
  5193.7     .05       0
Bank Sta=4996.8,5000.8
XS Rating Curve= 0 ,0
Exp/Cntr=0.3,0.1

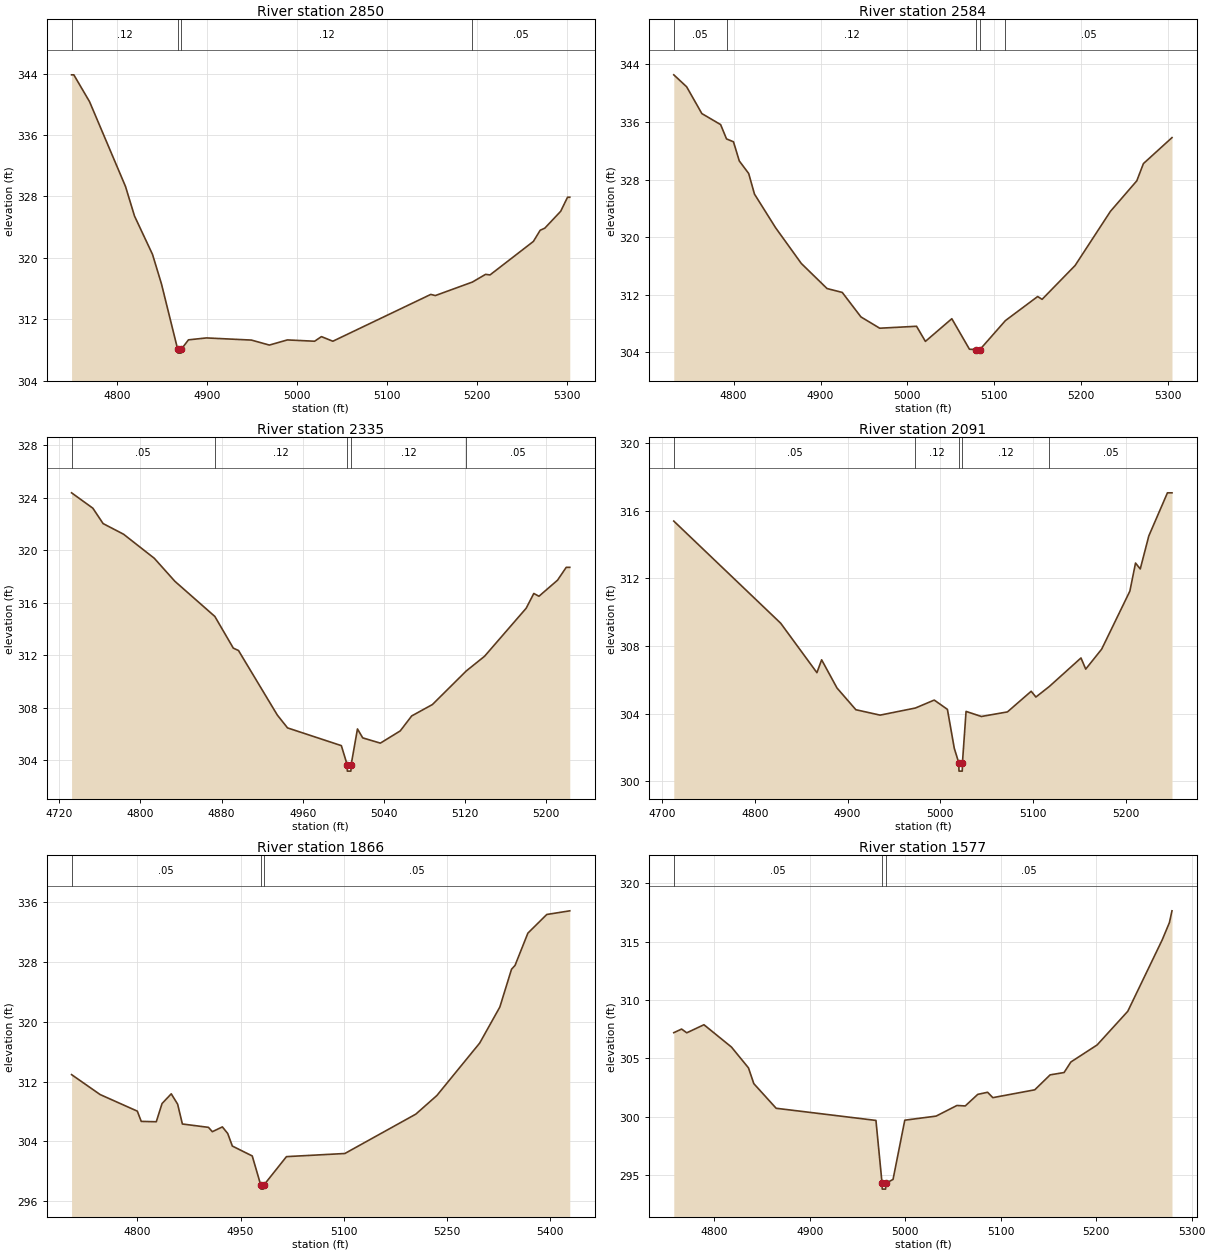
Type RM Length L Ch R = 1 ,2850    ,266,266,266
BEGIN DESCRIPTION:
Walnut72 9.0
END DESCRIPTION:
XS GIS Cut Line= 3
      2737976.01        6749511.        2737726.        6749511.
      2737426.04      6749461.01
#Sta/Elev= 30
  4749.2  343.85  4751.7  343.85  4769.2  340.35  4809.2   329.3  4819.2  325.45
  4839.2  320.46  4849.2   316.6  4867.2  308.09  4867.5  307.59    4871  307.59
  4871.2  308.09  4879.2  309.32  4899.2  309.57  4949.2  309.29  4969.2  308.64
  4989.2  309.31  5019.5  309.14  5027.1  309.74  5039.8  309.14  5148.7  315.24
  5153.8  315.09    5195  316.85  5209.6  317.85  5214.6  317.78  5262.8  322.14
  5270.4   323.6  5275.5  323.87  5293.2  326.07  5300.8   327.9  5303.3   327.9
#Mann= 4 ,-1 , 0
  4749.2     .12       0  4867.2     .07       0  4871.2     .12       0
    5195     .05       0
Bank Sta=4867.2,4871.2
XS Rating Curve= 0 ,0
Exp/Cntr=0.3,0.1

Type RM Length L Ch R = 1 ,2584    ,249,249,249
BEGIN DESCRIPTION:
Walnut72 8.0
END DESCRIPTION:
XS GIS Cut Line= 3
      2738026.03      6749361.01        2737776.        6749261.
      2737476.03        6749211.
#Sta/Elev= 30
  4731.1  342.56  4745.9   340.9  4763.4  337.18    4785  335.65  4791.8  333.66
  4799.8  333.26  4806.5   330.6  4817.3  328.86    4824  325.99  4848.3  321.32
  4877.9  316.36  4907.5  312.88    4925  312.34  4946.5  308.94  4968.1  307.37
  5010.5  307.64  5020.7  305.54  5051.1  308.69  5071.4  304.45  5079.5  304.41
  5079.7  303.91  5083.5  304.41  5112.8  308.43  5149.9  311.77    5155  311.38
    5193  316.08  5233.6  323.59    5264  327.84  5271.6  330.23  5304.5  333.84
#Mann= 5 ,-1 , 0
  4731.1     .05       0  4791.8     .12       0  5079.5     .07       0
  5083.5     .12       0  5112.8     .05       0
Bank Sta=5079.5,5083.5
XS Rating Curve= 0 ,0
Exp/Cntr=0.3,0.1

Type RM Length L Ch R = 1 ,2335    ,244,244,244
BEGIN DESCRIPTION:
Walnut72 7.0
END DESCRIPTION:
XS GIS Cut Line= 3
      2738086.74      6749099.85        2737826.        6749061.
      2737604.18      6749008.33
#Sta/Elev= 30
    4732  324.37    4753   323.2  4763.1  322.03  4783.3  321.22  4813.6  319.39
  4833.9  317.64  4873.4  314.96  4891.6  312.55  4896.7  312.37    4935  307.46
  4945.1  306.48  4998.2  305.13  5003.9  303.69  5004.1  303.19  5007.6  303.19
  5007.9  303.69  5014.1   306.4  5019.3  305.72  5036.7  305.32  5056.3  306.25
  5067.6  307.39  5088.1  308.26  5121.4  310.81  5139.5  311.93  5180.6  315.59
  5188.1  316.71  5193.2   316.5  5211.5  317.72  5220.1   318.7  5223.6   318.7
#Mann= 5 ,-1 , 0
    4732     .05       0  4873.4     .12       0  5003.9     .07       0
  5007.9     .12       0  5121.4     .05       0
Bank Sta=5003.9,5007.9
XS Rating Curve= 0 ,0
Exp/Cntr=0.3,0.1

Type RM Length L Ch R = 1 ,2091    ,225,225,225
BEGIN DESCRIPTION:
Walnut72 6.0
END DESCRIPTION:
XS GIS Cut Line= 4
      2738119.96      6748900.17      2737850.84      6748858.48
       2737817.7      6748828.07      2737601.36      6748789.24
#Sta/Elev= 30
  4712.7  315.39    4828  309.35    4867  306.43  4872.1  307.19  4888.7  305.52
    4909  304.24  4935.1  303.92  4973.2  304.34  4993.5  304.81  5007.7  304.26
  5015.1  301.96  5019.9  301.11  5020.2  300.61  5023.7  300.61  5023.9  301.11
  5027.8  304.14  5044.3  303.84  5072.4  304.11    5098  305.33  5103.1  304.99
  5117.5  305.61  5151.7   307.3  5156.8  306.64    5174  307.82  5204.4  311.25
  5210.5  312.91  5215.6  312.56  5224.8  314.51  5244.9  317.06  5249.8  317.06
#Mann= 5 ,-1 , 0
  4712.7     .05       0  4973.2     .12       0  5019.9     .05       0
  5023.9     .12       0  5117.5     .05       0
Bank Sta=5019.9,5023.9
XS Rating Curve= 0 ,0
Exp/Cntr=0.3,0.1

Type RM Length L Ch R = 1 ,1866    ,289,289,289
BEGIN DESCRIPTION:
Walnut72 5.0
END DESCRIPTION:
XS GIS Cut Line= 4
      2738111.65      6748833.61      2737923.08      6748731.01
      2737766.32      6748529.19      2737516.14      6748479.93
#Sta/Elev= 30
  4704.1  312.95  4745.7  310.28  4799.8  308.06  4805.5  306.69  4827.4  306.64
  4835.8  309.08  4849.2  310.38  4858.5  308.99  4865.4  306.34  4903.4  305.89
    4909  305.31  4923.6  305.95  4931.4  305.07  4938.1  303.39  4967.1  302.06
  4979.6  298.12  4979.8  297.62  4983.3  297.62  4983.6  298.12  5016.9  301.97
  5101.9  302.39  5205.2  307.66  5235.8  310.15  5298.2  317.18  5327.5     322
  5344.5  327.06  5349.6  327.57  5368.3  331.89  5395.8  334.39  5429.3  334.88
#Mann= 3 ,-1 , 0
  4704.1     .05       0  4979.6     .07       0  4983.6     .05       0
Bank Sta=4979.6,4983.6
XS Rating Curve= 0 ,0
Exp/Cntr=0.3,0.1

Type RM Length L Ch R = 1 ,1577    ,266,266,266
BEGIN DESCRIPTION:
Walnut72 4.0
END DESCRIPTION:
XS GIS Cut Line= 3
      2738197.63      6748539.66      2737887.03      6748403.77
      2737727.09      6748315.52
#Sta/Elev= 30
  4757.7   307.2  4765.9  307.51  4771.3  307.19  4789.3  307.88  4818.1  305.97
  4835.9  304.19  4841.5  302.84  4864.9  300.73  4969.4  299.69  4975.8  294.31
    4976  293.81  4979.5  293.81  4979.8  294.31  4987.3  294.64  4999.6  299.71
  5032.4  300.06  5054.2  300.97  5062.9  300.93    5076  301.92  5086.3   302.1
  5091.8  301.64  5135.7  302.31  5151.8  303.59  5166.4  303.79  5173.5  304.69
    5201  306.15  5233.1  309.03  5269.2  315.15  5276.7  316.62  5279.4  317.63
#Mann= 3 ,-1 , 0
  4757.7     .05       0  4975.8     .04       0  4979.8     .05       0
Bank Sta=4975.8,4979.8
XS Rating Curve= 0 ,0
Exp/Cntr=0.3,0.1

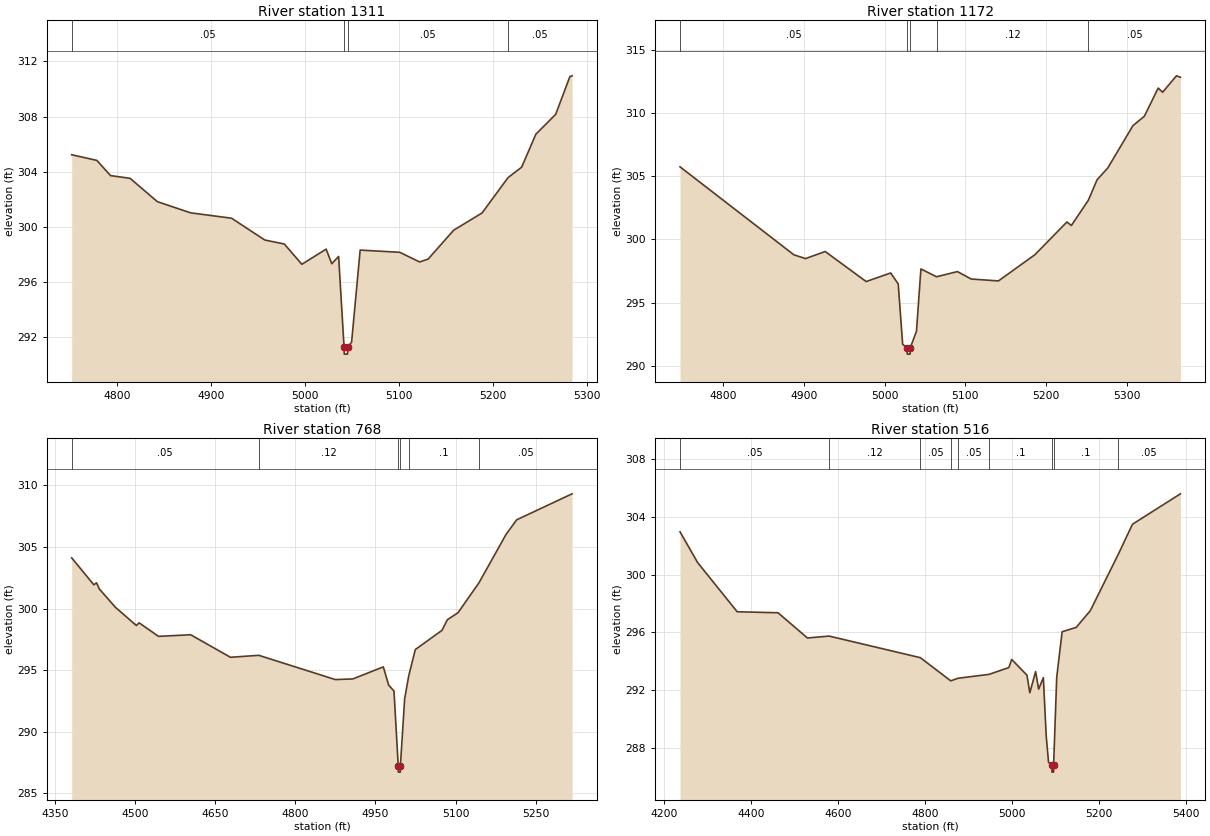
Type RM Length L Ch R = 1 ,1311    ,139,139,139
BEGIN DESCRIPTION:
Walnut72 3.0
END DESCRIPTION:
XS GIS Cut Line= 3
      2738272.47      6748362.14        2738076.        6748211.
      2737838.41      6748055.19
#Sta/Elev= 30
  4752.1  305.24  4778.9  304.83  4793.4  303.73  4814.2  303.53  4843.2  301.84
  4878.5  301.03  4922.1  300.64  4957.4  299.06  4978.2  298.77  4996.8   297.3
  5022.6   298.4  5028.6  297.34  5035.9  297.87  5041.7  291.29  5041.9  290.79
  5045.4  290.79  5045.7  291.29  5049.7  291.66  5058.8  298.33  5100.9  298.17
    5122  297.47  5131.1  297.68  5158.2  299.77  5188.4  301.02    5216  303.58
  5230.5  304.34  5245.6  306.73  5266.7  308.17  5281.8  310.91  5284.1  310.96
#Mann= 4 ,-1 , 0
  4752.1     .05       0  5041.7     .04       0  5045.7     .05       0
    5216     .05       0
Bank Sta=5041.7,5045.7
XS Rating Curve= 0 ,0
Exp/Cntr=0.3,0.1

Type RM Length L Ch R = 1 ,1172    ,404,404,404
BEGIN DESCRIPTION:
Walnut72 2.0
END DESCRIPTION:
XS GIS Cut Line= 3
      2738289.13      6748281.72      2738230.91      6748137.54
      2737813.07      6747935.53
#Sta/Elev= 30
  4746.6  305.75  4887.6  298.78    4902  298.48  4926.4  299.04  4977.1  296.66
  5007.5  297.34  5016.8  296.47  5022.3  291.69  5027.7  291.41    5028  290.91
  5031.5  290.91  5031.7  291.41  5039.4  292.72  5044.9  297.66  5064.2  297.04
  5090.1  297.45  5107.2  296.86  5140.9  296.71  5186.1  298.79  5225.7  301.38
  5231.2   301.1  5252.3  303.11    5263  304.72  5276.4  305.67  5307.4  309.01
  5321.6  309.76  5338.7  311.99  5344.2  311.66  5361.3  312.96  5366.2  312.85
#Mann= 5 ,-1 , 0
  4746.6     .05       0  5027.7     .04       0  5031.7     .05       0
  5064.2     .12       0  5252.3     .05       0
Bank Sta=5027.7,5031.7
XS Rating Curve= 0 ,0
Exp/Cntr=0.3,0.1

Type RM Length L Ch R = 1 ,768     ,252,252,252
BEGIN DESCRIPTION:
Walnut72 1.5
END DESCRIPTION:
XS GIS Cut Line= 4
      2738316.88      6748262.34       2738283.6      6748001.65
      2738175.44      6747763.15      2737762.23      6747760.38
#Sta/Elev= 30
  4380.6  304.12  4422.1  301.93  4427.2  302.09  4432.4  301.59  4462.6   300.1
  4501.9  298.62    4507  298.84  4543.3  297.74  4603.7  297.87  4678.2  296.04
  4731.3   296.2  4874.7  294.23  4907.5  294.28  4964.7  295.26  4974.7  293.78
  4984.7   293.3  4992.7  287.21    4993  286.71  4996.5  286.71  4996.7  287.21
  5004.7  292.67  5012.3  294.53  5024.7  296.67  5074.7  298.23  5084.7  299.09
  5104.7  299.66  5144.1   302.1  5194.7  306.02  5214.7  307.21  5318.5  309.32
#Mann= 6 ,-1 , 0
  4380.6     .05       0  4731.3     .12       0  4992.7     .07       0
  4996.7     .12       0  5012.3      .1       0  5144.1     .05       0
Bank Sta=4992.7,4996.7
XS Rating Curve= 0 ,0
Exp/Cntr=0.3,0.1

Type RM Length L Ch R = 1 ,516     ,0,0,0
BEGIN DESCRIPTION:
Walnut72 1.0
END DESCRIPTION:
XS GIS Cut Line= 4
      2738339.06      6748251.23       2738265.7      6747673.14
      2738122.75      6747502.47      2737803.88      6747630.02
#Sta/Elev= 30
  4237.5  302.95  4278.1  300.82  4368.8  297.43  4462.5  297.36  4530.1  295.62
  4579.9  295.75  4789.3  294.26  4859.1  292.66  4875.9  292.84  4947.3  293.11
  4992.5  293.58    4999  294.14  5034.1  293.05  5040.6  291.84  5053.9   293.3
  5060.9  292.09  5071.7  292.88  5078.2  288.88  5083.6  287.04  5091.2  286.86
  5091.5  286.36    5095  286.36  5095.2  286.86  5102.4  292.92  5114.8  296.05
  5147.1  296.35  5179.4   297.5  5243.3  301.37  5276.3  303.47  5386.3  305.57
#Mann= 9 ,-1 , 0
  4237.5     .05       0  4579.9     .12       0  4789.3     .05       0
  4859.1     .12       0  4875.9     .05       0  4947.3      .1       0
  5091.2     .07       0  5095.2      .1       0  5243.3     .05       0
Bank Sta=5091.2,5095.2
XS Rating Curve= 0 ,0
Exp/Cntr=0.3,0.1

Chan Stop Cuts=-1
Use User Specified Reach Order=0
Composite Channel Slope=5