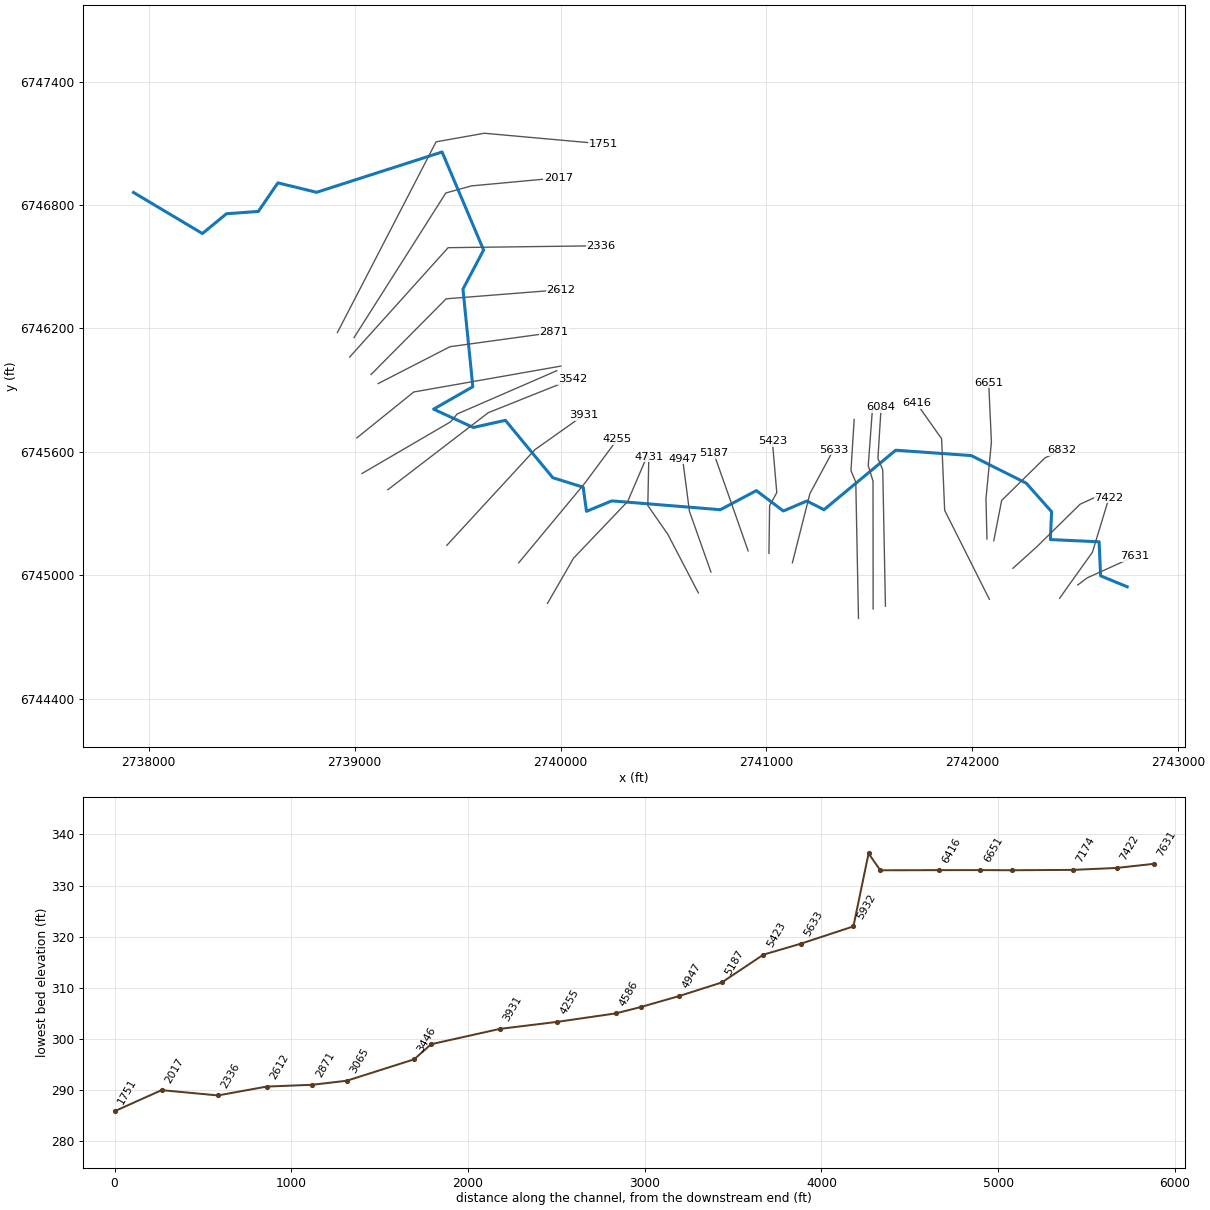
--- Walnut74.prj (project) ---

Proj Title=Walnut74 Base Level Engineering
Current Plan=p01
Default Exp/Contr=0.3,0.1
English Units
Geom File=g01
Flow File=f01
Plan File=p01
Y Axis Title=Elevation
X Axis Title(PF)=Main Channel Distance
X Axis Title(XS)=Station
BEGIN DESCRIPTION:
Walnut74
END DESCRIPTION:
DSS Export Rating Curves= 0
DSS Export Rating Curve Sorted= 0
DSS Export Volume Flow Curves= 0
DXF OffsetX= 0
DXF OffsetY= 0
DXF ScaleX= 1
DXF ScaleY= 10

--- Walnut74.p01 (plan) ---

Plan Title=Multiple Run
Program Version=4.10
Short Identifier=Multiple
Geom File=g01
Flow File=f01
Subcritical Flow
K Sum by GR= 0
Std Step Tol= 0.01
Critical Tol= 0.01
Num of Std Step Trials= 20
Max Error Tol= 0.3
Flow Tol Ratio= 0.001
Split Flow NTrial= 30
Split Flow Tol= 0.02
Split Flow Ratio= 0.02
Log Output Level= 0
Friction Slope Method= 1
Unsteady Friction Slope Method= 2
Unsteady Bridges Friction Slope Method= 1
Parabolic Critical Depth
Global Vel Dist= 1 , 1 , 1
Global Log Level= 0
CheckData=True
Encroach Param=-1 ,0,0, 0
BEGIN DESCRIPTION:
Multiple Run
END DESCRIPTION:
Computation Interval=1HOUR
Output Interval=1HOUR
Run HTab= 0
Run UNet= 0
Run PostProcess= 0
Run WQNet= 0
UNET Theta= 1
UNET Theta Warmup= 1
UNET ZTol= 0.02
UNET ZSATol= 0.05
UNET MxIter= 20
UNET MaxInSteps= 0
UNET DtIC= 0
UNET DtMin= 0
UNET MaxCRTS= 20
UNET WFStab= 2
UNET SFStab= 1
UNET WFX= 1
UNET SFX= 1
UNET DSS MLevel= 4
UNET DZMax Abort= 100
UNET Convert EG Bridges= 0
UNET Use Existing IB Tables=-1
UNET Froude Reduction=False
UNET Froude Limit= 1
UNET Froude Power= 10
UNET Time Slicing=0,0, 5
UNET Junction Losses=0
Instantaneous Interval=1HOUR
Write IC File= 0
Write IC File at Sim End=0
Echo Input=False
Echo Parameters=False
Echo Output=False
Write Detailed= 0
WQ AD Non Conservative
WQ ULTIMATE=-1
WQ Max Comp Step=1HOUR
WQ Output Interval=15MIN
WQ Output Selected Increments= 0
WQ Output face flow=0
WQ Output face velocity=0
WQ Output face area=0
WQ Output face dispersion=0
WQ Output cell volume=0
WQ Output cell surface area=0
WQ Output cell continuity=0
WQ Output cumulative cell continuity=0
WQ Output face conc=0
WQ Output face dconc_dx=0
WQ Output face courant=0
WQ Output face peclet=0
WQ Output face adv mass=0
WQ Output face disp mass=0
WQ Output cell mass=0
WQ Output cell source sink temp=0
WQ Output cell source sink nsm=0
WQ Output MaxMinRange=-1
WQ Daily Max Min Mean=-1
WQ Daily Range=0
WQ Daily Time=0
WQ Create Restart=0
WQ Fixed Restart=0
WQ System Summary=0
WQ Use Fixed Temperature=0
Sorting and Armoring Iterations= 10
XS Update Threshold= 0.02
Hydraulics Update Threshold= 0.02
Energy Slope Method= 1
Volume Change Method= 0
XS Weighting Method= 0
Number of US Weighted Cross Sections= 1
Number of DS Weighted Cross Sections= 1
Upstream XS Weight=0.25
Main XS Weight=0.5
Downstream XS Weight=0.25
Number of DS XS's Weighted with US Boundary= 1
Upstream Boundary Weight= 1
Weight of XSs Associated with US Boundary= 0
Number of US XS's Weighted with DS Boundary= 1
Downstream Boundary Weight= 0.5
Weight of XSs Associated with DS Boundary= 0.5
Sediment Output Level= 4
Mass or Volume Output= 0
Output Increment Type= 1
Profile and TS Output Increment= 10
XS Output Flag= 0
XS Output Increment= 10
Disregard all LS=0
Disregard all Conn=0
Disregard all Breaches=0
Disregard all Pumps=0

--- Walnut74.f01 (steady flow) ---

Flow Title=Multiple
Program Version=4.10
Number of Profiles= 7
Profile Names=10-year,25-year,50-year,1pct_min,100-year,1pct_plu,500-year
River Rch & RM=Walnut74,Reach-1         ,7631
     250     322     378     221     442     882     603
River Rch & RM=Walnut74,Reach-1         ,4586
     411     537     637     375     749    1494    1038
Boundary for River Rch & Prof#=Walnut74,Reach-1         , 1
Up Type= 0
Dn Type= 3
Dn Slope=0.015
Boundary for River Rch & Prof#=Walnut74,Reach-1         , 2
Up Type= 0
Dn Type= 3
Dn Slope=0.015
Boundary for River Rch & Prof#=Walnut74,Reach-1         , 3
Up Type= 0
Dn Type= 3
Dn Slope=0.015
Boundary for River Rch & Prof#=Walnut74,Reach-1         , 4
Up Type= 0
Dn Type= 3
Dn Slope=0.015
Boundary for River Rch & Prof#=Walnut74,Reach-1         , 5
Up Type= 0
Dn Type= 3
Dn Slope=0.015
Boundary for River Rch & Prof#=Walnut74,Reach-1         , 6
Up Type= 0
Dn Type= 3
Dn Slope=0.015
Boundary for River Rch & Prof#=Walnut74,Reach-1         , 7
Up Type= 0
Dn Type= 3
Dn Slope=0.015
DSS Import GetInterval= 0
DSS Import GetPeak= 0
DSS Import FillOption= 0

--- Walnut74.g01 (geometry) ---

Geom Title=Existing Conditions
Program Version=4.10

River Reach=Walnut74        ,Reach-1
Reach XY= 30
      2742752.03      6744944.05      2742622.77      6744997.21
      2742615.52      6745162.71      2742378.74      6745173.59
      2742384.78      6745308.89      2742261.56      6745447.81
      2741994.58      6745581.91      2741627.68      6745607.92
      2741279.41      6745318.82       2741196.2      6745361.19
      2741082.04      6745312.63      2740951.03       6745411.5
      2740775.92      6745318.76      2740248.74      6745361.69
        2740126.        6745311.      2740109.78      6745428.27
      2739962.35      6745474.26      2739732.17      6745753.24
        2739576.      6745718.56      2739383.38      6745807.59
      2739574.04      6745916.65      2739526.04      6746390.97
       2739626.3      6746581.17      2739424.72      6747057.63
      2738815.32      6746861.75      2738627.28      6746907.63
      2738532.47       6746768.7      2738377.47      6746757.44
      2738260.78      6746661.24        2737926.        6746861.

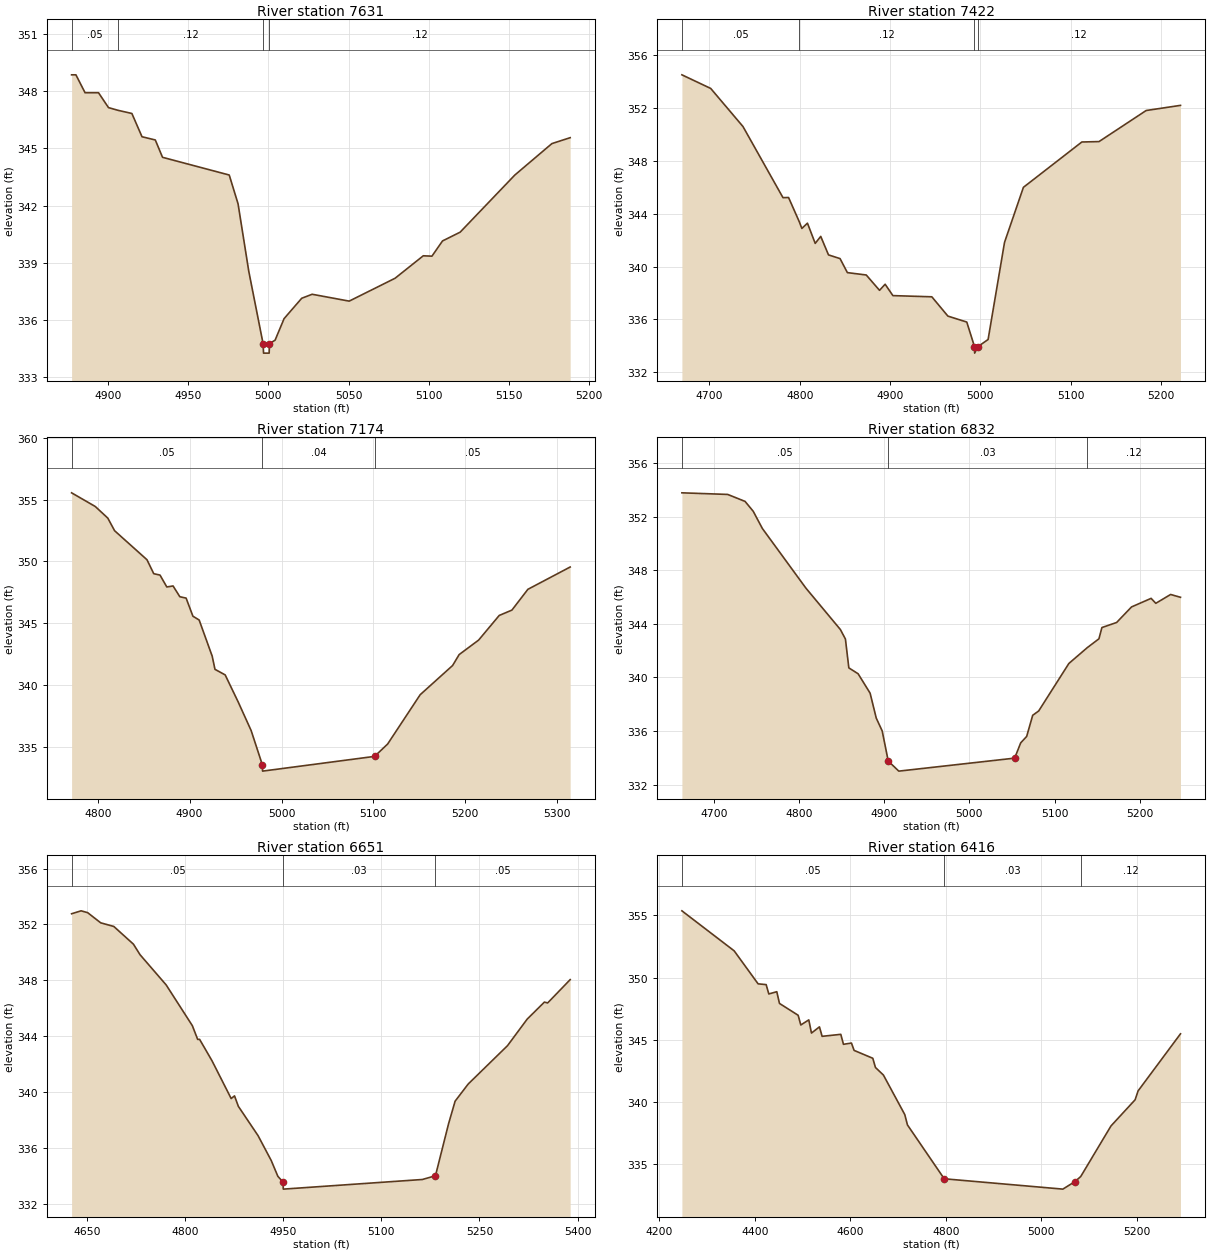
Type RM Length L Ch R = 1 ,7631    ,209,209,209
BEGIN DESCRIPTION:
Walnut74 13.0
END DESCRIPTION:
XS GIS Cut Line= 3
      2742511.74      6744952.81      2742558.13      6744987.61
      2742788.48      6745092.01
#Sta/Elev= 30
  4877.3  348.86    4880  348.86  4885.7  347.92  4894.1  347.92  4900.3  347.14
  4906.1     347  4914.9  346.83  4921.2  345.61  4929.5  345.44    4934  344.53
  4975.6   343.6  4981.1  342.09  4987.8  338.54  4996.7  334.75    4997  334.25
  5000.5  334.25  5000.7  334.75  5004.2  334.93  5009.8  336.06  5020.8  337.13
  5027.3  337.34  5050.4  336.98    5079  338.18  5096.6  339.36    5102  339.34
  5108.6  340.14  5119.6   340.6  5153.7   343.6  5176.8  345.25  5188.2  345.56
#Mann= 4 ,-1 , 0
  4877.3     .05       0  4906.1     .12       0  4996.7     .07       0
  5000.7     .12       0
Bank Sta=4996.7,5000.7
XS Rating Curve= 0 ,0
Exp/Cntr=0.3,0.1

Type RM Length L Ch R = 1 ,7422    ,248,248,248
BEGIN DESCRIPTION:
Walnut74 12.9
END DESCRIPTION:
XS GIS Cut Line= 4
      2742423.88      6744888.15      2742466.99      6744949.49
      2742582.98      6745111.89      2742663.77      6745377.32
#Sta/Elev= 30
  4669.5   354.5  4701.4  353.47  4737.1  350.59  4781.4  345.21  4787.6  345.22
  4799.5  343.38  4802.3  342.88  4808.5  343.28  4817.1  341.75  4823.2  342.28
  4831.8  340.88  4844.6   340.6  4852.7  339.54  4873.6  339.36  4888.3   338.2
  4894.5  338.66  4903.1   337.8  4946.2  337.71    4964  336.25  4984.9   335.8
  4993.4  333.95  4993.6  333.45  4997.4  333.95  5008.5  334.48  5026.7  341.83
  5047.6  345.99  5112.3  349.42  5131.3  349.45  5183.5   351.8  5221.5  352.19
#Mann= 4 ,-1 , 0
  4669.5     .05       0  4799.5     .12       0  4993.4     .07       0
  4997.4     .12       0
Bank Sta=4993.4,4997.4
XS Rating Curve= 0 ,0
Exp/Cntr=0.3,0.1

Type RM Length L Ch R = 1 ,7174    ,342,342,342
BEGIN DESCRIPTION:
Walnut74 12.8
END DESCRIPTION:
XS GIS Cut Line= 4
      2742196.91      6745034.02      2742312.88       6745138.4
      2742523.33      6745345.53      2742606.17      6745383.64
#Sta/Elev= 30
  4771.6  355.54  4797.3  354.44    4811   353.5  4818.4  352.48  4853.6  350.14
    4861  349.01  4867.8   348.9  4875.2  347.94    4882  348.02  4889.4  347.15
  4896.2  347.04  4903.6  345.58  4910.4  345.27  4924.6  342.35  4927.6  341.29
  4938.7  340.84  4952.9  338.65    4967  336.34  4979.2  333.57  4979.4  333.07
  5101.3  334.26  5115.5  335.26  5150.9  339.24  5186.2   341.6  5193.3  342.48
  5214.5  343.65  5236.9  345.64  5250.7  346.07  5268.1  347.75  5314.1  349.55
#Mann= 3 ,-1 , 0
  4771.6     .05       0  4979.2     .04       0  5101.3     .05       0
Bank Sta=4979.2,5101.3
XS Rating Curve= 0 ,0
Exp/Cntr=0.3,0.1

Type RM Length L Ch R = 1 ,6832    ,181,181,181
BEGIN DESCRIPTION:
Walnut74 12.6
END DESCRIPTION:
XS GIS Cut Line= 4
      2742104.09      6745168.22       2742142.2      6745363.76
      2742352.65       6745570.9       2742435.5      6745609.01
#Sta/Elev= 30
  4662.3  353.78  4716.1  353.66  4736.5  353.14  4746.1   352.4  4756.8  351.12
  4807.9  346.67  4848.5  343.57  4854.4  342.86  4858.4  340.71  4869.3  340.27
  4883.4  338.82  4890.6  336.96  4897.6     336  4904.7  333.75  4917.1     333
  5053.2  333.97  5060.3  335.11  5067.3  335.59  5074.4  337.17  5081.4  337.49
  5116.9  341.04  5138.7  342.23  5152.2  342.88  5155.7  343.72    5173   344.1
  5190.5  345.26  5213.5   345.9    5219  345.53  5236.4  346.19    5248  345.98
#Mann= 3 ,-1 , 0
  4662.3     .05       0  4904.7     .03       0  5138.7     .12       0
Bank Sta=4904.7,5053.2
XS Rating Curve= 0 ,0
Exp/Cntr=0.3,0.1

Type RM Length L Ch R = 1 ,6651    ,235,235,235
BEGIN DESCRIPTION:
Walnut74 12.4
END DESCRIPTION:
XS GIS Cut Line= 4
      2742070.95      6745176.53      2742065.98      6745372.05
      2742092.49      6745647.12      2742079.26      6745936.59
#Sta/Elev= 30
  4626.9  352.76  4641.4  352.97  4651.4  352.84  4671.4  352.11  4691.4  351.85
  4721.4  350.58  4731.4  349.83  4771.4  347.66  4811.4  344.74  4819.5  343.76
  4822.5  343.76  4841.5  342.22  4870.7  339.52  4875.8  339.71  4881.7  338.96
  4911.8  336.86  4931.9  335.08    4942  333.95    4950  333.53  4950.3  333.03
  5162.8  333.72  5182.8  333.99  5202.8  337.71  5212.8  339.33  5232.8  340.56
  5292.9  343.31  5322.9  345.21  5349.2  346.43  5354.2  346.37  5388.6  348.04
#Mann= 3 ,-1 , 0
  4626.9     .05       0    4950     .03       0  5182.8     .05       0
Bank Sta=4950,5182.8
XS Rating Curve= 0 ,0
Exp/Cntr=0.3,0.1

Type RM Length L Ch R = 1 ,6416    ,332,332,332
BEGIN DESCRIPTION:
Walnut74 12.2
END DESCRIPTION:
XS GIS Cut Line= 4
      2742082.54      6744883.22      2741865.47      6745315.71
      2741850.56      6745663.69      2741728.55      6745836.81
#Sta/Elev= 30
  4247.5  355.35  4356.9  352.14  4407.1  349.49  4423.9  349.43  4429.5  348.68
  4446.2  348.86  4451.8  347.92  4490.9  346.97  4496.5  346.19  4513.2   346.6
  4518.8  345.54  4535.5  346.04  4541.1  345.28  4580.2  345.44  4585.8  344.64
  4602.5  344.74  4608.1  344.15  4647.2  343.52  4652.8  342.78  4669.5  342.17
  4714.2     339  4719.8  338.17  4796.8  333.85  5045.2  333.02  5070.7  333.63
  5082.6  334.03    5146  338.09  5196.5  340.19  5202.7   340.9  5291.5  345.48
#Mann= 3 ,-1 , 0
  4247.5     .05       0  4796.8     .03       0  5082.6     .12       0
Bank Sta=4796.8,5070.7
XS Rating Curve= 0 ,0
Exp/Cntr=0.3,0.1

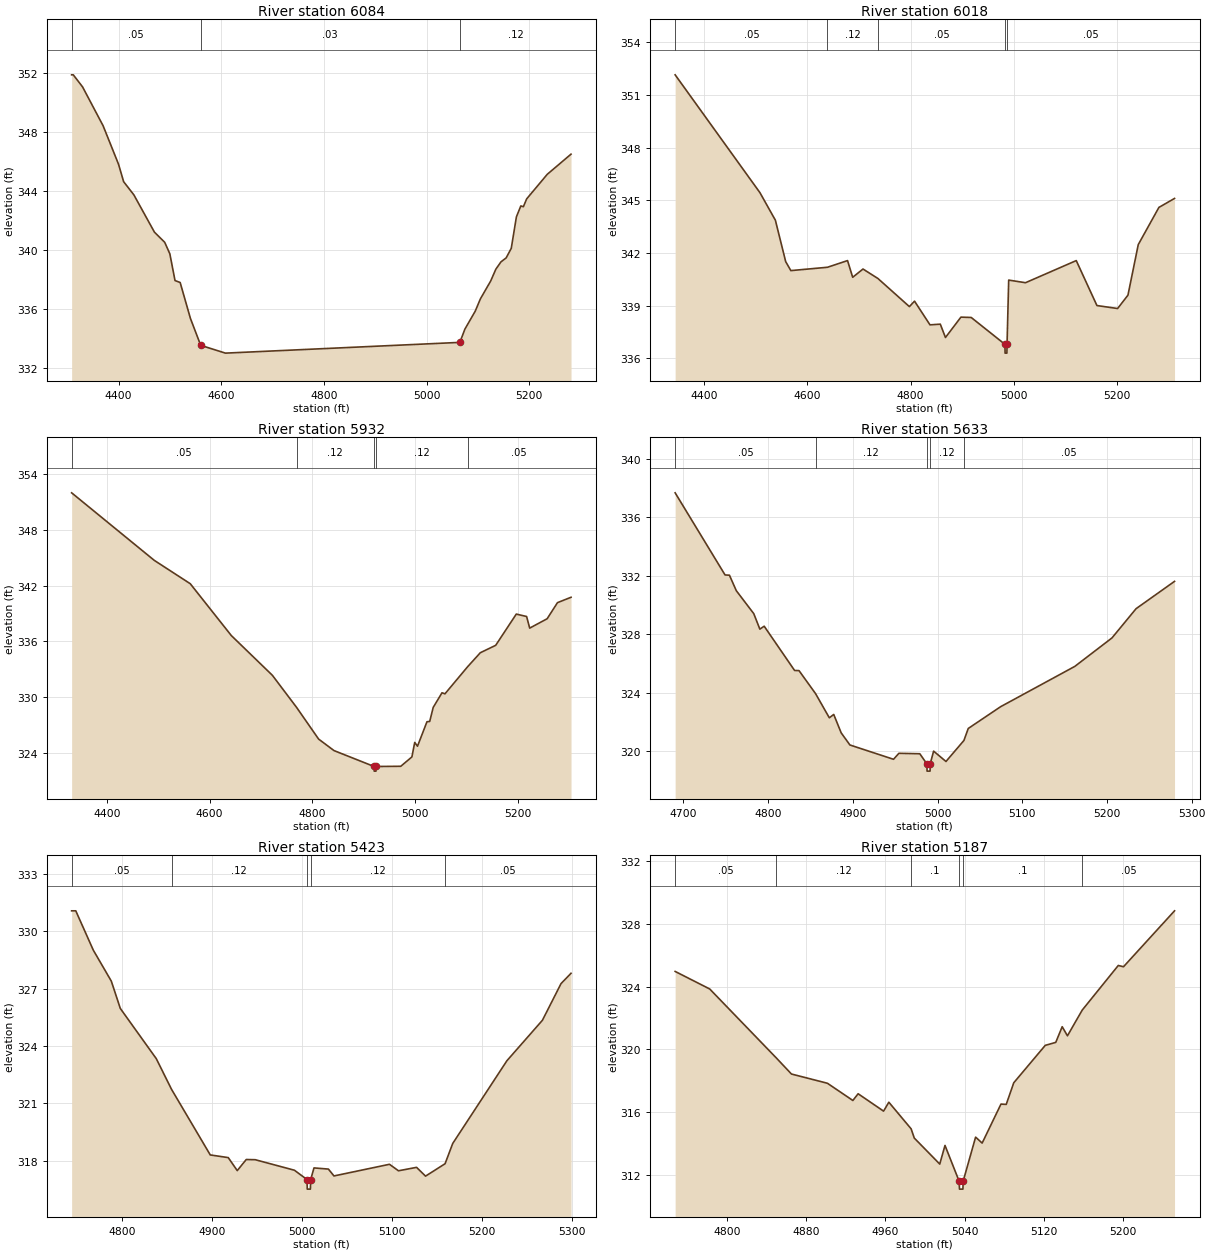
Type RM Length L Ch R = 1 ,6084    ,66,66,66
BEGIN DESCRIPTION:
Walnut74 12.0
END DESCRIPTION:
XS GIS Cut Line= 4
      2741577.79      6744849.69      2741564.75      6745512.26
      2741541.33      6745568.47      2741556.87      6745817.19
#Sta/Elev= 30
  4308.6   351.9  4311.8   351.9  4329.9  351.08  4369.9  348.44  4399.9  345.83
  4409.9  344.64  4429.9  343.74  4469.9  341.21  4489.9  340.52  4499.9  339.74
    4510  337.92    4520  337.79    4540  335.35    4560  333.52  4608.2  332.99
  5064.8  333.72  5074.8  334.63  5094.8  335.84  5104.9  336.68  5124.9  337.89
  5134.9  338.69  5144.9  339.19    5155  339.46    5165  340.11    5175  342.25
  5183.6  342.99  5188.6  342.94    5195  343.47  5235.1  345.14  5281.4  346.51
#Mann= 3 ,-1 , 0
  4308.6     .05       0    4560     .03       0  5064.8     .12       0
Bank Sta=4560,5064.8
XS Rating Curve= 0 ,0
Exp/Cntr=0.3,0.1

Type RM Length L Ch R = 1 ,6018    ,86,86,86
BEGIN DESCRIPTION:
Walnut74 11.8
END DESCRIPTION:
XS GIS Cut Line= 4
      2741518.13      6744836.46      2741517.49      6745458.22
      2741494.29      6745532.78      2741514.17       6745801.2
#Sta/Elev= 30
  4343.3  352.14  4507.8  345.43  4537.8  343.86  4557.8   341.5  4567.8  340.99
  4638.9  341.18  4677.8  341.56  4687.8  340.61  4707.8  341.08  4736.8  340.54
  4797.8  338.94  4807.8  339.25  4837.8   337.9  4857.8  337.94  4867.8  337.18
  4897.8  338.34  4917.8  338.32  4983.3  336.79  4983.5  336.29    4987  336.29
  4987.3  336.79  4990.5  340.45  5023.1   340.3  5121.6  341.56  5161.7     339
  5201.8  338.83  5221.9  339.59  5241.9  342.47    5282  344.59  5312.3   345.1
#Mann= 5 ,-1 , 0
  4343.3     .05       0  4638.9     .12       0  4736.8     .05       0
  4983.3     .05       0  4987.3     .05       0
Bank Sta=4983.3,4987.3
XS Rating Curve= 0 ,0
Exp/Cntr=0.3,0.1

Type RM Length L Ch R = 1 ,5932    ,299,299,299
BEGIN DESCRIPTION:
Walnut74 11.6
END DESCRIPTION:
XS GIS Cut Line= 4
      2741446.88      6744790.08      2741433.84      6745452.61
      2741410.42      6745508.82      2741425.96      6745757.38
#Sta/Elev= 30
  4331.2  351.98  4492.2  344.71  4562.2   342.2  4642.2  336.62  4722.2  332.34
  4769.3  328.89  4812.2  325.48  4842.2  324.24  4920.2  322.53  4920.5  322.03
    4924  322.03  4924.2  322.53  4972.2  322.55  4993.9  323.56  4999.4  325.12
  5004.8  324.71  5023.2  327.34  5028.6  327.38  5035.4  328.89  5052.5  330.46
  5058.3  330.35  5102.2  333.25  5127.1  334.77  5157.1  335.57  5197.2  338.93
  5217.3  338.67  5223.3  337.42  5257.3  338.43  5277.4  340.16  5303.8  340.74
#Mann= 5 ,-1 , 0
  4331.2     .05       0  4769.3     .12       0  4920.2     .07       0
  4924.2     .12       0  5102.2     .05       0
Bank Sta=4920.2,4924.2
XS Rating Curve= 0 ,0
Exp/Cntr=0.3,0.1

Type RM Length L Ch R = 1 ,5633    ,210,210,210
BEGIN DESCRIPTION:
Walnut74 11.0
END DESCRIPTION:
XS GIS Cut Line= 3
      2741126.01      6745061.02      2741210.93       6745396.9
      2741325.99      6745610.99
#Sta/Elev= 30
  4690.3  337.68  4749.2  332.06  4754.4  332.04  4762.5  330.98  4783.1  329.41
  4790.3  328.35  4795.4  328.55  4831.3  325.52  4836.5  325.51    4856  323.94
  4872.3  322.28  4877.5  322.51  4886.3  321.25  4896.6  320.42  4948.1  319.44
  4954.4  319.85  4979.1  319.82  4987.4  319.13  4987.7  318.63  4991.2  318.63
  4991.4  319.13  4995.4     320    5010  319.29  5031.2  320.73  5036.3  321.55
  5074.5  323.04  5162.1   325.8    5206  327.75  5234.4  329.75  5279.8  331.62
#Mann= 5 ,-1 , 0
  4690.3     .05       0    4856     .12       0  4987.4     .07       0
  4991.4     .12       0  5031.2     .05       0
Bank Sta=4987.4,4991.4
XS Rating Curve= 0 ,0
Exp/Cntr=0.3,0.1

Type RM Length L Ch R = 1 ,5423    ,236,236,236
BEGIN DESCRIPTION:
Walnut74 10.0
END DESCRIPTION:
XS GIS Cut Line= 4
      2741012.08      6745106.88      2741015.39      6745338.91
      2741050.19      6745401.87      2741028.65      6745652.05
#Sta/Elev= 30
  4743.9  331.08  4748.5  331.08    4768  329.02    4788   327.4    4798  325.97
    4838  323.34    4855  321.73    4898   318.3    4918  318.16    4928  317.48
    4938  318.06    4948  318.05  4991.5   317.5  5005.6  317.01  5005.8  316.51
  5009.3  316.51  5009.6  317.01  5013.3  317.62  5029.3  317.56  5035.5   317.2
  5097.2  317.81  5107.2  317.47  5127.3  317.65  5137.3  317.19    5159  317.84
  5167.5   318.9  5227.7  323.23  5267.2  325.35  5287.9  327.27    5299  327.81
#Mann= 5 ,-1 , 0
  4743.9     .05       0    4855     .12       0  5005.6     .07       0
  5009.6     .12       0    5159     .05       0
Bank Sta=5005.6,5009.6
XS Rating Curve= 0 ,0
Exp/Cntr=0.3,0.1

Type RM Length L Ch R = 1 ,5187    ,240,240,240
BEGIN DESCRIPTION:
Walnut74 9.0
END DESCRIPTION:
XS GIS Cut Line= 3
      2740910.99      6745118.55        2740826.        6745361.
      2740743.64      6745594.07
#Sta/Elev= 30
  4747.8  324.97  4782.7  323.85  4849.7  319.46  4865.2  318.42  4901.5  317.83
  4927.2  316.73  4932.5  317.16  4958.2  316.05  4963.5  316.62    4986  314.92
  4989.2  314.33  5014.9  312.67  5020.2  313.86  5034.5  311.57  5034.8  311.07
  5038.3  311.07  5038.5  311.57  5051.1  314.39  5057.7  314.01  5076.7   316.5
    5082  316.48  5089.6  317.86  5121.4  320.25    5132  320.44  5138.5  321.44
  5143.8  320.86  5158.7   322.5  5195.1  325.35  5200.4  325.27  5251.9  328.84
#Mann= 6 ,-1 , 0
  4747.8     .05       0  4849.7     .12       0    4986      .1       0
  5034.5     .07       0  5038.5      .1       0  5158.7     .05       0
Bank Sta=5034.5,5038.5
XS Rating Curve= 0 ,0
Exp/Cntr=0.3,0.1

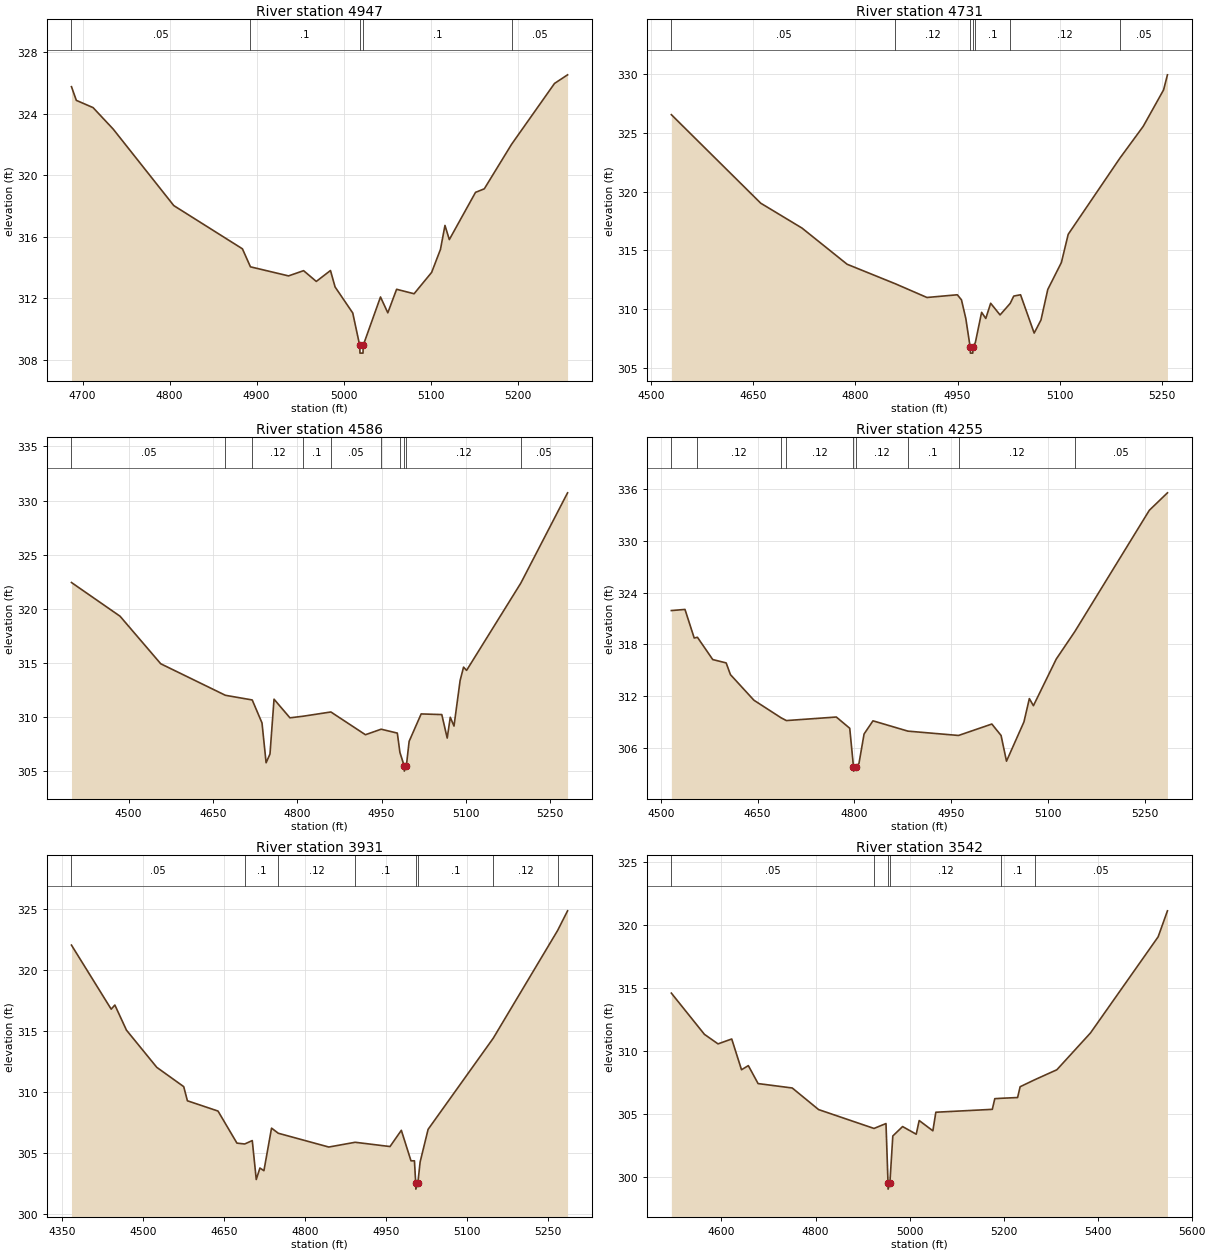
Type RM Length L Ch R = 1 ,4947    ,216,216,216
BEGIN DESCRIPTION:
Walnut74 8.0
END DESCRIPTION:
XS GIS Cut Line= 3
      2740730.39      6745015.74        2740626.        6745311.
      2740592.85      6745565.88
#Sta/Elev= 30
  4687.3  325.75  4692.9  324.86  4712.1  324.39  4735.3  322.99  4804.9  318.02
  4883.8  315.21    4893  314.04  4936.8  313.45  4954.1  313.79  4968.7  313.09
    4985   313.8  4990.3  312.73  5010.6  311.04  5018.6  308.93  5018.9  308.43
  5022.4  308.43  5022.6  308.93  5042.5  312.08  5050.9  311.05    5061  312.58
  5081.1  312.29  5101.3  313.68  5111.4  315.17  5116.6  316.73  5121.6  315.81
  5151.7  318.88  5161.8  319.11  5193.1     322  5242.5  325.96  5257.5  326.52
#Mann= 5 ,-1 , 0
  4687.3     .05       0    4893      .1       0  5018.6     .07       0
  5022.6      .1       0  5193.1     .05       0
Bank Sta=5018.6,5022.6
XS Rating Curve= 0 ,0
Exp/Cntr=0.3,0.1

Type RM Length L Ch R = 1 ,4731    ,145,145,145
BEGIN DESCRIPTION:
Walnut74 7.0
END DESCRIPTION:
XS GIS Cut Line= 4
      2740669.08      6744914.67      2740520.68      6745199.73
      2740423.82      6745338.91      2740428.77      6745576.72
#Sta/Elev= 30
  4529.6  326.52  4660.9  319.01  4721.5   316.9  4787.8  313.83  4858.8  312.17
  4905.1  311.01  4949.7  311.24  4955.8  310.81  4962.2  309.22  4968.6  306.79
  4968.9  306.29  4972.4  306.29  4972.6  306.79  4976.2  307.19  4985.4  309.75
  4991.5  309.23  4998.7  310.52  5012.5  309.53  5027.4  310.51  5032.6  311.13
  5042.6  311.24  5062.6  307.99  5072.6   309.1  5082.6  311.69  5102.6  313.98
  5112.6  316.37  5188.3  322.81  5222.7  325.52  5252.7  328.62  5258.4   329.9
#Mann= 7 ,-1 , 0
  4529.6     .05       0  4858.8     .12       0  4968.6     .07       0
  4972.6     .12       0  4976.2      .1       0  5027.4     .12       0
  5188.3     .05       0
Bank Sta=4968.6,4972.6
XS Rating Curve= 0 ,0
Exp/Cntr=0.3,0.1

Type RM Length L Ch R = 1 ,4586    ,331,331,331
BEGIN DESCRIPTION:
Walnut74 6.5
END DESCRIPTION:
XS GIS Cut Line= 4
      2739936.65      6744863.35      2740063.21      6745083.19
      2740326.05      6745358.79       2740423.5      6745586.72
#Sta/Elev= 30
  4398.5  322.43  4484.9  319.32  4557.3  314.93  4672.3  312.02    4720  311.59
  4737.4  309.47  4744.7  305.79  4751.6   306.6  4758.8  311.66  4787.1  309.94
  4810.8  310.09  4859.9  310.48  4921.4  308.38  4949.3  308.89  4978.1  308.53
  4982.7  306.75  4990.2  305.52  4990.5  305.02  4994.2  305.52  4999.1  307.77
  5020.5   310.3  5057.2  310.24  5066.8  308.07  5072.3  309.99  5078.9  309.18
  5089.8  313.39  5095.9  314.62  5101.3  314.32  5197.8  322.38  5280.9  330.71
#Mann= 10 ,-1 , 0
  4398.5     .05       0  4672.3      .1       0    4720     .12       0
  4810.8      .1       0  4859.9     .05       0  4949.3      .1       0
  4982.7     .12       0  4990.2     .07       0  4994.2     .12       0
  5197.8     .05       0
Bank Sta=4990.2,4994.2
XS Rating Curve= 0 ,0
Exp/Cntr=0.3,0.1

Type RM Length L Ch R = 1 ,4255    ,324,324,324
BEGIN DESCRIPTION:
Walnut74 6.0
END DESCRIPTION:
XS GIS Cut Line= 3
      2739796.88      6745060.59      2740117.74      6745447.51
        2740276.      6745660.99
#Sta/Elev= 30
  4516.5  321.92  4537.6  322.05  4551.9  318.75  4556.9  318.83  4580.6  316.26
  4601.4  315.87    4608  314.52  4644.4  311.56  4686.7  309.52  4694.7  309.21
    4772  309.62  4792.8  308.32  4798.6  303.87  4798.9  303.37  4802.6  303.87
  4807.1  304.26    4815  307.66  4828.8  309.18  4882.9  307.99  4961.3  307.49
  5012.9  308.81  5027.2  307.49  5035.6  304.52  5062.6  309.05    5071  311.75
  5077.3  310.93  5112.7  316.32  5141.5   319.5  5256.8   333.5  5284.9  335.52
#Mann= 9 ,-1 , 0
  4516.5     .05       0  4556.9     .12       0  4686.7      .1       0
  4694.7     .12       0  4798.6     .07       0  4802.6     .12       0
  4882.9      .1       0  4961.3     .12       0  5141.5     .05       0
Bank Sta=4798.6,4802.6
XS Rating Curve= 0 ,0
Exp/Cntr=0.3,0.1

Type RM Length L Ch R = 1 ,3931    ,389,389,389
BEGIN DESCRIPTION:
Walnut74 5.0
END DESCRIPTION:
XS GIS Cut Line= 3
      2739447.77      6745145.57        2739876.        6745611.
      2740109.98      6745776.75
#Sta/Elev= 30
  4367.3     322  4440.9  316.75  4447.7  317.09  4469.2  315.03  4525.4  311.98
  4575.3   310.4  4582.1  309.24  4638.8   308.4  4673.9  305.77  4688.3   305.7
  4702.3  305.98  4709.7  302.79  4716.5  303.73  4723.9  303.51    4738     307
  4750.5  306.58  4844.1  305.45    4893  305.84  4957.5  305.49  4978.5  306.82
  4996.4  304.32  5002.8  304.32  5005.1   302.5  5005.4     302  5009.1   302.5
  5013.3  304.22  5028.1   306.9  5148.8  314.37  5268.1   323.2  5286.5  324.81
#Mann= 8 ,-1 , 0
  4367.3     .05       0  4688.3      .1       0  4750.5     .12       0
    4893      .1       0  5005.1     .07       0  5009.1      .1       0
  5148.8     .12       0  5268.1     .05       0
Bank Sta=5005.1,5009.1
XS Rating Curve= 0 ,0
Exp/Cntr=0.3,0.1

Type RM Length L Ch R = 1 ,3542    ,96,96,96
BEGIN DESCRIPTION:
Walnut74 4.5
END DESCRIPTION:
XS GIS Cut Line= 3
      2739161.49      6745416.04      2739649.06      6745790.37
      2740057.97      6745953.93
#Sta/Elev= 30
  4493.4   314.6  4563.7  311.32  4592.7  310.56  4621.8  310.95  4642.6   308.5
  4657.1  308.83  4677.9   307.4  4750.5  307.05  4806.6  305.33  4924.4  303.83
  4949.9  304.22  4954.2   299.5  4954.4     299  4958.2   299.5  4964.4  303.23
  4985.2  303.98  5014.2  303.37  5020.5  304.46  5049.6  303.64  5055.9  305.12
    5176  305.35  5181.3   306.2  5195.1  306.23  5229.8  306.29  5235.2  307.15
  5266.5  307.71  5313.3   308.5  5384.8  311.43  5528.7  319.08  5548.5  321.15
#Mann= 6 ,-1 , 0
  4493.4     .05       0  4924.4     .12       0  4954.2     .07       0
  4958.2     .12       0  5195.1      .1       0  5266.5     .05       0
Bank Sta=4954.2,4958.2
XS Rating Curve= 0 ,0
Exp/Cntr=0.3,0.1

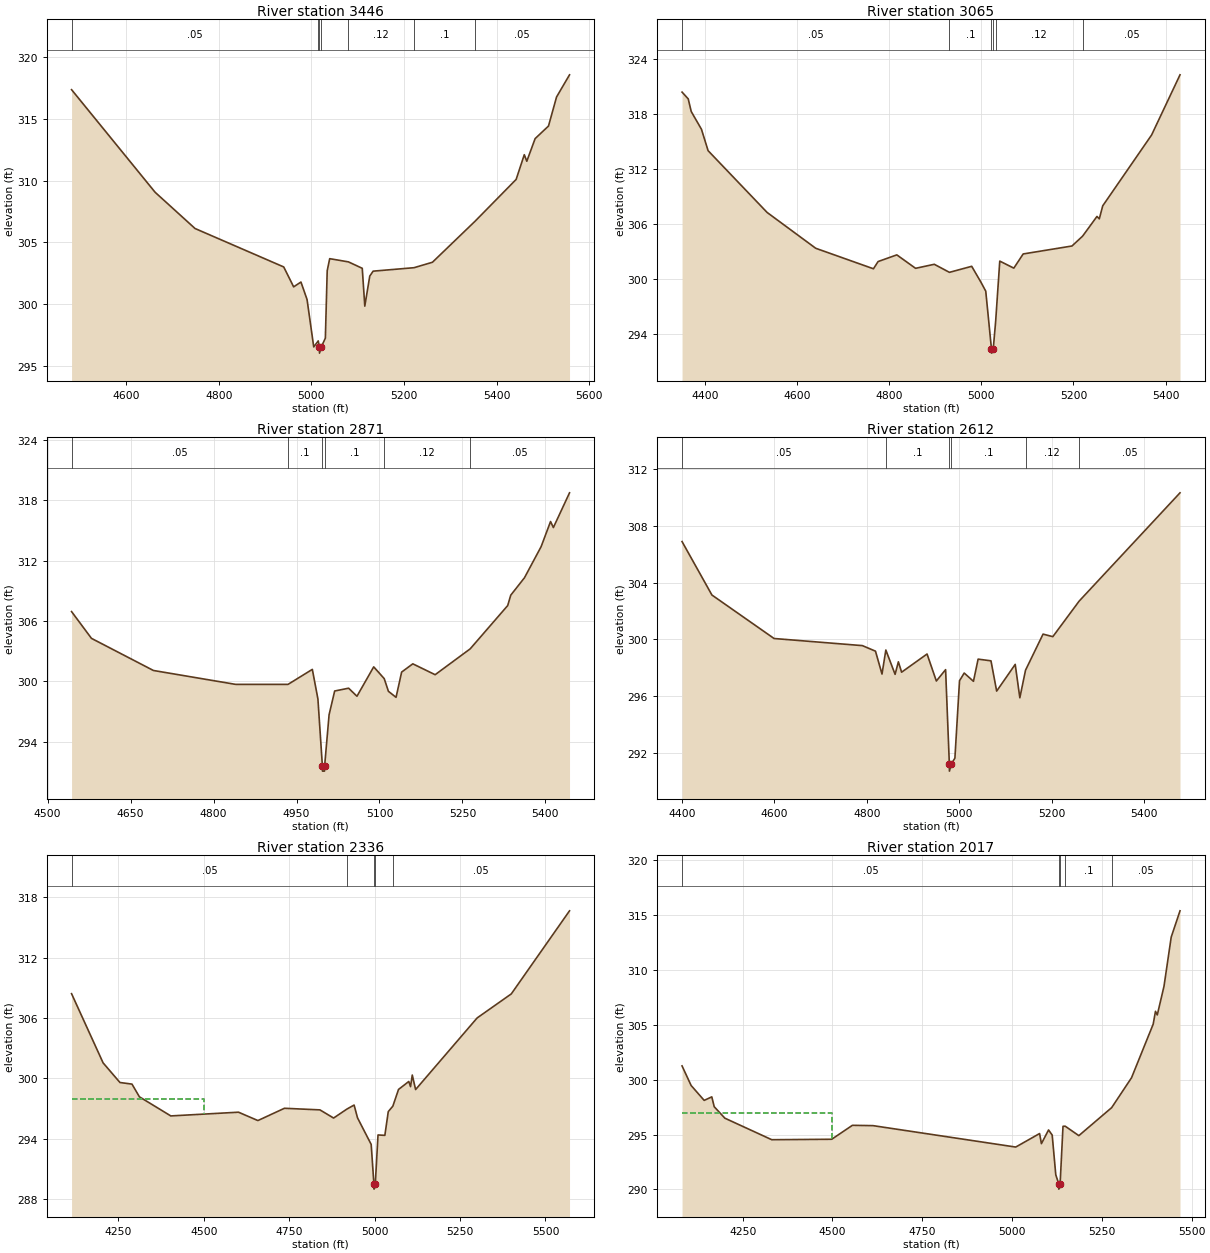
Type RM Length L Ch R = 1 ,3446    ,381,381,381
BEGIN DESCRIPTION:
Walnut74 4.3
END DESCRIPTION:
XS GIS Cut Line= 4
      2739035.68      6745494.69      2739466.62      6745746.33
      2739498.07      6745784.08      2739981.72      6745994.49
#Sta/Elev= 30
  4481.9  317.36  4662.4  309.06  4748.6  306.13  4940.2  303.02  4961.6  301.41
  4977.4   301.8  4990.6  300.38    5005  296.55  5014.7  297.04  5017.3  296.55
  5017.5  296.05  5021.3  296.55  5030.1  297.26  5034.1  302.72  5039.5  303.69
    5080  303.43  5109.8  302.91  5115.3  299.85    5126  302.28  5133.3  302.68
  5221.7  302.96  5261.4   303.4  5353.5  306.72  5442.2   310.1  5459.8   312.1
  5465.2  311.57  5483.2   313.4  5512.1  314.42  5529.5  316.77  5557.5  318.56
#Mann= 7 ,-1 , 0
  4481.9     .05       0  5014.7      .1       0  5017.3     .04       0
  5021.3      .1       0    5080     .12       0  5221.7      .1       0
  5353.5     .05       0
Bank Sta=5017.3,5021.3
XS Rating Curve= 0 ,0
Exp/Cntr=0.3,0.1

Type RM Length L Ch R = 1 ,3065    ,194,194,194
BEGIN DESCRIPTION:
Walnut74 4.0
END DESCRIPTION:
XS GIS Cut Line= 3
       2739010.5      6745667.68      2739287.32      6745891.02
      2740001.14      6746016.81
#Sta/Elev= 30
  4350.7   320.4  4364.1  319.66  4370.6  318.28  4392.8  316.34  4407.2     314
  4535.2  307.25  4640.8  303.33    4766  301.09  4776.1  301.88  4816.7  302.61
  4857.4  301.14    4898  301.58  4930.9   300.7  4979.2  301.36  4999.5   299.6
  5009.7  298.64    5022  292.37  5022.3  291.87    5026  292.37  5031.2  295.36
  5040.1  301.93  5070.6  301.16  5090.9  302.71  5196.8  303.58  5219.9  304.66
    5251  306.81  5256.1  306.55  5263.5  307.97  5369.5  315.71  5431.2  322.29
#Mann= 6 ,-1 , 0
  4350.7     .05       0  4930.9      .1       0    5022     .07       0
    5026      .1       0  5031.2     .12       0  5219.9     .05       0
Bank Sta=5022,5026
XS Rating Curve= 0 ,0
Exp/Cntr=0.3,0.1

Type RM Length L Ch R = 1 ,2871    ,259,259,259
BEGIN DESCRIPTION:
Walnut74 3.0
END DESCRIPTION:
XS GIS Cut Line= 3
      2739114.35      6745931.93      2739463.47      6746111.21
      2739966.78      6746180.42
#Sta/Elev= 30
  4543.2  306.93  4579.2  304.27  4691.2  301.08  4839.8   299.7  4934.7   299.7
  4978.6  301.19  4988.7  298.25  4996.8  291.58    4997  291.08  5000.5  291.08
  5000.8  291.58  5008.9  296.68    5019  299.04  5044.2  299.32  5059.3  298.52
  5089.6  301.44  5108.6  300.27  5116.2  299.01    5130  298.41  5140.1  300.92
  5160.3  301.74  5200.7  300.66  5264.1  303.23  5331.9  307.53  5337.4  308.56
  5362.2  310.29  5392.4  313.39  5409.4  315.88  5414.5  315.28  5443.7  318.73
#Mann= 6 ,-1 , 0
  4543.2     .05       0  4934.7      .1       0  4996.8     .07       0
  5000.8      .1       0  5108.6     .12       0  5264.1     .05       0
Bank Sta=4996.8,5000.8
XS Rating Curve= 0 ,0
Exp/Cntr=0.3,0.1

Type RM Length L Ch R = 1 ,2612    ,276,276,276
BEGIN DESCRIPTION:
Walnut74 2.0
END DESCRIPTION:
XS GIS Cut Line= 3
      2739079.69      6745975.93       2739444.6      6746343.98
      2740001.18        6746388.
#Sta/Elev= 30
  4400.5  306.88  4465.1  303.12  4599.5  300.06  4790.4  299.56  4818.7  299.17
  4832.8  297.56  4841.1  299.25  4861.1  297.54  4868.2  298.42  4875.2  297.69
  4930.2  298.97  4950.3  297.07  4970.3  297.87  4978.4  291.23  4978.6  290.73
  4982.4  291.23  4990.4  291.64  5000.4  297.09  5010.5  297.63  5030.5  297.05
  5040.6  298.61  5068.4  298.49  5080.7  296.36  5120.8  298.24  5130.8  295.89
  5143.1  297.83    5181  300.37  5202.1  300.19    5259  302.69  5477.1  310.31
#Mann= 6 ,-1 , 0
  4400.5     .05       0  4841.1      .1       0  4978.4     .07       0
  4982.4      .1       0  5143.1     .12       0    5259     .05       0
Bank Sta=4978.4,4982.4
XS Rating Curve= 0 ,0
Exp/Cntr=0.3,0.1

Type RM Length L Ch R = 1 ,2336    ,319,319,319
BEGIN DESCRIPTION:
Walnut74 1.0
END DESCRIPTION:
XS GIS Cut Line= 3
        2738976.        6746061.      2739454.04      6746592.47
      2740196.34      6746601.91
#Sta/Elev= 30
  4113.2  308.41  4205.5  301.54  4254.8  299.59    4290  299.43  4311.7  298.17
  4403.6  296.27  4601.7  296.64  4658.5  295.81  4736.2  297.03    4840  296.87
    4880  296.06  4919.4  296.96    4940  297.35    4950  296.08    4990  293.44
    4998   289.5  4998.3     289    5002   289.5    5010  294.38    5030  294.34
    5040   296.7  5053.4  297.24    5070   298.9    5100  299.69  5105.2  299.18
  5110.2  300.33    5120  298.89    5300     306    5400  308.39  5570.4  316.64
#Mann= 5 ,-1 , 0
  4113.2     .05       0  4919.4      .1       0    4998     .05       0
    5002      .1       0  5053.4     .05       0
#XS Ineff= 2 , 0
       0    4500     298               0
Permanent Ineff=
       F       F
Bank Sta=4998,5002
XS Rating Curve= 0 ,0
Exp/Cntr=0.3,0.1

Type RM Length L Ch R = 1 ,2017    ,266,266,266
BEGIN DESCRIPTION:
Walnut74 0.8
END DESCRIPTION:
XS GIS Cut Line= 4
      2738997.14      6746155.31      2739442.95      6746858.44
      2739567.51      6746892.86       2739990.4       6746932.2
#Sta/Elev= 30
  4081.2  301.25  4106.4  299.47  4142.8  298.11    4164  298.43  4170.8  297.53
  4200.4  296.49  4330.9  294.53  4497.9  294.57  4555.5  295.84  4613.1  295.81
  5010.3  293.86  5076.7  295.09  5081.8  294.17  5101.7  295.42  5111.8  294.95
  5121.8  291.33  5129.9  290.53  5130.1  290.03  5133.9  290.53  5141.9  295.75
    5148  295.76    5186   294.9  5277.4  297.45  5332.7  300.17    5393  305.05
  5399.4  306.22  5404.4  305.89  5423.1   308.5  5443.2  312.98  5467.7  315.37
#Mann= 5 ,-1 , 0
  4081.2     .05       0  5129.9     .05       0  5133.9     .05       0
    5148      .1       0  5277.4     .05       0
#XS Ineff= 2 , 0
       0    4500     297               0
Permanent Ineff=
       F       F
Bank Sta=5129.9,5133.9
XS Rating Curve= 0 ,0
Exp/Cntr=0.3,0.1

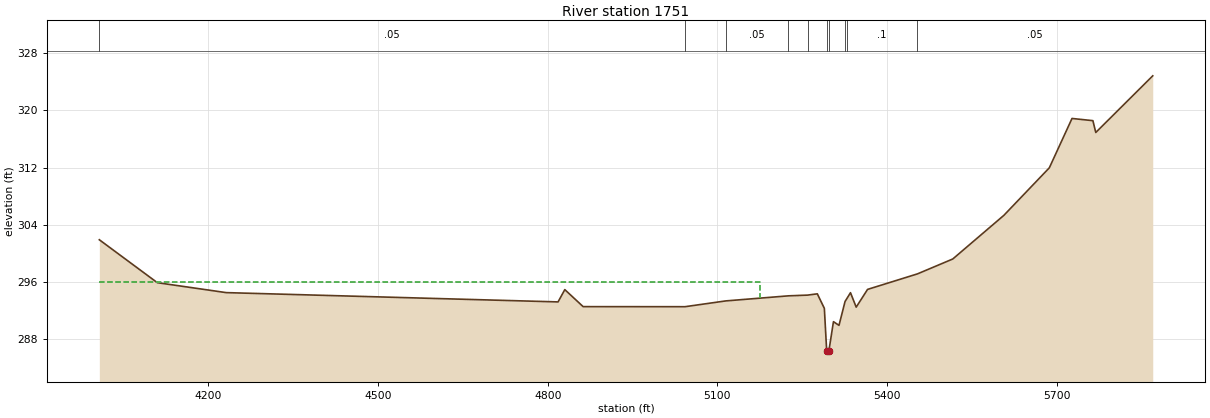
Type RM Length L Ch R = 1 ,1751    ,0,0,0
BEGIN DESCRIPTION:
Walnut74 0.6
END DESCRIPTION:
XS GIS Cut Line= 4
      2738916.42      6746180.05      2739395.57      6747107.09
      2739629.94      6747148.76      2740208.11      6747096.67
#Sta/Elev= 30
  4007.4   301.9  4109.9   295.9  4231.6  294.51  4818.3  293.21  4830.2  294.93
  4862.6  292.55  5042.7  292.54  5114.7  293.35  5225.6  294.06  5259.3  294.16
  5276.6  294.34    5289  292.31  5293.1  286.41  5293.3  285.91  5297.1  286.41
  5305.1  290.45  5314.9  289.93  5325.6  293.27  5328.6  293.65  5335.2   294.5
  5345.3  292.48  5365.4  294.96  5453.6  297.13    5516  299.21  5606.3  305.31
  5686.7  311.96  5726.8  318.86  5763.7  318.55  5768.8   316.9  5869.5  324.82
#Mann= 10 ,-1 , 0
  4007.4     .05       0  5042.7     .12       0  5114.7     .05       0
  5225.6     .12       0  5259.3      .1       0  5293.1     .05       0
  5297.1      .1       0  5325.6     .12       0  5328.6      .1       0
  5453.6     .05       0
#XS Ineff= 2 , 0
       0    5175     296               0
Permanent Ineff=
       F       F
Bank Sta=5293.1,5297.1
XS Rating Curve= 0 ,0
Exp/Cntr=0.3,0.1

Chan Stop Cuts=-1
Use User Specified Reach Order=0
Composite Channel Slope=5