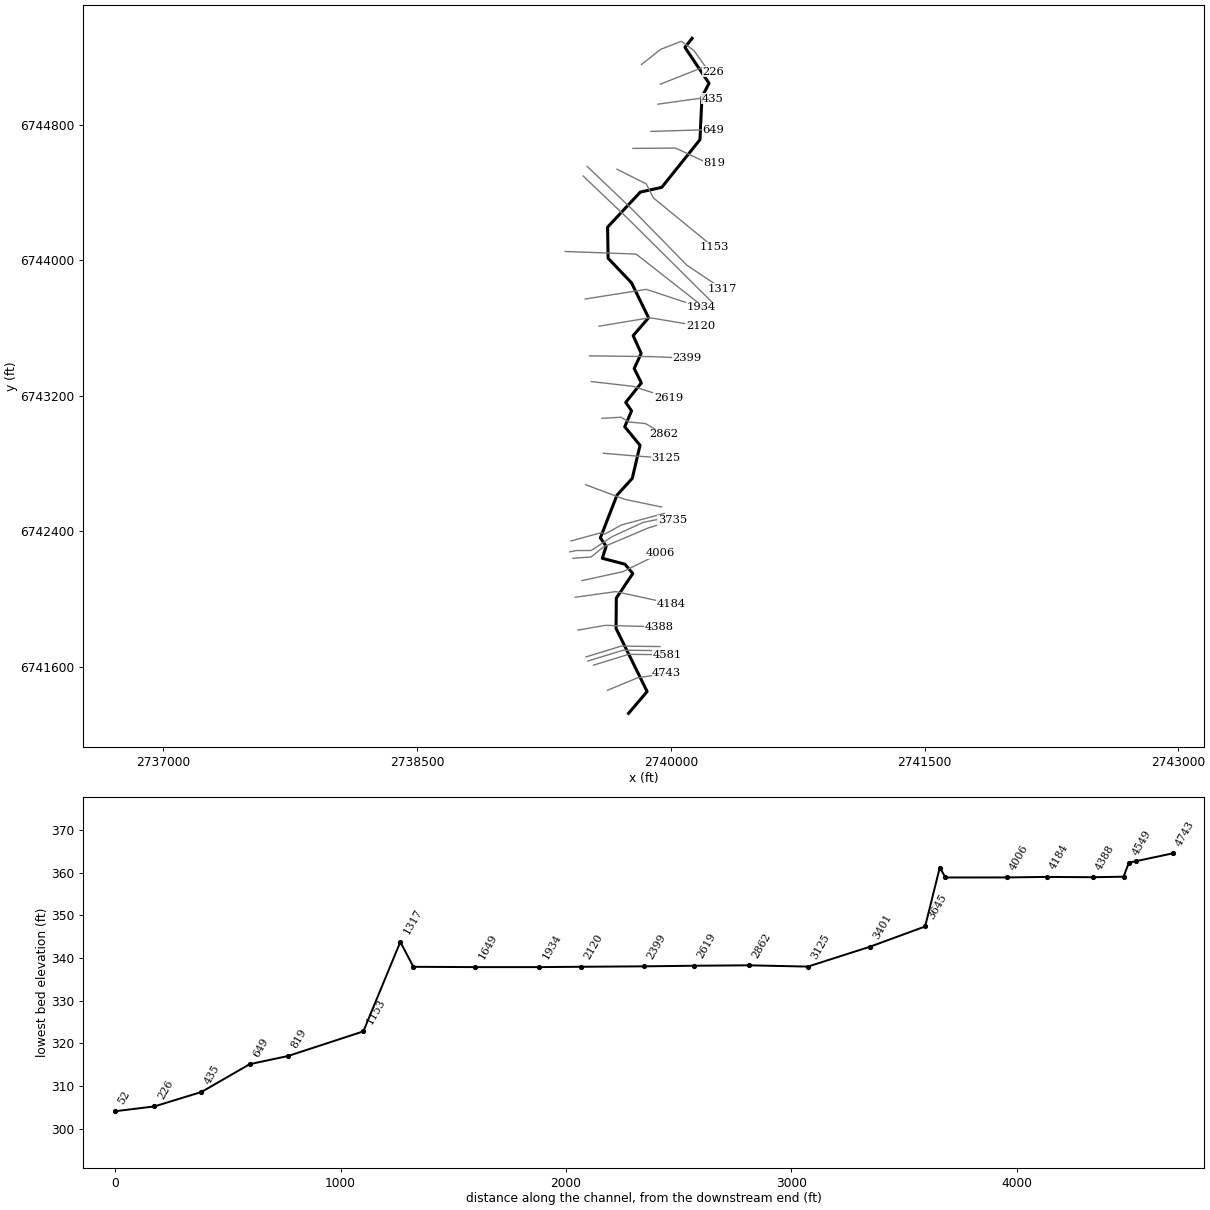
--- Walnut75.prj (project) ---

Proj Title=Walnut75 Base Level Engineering
Current Plan=p01
Default Exp/Contr=0.3,0.1
English Units
Geom File=g01
Flow File=f01
Plan File=p01
Y Axis Title=Elevation
X Axis Title(PF)=Main Channel Distance
X Axis Title(XS)=Station
BEGIN DESCRIPTION:
Walnut75
END DESCRIPTION:
DSS Export Rating Curves= 0
DSS Export Rating Curve Sorted= 0
DSS Export Volume Flow Curves= 0
DXF OffsetX= 0
DXF OffsetY= 0
DXF ScaleX= 1
DXF ScaleY= 10

--- Walnut75.p01 (plan) ---

Plan Title=Multiple Run
Program Version=4.10
Short Identifier=Multiple
Geom File=g01
Flow File=f01
Subcritical Flow
K Sum by GR= 0
Std Step Tol= 0.01
Critical Tol= 0.01
Num of Std Step Trials= 20
Max Error Tol= 0.3
Flow Tol Ratio= 0.001
Split Flow NTrial= 30
Split Flow Tol= 0.02
Split Flow Ratio= 0.02
Log Output Level= 0
Friction Slope Method= 1
Unsteady Friction Slope Method= 2
Unsteady Bridges Friction Slope Method= 1
Parabolic Critical Depth
Global Vel Dist= 1 , 1 , 1
Global Log Level= 0
CheckData=True
Encroach Param=-1 ,0,0, 0
BEGIN DESCRIPTION:
Multiple Run
END DESCRIPTION:
Computation Interval=1HOUR
Output Interval=1HOUR
Run HTab= 0
Run UNet= 0
Run PostProcess= 0
Run WQNet= 0
UNET Theta= 1
UNET Theta Warmup= 1
UNET ZTol= 0.02
UNET ZSATol= 0.05
UNET MxIter= 20
UNET MaxInSteps= 0
UNET DtIC= 0
UNET DtMin= 0
UNET MaxCRTS= 20
UNET WFStab= 2
UNET SFStab= 1
UNET WFX= 1
UNET SFX= 1
UNET DSS MLevel= 4
UNET DZMax Abort= 100
UNET Convert EG Bridges= 0
UNET Use Existing IB Tables=-1
UNET Froude Reduction=False
UNET Froude Limit= 1
UNET Froude Power= 10
UNET Time Slicing=0,0, 5
UNET Junction Losses=0
Instantaneous Interval=1HOUR
Write IC File= 0
Write IC File at Sim End=0
Echo Input=False
Echo Parameters=False
Echo Output=False
Write Detailed= 0
WQ AD Non Conservative
WQ ULTIMATE=-1
WQ Max Comp Step=1HOUR
WQ Output Interval=15MIN
WQ Output Selected Increments= 0
WQ Output face flow=0
WQ Output face velocity=0
WQ Output face area=0
WQ Output face dispersion=0
WQ Output cell volume=0
WQ Output cell surface area=0
WQ Output cell continuity=0
WQ Output cumulative cell continuity=0
WQ Output face conc=0
WQ Output face dconc_dx=0
WQ Output face courant=0
WQ Output face peclet=0
WQ Output face adv mass=0
WQ Output face disp mass=0
WQ Output cell mass=0
WQ Output cell source sink temp=0
WQ Output cell source sink nsm=0
WQ Output MaxMinRange=-1
WQ Daily Max Min Mean=-1
WQ Daily Range=0
WQ Daily Time=0
WQ Create Restart=0
WQ Fixed Restart=0
WQ System Summary=0
WQ Use Fixed Temperature=0
Sorting and Armoring Iterations= 10
XS Update Threshold= 0.02
Hydraulics Update Threshold= 0.02
Energy Slope Method= 1
Volume Change Method= 0
XS Weighting Method= 0
Number of US Weighted Cross Sections= 1
Number of DS Weighted Cross Sections= 1
Upstream XS Weight=0.25
Main XS Weight=0.5
Downstream XS Weight=0.25
Number of DS XS's Weighted with US Boundary= 1
Upstream Boundary Weight= 1
Weight of XSs Associated with US Boundary= 0
Number of US XS's Weighted with DS Boundary= 1
Downstream Boundary Weight= 0.5
Weight of XSs Associated with DS Boundary= 0.5
Sediment Output Level= 4
Mass or Volume Output= 0
Output Increment Type= 1
Profile and TS Output Increment= 10
XS Output Flag= 0
XS Output Increment= 10
Disregard all LS=0
Disregard all Conn=0
Disregard all Breaches=0
Disregard all Pumps=0

--- Walnut75.f01 (steady flow) ---

Flow Title=Multiple
Number of Profiles=7
Profile Names=10-year,25-year,50-year,1pct_min,100-year,1pct_plu,500-year
River Rch & RM= Walnut75,Reach-1,4743
     146     180     206     118     235     469     305
Boundary for River Rch & Prof#=Walnut75,Reach-1,1
Up Type=0
Dn Type=3
Dn Slope=0.005
Boundary for River Rch & Prof#=Walnut75,Reach-1,2
Up Type=0
Dn Type=3
Dn Slope=0.005
Boundary for River Rch & Prof#=Walnut75,Reach-1,3
Up Type=0
Dn Type=3
Dn Slope=0.005
Boundary for River Rch & Prof#=Walnut75,Reach-1,4
Up Type=0
Dn Type=3
Dn Slope=0.005
Boundary for River Rch & Prof#=Walnut75,Reach-1,5
Up Type=0
Dn Type=3
Dn Slope=0.005
Boundary for River Rch & Prof#=Walnut75,Reach-1,6
Up Type=0
Dn Type=3
Dn Slope=0.005
Boundary for River Rch & Prof#=Walnut75,Reach-1,7
Up Type=0
Dn Type=3
Dn Slope=0.005

--- Walnut75.g01 (geometry) ---

Geom Title=Existing Conditions

River Reach=Walnut75,Reach-1
Reach XY= 30
      2739750.23      6741324.51      2739860.08      6741453.53
      2739676.52      6741826.22      2739678.07      6742005.14
      2739775.52      6742150.53      2739728.75      6742205.58
      2739595.17      6742240.52      2739617.95      6742310.98
      2739583.78      6742360.90      2739681.85      6742613.29
      2739772.45      6742712.47      2739818.12      6742907.78
      2739727.67      6743017.05      2739768.16      6743111.09
      2739733.56      6743161.00      2739825.98      6743276.36
      2739783.62      6743361.00      2739825.16      6743450.30
      2739777.64      6743554.96      2739868.70      6743660.92
      2739767.86      6743867.06      2739629.54      6744012.46
      2739626.38      6744195.84      2739819.83      6744403.14
      2739946.20      6744430.61      2740172.46      6744712.47
      2740184.32      6744964.23      2740225.99      6745045.64
      2740083.58      6745257.80      2740126.00      6745311.00

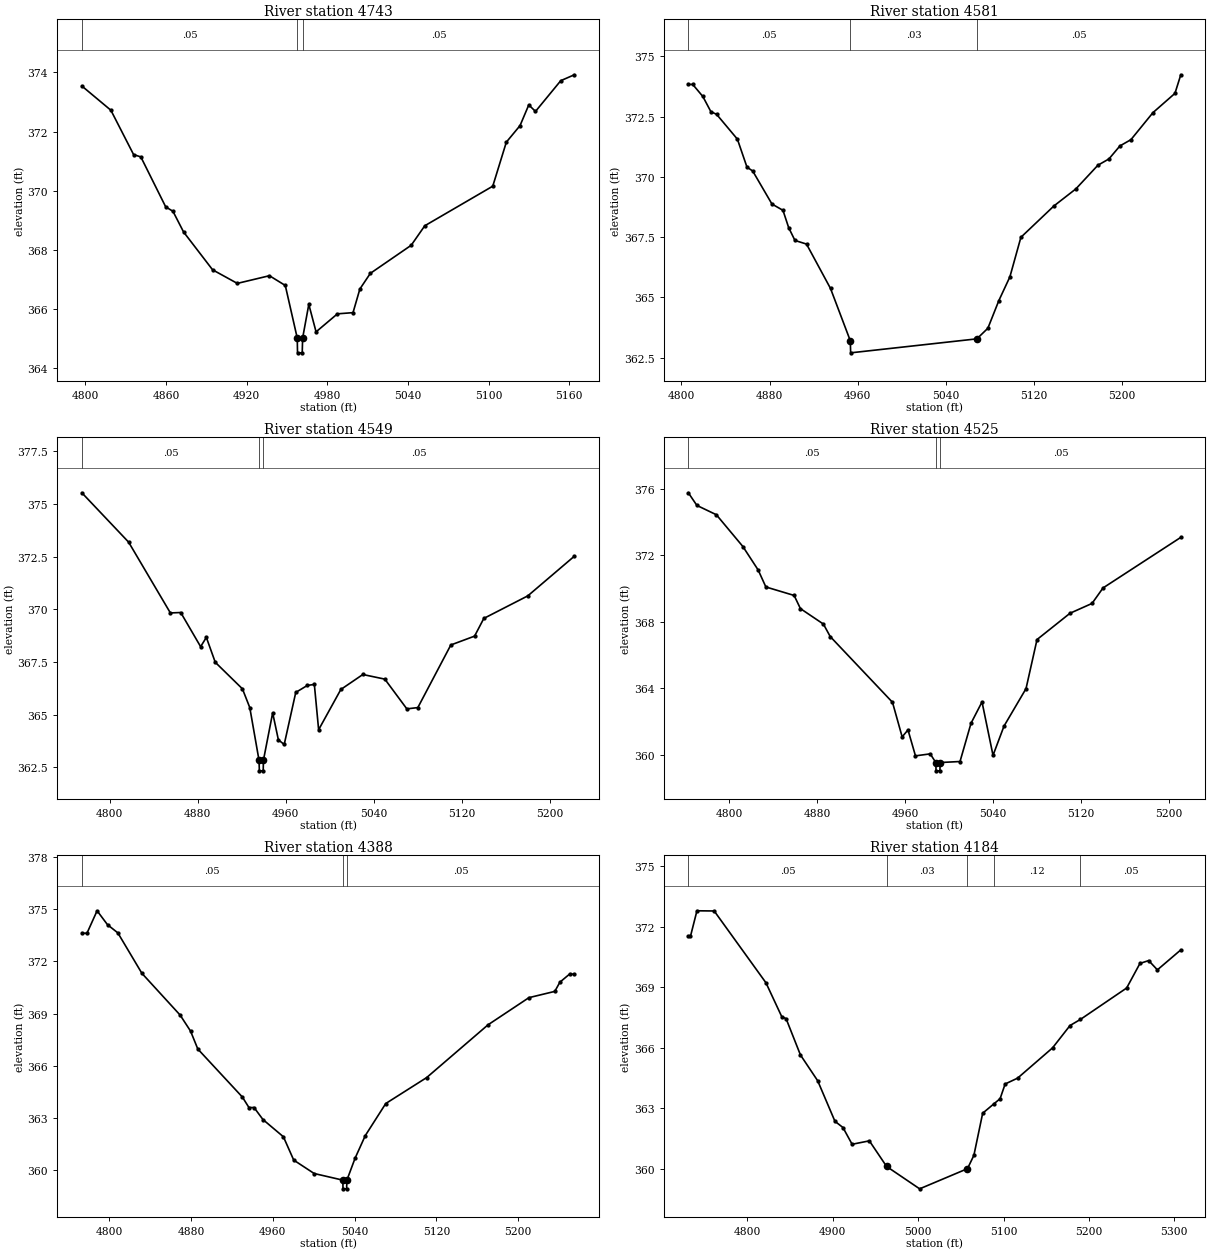
Type RM Length L Ch R = 1,4743,162,162,162
BEGIN DESCRIPTION:
Walnut75 14.0
END DESCRIPTION:
XS GIS Cut Line= 3
      2739626.04      6741461.02      2739802.60      6741534.00
      2739975.96      6741560.99
#Sta/Elev= 30
  4797.3  373.54  4818.9  372.72  4835.8  371.22  4841.2  371.14  4859.7  369.45
  4865.1  369.30  4873.0  368.60  4894.6  367.32  4913.0  366.86  4936.9  367.12
  4948.7  366.79  4957.6  365.01  4957.8  364.51  4961.3  364.51  4961.6  365.01
  4966.2  366.15  4971.6  365.22  4987.5  365.83  4999.1  365.87  5004.2  366.67
  5012.0  367.20  5042.4  368.15  5052.5  368.81  5103.1  370.15  5113.2  371.64
  5123.4  372.20  5129.9  372.90  5134.9  372.68  5153.7  373.72  5163.8  373.92
#Mann=3,-1,0
  4797.3    0.05       0  4957.6    0.05       0  4961.6    0.05       0
Bank Sta=4957.6,4961.6
Exp/Cntr=0.3,0.1

Type RM Length L Ch R = 1,4581,32,32,32
BEGIN DESCRIPTION:
Walnut75 13.6
END DESCRIPTION:
XS GIS Cut Line= 3
      2739543.34      6741609.38      2739751.51      6741673.24
      2739981.25      6741670.69
#Sta/Elev= 30
  4806.2  373.83  4810.2  373.83  4819.4  373.33  4826.7  372.70  4831.9  372.59
  4850.8  371.56  4859.5  370.40  4864.7  370.24  4882.2  368.87  4892.2  368.61
  4897.4  367.89  4903.1  367.36  4913.6  367.21  4935.4  365.37  4953.4  363.20
  4953.7  362.70  5068.4  363.28  5078.4  363.72  5088.4  364.87  5098.4  365.85
  5108.4  367.49  5138.4  368.79  5158.4  369.50  5178.4  370.48  5188.4  370.74
  5198.4  371.28  5208.4  371.54  5228.4  372.66  5248.4  373.46  5253.7  374.23
#Mann=3,-1,0
  4806.2    0.05       0  4953.4    0.03       0  5068.4    0.05       0
Bank Sta=4953.4,5068.4
Exp/Cntr=0.3,0.1

Type RM Length L Ch R = 1,4549,24,24,24
BEGIN DESCRIPTION:
Walnut75 13.4
END DESCRIPTION:
XS GIS Cut Line= 3
      2739510.04      6741633.63      2739718.29      6741697.51
      2739948.25      6741694.95
#Sta/Elev= 30
  4774.6  375.53  4817.1  373.19  4855.1  369.83  4864.5  369.85  4882.6  368.23
  4887.8  368.67  4895.9  367.49  4920.6  366.23  4927.3  365.34  4935.7  362.84
  4936.0  362.34  4939.5  362.34  4939.7  362.84  4948.1  365.09  4953.3  363.81
  4958.6  363.59  4969.1  366.06  4979.6  366.39  4986.0  366.44  4989.9  364.29
  5010.1  366.20  5030.1  366.91  5050.1  366.69  5070.1  365.28  5080.1  365.34
  5110.1  368.31  5131.7  368.73  5140.1  369.57  5180.1  370.64  5222.4  372.52
#Mann=3,-1,0
  4774.6    0.05       0  4935.7    0.05       0  4939.7    0.05       0
Bank Sta=4935.7,4939.7
Exp/Cntr=0.3,0.1

Type RM Length L Ch R = 1,4525,137,137,137
BEGIN DESCRIPTION:
Walnut75 13.2
END DESCRIPTION:
XS GIS Cut Line= 3
      2739498.58      6741657.91      2739706.80      6741721.78
      2739936.69      6741719.22
#Sta/Elev= 30
  4762.9  375.76  4770.7  375.00  4788.4  374.44  4812.5  372.53  4826.4  371.12
  4833.4  370.10  4859.1  369.59  4864.8  368.80  4885.7  367.87  4891.9  367.12
  4948.5  363.17  4957.3  361.09  4962.6  361.51  4969.4  359.95  4982.8  360.07
  4987.9  359.55  4988.1  359.05  4991.6  359.05  4991.9  359.55  5009.9  359.61
  5019.9  361.91  5029.9  363.19  5039.9  359.98  5049.9  361.74  5069.9  363.99
  5079.9  366.94  5109.9  368.52  5129.9  369.11  5139.9  370.04  5210.6  373.08
#Mann=3,-1,0
  4762.9    0.05       0  4987.9    0.05       0  4991.9    0.05       0
Bank Sta=4987.9,4991.9
Exp/Cntr=0.3,0.1

Type RM Length L Ch R = 1,4388,204,204,204
BEGIN DESCRIPTION:
Walnut75 13.0
END DESCRIPTION:
XS GIS Cut Line= 3
      2739451.28      6741816.30      2739613.55      6741844.41
      2739930.34      6741835.47
#Sta/Elev= 30
  4773.2  373.61  4778.2  373.61  4788.1  374.90  4798.3  374.10  4808.4  373.63
  4831.9  371.31  4869.3  368.91  4879.5  367.99  4886.6  366.96  4930.2  364.20
  4936.6  363.60  4941.6  363.60  4950.3  362.91  4970.3  361.92  4980.4  360.58
  5000.4  359.81  5028.4  359.43  5028.6  358.93  5032.1  358.93  5032.4  359.43
  5040.4  360.69  5050.4  361.99  5070.4  363.83  5110.4  365.32  5170.4  368.35
  5210.4  369.91  5235.7  370.27  5240.7  370.80  5250.1  371.26  5254.8  371.26
#Mann=3,-1,0
  4773.2    0.05       0  5028.4    0.05       0  5032.4    0.05       0
Bank Sta=5028.4,5032.4
Exp/Cntr=0.3,0.1

Type RM Length L Ch R = 1,4184,178,178,178
BEGIN DESCRIPTION:
Walnut75 12.0
END DESCRIPTION:
XS GIS Cut Line= 3
      2739435.98      6742010.47      2739674.86      6742043.68
      2740002.75      6741972.51
#Sta/Elev= 30
  4730.9  371.52  4733.4  371.52  4741.0  372.79  4761.2  372.78  4821.8  369.22
  4840.3  367.54  4845.4  367.44  4862.2  365.64  4882.4  364.36  4902.6  362.35
  4912.0  362.04  4922.7  361.21  4942.9  361.38  4963.1  360.11  5001.8  359.00
  5057.8  360.00  5065.3  360.66  5075.6  362.75  5088.3  363.20  5096.0  363.47
  5101.9  364.20  5116.5  364.49  5157.4  365.99  5177.9  367.10  5190.0  367.40
  5244.2  368.96  5259.8  370.18  5270.0  370.32  5280.2  369.86  5307.6  370.85
#Mann=5,-1,0
  4730.9    0.05       0  4963.1    0.03       0  5057.8    0.05       0
  5088.3    0.12       0  5190.0    0.05       0
Bank Sta=4963.1,5057.8
Exp/Cntr=0.3,0.1

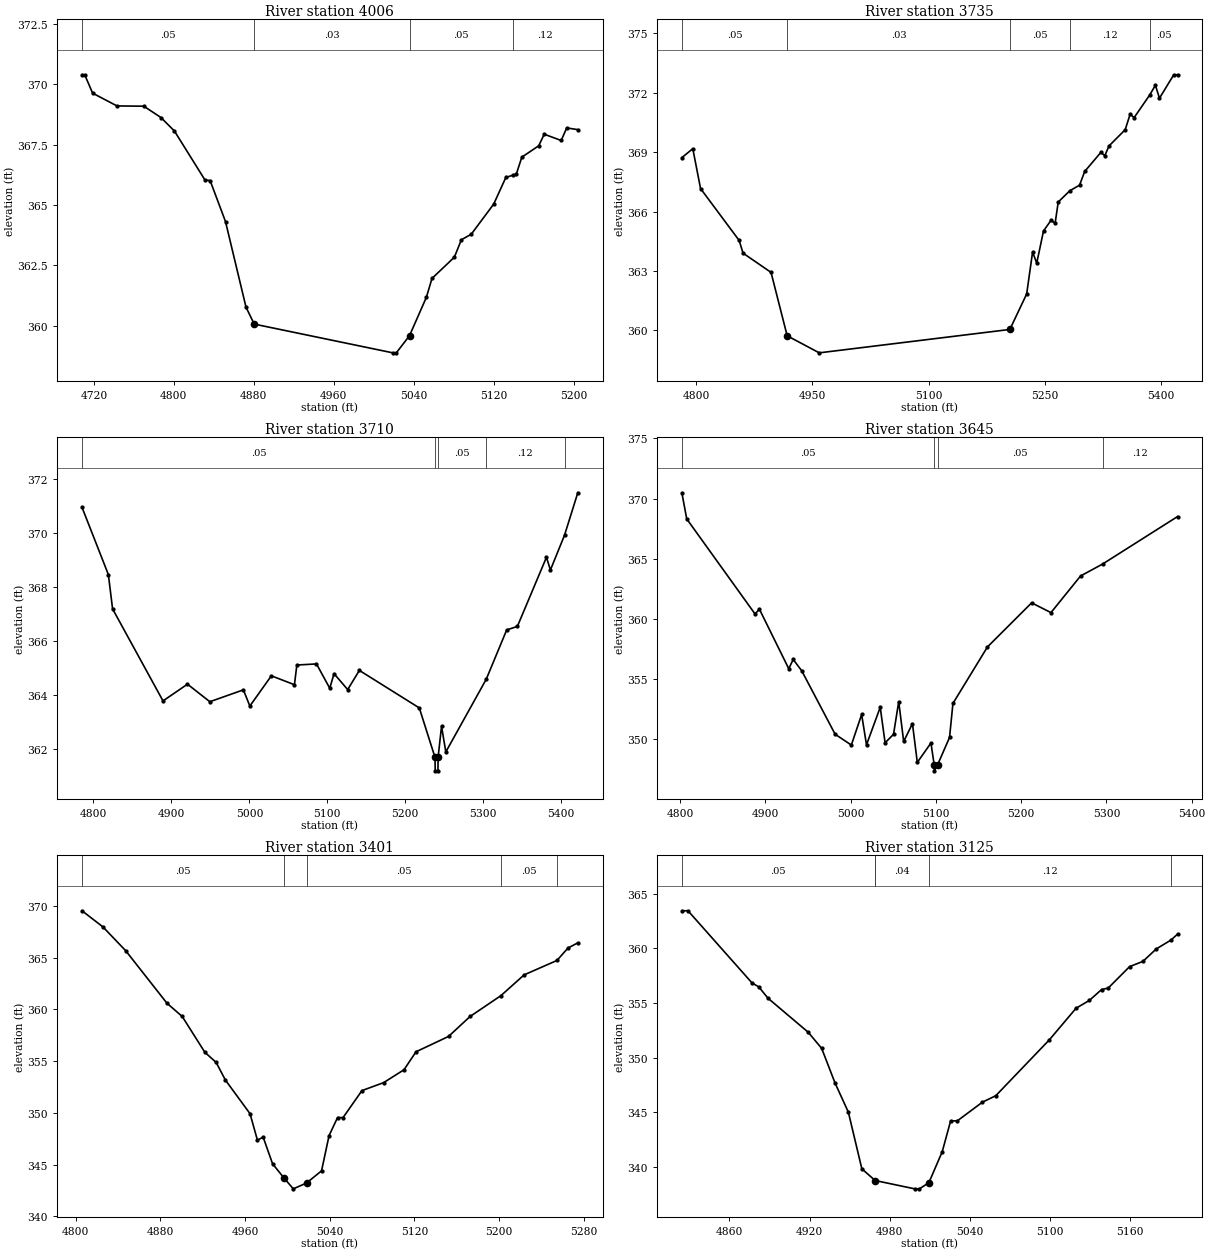
Type RM Length L Ch R = 1,4006,271,271,271
BEGIN DESCRIPTION:
Walnut75 11.0
END DESCRIPTION:
XS GIS Cut Line= 3
      2739475.63      6742108.84      2739717.02      6742161.20
      2739940.57      6742271.06
#Sta/Elev= 30
  4708.1  370.39  4710.8  370.39  4718.7  369.63  4743.1  369.10  4769.9  369.09
  4787.1  368.62  4800.6  368.06  4831.2  366.03  4836.3  366.01  4851.7  364.31
  4872.2  360.77  4880.4  360.07  5019.1  358.88  5022.6  358.88  5035.8  359.59
  5052.7  361.18  5058.3  361.96  5080.7  362.84  5087.7  363.56  5097.6  363.79
  5120.1  365.04  5132.2  366.14  5139.0  366.23  5142.6  366.27  5148.2  366.98
  5165.1  367.45  5170.6  367.93  5187.6  367.67  5193.1  368.19  5204.2  368.12
#Mann=4,-1,0
  4708.1    0.05       0  4880.4    0.03       0  5035.8    0.05       0
  5139.0    0.12       0
Bank Sta=4880.4,5035.8
Exp/Cntr=0.3,0.1

Type RM Length L Ch R = 1,3735,25,25,25
BEGIN DESCRIPTION:
Walnut75 10.5
END DESCRIPTION:
XS GIS Cut Line= 5
      2739421.93      6742240.40      2739529.24      6742248.06
      2739603.33      6742308.10      2739866.06      6742419.12
      2740010.54      6742463.81
#Sta/Elev= 30
  4781.7  368.72  4795.8  369.17  4805.8  367.16  4855.6  364.54  4860.6  363.90
  4896.7  362.93  4917.5  359.73  4958.9  358.87  5204.7  360.05  5226.4  361.84
  5234.0  363.95  5239.4  363.40  5248.1  365.02  5257.7  365.55  5263.1  365.41
  5267.1  366.48  5282.1  367.05  5294.6  367.33  5301.2  368.02  5322.0  368.98
  5327.2  368.82  5332.6  369.31  5353.5  370.13  5359.8  370.91  5365.0  370.74
  5384.9  371.87  5392.4  372.37  5397.7  371.72  5416.1  372.90  5421.1  372.90
#Mann=5,-1,0
  4781.7    0.05       0  4917.5    0.03       0  5204.7    0.05       0
  5282.1    0.12       0  5384.9    0.05       0
Bank Sta=4917.5,5204.7
Exp/Cntr=0.3,0.1

Type RM Length L Ch R = 1,3710,65,65,65
BEGIN DESCRIPTION:
Walnut75 10.2
END DESCRIPTION:
XS GIS Cut Line= 6
      2739402.78      6742278.72      2739443.66      6742286.39
      2739529.24      6742286.39      2739655.70      6742369.42
      2739837.11      6742452.61      2739992.02      6742483.55
#Sta/Elev= 30
  4785.3  370.96  4819.1  368.47  4824.5  367.20  4889.2  363.79  4920.6  364.41
  4949.3  363.76  4992.3  364.20  5000.6  363.60  5028.2  364.72  5057.8  364.39
  5060.9  365.12  5086.1  365.16  5103.1  364.26  5108.6  364.80  5126.1  364.21
  5141.1  364.92  5218.0  363.53  5238.1  361.70  5238.4  361.20  5241.9  361.20
  5242.1  361.70  5246.5  362.85  5252.0  361.90  5303.8  364.59  5330.1  366.42
  5343.8  366.55  5381.1  369.11  5386.2  368.64  5404.3  369.93  5421.3  371.50
#Mann=5,-1,0
  4785.3    0.05       0  5238.1    0.05       0  5242.1    0.05       0
  5303.8    0.12       0  5404.3    0.05       0
Bank Sta=5238.1,5242.1
Exp/Cntr=0.3,0.1

Type RM Length L Ch R = 1,3645,244,244,244
BEGIN DESCRIPTION:
Walnut75 10.0
END DESCRIPTION:
XS GIS Cut Line= 5
      2739410.48      6742342.60      2739586.72      6742391.13
      2739611.01      6742383.44      2739708.08      6742437.12
      2739961.37      6742505.62
#Sta/Elev= 30
  4801.9  370.48  4807.6  368.31  4887.7  360.42  4892.9  360.81  4927.3  355.87
  4932.5  356.64  4942.5  355.70  4981.7  350.43  5000.7  349.53  5012.8  352.07
  5018.5  349.55  5034.6  352.67  5040.3  349.72  5050.2  350.42  5056.3  353.14
  5062.1  349.83  5072.4  351.31  5078.1  348.09  5094.1  349.70  5097.9  347.89
  5098.1  347.39  5101.9  347.89  5115.9  350.16  5119.9  352.99  5160.4  357.68
  5212.2  361.34  5234.9  360.53  5269.6  363.57  5295.4  364.56  5383.5  368.51
#Mann=4,-1,0
  4801.9    0.05       0  5097.9    0.05       0  5101.9    0.05       0
  5295.4    0.12       0
Bank Sta=5097.9,5101.9
Exp/Cntr=0.3,0.1

Type RM Length L Ch R = 1,3401,276,276,276
BEGIN DESCRIPTION:
Walnut75 9.0
END DESCRIPTION:
XS GIS Cut Line= 3
      2739497.29      6742674.72      2739725.96      6742589.13
      2739945.63      6742543.15
#Sta/Elev= 30
  4805.9  369.52  4825.7  367.96  4847.2  365.66  4886.2  360.59  4900.6  359.31
  4922.0  355.85  4932.7  354.87  4941.4  353.17  4964.7  349.92  4971.7  347.36
  4977.1  347.66  4986.0  345.08  4996.7  343.72  5005.6  342.66  5018.1  343.22
  5032.3  344.40  5039.4  347.80  5047.4  349.54  5052.6  349.54  5070.5  352.15
  5091.0  352.92  5110.2  354.16  5121.6  355.90  5152.3  357.38  5172.7  359.31
  5201.8  361.32  5223.8  363.33  5254.8  364.72  5265.2  365.92  5274.5  366.42
#Mann=5,-1,0
  4805.9    0.05       0  4996.7    0.04       0  5018.1    0.05       0
  5201.8    0.05       0  5254.8    0.12       0
Bank Sta=4996.7,5018.1
Exp/Cntr=0.3,0.1

Type RM Length L Ch R = 1,3125,263,263,263
BEGIN DESCRIPTION:
Walnut75 8.0
END DESCRIPTION:
XS GIS Cut Line= 3
      2739601.71      6742860.77      2739803.50      6742843.41
      2739971.92      6742832.62
#Sta/Elev= 30
  4824.4  363.43  4829.0  363.43  4877.0  356.82  4882.0  356.47  4888.9  355.43
  4919.0  352.32  4929.1  350.84  4939.1  347.68  4949.1  345.00  4959.2  339.82
  4968.7  338.80  4969.2  338.75  4998.8  337.99  5002.3  337.99  5009.4  338.55
  5019.4  341.39  5025.7  344.21  5030.7  344.21  5049.5  345.92  5059.5  346.51
  5099.6  351.62  5119.6  354.51  5129.6  355.23  5138.7  356.22  5143.7  356.36
  5159.7  358.32  5169.7  358.80  5179.7  359.94  5190.7  360.75  5195.7  361.30
#Mann=5,-1,0
  4824.4    0.05       0  4968.7    0.12       0  4969.2    0.04       0
  5009.4    0.12       0  5190.7    0.05       0
Bank Sta=4969.2,5009.4
Exp/Cntr=0.3,0.1

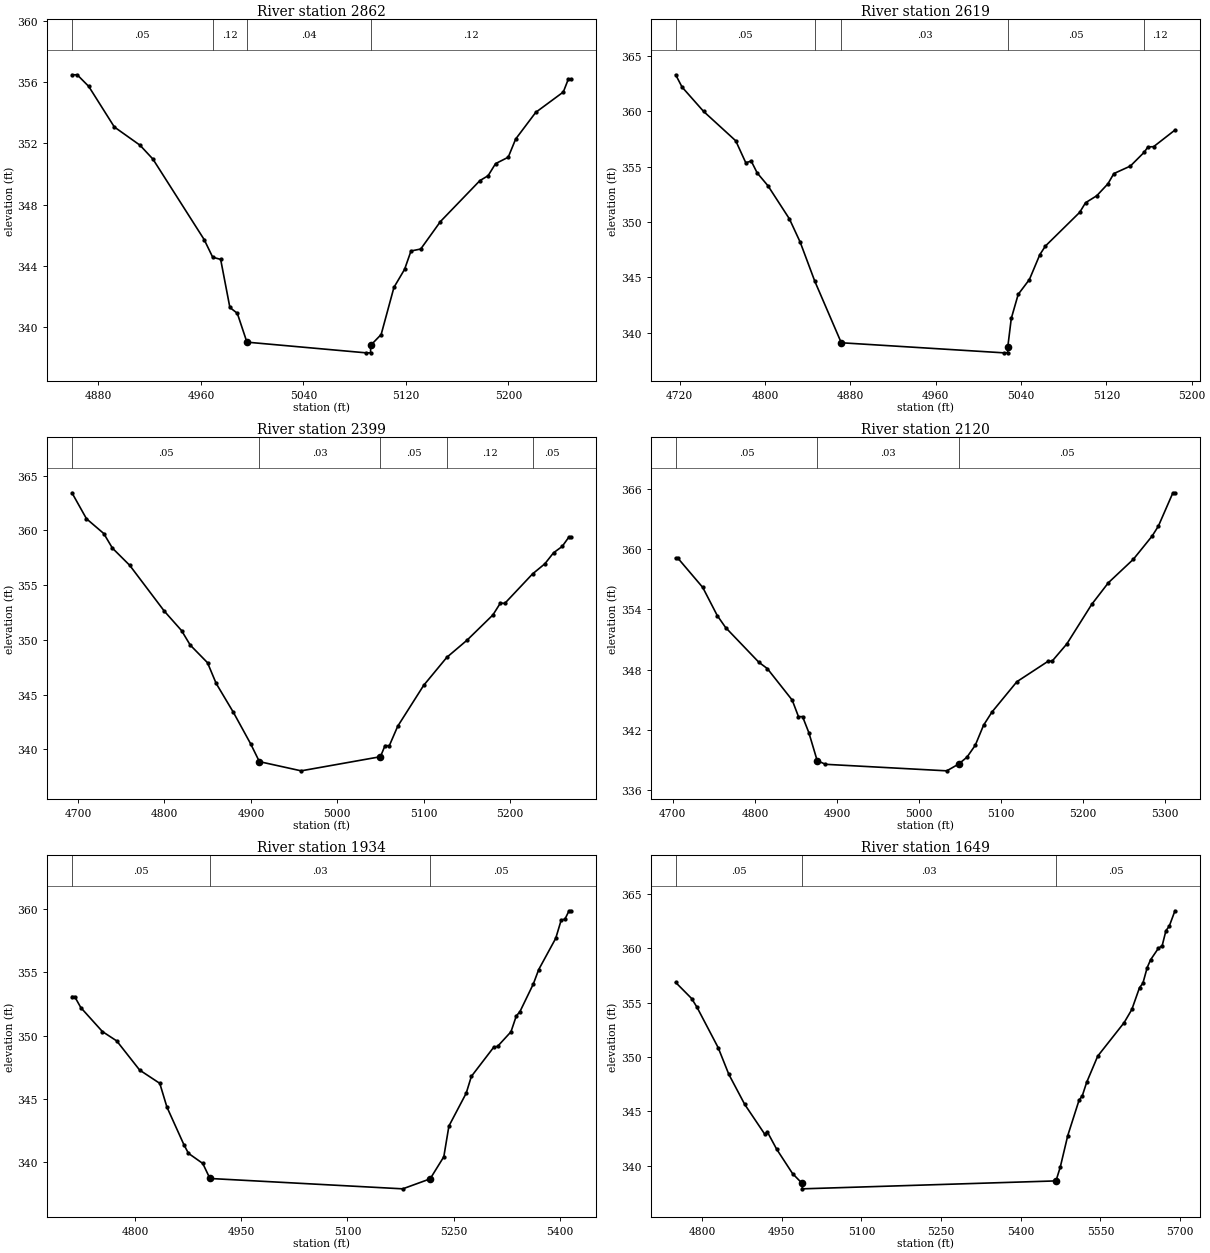
Type RM Length L Ch R = 1,2862,243,243,243
BEGIN DESCRIPTION:
Walnut75 7.0
END DESCRIPTION:
XS GIS Cut Line= 5
      2739592.95      6743066.93      2739705.85      6743073.45
      2739752.41      6743045.45      2739851.15      6743035.63
      2739957.56      6742973.63
#Sta/Elev= 30
  4859.3  356.50  4863.4  356.50  4872.4  355.74  4892.4  353.08  4912.4  351.89
  4922.5  350.98  4962.5  345.71  4969.2  344.55  4975.4  344.41  4982.6  341.26
  4988.4  340.88  4995.9  338.99  5088.9  338.29  5092.4  338.29  5092.6  338.79
  5100.7  339.49  5110.7  342.58  5119.0  343.76  5124.0  344.96  5131.6  345.09
  5147.0  346.89  5177.8  349.57  5184.2  349.89  5190.0  350.68  5199.9  351.10
  5205.7  352.29  5221.4  354.04  5242.9  355.37  5246.8  356.21  5249.1  356.21
#Mann=4,-1,0
  4859.3    0.05       0  4969.2    0.12       0  4995.9    0.04       0
  5092.6    0.12       0
Bank Sta=4995.9,5092.6
Exp/Cntr=0.3,0.1

Type RM Length L Ch R = 1,2619,220,220,220
BEGIN DESCRIPTION:
Walnut75 6.0
END DESCRIPTION:
XS GIS Cut Line= 3
      2739530.08      6743283.95      2739777.46      6743255.74
      2739985.78      6743188.47
#Sta/Elev= 30
  4716.4  363.29  4722.4  362.18  4742.5  359.99  4772.7  357.33  4782.1  355.35
  4787.2  355.50  4792.8  354.43  4802.9  353.27  4823.0  350.28  4833.1  348.18
  4846.8  344.65  4871.6  339.10  5023.9  338.19  5027.4  338.19  5027.6  338.69
  5030.9  341.29  5037.4  343.47  5047.9  344.81  5057.7  347.06  5062.9  347.83
  5095.0  350.87  5100.5  351.74  5111.0  352.37  5121.5  353.45  5127.0  354.37
  5142.5  355.05  5155.4  356.29  5159.0  356.78  5164.3  356.80  5184.3  358.30
#Mann=5,-1,0
  4716.4    0.05       0  4846.8    0.12       0  4871.6    0.03       0
  5027.6    0.05       0  5155.4    0.12       0
Bank Sta=4871.6,5027.6
Exp/Cntr=0.3,0.1

Type RM Length L Ch R = 1,2399,279,279,279
BEGIN DESCRIPTION:
Walnut75 5.0
END DESCRIPTION:
XS GIS Cut Line= 3
      2739519.22      6743435.86      2739881.63      6743431.52
      2740096.51      6743422.84
#Sta/Elev= 30
  4693.0  363.43  4709.8  361.06  4729.8  359.71  4739.8  358.38  4759.8  356.81
  4799.8  352.63  4819.8  350.85  4829.8  349.53  4849.8  347.92  4859.8  346.03
  4879.8  343.38  4899.8  340.50  4909.8  338.89  4958.1  338.05  5049.8  339.34
  5055.1  340.35  5060.1  340.35  5069.8  342.12  5099.8  345.85  5126.6  348.41
  5149.9  349.97  5179.9  352.28  5188.6  353.37  5193.6  353.33  5225.7  356.02
  5240.0  356.95  5250.0  357.95  5260.0  358.53  5267.7  359.38  5270.5  359.38
#Mann=5,-1,0
  4693.0    0.05       0  4909.8    0.03       0  5049.8    0.05       0
  5126.6    0.12       0  5225.7    0.05       0
Bank Sta=4909.8,5049.8
Exp/Cntr=0.3,0.1

Type RM Length L Ch R = 1,2120,186,186,186
BEGIN DESCRIPTION:
Walnut75 4.0
END DESCRIPTION:
XS GIS Cut Line= 3
      2739575.97      6743610.99      2739876.00      6743661.00
      2740175.99      6743611.00
#Sta/Elev= 30
  4703.4  359.10  4706.0  359.10  4736.4  356.18  4754.1  353.38  4764.3  352.19
  4804.8  348.74  4815.0  348.12  4845.4  344.98  4853.0  343.34  4858.0  343.34
  4865.6  341.76  4875.8  338.97  4885.9  338.60  5033.7  337.95  5048.1  338.62
  5058.3  339.31  5068.4  340.49  5078.5  342.48  5088.7  343.79  5119.1  346.81
  5157.1  348.84  5162.2  348.87  5179.9  350.56  5210.3  354.50  5230.6  356.65
  5261.0  358.98  5283.8  361.28  5291.4  362.26  5309.2  365.59  5311.7  365.59
#Mann=3,-1,0
  4703.4    0.05       0  4875.8    0.03       0  5048.1    0.05       0
Bank Sta=4875.8,5048.1
Exp/Cntr=0.3,0.1

Type RM Length L Ch R = 1,1934,285,285,285
BEGIN DESCRIPTION:
Walnut75 3.8
END DESCRIPTION:
XS GIS Cut Line= 3
      2739493.53      6743771.59      2739855.59      6743828.66
      2740176.81      6743722.30
#Sta/Elev= 30
  4711.1  353.09  4714.9  353.09  4723.7  352.21  4754.1  350.32  4774.3  349.58
  4806.7  347.27  4835.1  346.22  4845.2  344.34  4869.2  341.36  4875.6  340.68
  4895.8  339.88  4905.9  338.69  5178.1  337.87  5216.8  338.66  5236.1  340.41
  5243.3  342.84  5267.7  345.44  5275.0  346.77  5306.7  349.09  5311.9  349.14
  5330.9  350.30  5338.4  351.55  5343.6  351.90  5362.5  354.09  5370.1  355.23
  5394.1  357.70  5401.8  359.14  5407.1  359.22  5412.9  359.88  5416.0  359.88
#Mann=3,-1,0
  4711.1    0.05       0  4905.9    0.03       0  5216.8    0.05       0
Bank Sta=4905.9,5216.8
Exp/Cntr=0.3,0.1

Type RM Length L Ch R = 1,1649,274,274,274
BEGIN DESCRIPTION:
Walnut75 3.4
END DESCRIPTION:
XS GIS Cut Line= 3
      2739376.01      6744052.18      2739794.82      6744036.99
      2740204.87      6743715.89
#Sta/Elev= 30
  4750.3  356.86  4780.3  355.38  4790.3  354.59  4830.3  350.86  4850.4  348.40
  4880.4  345.63  4918.1  342.89  4923.1  343.09  4940.4  341.52  4970.4  339.27
  4988.4  338.37  4988.7  337.87  5466.2  338.60  5474.3  339.87  5488.4  342.77
  5509.5  346.00  5515.9  346.45  5524.0  347.67  5544.8  350.08  5594.5  353.16
  5609.0  354.37  5623.5  356.38  5629.8  356.78  5637.9  358.22  5644.3  358.94
  5658.7  359.98  5666.2  360.25  5673.2  361.62  5679.5  362.04  5690.2  363.45
#Mann=3,-1,0
  4750.3    0.05       0  4988.4    0.03       0  5466.2    0.05       0
Bank Sta=4988.4,5466.2
Exp/Cntr=0.3,0.1

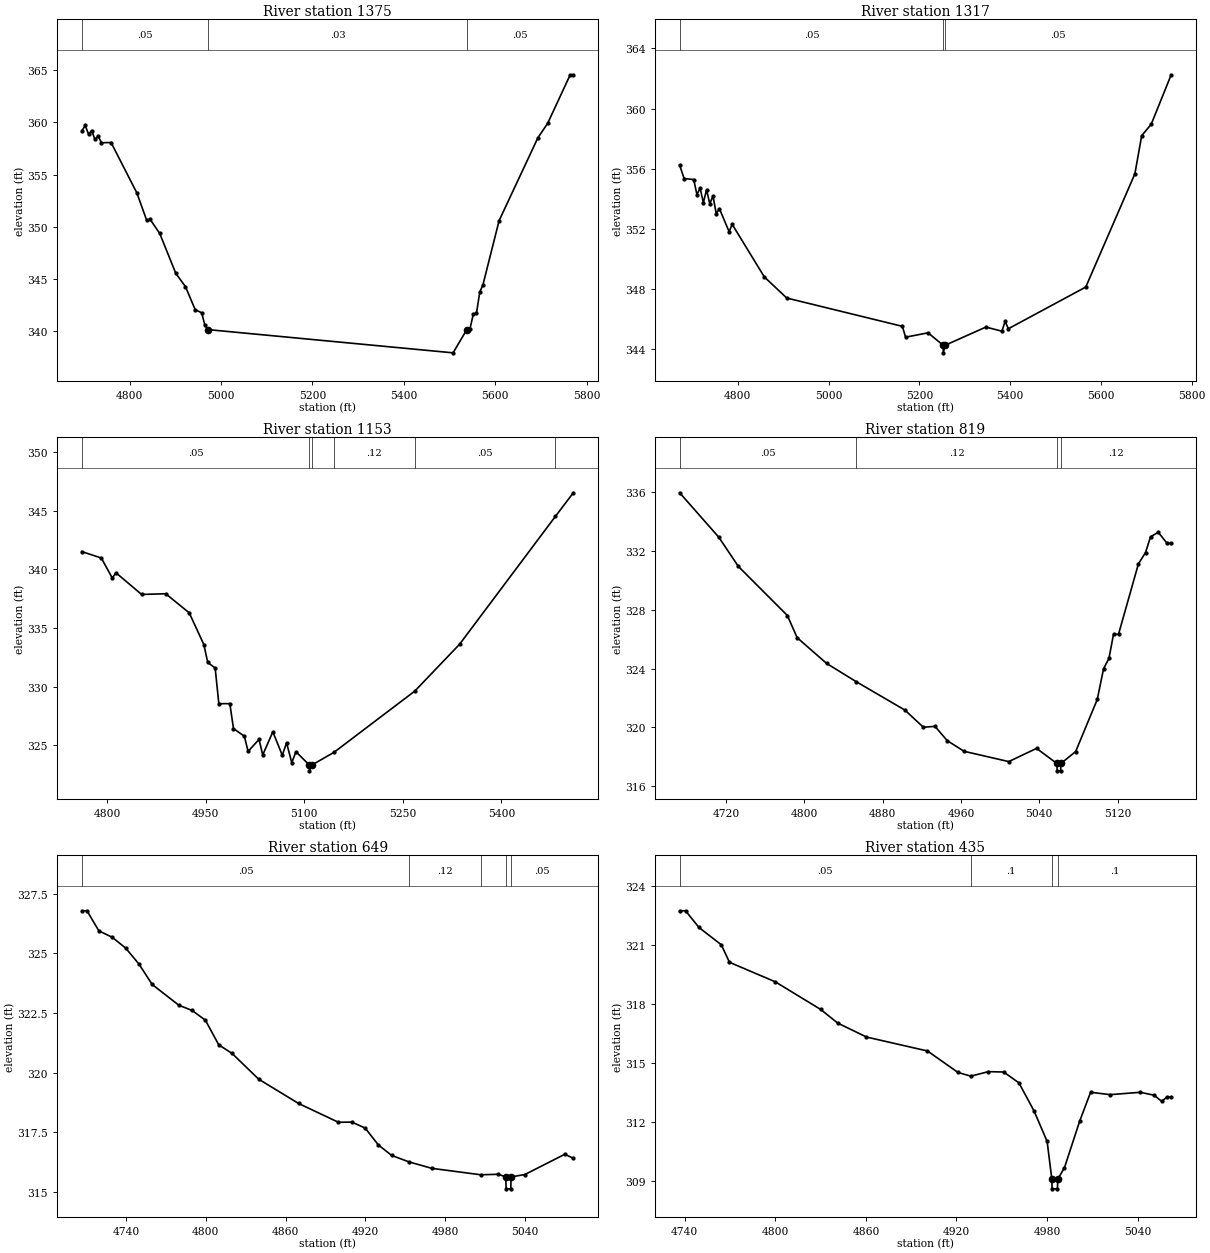
Type RM Length L Ch R = 1,1375,58,58,58
BEGIN DESCRIPTION:
Walnut75 3.0
END DESCRIPTION:
XS GIS Cut Line= 3
      2739482.27      6744497.89      2739744.42      6744248.22
      2740250.65      6743746.15
#Sta/Elev= 30
  4695.5  359.16  4702.9  359.69  4710.2  358.86  4717.1  359.20  4724.3  358.35
  4731.2  358.67  4738.5  358.04  4759.5  358.06  4816.1  353.22  4837.5  350.60
  4844.4  350.74  4865.9  349.36  4901.1  345.54  4922.1  344.28  4943.5  342.07
  4957.7  341.77  4964.6  340.59  4971.8  340.16  5507.5  337.94  5537.5  340.16
  5544.6  340.26  5551.7  341.63  5558.7  341.73  5565.8  343.73  5572.9  344.46
  5608.2  350.59  5693.1  358.52  5714.3  359.89  5763.7  364.54  5770.5  364.54
#Mann=3,-1,0
  4695.5    0.05       0  4971.8    0.03       0  5537.5    0.05       0
Bank Sta=4971.8,5537.5
Exp/Cntr=0.3,0.1

Type RM Length L Ch R = 1,1317,164,164,164
BEGIN DESCRIPTION:
Walnut75 2.8
END DESCRIPTION:
XS GIS Cut Line= 4
      2739505.90      6744554.70      2739768.00      6744305.09
      2740095.31      6743970.84      2740306.15      6743830.74
#Sta/Elev= 30
  4672.0  356.23  4681.8  355.35  4702.9  355.28  4710.1  354.28  4717.0  354.71
  4724.3  353.75  4731.2  354.60  4738.4  353.67  4745.4  354.19  4752.6  353.01
  4759.5  353.35  4780.9  351.82  4787.8  352.30  4858.6  348.81  4908.0  347.41
  5162.7  345.53  5169.7  344.81  5219.3  345.10  5252.6  344.27  5252.9  343.77
  5256.6  344.27  5346.6  345.48  5381.9  345.21  5389.1  345.86  5396.1  345.37
  5566.7  348.14  5674.9  355.66  5689.9  358.19  5711.0  358.96  5754.9  362.24
#Mann=3,-1,0
  4672.0    0.05       0  5252.6    0.03       0  5256.6    0.05       0
Bank Sta=5252.6,5256.6
Exp/Cntr=0.3,0.1

Type RM Length L Ch R = 1,1153,334,334,334
BEGIN DESCRIPTION:
Walnut75 2.0
END DESCRIPTION:
XS GIS Cut Line= 4
      2739681.98      6744538.10      2739855.37      6744450.71
      2739896.98      6744368.88      2740254.79      6744076.26
#Sta/Elev= 30
  4761.3  341.53  4791.0  340.98  4807.7  339.27  4813.3  339.72  4852.3  337.87
  4889.0  337.93  4924.8  336.30  4947.1  333.59  4953.0  332.06  4964.3  331.59
  4969.9  328.54  4986.6  328.55  4992.2  326.42  5008.8  325.76  5014.4  324.47
  5031.1  325.49  5036.7  324.17  5052.1  326.14  5066.5  324.14  5073.0  325.20
  5080.9  323.51  5087.3  324.44  5107.6  323.31  5107.8  322.81  5111.6  323.31
  5145.2  324.39  5268.2  329.62  5336.4  333.62  5482.3  344.54  5509.5  346.55
#Mann=6,-1,0
  4761.3    0.05       0  5107.6    0.03       0  5111.6    0.05       0
  5145.2    0.12       0  5268.2    0.05       0  5482.3    0.12       0
Bank Sta=5107.6,5111.6
Exp/Cntr=0.3,0.1

Type RM Length L Ch R = 1,819,170,170,170
BEGIN DESCRIPTION:
Walnut75 1.0
END DESCRIPTION:
XS GIS Cut Line= 4
      2739775.96      6744661.00      2740028.74      6744662.91
      2740201.12      6744582.04      2740259.04      6744571.85
#Sta/Elev= 30
  4672.7  335.98  4712.7  332.95  4732.7  330.96  4782.7  327.62  4792.7  326.11
  4822.7  324.36  4853.1  323.11  4902.7  321.18  4921.6  320.01  4933.5  320.07
  4945.9  319.10  4963.2  318.37  5008.8  317.67  5037.2  318.57  5058.0  317.54
  5058.3  317.04  5061.8  317.04  5062.0  317.54  5077.1  318.35  5099.2  321.90
  5105.6  323.98  5111.2  324.72  5115.8  326.34  5120.9  326.34  5141.2  331.13
  5148.5  331.91  5153.6  332.98  5161.5  333.29  5170.6  332.53  5174.7  332.53
#Mann=4,-1,0
  4672.7    0.05       0  4853.1    0.12       0  5058.0    0.07       0
  5062.0    0.12       0
Bank Sta=5058,5062
Exp/Cntr=0.3,0.1

Type RM Length L Ch R = 1,649,214,214,214
BEGIN DESCRIPTION:
Walnut75 0.7
END DESCRIPTION:
XS GIS Cut Line= 3
      2739883.16      6744761.38      2740206.26      6744771.09
      2740252.42      6744771.28
#Sta/Elev= 30
  4706.8  326.79  4710.7  326.79  4719.6  325.95  4729.6  325.68  4739.7  325.23
  4749.7  324.56  4759.7  323.70  4779.7  322.83  4789.7  322.61  4799.7  322.20
  4809.7  321.17  4819.7  320.81  4839.7  319.73  4869.7  318.71  4899.7  317.92
  4909.7  317.93  4919.7  317.68  4929.7  316.97  4939.7  316.53  4952.7  316.26
  4969.8  315.99  5006.6  315.72  5019.8  315.74  5025.4  315.63  5025.7  315.13
  5029.2  315.13  5029.4  315.63  5039.8  315.73  5069.8  316.58  5076.2  316.41
#Mann=5,-1,0
  4706.8    0.05       0  4952.7    0.12       0  5006.6    0.05       0
  5025.4    0.07       0  5029.4    0.05       0
Bank Sta=5025.4,5029.4
Exp/Cntr=0.3,0.1

Type RM Length L Ch R = 1,435,209,209,209
BEGIN DESCRIPTION:
Walnut75 0.4
END DESCRIPTION:
XS GIS Cut Line= 3
      2739923.34      6744922.27      2740195.17      6744959.71
      2740246.29      6744955.38
#Sta/Elev= 30
  4736.6  322.75  4740.5  322.75  4749.4  321.90  4764.2  321.02  4769.6  320.13
  4799.9  319.14  4830.1  317.73  4841.3  317.04  4860.4  316.33  4900.8  315.62
  4921.0  314.53  4929.5  314.34  4941.2  314.57  4951.3  314.55  4961.4  314.00
  4971.5  312.56  4980.1  311.02  4983.2  309.11  4983.4  308.61  4986.9  308.61
  4987.2  309.11  4991.6  309.69  5001.7  312.06  5008.9  313.52  5021.9  313.40
  5041.9  313.52  5051.0  313.37  5056.0  313.06  5059.6  313.28  5062.3  313.28
#Mann=4,-1,0
  4736.6    0.05       0  4929.5     0.1       0  4983.2    0.07       0
  4987.2     0.1       0
Bank Sta=4983.2,4987.2
Exp/Cntr=0.3,0.1

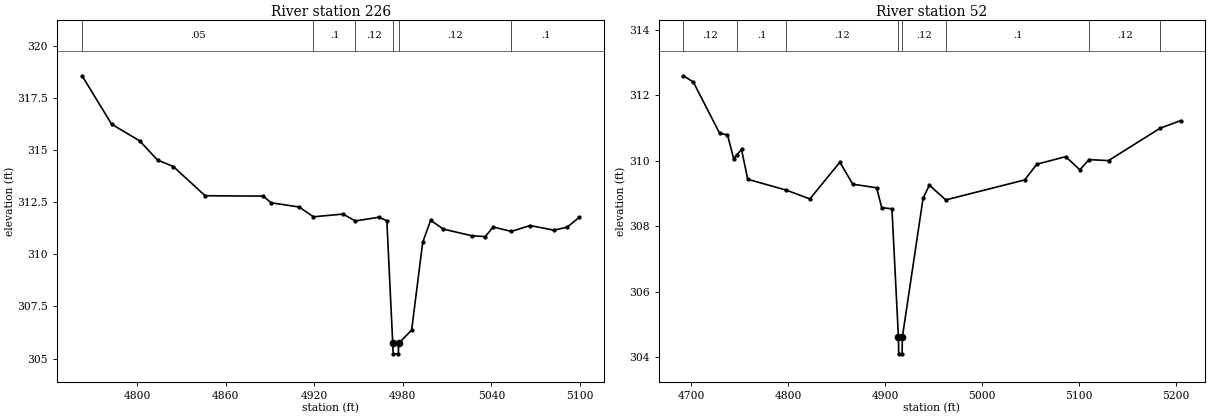
Type RM Length L Ch R = 1,226,174,174,174
BEGIN DESCRIPTION:
Walnut75 0.2
END DESCRIPTION:
XS GIS Cut Line= 3
      2739938.54      6745040.13      2740186.85      6745138.62
      2740252.03      6745114.30
#Sta/Elev= 30
  4762.8  318.56  4782.8  316.24  4801.8  315.44  4813.9  314.52  4824.6  314.21
  4846.1  312.81  4885.5  312.79  4890.9  312.47  4909.8  312.27  4919.5  311.80
  4939.5  311.93  4947.9  311.60  4963.8  311.78  4969.2  311.61  4973.2  305.73
  4973.5  305.23  4977.0  305.23  4977.2  305.73  4986.0  306.37  4993.5  310.58
  4998.9  311.63  5007.5  311.21  5026.8  310.89  5035.9  310.85  5041.2  311.31
  5053.6  311.10  5066.2  311.38  5082.4  311.16  5091.2  311.30  5099.5  311.77
#Mann=6,-1,0
  4762.8    0.05       0  4919.5     0.1       0  4947.9    0.12       0
  4973.2    0.07       0  4977.2    0.12       0  5053.6     0.1       0
Bank Sta=4973.2,4977.2
Exp/Cntr=0.3,0.1

Type RM Length L Ch R = 1,52,0,0,0
BEGIN DESCRIPTION:
Walnut75 0.1
END DESCRIPTION:
XS GIS Cut Line= 5
      2739826.95      6745156.54      2739940.09      6745246.03
      2740062.54      6745293.55      2740136.81      6745238.62
      2740221.08      6745121.09
#Sta/Elev= 30
  4692.0  312.59  4702.2  312.40  4729.4  310.83  4737.4  310.79  4743.8  310.06
  4747.2  310.18  4751.9  310.34  4758.3  309.43  4797.9  309.10  4822.4  308.83
  4853.3  309.95  4866.6  309.28  4891.2  309.17  4896.5  308.56  4907.0  308.53
  4913.7  304.60  4914.0  304.10  4917.5  304.10  4917.7  304.60  4939.1  308.85
  4945.6  309.25  4962.5  308.80  5043.9  309.41  5056.4  309.89  5086.1  310.12
  5100.8  309.72  5110.2  310.03  5130.3  310.00  5183.6  310.99  5204.6  311.22
#Mann=8,-1,0
  4692.0    0.12       0  4747.2     0.1       0  4797.9    0.12       0
  4913.7    0.07       0  4917.7    0.12       0  4962.5     0.1       0
  5110.2    0.12       0  5183.6     0.1       0
Bank Sta=4913.7,4917.7
Exp/Cntr=0.3,0.1

Chan Stop Cuts=-1