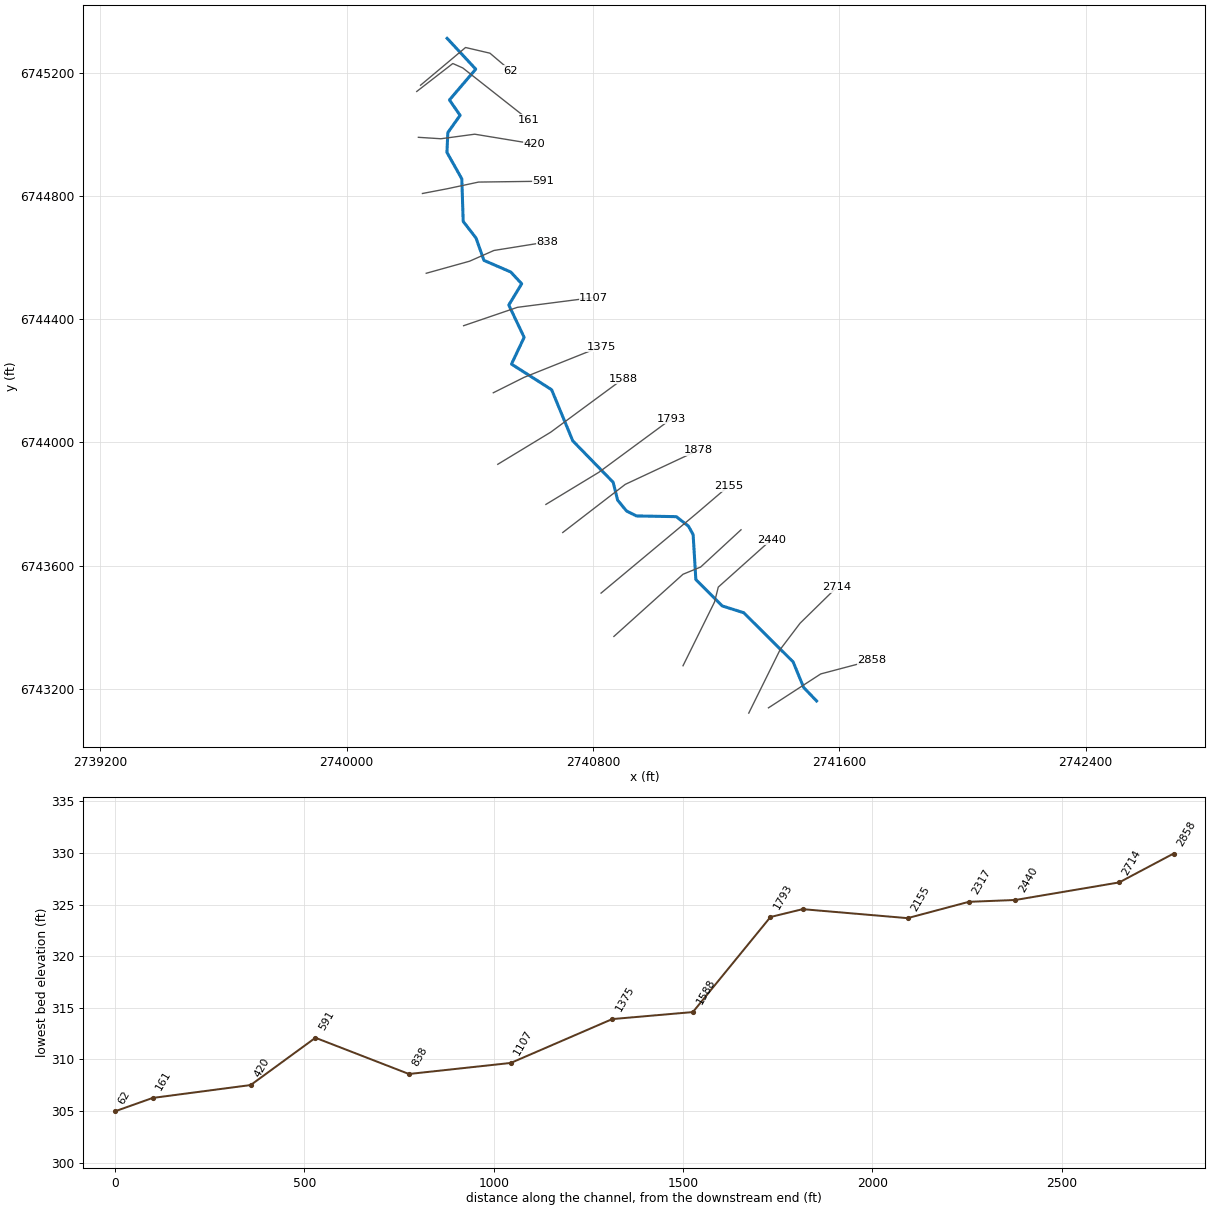
--- Walnut76.prj (project) ---

Proj Title=Walnut76 Base Level Engineering
Current Plan=p01
Default Exp/Contr=0.3,0.1
English Units
Geom File=g01
Flow File=f01
Plan File=p01
Y Axis Title=Elevation
X Axis Title(PF)=Main Channel Distance
X Axis Title(XS)=Station
BEGIN DESCRIPTION:
Walnut76
END DESCRIPTION:
DSS Export Rating Curves= 0
DSS Export Rating Curve Sorted= 0
DSS Export Volume Flow Curves= 0
DXF OffsetX= 0
DXF OffsetY= 0
DXF ScaleX= 1
DXF ScaleY= 10

--- Walnut76.p01 (plan) ---

Plan Title=Multiple Run
Program Version=4.10
Short Identifier=Multiple
Geom File=g01
Flow File=f01
Subcritical Flow
K Sum by GR= 0
Std Step Tol= 0.01
Critical Tol= 0.01
Num of Std Step Trials= 20
Max Error Tol= 0.3
Flow Tol Ratio= 0.001
Split Flow NTrial= 30
Split Flow Tol= 0.02
Split Flow Ratio= 0.02
Log Output Level= 0
Friction Slope Method= 1
Unsteady Friction Slope Method= 2
Unsteady Bridges Friction Slope Method= 1
Parabolic Critical Depth
Global Vel Dist= 1 , 1 , 1
Global Log Level= 0
CheckData=True
Encroach Param=-1 ,0,0, 0
BEGIN DESCRIPTION:
Multiple Run
END DESCRIPTION:
Computation Interval=1HOUR
Output Interval=1HOUR
Run HTab= 0
Run UNet= 0
Run PostProcess= 0
Run WQNet= 0
UNET Theta= 1
UNET Theta Warmup= 1
UNET ZTol= 0.02
UNET ZSATol= 0.05
UNET MxIter= 20
UNET MaxInSteps= 0
UNET DtIC= 0
UNET DtMin= 0
UNET MaxCRTS= 20
UNET WFStab= 2
UNET SFStab= 1
UNET WFX= 1
UNET SFX= 1
UNET DSS MLevel= 4
UNET DZMax Abort= 100
UNET Convert EG Bridges= 0
UNET Use Existing IB Tables=-1
UNET Froude Reduction=False
UNET Froude Limit= 1
UNET Froude Power= 10
UNET Time Slicing=0,0, 5
UNET Junction Losses=0
Instantaneous Interval=1HOUR
Write IC File= 0
Write IC File at Sim End=0
Echo Input=False
Echo Parameters=False
Echo Output=False
Write Detailed= 0
WQ AD Non Conservative
WQ ULTIMATE=-1
WQ Max Comp Step=1HOUR
WQ Output Interval=15MIN
WQ Output Selected Increments= 0
WQ Output face flow=0
WQ Output face velocity=0
WQ Output face area=0
WQ Output face dispersion=0
WQ Output cell volume=0
WQ Output cell surface area=0
WQ Output cell continuity=0
WQ Output cumulative cell continuity=0
WQ Output face conc=0
WQ Output face dconc_dx=0
WQ Output face courant=0
WQ Output face peclet=0
WQ Output face adv mass=0
WQ Output face disp mass=0
WQ Output cell mass=0
WQ Output cell source sink temp=0
WQ Output cell source sink nsm=0
WQ Output MaxMinRange=-1
WQ Daily Max Min Mean=-1
WQ Daily Range=0
WQ Daily Time=0
WQ Create Restart=0
WQ Fixed Restart=0
WQ System Summary=0
WQ Use Fixed Temperature=0
Sorting and Armoring Iterations= 10
XS Update Threshold= 0.02
Hydraulics Update Threshold= 0.02
Energy Slope Method= 1
Volume Change Method= 0
XS Weighting Method= 0
Number of US Weighted Cross Sections= 1
Number of DS Weighted Cross Sections= 1
Upstream XS Weight=0.25
Main XS Weight=0.5
Downstream XS Weight=0.25
Number of DS XS's Weighted with US Boundary= 1
Upstream Boundary Weight= 1
Weight of XSs Associated with US Boundary= 0
Number of US XS's Weighted with DS Boundary= 1
Downstream Boundary Weight= 0.5
Weight of XSs Associated with DS Boundary= 0.5
Sediment Output Level= 4
Mass or Volume Output= 0
Output Increment Type= 1
Profile and TS Output Increment= 10
XS Output Flag= 0
XS Output Increment= 10
Disregard all LS=0
Disregard all Conn=0
Disregard all Breaches=0
Disregard all Pumps=0

--- Walnut76.f01 (steady flow) ---

Flow Title=Multiple
Number of Profiles=7
Profile Names=10-year,25-year,50-year,1pct_min,100-year,1pct_plu,500-year
River Rch & RM= Walnut76,Reach-1,2858
     238     305     357     209     416     831     566
Boundary for River Rch & Prof#=Walnut76,Reach-1,1
Up Type=0
Dn Type=3
Dn Slope=0.013
Boundary for River Rch & Prof#=Walnut76,Reach-1,2
Up Type=0
Dn Type=3
Dn Slope=0.013
Boundary for River Rch & Prof#=Walnut76,Reach-1,3
Up Type=0
Dn Type=3
Dn Slope=0.013
Boundary for River Rch & Prof#=Walnut76,Reach-1,4
Up Type=0
Dn Type=3
Dn Slope=0.013
Boundary for River Rch & Prof#=Walnut76,Reach-1,5
Up Type=0
Dn Type=3
Dn Slope=0.013
Boundary for River Rch & Prof#=Walnut76,Reach-1,6
Up Type=0
Dn Type=3
Dn Slope=0.013
Boundary for River Rch & Prof#=Walnut76,Reach-1,7
Up Type=0
Dn Type=3
Dn Slope=0.013

--- Walnut76.g01 (geometry) ---

Geom Title=Existing Conditions

River Reach=Walnut76,Reach-1
Reach XY= 30
      2741526.00      6743161.00      2741483.94      6743204.86
      2741449.72      6743287.83      2741289.21      6743447.37
      2741219.93      6743469.15      2741133.81      6743554.79
      2741125.01      6743700.73      2741109.76      6743728.23
      2741070.35      6743759.02      2740941.04      6743761.35
      2740908.86      6743777.28      2740879.87      6743812.40
      2740865.21      6743870.66      2740734.14      6744004.94
      2740665.36      6744171.00      2740535.03      6744253.99
      2740576.19      6744340.79      2740526.24      6744445.67
      2740568.28      6744514.66      2740532.67      6744552.84
      2740445.63      6744590.53      2740419.85      6744663.15
      2740378.25      6744716.93      2740373.73      6744855.06
      2740325.42      6744940.96      2740328.36      6745005.11
      2740368.19      6745061.10      2740333.57      6745111.01
      2740419.01      6745211.00      2740326.00      6745311.00

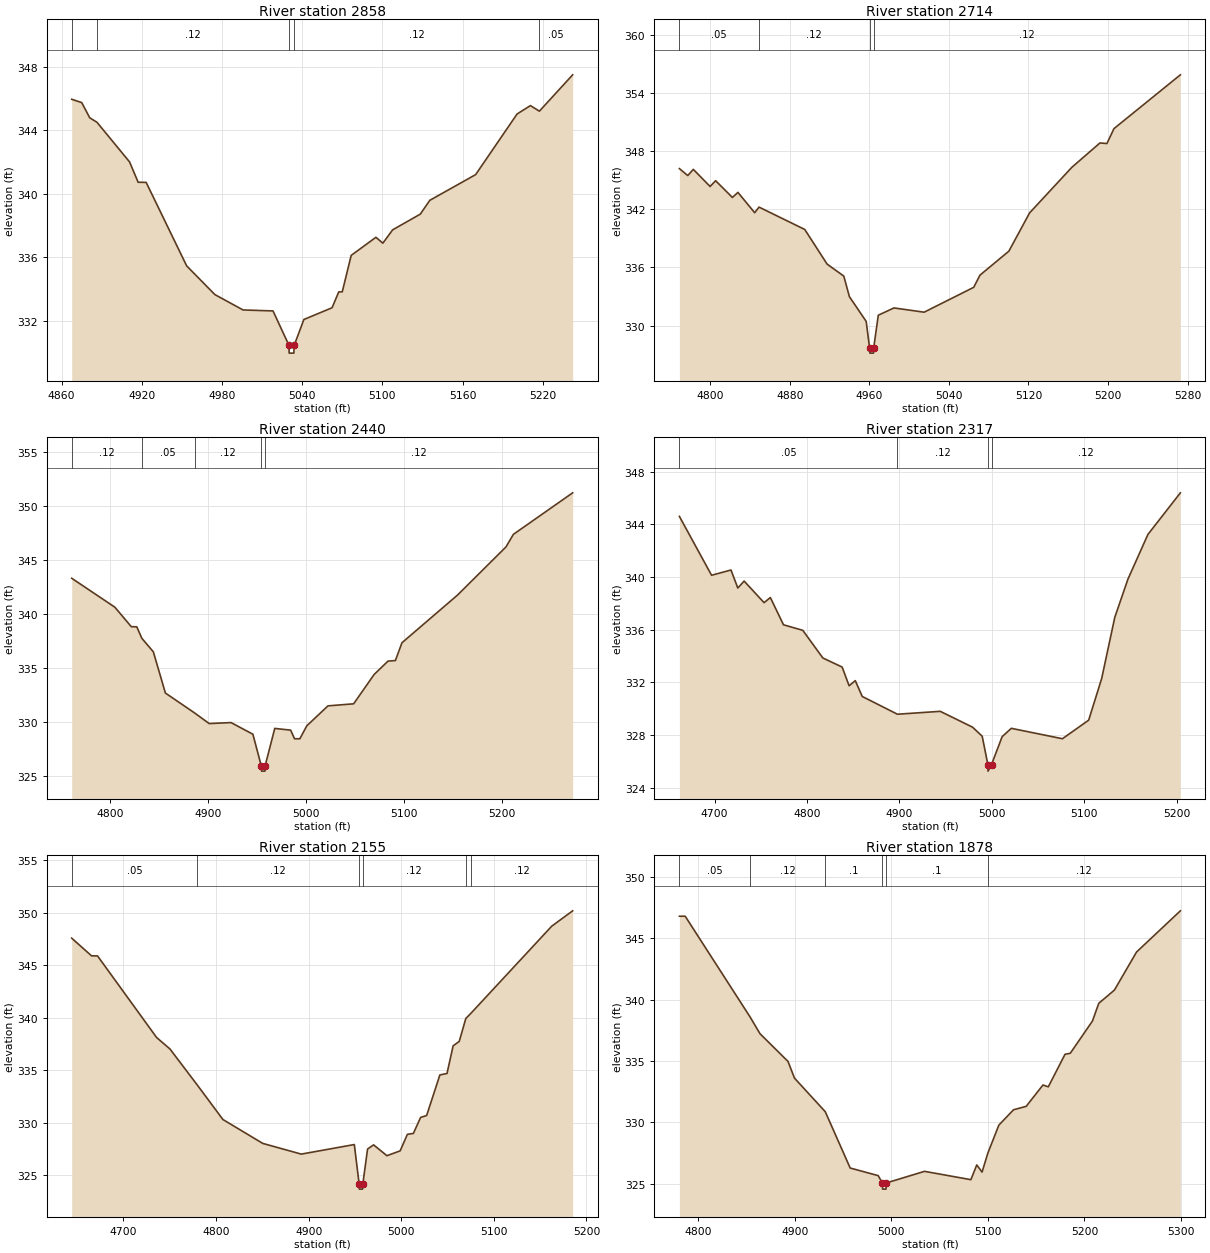
Type RM Length L Ch R = 1,2858,144,144,144
BEGIN DESCRIPTION:
Walnut76 10.0
END DESCRIPTION:
XS GIS Cut Line= 3
      2741369.67      6743138.71      2741539.51      6743248.79
      2741706.19      6743292.82
#Sta/Elev= 30
  4867.6  345.95  4875.1  345.74  4881.1  344.78  4886.5  344.50  4910.9  342.00
  4917.3  340.72  4923.3  340.71  4953.6  335.45  4974.7  333.64  4995.8  332.67
  5018.2  332.61  5030.1  330.45  5030.3  329.95  5033.8  329.95  5034.1  330.45
  5041.3  332.07  5062.4  332.81  5067.4  333.81  5070.0  333.81  5076.7  336.11
  5095.2  337.25  5100.4  336.88  5107.7  337.72  5128.4  338.71  5135.5  339.58
  5169.8  341.20  5200.8  345.02  5210.8  345.55  5217.5  345.20  5242.4  347.49
#Mann=5,-1,0
  4867.6    0.05       0  4886.5    0.12       0  5030.1    0.07       0
  5034.1    0.12       0  5217.5    0.05       0
Bank Sta=5030.1,5034.1
Exp/Cntr=0.3,0.1

Type RM Length L Ch R = 1,2714,274,274,274
BEGIN DESCRIPTION:
Walnut76 9.5
END DESCRIPTION:
XS GIS Cut Line= 4
      2741305.68      6743121.65      2741408.03      6743328.44
      2741472.34      6743413.29      2741591.57      6743529.93
#Sta/Elev= 30
  4768.8  346.22  4777.2  345.50  4782.8  346.14  4799.7  344.37  4805.2  344.97
  4822.1  343.24  4827.7  343.76  4844.5  341.66  4848.9  342.24  4894.9  339.93
  4917.4  336.35  4934.2  335.11  4939.8  332.99  4956.7  330.43  4960.2  327.65
  4960.5  327.15  4964.0  327.15  4964.2  327.65  4968.9  331.07  4984.7  331.82
  5015.0  331.38  5064.9  333.95  5071.2  335.21  5100.3  337.69  5121.1  341.64
  5163.6  346.35  5191.9  348.87  5198.9  348.81  5206.0  350.35  5272.8  355.91
#Mann=4,-1,0
  4768.8    0.05       0  4848.9    0.12       0  4960.2    0.07       0
  4964.2    0.12       0
Bank Sta=4960.2,4964.2
Exp/Cntr=0.3,0.1

Type RM Length L Ch R = 1,2440,123,123,123
BEGIN DESCRIPTION:
Walnut76 9.0
END DESCRIPTION:
XS GIS Cut Line= 4
      2741092.14      6743275.28      2741194.49      6743482.09
      2741206.71      6743530.48      2741378.59      6743684.13
#Sta/Elev= 30
  4761.2  343.33  4805.2  340.65  4822.0  338.84  4827.6  338.83  4832.8  337.76
  4844.5  336.51  4856.8  332.69  4886.5  330.85  4901.5  329.86  4923.8  329.95
  4946.1  328.87  4954.6  325.95  4954.9  325.45  4958.4  325.45  4958.6  325.95
  4968.4  329.41  4984.6  329.25  4988.6  328.45  4994.0  328.45  5001.1  329.65
  5022.7  331.50  5048.9  331.69  5069.8  334.41  5084.0  335.65  5091.5  335.70
  5098.2  337.35  5155.0  341.78  5204.4  346.24  5211.9  347.40  5272.4  351.25
#Mann=5,-1,0
  4761.2    0.12       0  4832.8    0.05       0  4886.5    0.12       0
  4954.6    0.07       0  4958.6    0.12       0
Bank Sta=4954.6,4958.6
Exp/Cntr=0.3,0.1

Type RM Length L Ch R = 1,2317,162,162,162
BEGIN DESCRIPTION:
Walnut76 8.5
END DESCRIPTION:
XS GIS Cut Line= 4
      2740867.68      6743370.39      2741092.13      6743572.15
      2741149.42      6743595.58      2741280.54      6743716.41
#Sta/Elev= 30
  4661.9  344.61  4696.7  340.14  4717.7  340.54  4725.1  339.17  4731.9  339.70
  4753.5  338.06  4760.3  338.45  4774.5  336.38  4795.4  335.96  4817.1  333.86
  4838.0  333.17  4845.5  331.75  4852.2  332.14  4859.7  330.94  4897.8  329.59
  4944.1  329.81  4979.0  328.61  4989.5  327.92  4995.6  325.77  4995.8  325.27
  4999.6  325.77  5011.1  327.89  5021.0  328.52  5076.3  327.73  5104.7  329.14
  5118.8  332.31  5133.0  336.96  5147.2  339.85  5168.8  343.24  5203.9  346.40
#Mann=4,-1,0
  4661.9    0.05       0  4897.8    0.12       0  4995.6    0.07       0
  4999.6    0.12       0
Bank Sta=4995.6,4999.6
Exp/Cntr=0.3,0.1

Type RM Length L Ch R = 1,2155,277,277,277
BEGIN DESCRIPTION:
Walnut76 8.0
END DESCRIPTION:
XS GIS Cut Line= 3
      2740826.03      6743511.03      2741133.80      6743767.46
      2741240.58      6743858.62
#Sta/Elev= 30
  4644.1  347.56  4665.5  345.88  4672.0  345.87  4735.8  338.11  4750.2  337.02
  4779.9  333.57  4807.4  330.31  4850.4  328.04  4892.0  327.02  4949.3  327.93
  4954.5  324.19  4954.7  323.69  4958.2  323.69  4958.5  324.19  4963.6  327.50
  4970.1  327.90  4984.5  326.87  4998.8  327.33  5006.6  328.90  5013.1  328.99
  5020.9  330.51  5027.4  330.69  5041.7  334.55  5049.4  334.69  5056.0  337.32
  5062.6  337.74  5069.7  339.92  5075.6  340.45  5162.5  348.70  5185.1  350.16
#Mann=6,-1,0
  4644.1    0.05       0  4779.9    0.12       0  4954.5    0.07       0
  4958.5    0.12       0  5069.7     0.1       0  5075.6    0.12       0
Bank Sta=4954.5,4958.5
Exp/Cntr=0.3,0.1

Type RM Length L Ch R = 1,1878,85,85,85
BEGIN DESCRIPTION:
Walnut76 7.0
END DESCRIPTION:
XS GIS Cut Line= 3
      2740701.53      6743707.58      2740904.63      6743863.81
      2741142.59      6743975.03
#Sta/Elev= 30
  4780.5  346.81  4786.5  346.81  4853.6  338.61  4864.0  337.23  4893.0  334.97
  4899.7  333.61  4931.6  330.87  4957.4  326.28  4986.4  325.66  4990.7  325.06
  4991.0  324.56  4994.5  324.56  4994.7  325.06  5034.4  326.01  5082.4  325.33
  5088.5  326.53  5094.0  325.95  5100.0  327.50  5111.4  329.78  5126.6  331.03
  5139.7  331.31  5157.1  333.05  5162.6  332.90  5179.9  335.55  5185.4  335.64
  5208.3  338.26  5214.9  339.71  5231.1  340.79  5254.0  343.89  5299.4  347.25
#Mann=6,-1,0
  4780.5    0.05       0  4853.6    0.12       0  4931.6     0.1       0
  4990.7    0.07       0  4994.7     0.1       0  5100.0    0.12       0
Bank Sta=4990.7,4994.7
Exp/Cntr=0.3,0.1

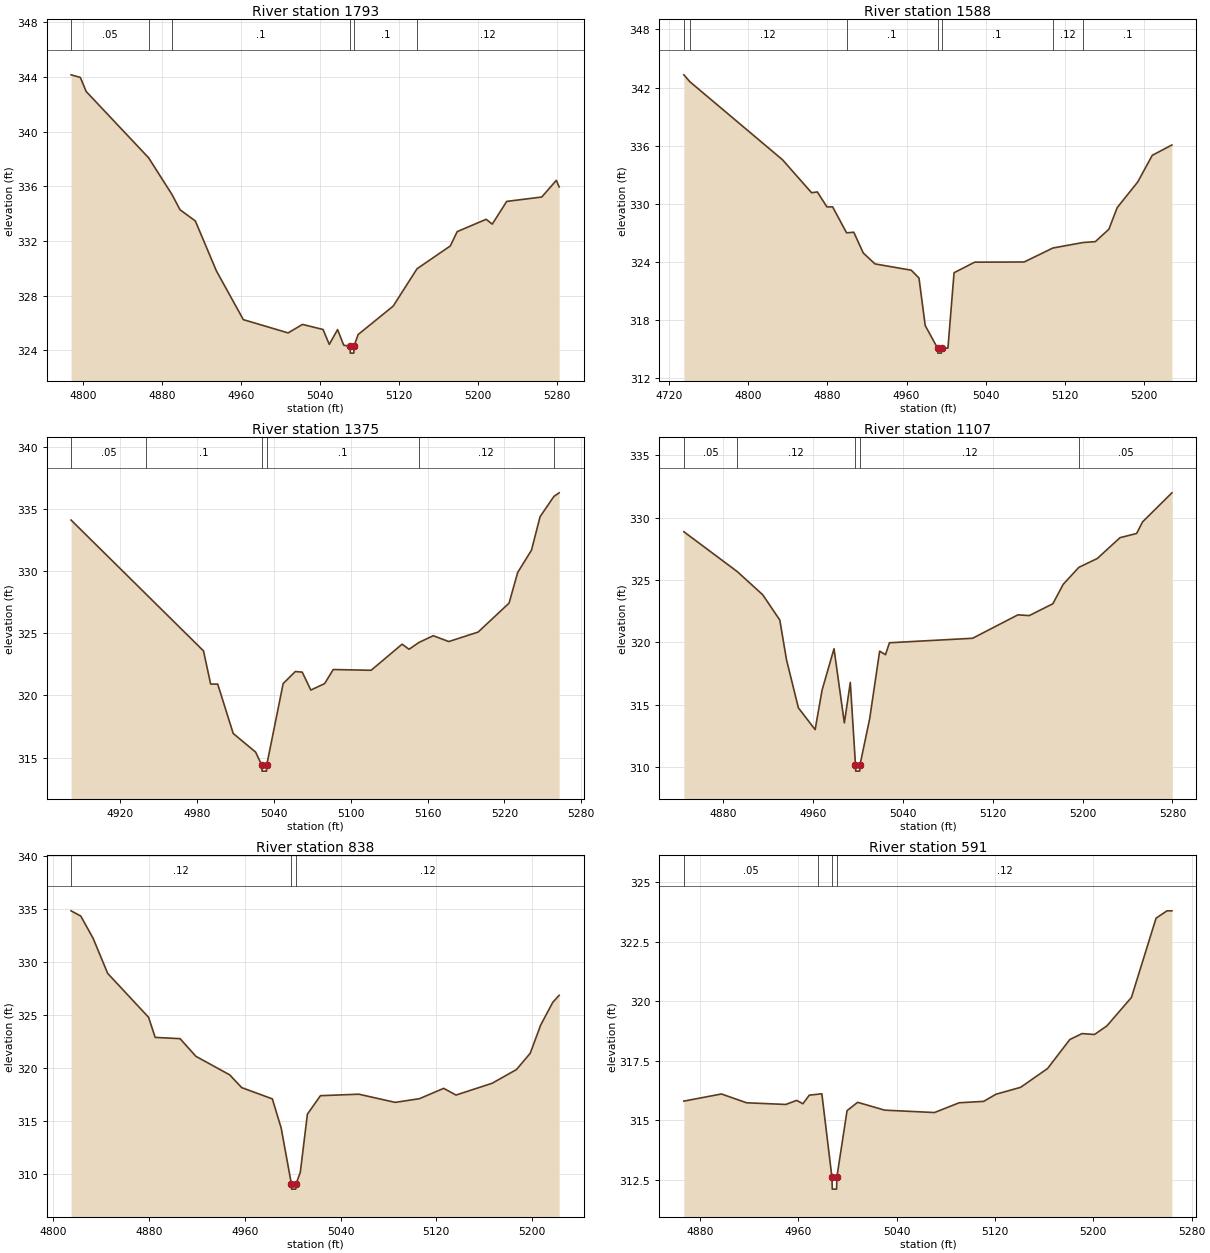
Type RM Length L Ch R = 1,1793,205,205,205
BEGIN DESCRIPTION:
Walnut76 6.5
END DESCRIPTION:
XS GIS Cut Line= 3
      2740646.85      6743798.73      2740818.69      6743902.87
      2741054.77      6744076.69
#Sta/Elev= 30
  4787.8  344.16  4797.2  343.97  4803.1  342.94  4866.3  338.09  4890.0  335.40
  4898.1  334.29  4913.6  333.47  4934.9  329.82  4962.2  326.25  5007.5  325.28
  5022.1  325.90  5042.9  325.53  5049.2  324.44  5057.6  325.52  5063.8  324.38
  5070.2  324.30  5070.5  323.80  5074.0  323.80  5074.2  324.30  5078.4  325.16
  5113.9  327.24  5138.0  329.97  5171.7  331.64  5178.7  332.69  5208.0  333.59
  5214.2  333.24  5228.8  334.90  5264.3  335.22  5279.0  336.44  5281.9  335.96
#Mann=6,-1,0
  4787.8    0.05       0  4866.3    0.12       0  4890.0     0.1       0
  5070.2    0.07       0  5074.2     0.1       0  5138.0    0.12       0
Bank Sta=5070.2,5074.2
Exp/Cntr=0.3,0.1

Type RM Length L Ch R = 1,1588,213,213,213
BEGIN DESCRIPTION:
Walnut76 6.0
END DESCRIPTION:
XS GIS Cut Line= 3
      2740490.56      6743928.91      2740662.44      6744033.08
      2740898.40      6744206.81
#Sta/Elev= 30
  4734.6  343.32  4740.9  342.59  4834.5  334.55  4863.9  331.15  4869.7  331.23
  4879.4  329.69  4885.2  329.69  4899.3  327.01  4906.6  327.07  4916.2  324.93
  4928.1  323.80  4964.8  323.15  4972.6  322.34  4978.9  317.44  4991.5  315.09
  4991.7  314.59  4995.2  314.59  4995.5  315.09  5001.9  315.11  5008.1  322.89
  5029.0  323.98  5079.1  324.00  5108.1  325.44  5138.7  326.01  5151.1  326.10
  5164.8  327.38  5173.2  329.61  5194.0  332.26  5208.7  335.01  5228.6  336.08
#Mann=7,-1,0
  4734.6    0.05       0  4740.9    0.12       0  4899.3     0.1       0
  4991.5    0.07       0  4995.5     0.1       0  5108.1    0.12       0
  5138.7     0.1       0
Bank Sta=4991.5,4995.5
Exp/Cntr=0.3,0.1

Type RM Length L Ch R = 1,1375,268,268,268
BEGIN DESCRIPTION:
Walnut76 5.0
END DESCRIPTION:
XS GIS Cut Line= 3
      2740476.01      6744161.00      2740576.00      6744211.00
      2740826.04      6744311.02
#Sta/Elev= 30
  4881.6  334.10  4940.1  328.15  4985.0  323.58  4990.6  320.91  4996.1  320.91
  5008.2  316.94  5025.7  315.44  5030.4  314.41  5030.7  313.91  5034.2  313.91
  5034.4  314.41  5047.2  320.95  5056.7  321.92  5062.1  321.87  5068.8  320.43
  5079.6  320.95  5086.3  322.08  5115.9  322.02  5140.1  324.12  5145.5  323.71
  5153.1  324.25  5164.4  324.80  5176.5  324.33  5199.4  325.09  5223.6  327.42
  5230.3  329.88  5241.1  331.68  5247.8  334.37  5258.6  336.00  5262.7  336.29
#Mann=6,-1,0
  4881.6    0.05       0  4940.1     0.1       0  5030.4    0.07       0
  5034.4     0.1       0  5153.1    0.12       0  5258.6    0.05       0
Bank Sta=5030.4,5034.4
Exp/Cntr=0.3,0.1

Type RM Length L Ch R = 1,1107,269,269,269
BEGIN DESCRIPTION:
Walnut76 4.0
END DESCRIPTION:
XS GIS Cut Line= 3
      2740379.60      6744378.58      2740554.38      6744438.23
      2740801.87      6744470.03
#Sta/Elev= 30
  4845.3  328.87  4892.7  325.68  4915.5  323.81  4930.7  321.78  4936.6  318.61
  4947.2  314.74  4962.1  312.99  4968.3  316.17  4978.9  319.48  4988.1  313.53
  4993.4  316.78  4998.0  310.16  4998.2  309.66  5001.7  309.66  5002.0  310.16
  5010.6  313.85  5019.5  319.29  5024.7  319.00  5028.2  319.96  5102.2  320.32
  5142.5  322.20  5152.6  322.14  5173.6  323.09  5182.8  324.65  5196.7  326.01
  5213.1  326.72  5233.3  328.39  5248.1  328.73  5253.4  329.66  5279.5  331.99
#Mann=5,-1,0
  4845.3    0.05       0  4892.7    0.12       0  4998.0    0.07       0
  5002.0    0.12       0  5196.7    0.05       0
Bank Sta=4998,5002
Exp/Cntr=0.3,0.1

Type RM Length L Ch R = 1,838,247,247,247
BEGIN DESCRIPTION:
Walnut76 3.0
END DESCRIPTION:
XS GIS Cut Line= 4
      2740258.23      6744548.71      2740398.83      6744587.81
      2740478.10      6744622.69      2740651.25      6744650.40
#Sta/Elev= 30
  4814.8  334.80  4822.9  334.31  4833.2  332.22  4845.4  328.91  4879.6  324.77
  4885.1  322.88  4905.9  322.76  4919.1  321.10  4947.4  319.35  4957.4  318.15
  4983.0  317.09  4990.4  314.34  4998.9  309.09  4999.1  308.59  5002.6  308.59
  5002.9  309.09  5006.4  310.19  5012.3  315.65  5023.2  317.39  5055.3  317.53
  5085.7  316.76  5106.0  317.11  5126.2  318.08  5136.5  317.45  5166.7  318.56
  5187.0  319.85  5198.5  321.38  5207.3  324.05  5217.4  326.19  5222.7  326.84
#Mann=3,-1,0
  4814.8    0.12       0  4998.9    0.07       0  5002.9    0.12       0
Bank Sta=4998.9,5002.9
Exp/Cntr=0.3,0.1

Type RM Length L Ch R = 1,591,171,171,171
BEGIN DESCRIPTION:
Walnut76 2.0
END DESCRIPTION:
XS GIS Cut Line= 4
      2740245.90      6744807.56      2740327.34      6744823.11
      2740428.17      6744844.60      2740638.95      6744847.37
#Sta/Elev= 30
  4867.1  315.80  4897.7  316.10  4918.1  315.73  4950.0  315.66  4958.8  315.83
  4963.9  315.69  4969.1  316.05  4976.1  316.09  4979.3  316.11  4987.5  312.60
  4987.8  312.10  4991.3  312.10  4991.5  312.60  4999.8  315.40  5008.4  315.75
  5030.4  315.42  5070.9  315.32  5090.9  315.73  5110.9  315.79  5120.9  316.09
  5140.9  316.38  5162.8  317.17  5180.9  318.39  5190.9  318.64  5200.9  318.60
  5211.0  318.96  5231.0  320.16  5251.0  323.49  5259.9  323.80  5263.9  323.80
#Mann=4,-1,0
  4867.1    0.05       0  4976.1    0.12       0  4987.5    0.07       0
  4991.5    0.12       0
Bank Sta=4987.5,4991.5
Exp/Cntr=0.3,0.1

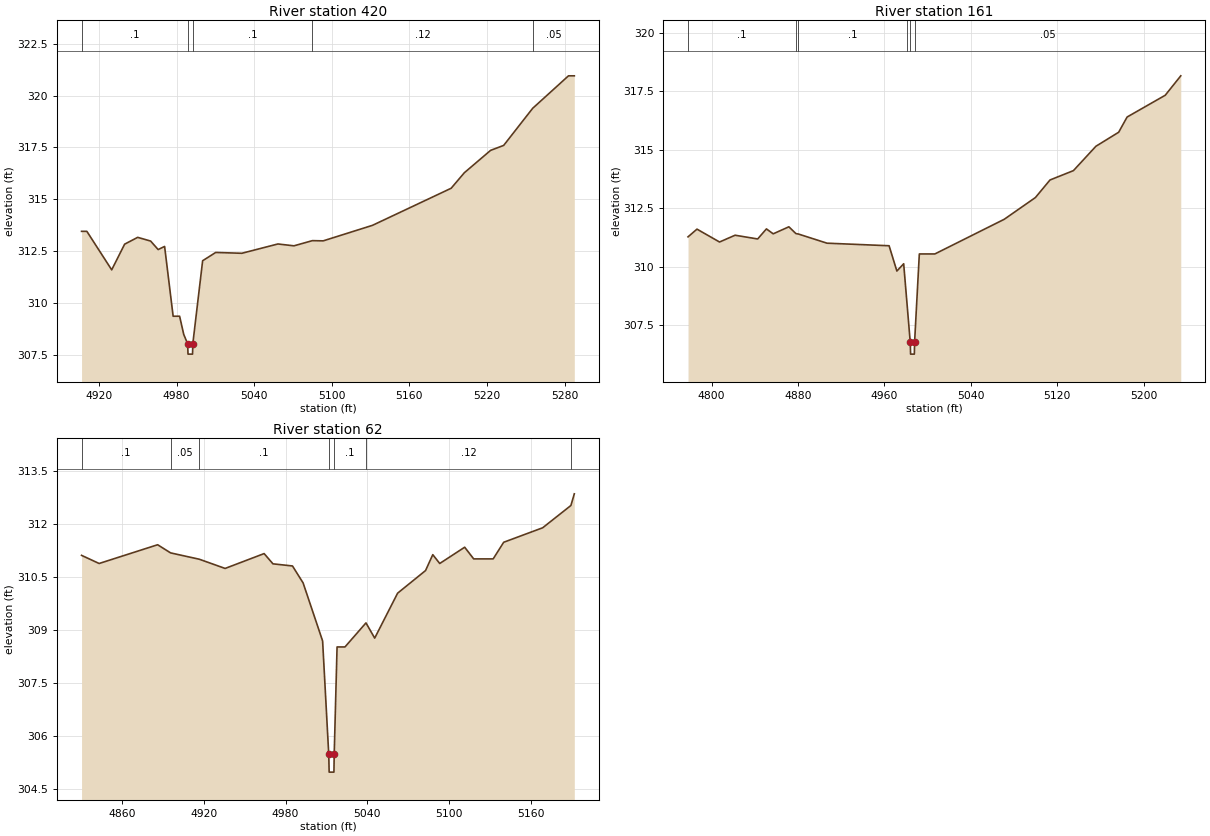
Type RM Length L Ch R = 1,420,259,259,259
BEGIN DESCRIPTION:
Walnut76 1.5
END DESCRIPTION:
XS GIS Cut Line= 4
      2740232.73      6744989.81      2740305.81      6744985.16
      2740415.69      6744999.93      2740609.89      6744968.03
#Sta/Elev= 30
  4906.6  313.45  4910.7  313.45  4929.9  311.59  4939.9  312.83  4950.0  313.16
  4960.0  312.98  4965.8  312.57  4970.8  312.72  4977.4  309.35  4982.4  309.35
  4985.6  308.47  4988.6  308.02  4988.9  307.52  4992.4  307.52  4992.6  308.02
  5000.2  312.03  5010.3  312.43  5030.5  312.39  5058.4  312.84  5070.8  312.75
  5085.0  313.00  5093.4  312.99  5131.5  313.74  5192.3  315.53  5202.5  316.28
  5222.8  317.36  5232.9  317.60  5255.3  319.39  5283.0  320.96  5287.5  320.96
#Mann=5,-1,0
  4906.6     0.1       0  4988.6    0.07       0  4992.6     0.1       0
  5085.0    0.12       0  5255.3    0.05       0
Bank Sta=4988.6,4992.6
Exp/Cntr=0.3,0.1

Type RM Length L Ch R = 1,161,99,99,99
BEGIN DESCRIPTION:
Walnut76 1.0
END DESCRIPTION:
XS GIS Cut Line= 4
      2740227.39      6745138.58      2740344.51      6745229.29
      2740376.85      6745214.90      2740591.19      6745046.20
#Sta/Elev= 30
  4778.2  311.28  4786.5  311.61  4807.4  311.06  4821.8  311.35  4842.7  311.19
  4850.8  311.62  4857.1  311.41  4871.6  311.71  4878.1  311.42  4880.5  311.40
  4906.9  311.01  4964.4  310.90  4971.6  309.82  4977.9  310.13  4980.7  308.59
  4984.0  306.77  4984.3  306.27  4987.8  306.27  4988.0  306.77  4992.4  310.55
  5006.8  310.55  5071.0  312.03  5099.9  312.96  5113.4  313.71  5135.1  314.11
  5155.9  315.15  5177.0  315.75  5184.8  316.40  5220.1  317.33  5234.5  318.16
#Mann=6,-1,0
  4778.2     0.1       0  4878.1    0.05       0  4880.5     0.1       0
  4980.7    0.05       0  4984.0    0.05       0  4988.0    0.05       0
Bank Sta=4984,4988
Exp/Cntr=0.3,0.1

Type RM Length L Ch R = 1,62,0,0,0
BEGIN DESCRIPTION:
Walnut76 0.5
END DESCRIPTION:
XS GIS Cut Line= 4
      2740239.75      6745158.86      2740385.89      6745281.23
      2740465.13      6745262.74      2740533.33      6745204.91
#Sta/Elev= 30
  4830.4  311.11  4843.3  310.88  4886.2  311.41  4895.7  311.18  4916.8  311.00
  4935.7  310.74  4964.3  311.16  4970.8  310.87  4985.1  310.81  4992.9  310.33
  5007.2  308.69  5011.7  305.48  5012.0  304.98  5015.5  304.98  5015.7  305.48
  5017.8  308.52  5023.6  308.52  5039.0  309.20  5045.4  308.77  5062.2  310.04
  5082.7  310.68  5088.0  311.13  5093.1  310.88  5111.4  311.34  5118.0  311.01
  5132.3  311.01  5140.0  311.48  5168.6  311.89  5189.3  312.52  5191.8  312.85
#Mann=7,-1,0
  4830.4     0.1       0  4895.7    0.05       0  4916.8     0.1       0
  5011.7    0.07       0  5015.7     0.1       0  5039.0    0.12       0
  5189.3    0.05       0
Bank Sta=5011.7,5015.7
Exp/Cntr=0.3,0.1

Chan Stop Cuts=-1