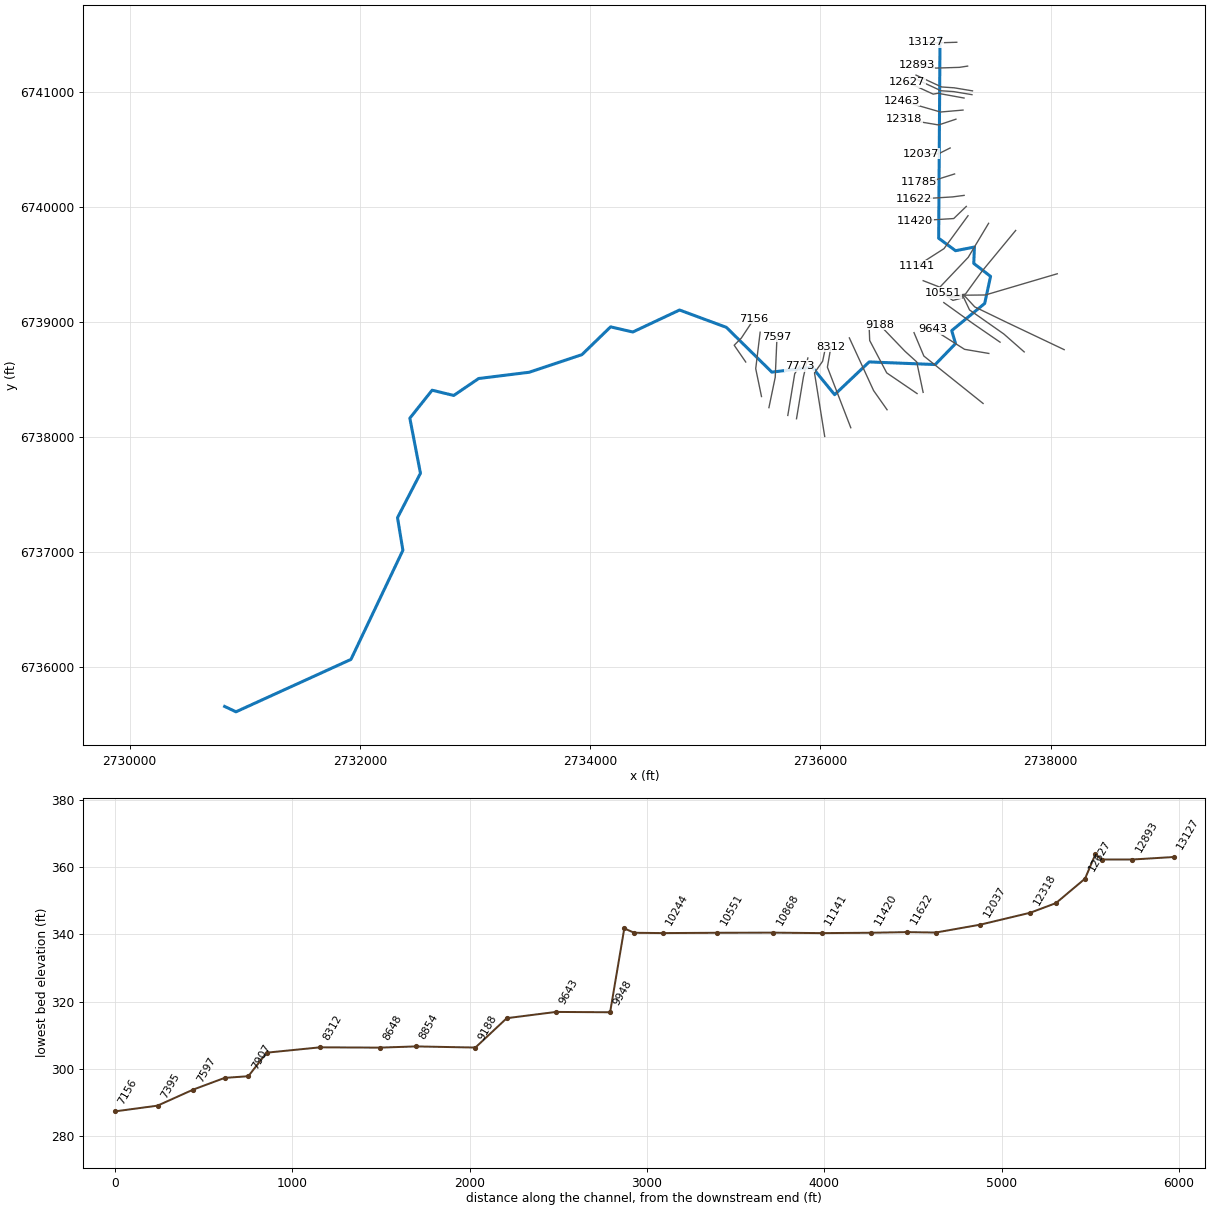
--- Walnut79.prj (project) ---

Proj Title=Walnut79 Base Level Engineering
Current Plan=p01
Default Exp/Contr=0.3,0.1
English Units
Geom File=g01
Flow File=f01
Plan File=p01
Y Axis Title=Elevation
X Axis Title(PF)=Main Channel Distance
X Axis Title(XS)=Station
BEGIN DESCRIPTION:
Walnut79
END DESCRIPTION:
DSS Export Rating Curves= 0
DSS Export Rating Curve Sorted= 0
DSS Export Volume Flow Curves= 0
DXF OffsetX= 0
DXF OffsetY= 0
DXF ScaleX= 1
DXF ScaleY= 10

--- Walnut79.p01 (plan) ---

Plan Title=Multiple Run
Program Version=4.10
Short Identifier=Multiple
Geom File=g01
Flow File=f01
Subcritical Flow
K Sum by GR= 0
Std Step Tol= 0.01
Critical Tol= 0.01
Num of Std Step Trials= 20
Max Error Tol= 0.3
Flow Tol Ratio= 0.001
Split Flow NTrial= 30
Split Flow Tol= 0.02
Split Flow Ratio= 0.02
Log Output Level= 0
Friction Slope Method= 1
Unsteady Friction Slope Method= 2
Unsteady Bridges Friction Slope Method= 1
Parabolic Critical Depth
Global Vel Dist= 1 , 1 , 1
Global Log Level= 0
CheckData=True
Encroach Param=-1 ,0,0, 0
BEGIN DESCRIPTION:
Multiple Run
END DESCRIPTION:
Computation Interval=1HOUR
Output Interval=1HOUR
Run HTab= 0
Run UNet= 0
Run PostProcess= 0
Run WQNet= 0
UNET Theta= 1
UNET Theta Warmup= 1
UNET ZTol= 0.02
UNET ZSATol= 0.05
UNET MxIter= 20
UNET MaxInSteps= 0
UNET DtIC= 0
UNET DtMin= 0
UNET MaxCRTS= 20
UNET WFStab= 2
UNET SFStab= 1
UNET WFX= 1
UNET SFX= 1
UNET DSS MLevel= 4
UNET DZMax Abort= 100
UNET Convert EG Bridges= 0
UNET Use Existing IB Tables=-1
UNET Froude Reduction=False
UNET Froude Limit= 1
UNET Froude Power= 10
UNET Time Slicing=0,0, 5
UNET Junction Losses=0
Instantaneous Interval=1HOUR
Write IC File= 0
Write IC File at Sim End=0
Echo Input=False
Echo Parameters=False
Echo Output=False
Write Detailed= 0
WQ AD Non Conservative
WQ ULTIMATE=-1
WQ Max Comp Step=1HOUR
WQ Output Interval=15MIN
WQ Output Selected Increments= 0
WQ Output face flow=0
WQ Output face velocity=0
WQ Output face area=0
WQ Output face dispersion=0
WQ Output cell volume=0
WQ Output cell surface area=0
WQ Output cell continuity=0
WQ Output cumulative cell continuity=0
WQ Output face conc=0
WQ Output face dconc_dx=0
WQ Output face courant=0
WQ Output face peclet=0
WQ Output face adv mass=0
WQ Output face disp mass=0
WQ Output cell mass=0
WQ Output cell source sink temp=0
WQ Output cell source sink nsm=0
WQ Output MaxMinRange=-1
WQ Daily Max Min Mean=-1
WQ Daily Range=0
WQ Daily Time=0
WQ Create Restart=0
WQ Fixed Restart=0
WQ System Summary=0
WQ Use Fixed Temperature=0
Sorting and Armoring Iterations= 10
XS Update Threshold= 0.02
Hydraulics Update Threshold= 0.02
Energy Slope Method= 1
Volume Change Method= 0
XS Weighting Method= 0
Number of US Weighted Cross Sections= 1
Number of DS Weighted Cross Sections= 1
Upstream XS Weight=0.25
Main XS Weight=0.5
Downstream XS Weight=0.25
Number of DS XS's Weighted with US Boundary= 1
Upstream Boundary Weight= 1
Weight of XSs Associated with US Boundary= 0
Number of US XS's Weighted with DS Boundary= 1
Downstream Boundary Weight= 0.5
Weight of XSs Associated with DS Boundary= 0.5
Sediment Output Level= 4
Mass or Volume Output= 0
Output Increment Type= 1
Profile and TS Output Increment= 10
XS Output Flag= 0
XS Output Increment= 10
Disregard all LS=0
Disregard all Conn=0
Disregard all Breaches=0
Disregard all Pumps=0

--- Walnut79.f01 (steady flow) ---

Flow Title=Multiple
Number of Profiles=7
Profile Names=10-year,25-year,50-year,1pct_min,100-year,1pct_plu,500-year
River Rch & RM= Walnut79,Reach-1,13127
     129     157     177     100     200     399     254
River Rch & RM= Walnut79,Reach-1,10084
     379     504     605     362     723    1443    1033
River Rch & RM= Walnut79,Reach-1,7395
     472     637     772     467     932    1859    1357
River Rch & RM= Walnut79,Reach-1,5446
     386     504     596     351     700    1396     965
Boundary for River Rch & Prof#=Walnut79,Reach-1,1
Up Type=0
Dn Type=3
Dn Slope=0.01
Boundary for River Rch & Prof#=Walnut79,Reach-1,2
Up Type=0
Dn Type=3
Dn Slope=0.01
Boundary for River Rch & Prof#=Walnut79,Reach-1,3
Up Type=0
Dn Type=3
Dn Slope=0.01
Boundary for River Rch & Prof#=Walnut79,Reach-1,4
Up Type=0
Dn Type=3
Dn Slope=0.01
Boundary for River Rch & Prof#=Walnut79,Reach-1,5
Up Type=0
Dn Type=3
Dn Slope=0.01
Boundary for River Rch & Prof#=Walnut79,Reach-1,6
Up Type=0
Dn Type=3
Dn Slope=0.01
Boundary for River Rch & Prof#=Walnut79,Reach-1,7
Up Type=0
Dn Type=3
Dn Slope=0.01

--- Walnut79.g01 (geometry) ---

Geom Title=Existing Conditions
Program Version=4.10

River Reach=Walnut79        ,Reach-1
Reach XY= 30
      2737037.88      6741463.89      2737026.23      6739727.01
      2737172.59      6739618.81      2737336.52      6739650.57
      2737331.12      6739508.17      2737476.79      6739395.95
        2737426.        6739161.       2737139.4      6738924.73
      2737172.93      6738812.43      2736996.38      6738630.21
      2736422.69      6738652.93      2736122.85      6738368.51
      2735928.54      6738606.04      2735577.45      6738564.49
      2735182.48      6738953.31       2734776.1      6739103.68
      2734369.88      6738912.82       2734177.5      6738957.54
      2733928.55      6738716.22      2733470.14      6738563.07
      2733031.86      6738508.93      2732815.32      6738361.75
      2732627.58      6738407.33       2732434.1      6738164.29
      2732526.32      6737685.89       2732327.1      6737300.45
      2732373.77      6737016.93      2731922.84      6736069.34
      2730924.33      6735614.31        2730826.        6735661.

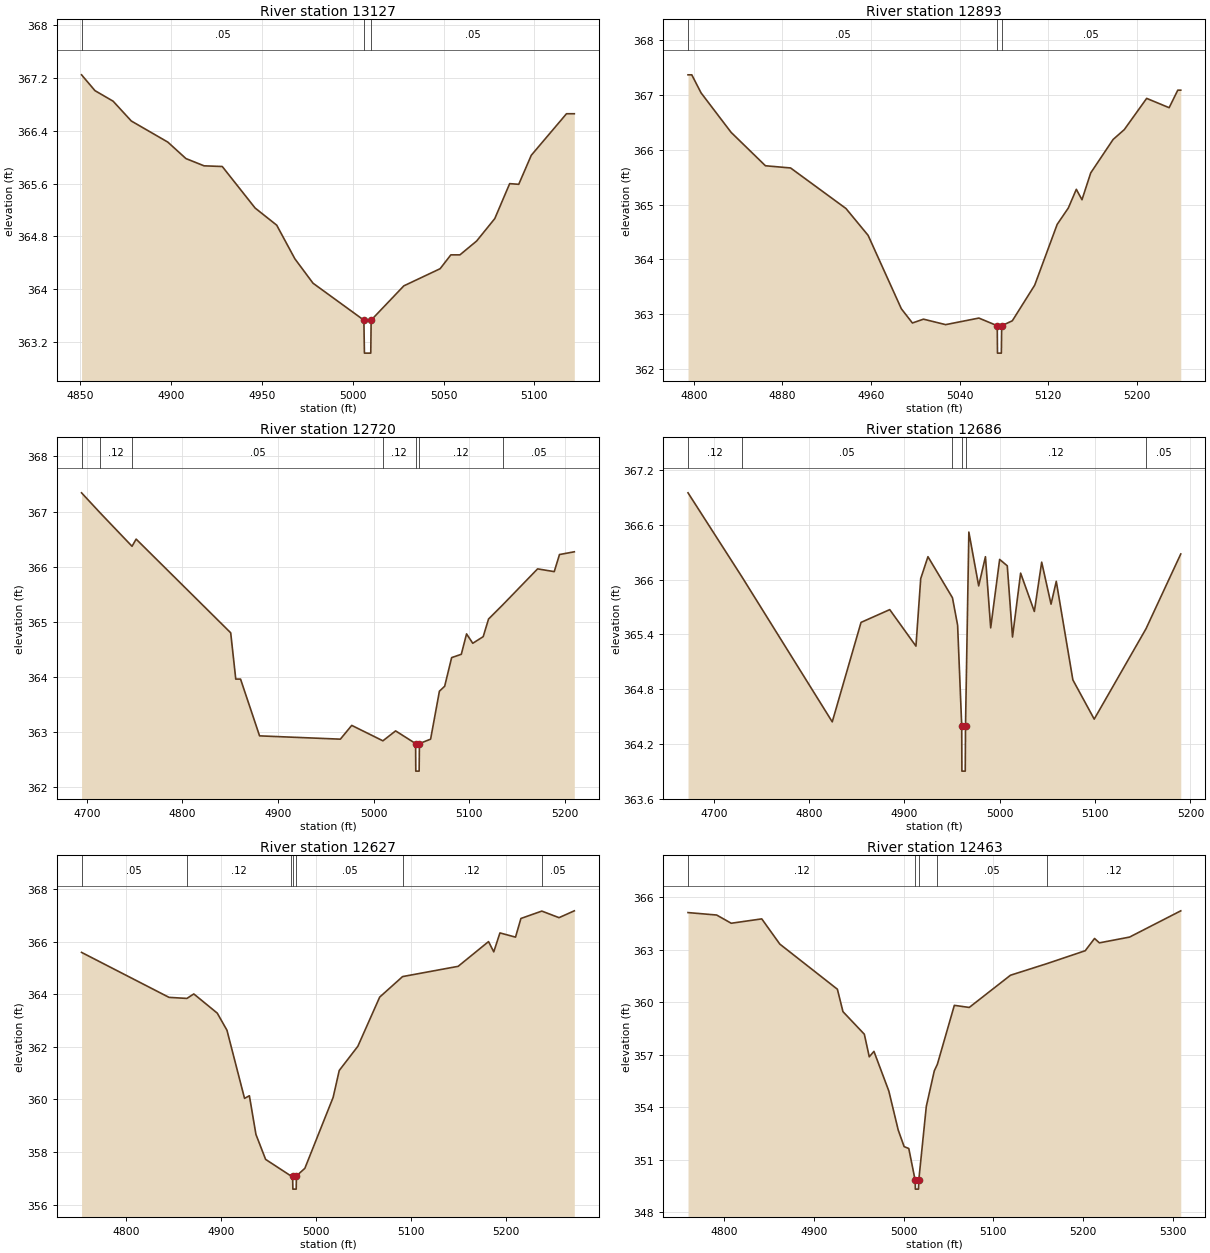
Type RM Length L Ch R = 1 ,13127   ,234,234,234
BEGIN DESCRIPTION:
Walnut79 29.0
END DESCRIPTION:
XS GIS Cut Line= 3
      2737183.43       6741429.1      2736979.28      6741422.69
      2736912.43       6741429.1
#Sta/Elev= 27
  4850.6  367.25    4858  367.01    4868  366.85    4878  366.55  4898.1  366.23
  4908.1  365.98  4918.1  365.87  4928.1  365.86  4946.2  365.23  4958.1  364.97
  4968.1  364.46  4978.1  364.09  5006.1  363.53  5006.4  363.03  5009.9  363.03
  5010.1  363.53  5028.1  364.05  5048.1  364.31    5054  364.52    5059  364.52
  5068.2  364.73  5078.2  365.07  5086.4   365.6  5091.4  365.59  5098.3  366.03
  5117.7  366.66    5122  366.66
#Mann= 3 ,-1 , 0
  4850.6     .05       0  5006.1     .04       0  5010.1     .05       0
Bank Sta=5006.1,5010.1
XS Rating Curve= 0 ,0
Exp/Cntr=0.3,0.1

Type RM Length L Ch R = 1 ,12893   ,173,173,173
BEGIN DESCRIPTION:
Walnut79 28.0
END DESCRIPTION:
XS GIS Cut Line= 4
      2737277.71      6741222.18      2737206.34       6741211.2
      2737002.17      6741204.79      2736835.57      6741229.51
#Sta/Elev= 30
  4794.7  367.37  4798.1  367.37  4806.5  367.04  4833.6  366.32  4864.6  365.71
  4887.3  365.67  4937.3  364.93  4957.3  364.44  4987.3   363.1  4997.3  362.84
  5007.3  362.91  5027.3  362.81  5057.3  362.93  5073.9  362.79  5074.1  362.29
  5077.6  362.29  5077.9  362.79  5087.5  362.88  5107.7  363.53    5128  364.64
  5138.1  364.94  5145.3  365.28  5150.4  365.09  5158.3  365.58  5178.5  366.19
  5188.6  366.37  5208.8  366.94  5229.1  366.77  5236.9  367.09  5239.6  367.09
#Mann= 3 ,-1 , 0
  4794.7     .05       0  5073.9     .04       0  5077.9     .05       0
Bank Sta=5073.9,5077.9
XS Rating Curve= 0 ,0
Exp/Cntr=0.3,0.1

Type RM Length L Ch R = 1 ,12720   ,34,34,34
BEGIN DESCRIPTION:
Walnut79 27.0
END DESCRIPTION:
XS GIS Cut Line= 4
       2737319.9      6741007.03      2737160.56      6741033.58
      2737051.61      6741040.91       2736829.6      6741143.73
#Sta/Elev= 30
  4694.6  367.34  4714.4  366.97  4747.4  366.37  4751.7   366.5  4850.6   364.8
  4855.9  363.96  4860.9  363.96  4880.8  362.93  4965.3  362.87  4977.2  363.12
  5009.8  362.84  5023.1  363.02    5044  362.79  5044.2  362.29  5047.7  362.29
    5048  362.79  5059.7  362.87  5068.9  363.74  5074.4  363.83  5081.7  364.35
  5091.8  364.41  5097.3  364.78  5103.8  364.61  5114.7  364.73  5120.3  365.05
  5135.3  365.31  5171.6  365.96    5189  365.91  5194.5  366.22    5210  366.27
#Mann= 7 ,-1 , 0
  4694.6     .05       0  4714.4     .12       0  4747.4     .05       0
  5009.8     .12       0    5044     .04       0    5048     .12       0
  5135.3     .05       0
Bank Sta=5044,5048
XS Rating Curve= 0 ,0
Exp/Cntr=0.3,0.1

Type RM Length L Ch R = 1 ,12686   ,59,59,59
BEGIN DESCRIPTION:
Walnut79 26.0
END DESCRIPTION:
XS GIS Cut Line= 4
      2737315.26      6740974.08      2737155.98      6741000.62
      2737047.03      6741007.95       2736823.6      6741111.42
#Sta/Elev= 30
    4673  366.95  4729.5  366.03  4824.3  364.44  4854.5  365.53  4884.6  365.67
  4912.1  365.27  4917.1  366.01  4924.7  366.25  4950.4   365.8  4955.8   365.5
  4960.1   364.4  4960.3   363.9  4963.8   363.9  4964.1   364.4  4967.6  366.52
  4977.9  365.93    4985  366.25  4990.5  365.47  4999.9  366.22  5007.9  366.15
  5013.4  365.37  5021.9  366.07  5036.3  365.65    5044  366.19  5053.8  365.73
  5059.3  365.98  5076.7   364.9  5099.1  364.47  5153.4  365.46  5189.9  366.28
#Mann= 6 ,-1 , 0
    4673     .12       0  4729.5     .05       0  4950.4     .12       0
  4960.1     .07       0  4964.1     .12       0  5153.4     .05       0
Bank Sta=4960.1,4964.1
XS Rating Curve= 0 ,0
Exp/Cntr=0.3,0.1

Type RM Length L Ch R = 1 ,12627   ,164,164,164
BEGIN DESCRIPTION:
Walnut79 25.0
END DESCRIPTION:
XS GIS Cut Line= 4
      2737246.64      6740944.77      2737019.57      6740985.98
      2736978.37      6740978.65      2736754.99       6741082.1
#Sta/Elev= 30
  4752.9  365.59    4845  363.88  4863.8  363.84  4871.1  364.01  4895.8  363.28
    4906  362.63  4924.5  360.04  4929.6  360.14  4936.5  358.67  4946.7  357.72
    4973   357.1  4975.1  357.09  4975.4  356.59  4978.9  356.59  4979.1  357.09
    4988  357.38  5017.8  360.08  5024.2   361.1  5043.8  362.02  5066.8  363.89
  5090.9  364.67  5149.4  365.06  5181.4     366  5186.9  365.61  5193.4  366.33
  5209.8  366.17  5215.5  366.88  5237.5  367.16  5255.6  366.91  5271.7  367.17
#Mann= 7 ,-1 , 0
  4752.9     .05       0  4863.8     .12       0    4973     .05       0
  4975.1     .04       0  4979.1     .05       0  5090.9     .12       0
  5237.5     .05       0
Bank Sta=4975.1,4979.1
XS Rating Curve= 0 ,0
Exp/Cntr=0.3,0.1

Type RM Length L Ch R = 1 ,12463   ,145,145,145
BEGIN DESCRIPTION:
Walnut79 24.5
END DESCRIPTION:
XS GIS Cut Line= 3
      2737237.83      6740840.24      2737042.29      6740823.32
       2736703.8       6740921.1
#Sta/Elev= 30
  4760.1  365.11    4792  364.97  4808.2   364.5  4842.2  364.75  4862.3  363.31
  4926.4  360.73  4932.6  359.45  4956.4  358.16  4961.9  356.87  4967.1  357.18
  4983.7  354.91  4994.1  352.69  5000.7  351.74  5005.9  351.63    5013  349.81
  5013.2  349.31  5016.7  349.31    5017  349.81  5025.4  354.04  5034.3  356.07
  5037.7  356.44  5056.6  359.81  5073.2  359.69  5119.1  361.53  5159.5  362.19
  5202.3  362.93  5212.7  363.63  5218.1  363.38  5251.7  363.71  5308.7  365.21
#Mann= 5 ,-1 , 0
  4760.1     .12       0    5013     .07       0    5017     .12       0
  5037.7     .05       0  5159.5     .12       0
Bank Sta=5013,5017
XS Rating Curve= 0 ,0
Exp/Cntr=0.3,0.1

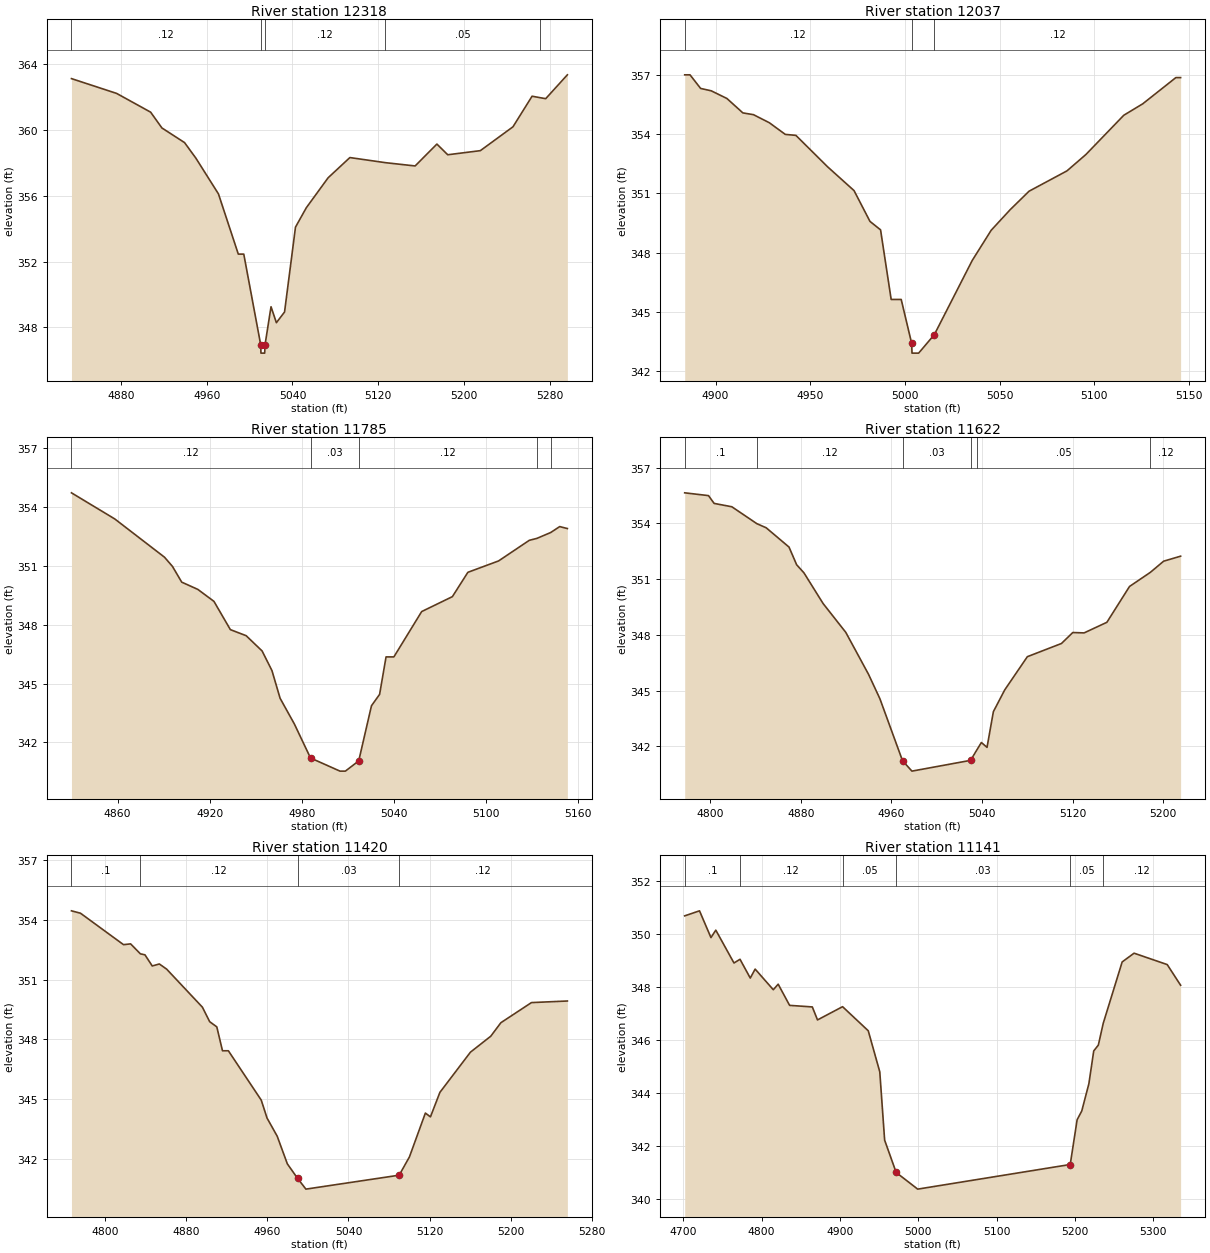
Type RM Length L Ch R = 1 ,12318   ,281,281,281
BEGIN DESCRIPTION:
Walnut79 24.0
END DESCRIPTION:
XS GIS Cut Line= 3
      2737175.98      6740760.99        2737026.        6740711.
      2736726.03      6740760.99
#Sta/Elev= 30
    4834  363.13  4876.1  362.23  4907.8  361.09  4918.3  360.13  4939.4  359.24
  4949.9   358.3    4971  356.12  4989.5  352.46  4994.6  352.46  5010.4  346.94
  5010.6  346.44  5014.1  346.44  5014.4  346.94    5020  349.26    5025  348.29
  5032.6  348.94  5042.8   354.1  5052.9  355.28  5073.2   357.1  5093.5  358.33
  5126.5  358.02  5154.3  357.82  5174.6  359.15  5184.7   358.5  5215.1  358.75
  5245.5   360.2  5263.3  362.06  5270.8  361.97    5276  361.91  5296.2  363.36
#Mann= 5 ,-1 , 0
    4834     .12       0  5010.4     .07       0  5014.4     .12       0
  5126.5     .05       0  5270.8     .12       0
Bank Sta=5010.4,5014.4
XS Rating Curve= 0 ,0
Exp/Cntr=0.3,0.1

Type RM Length L Ch R = 1 ,12037   ,252,252,252
BEGIN DESCRIPTION:
Walnut79 23.0
END DESCRIPTION:
XS GIS Cut Line= 3
      2737125.98      6740510.99        2737026.        6740461.
      2736875.98        6740461.
#Sta/Elev= 30
  4883.7  357.01  4886.5  357.01  4892.1  356.32  4897.7   356.2    4906  355.81
  4914.4  355.08    4920  354.99  4928.4  354.58  4936.8  353.99  4942.4  353.94
  4959.1  352.35  4973.1  351.14  4981.5  349.58  4987.1  349.15  4992.7  345.62
    4998  345.62  5003.5   343.4  5003.7   342.9  5007.2   342.9  5015.5  343.84
  5035.5   347.6  5045.5  349.13  5055.5  350.17  5065.5  351.11  5085.5  352.14
  5095.5  352.97  5115.5  354.96  5125.5  355.54    5143  356.87  5145.5  356.87
#Mann= 3 ,-1 , 0
  4883.7     .12       0  5003.5     .04       0  5015.5     .12       0
Bank Sta=5003.5,5015.5
XS Rating Curve= 0 ,0
Exp/Cntr=0.3,0.1

Type RM Length L Ch R = 1 ,11785   ,163,163,163
BEGIN DESCRIPTION:
Walnut79 22.0
END DESCRIPTION:
XS GIS Cut Line= 3
      2737164.53      6740285.51      2736967.07      6740223.45
      2736851.29      6740215.98
#Sta/Elev= 30
    4830  354.72  4858.2  353.39  4890.6  351.44  4895.8  350.97  4901.8  350.17
  4912.3   349.8  4922.8  349.19  4933.5  347.75  4943.8  347.44  4954.2  346.66
  4960.6  345.66  4965.9  344.25  4975.2  342.94  4985.7  341.21  5004.9  340.54
  5008.4  340.54  5017.1  341.06  5025.4  343.87  5030.7  344.45  5034.9  346.36
    5040  346.36  5058.1  348.67  5078.1  349.43  5088.2  350.67  5108.2  351.25
  5128.2   352.3  5133.2   352.4  5142.2   352.7    5148     353    5153   352.9
#Mann= 5 ,-1 , 0
    4830     .12       0  4985.7     .03       0  5017.1     .12       0
  5133.2     .05       0  5142.2     .12       0
Bank Sta=4985.7,5017.1
XS Rating Curve= 0 ,0
Exp/Cntr=0.3,0.1

Type RM Length L Ch R = 1 ,11622   ,202,202,202
BEGIN DESCRIPTION:
Walnut79 21.5
END DESCRIPTION:
XS GIS Cut Line= 3
      2737247.28      6740099.34       2737147.6      6740086.17
      2736810.98      6740065.49
#Sta/Elev= 30
  4777.6  355.65  4798.6   355.5  4803.6  355.08  4819.2   354.9  4841.3  353.99
  4849.5  353.77  4869.7  352.73  4876.4  351.78  4882.9  351.34  4899.8  349.69
  4919.8  348.14  4939.9  345.88  4949.9  344.57  4969.9  341.23  4978.2  340.67
    5030  341.25  5035.2  341.78  5039.5  342.21  5044.5  341.95  5050.1  343.87
  5060.1  345.04  5080.1  346.83  5110.2  347.54  5120.2  348.13  5130.2  348.11
  5150.3  348.68  5170.3  350.61  5188.7  351.37  5200.4  351.97  5215.4  352.24
#Mann= 6 ,-1 , 0
  4777.6      .1       0  4841.3     .12       0  4969.9     .03       0
    5030     .12       0  5035.2     .05       0  5188.7     .12       0
Bank Sta=4969.9,5030
XS Rating Curve= 0 ,0
Exp/Cntr=0.3,0.1

Type RM Length L Ch R = 1 ,11420   ,279,279,279
BEGIN DESCRIPTION:
Walnut79 21.0
END DESCRIPTION:
XS GIS Cut Line= 3
      2737266.08      6740003.44        2737157.      6739898.13
      2736820.65      6739877.46
#Sta/Elev= 30
  4767.1  354.46    4776  354.34  4818.4  352.76  4825.4   352.8    4835   352.3
  4839.5  352.25  4846.7  351.69  4853.7  351.79  4860.9  351.53  4896.1  349.62
  4903.3  348.89  4910.3  348.63  4915.9  347.43  4921.7  347.43  4954.1  344.95
  4959.8  344.05  4969.8  343.14  4979.8  341.75  4989.9  341.02  4998.1  340.48
    5090  341.18  5100.1   342.1  5115.8   344.3  5120.8  344.11  5130.1  345.34
  5160.2  347.36  5180.2  348.16  5190.2  348.84  5220.3  349.85  5255.7  349.93
#Mann= 4 ,-1 , 0
  4767.1      .1       0    4835     .12       0  4989.9     .03       0
    5090     .12       0
Bank Sta=4989.9,5090
XS Rating Curve= 0 ,0
Exp/Cntr=0.3,0.1

Type RM Length L Ch R = 1 ,11141   ,273,273,273
BEGIN DESCRIPTION:
Walnut79 20.8
END DESCRIPTION:
XS GIS Cut Line= 3
      2737281.13      6739922.59      2737072.38      6739636.74
      2736837.35      6739486.32
#Sta/Elev= 30
  4701.9  350.69  4720.8  350.88  4735.4  349.87  4741.6  350.15  4764.8  348.91
  4772.5  349.05  4785.6  348.34  4791.8  348.68    4815   347.9  4821.2  348.11
  4835.8  347.31  4864.8  347.25  4871.4  346.76  4903.4  347.26  4936.2  346.35
  4950.9   344.8  4957.1  342.22  4971.8     341  4999.3  340.37    5194   341.3
  5202.8  342.99  5208.7  343.32  5217.8  344.35    5224  345.59  5229.9  345.81
  5236.1  346.63  5260.3  348.95  5275.5  349.28  5317.8  348.85  5334.9  348.07
#Mann= 6 ,-1 , 0
  4701.9      .1       0  4772.5     .12       0  4903.4     .05       0
  4971.8     .03       0    5194     .05       0  5236.1     .12       0
Bank Sta=4971.8,5194
XS Rating Curve= 0 ,0
Exp/Cntr=0.3,0.1

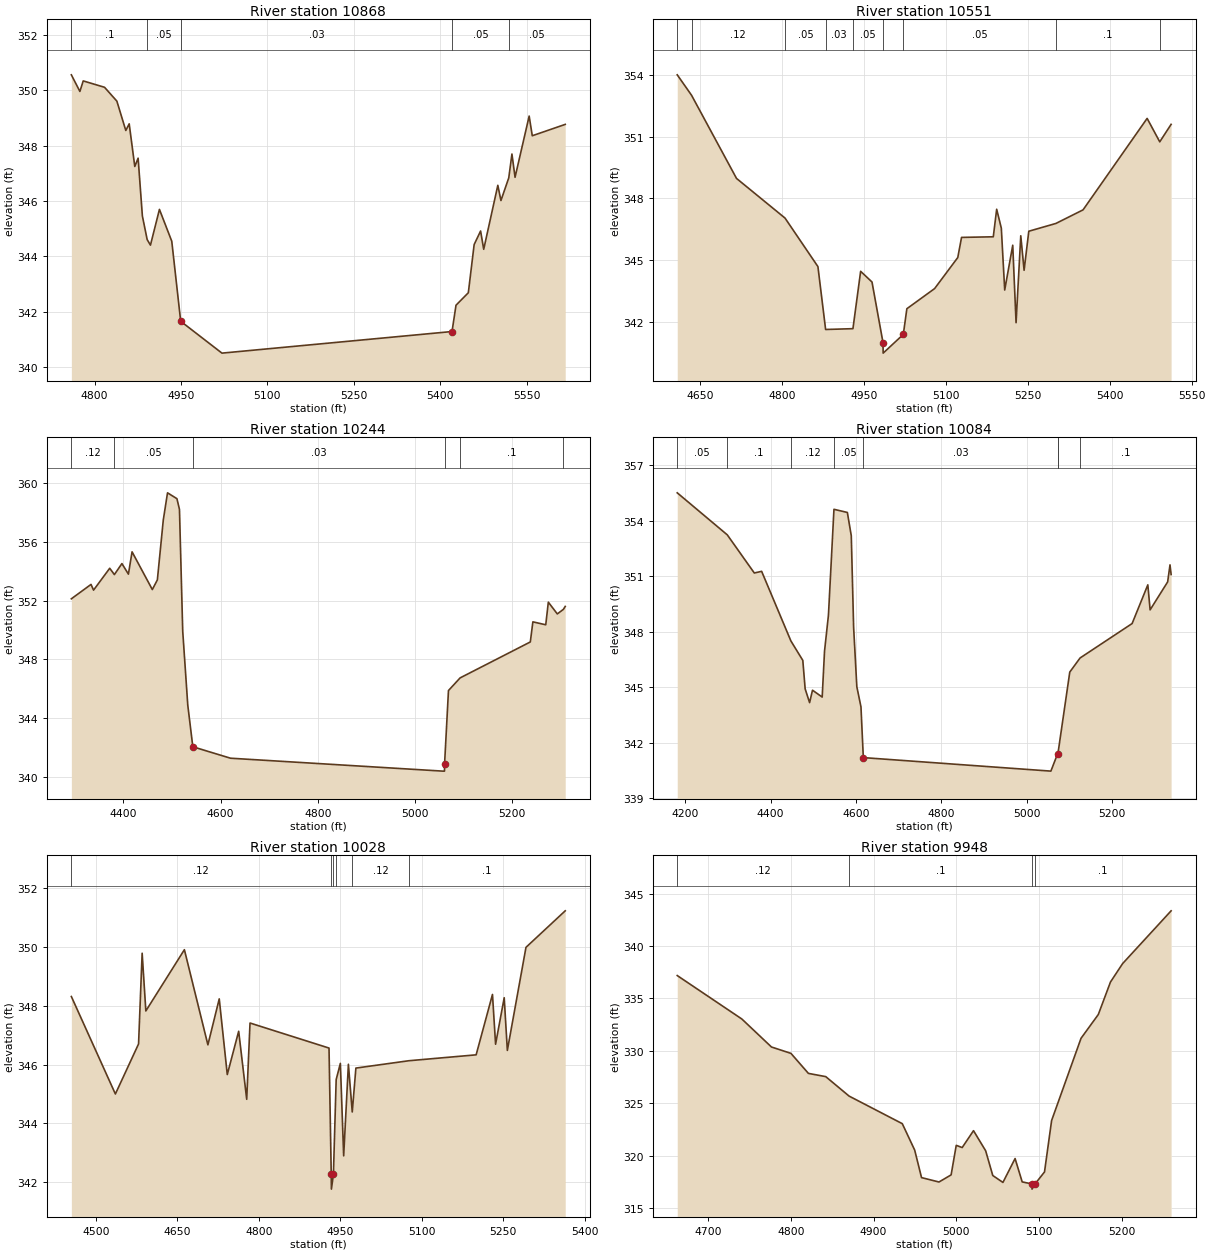
Type RM Length L Ch R = 1 ,10868   ,317,317,317
BEGIN DESCRIPTION:
Walnut79 20.6
END DESCRIPTION:
XS GIS Cut Line= 4
      2737459.76      6739856.76      2737282.99      6739561.52
      2737036.65      6739302.02      2736891.87      6739358.43
#Sta/Elev= 30
  4759.8  350.56  4774.6  349.96  4780.4  350.34  4817.4  350.11  4838.8  349.61
  4854.3  348.55  4860.2  348.79  4869.9  347.25  4875.7  347.55  4883.1  345.46
  4891.4  344.61  4897.1  344.41  4912.7   345.7  4934.1  344.55  4949.6  341.66
  5021.2  340.51  5420.6  341.29  5427.5  342.24  5448.9  342.69    5459  344.43
  5470.2  344.92  5475.6  344.26  5500.1  346.57  5505.5  346.02  5519.1  346.84
  5524.6   347.7    5530  346.86  5554.5  349.07  5559.9  348.36  5617.1  348.77
#Mann= 5 ,-1 , 0
  4759.8      .1       0  4891.4     .05       0  4949.6     .03       0
  5420.6     .05       0  5519.1     .05       0
Bank Sta=4949.6,5420.6
XS Rating Curve= 0 ,0
Exp/Cntr=0.3,0.1

Type RM Length L Ch R = 1 ,10551   ,307,307,307
BEGIN DESCRIPTION:
Walnut79 20.4
END DESCRIPTION:
XS GIS Cut Line= 5
      2737694.81      6739794.69      2737401.46      6739439.29
      2737258.55      6739241.84      2737160.76       6739226.8
      2737063.46      6739251.94
#Sta/Elev= 30
  4608.4  354.01  4634.5  353.02  4716.9  348.97  4805.7  347.04  4865.9  344.68
    4880  341.62    4930  341.66  4944.1  344.45  4964.9  343.93  4985.1  340.97
  4985.3  340.47  5022.2  341.38  5028.7  342.63  5079.5  343.61  5121.9  345.12
  5128.8   346.1  5186.9  346.13  5193.1  347.47  5201.6  346.55  5207.8  343.54
  5222.5  345.72  5228.6  341.95  5237.2  346.18  5243.3   344.5  5251.9   346.4
  5301.6  346.78  5351.2  347.44  5468.5  351.89  5491.6  350.75  5512.4   351.6
#Mann= 9 ,-1 , 0
  4608.4     .05       0  4634.5     .12       0  4805.7     .05       0
    4880     .03       0    4930     .05       0  4985.1     .03       0
  5022.2     .05       0  5301.6      .1       0  5491.6     .12       0
Bank Sta=4985.1,5022.2
XS Rating Curve= 0 ,0
Exp/Cntr=0.3,0.1

Type RM Length L Ch R = 1 ,10244   ,160,160,160
BEGIN DESCRIPTION:
Walnut79 20.2
END DESCRIPTION:
XS GIS Cut Line= 5
      2738055.89      6739418.61      2737431.55      6739234.32
      2737251.03      6739232.44      2737151.36      6739221.16
      2737070.51      6739247.69
#Sta/Elev= 30
  4292.8  352.12  4333.3   353.1  4338.5  352.71  4371.8   354.2  4381.4  353.77
  4396.9  354.52  4410.3   353.8  4417.8  355.32  4459.5  352.75  4469.9  353.41
  4482.1  357.49  4490.8  359.34  4510.2  358.94  4515.4  358.21  4522.1  349.92
  4532.5  344.88  4542.9  342.04  4620.5  341.26  5057.6  340.38  5061.1  340.38
  5061.3  340.88  5069.3  345.87  5093.2  346.73  5237.8  349.18  5243.1  350.55
  5269.6  350.35  5274.9  351.89  5293.4  351.09  5305.9   351.4  5309.7   351.6
#Mann= 6 ,-1 , 0
  4292.8     .12       0  4381.4     .05       0  4542.9     .03       0
  5061.3     .05       0  5093.2      .1       0  5305.9     .12       0
Bank Sta=4542.9,5061.3
XS Rating Curve= 0 ,0
Exp/Cntr=0.3,0.1

Type RM Length L Ch R = 1 ,10084   ,56,56,56
BEGIN DESCRIPTION:
Walnut79 20.0
END DESCRIPTION:
XS GIS Cut Line= 6
      2738116.15      6738759.44      2737611.13      6738999.33
      2737339.41       6739130.9      2737252.91      6739224.92
      2737143.84      6739213.64      2737089.82      6739237.59
#Sta/Elev= 30
  4181.3   355.5  4298.6  353.23  4361.9  351.17  4379.1  351.26  4447.7   347.5
  4475.6  346.45  4481.1  344.91  4491.5  344.17  4498.3  344.84    4521  344.47
  4526.5  346.95  4535.7   348.9  4548.6  354.61    4580  354.44  4589.2  353.18
  4594.7  348.23  4602.2  345.03  4611.9  343.94  4617.4   341.2    5057  340.47
    5073  341.42  5074.2  341.52  5101.3  345.82  5125.4  346.58  5247.4  348.44
  5284.2  350.53  5289.6  349.18  5330.7  350.69  5336.2  351.61  5338.8  351.09
#Mann= 8 ,-1 , 0
  4181.3     .05       0  4298.6      .1       0  4447.7     .12       0
  4548.6     .05       0  4617.4     .03       0    5073     .12       0
  5074.2     .05       0  5125.4      .1       0
Bank Sta=4617.4,5073
XS Rating Curve= 0 ,0
Exp/Cntr=0.3,0.1

Type RM Length L Ch R = 1 ,10028   ,80,80,80
BEGIN DESCRIPTION:
Walnut79 19.2
END DESCRIPTION:
XS GIS Cut Line= 6
      2737768.98      6738739.88      2737591.54      6738895.96
      2737294.28      6739104.57       2737243.5      6739211.76
      2737149.48      6739187.31      2737074.87       6739239.7
#Sta/Elev= 30
  4454.6  348.31  4535.7     345  4578.4   346.7    4585  349.78  4591.8  347.82
  4662.8   349.9  4706.1  346.67    4727  348.23  4741.8  345.66  4762.8  347.13
  4777.6  344.82  4783.7  347.41  4929.2  346.56  4933.3  342.27  4933.6  341.77
  4937.3  342.27  4942.4  345.49  4950.1  346.04  4956.2   342.9  4964.9  346.01
    4972  344.39  4978.7  345.88  5076.4  346.13  5200.2  346.33  5230.3  348.38
    5236  346.69  5251.9  348.27  5257.7  346.48    5292  349.98  5364.3  351.22
#Mann= 6 ,-1 , 0
  4454.6     .12       0  4933.3     .07       0  4937.3     .12       0
  4942.4      .1       0    4972     .12       0  5076.4      .1       0
Bank Sta=4933.3,4937.3
XS Rating Curve= 0 ,0
Exp/Cntr=0.3,0.1

Type RM Length L Ch R = 1 ,9948    ,305,305,305
BEGIN DESCRIPTION:
Walnut79 19.0
END DESCRIPTION:
XS GIS Cut Line= 3
      2737559.38      6738824.41      2737324.36       6738986.1
      2737070.72      6739168.35
#Sta/Elev= 30
  4662.4  337.19  4740.6  333.04  4776.4  330.37    4800  329.76  4821.1  327.85
  4842.1  327.54  4870.4  325.68  4934.7  323.05  4949.7  320.53    4958   317.9
  4979.1  317.48  4993.8  318.16    5000  320.98  5007.2  320.77  5020.9  322.38
  5035.6  320.46  5044.2   318.1  5056.5  317.44  5071.2  319.72  5079.8  317.49
  5091.4   317.3  5091.7   316.8  5095.4   317.3  5106.8  318.44  5115.4  323.35
    5151   331.2  5171.9  333.47  5186.6  336.57  5201.3  338.33    5260  343.37
#Mann= 4 ,-1 , 0
  4662.4     .12       0  4870.4      .1       0  5091.4     .07       0
  5095.4      .1       0
Bank Sta=5091.4,5095.4
XS Rating Curve= 0 ,0
Exp/Cntr=0.3,0.1

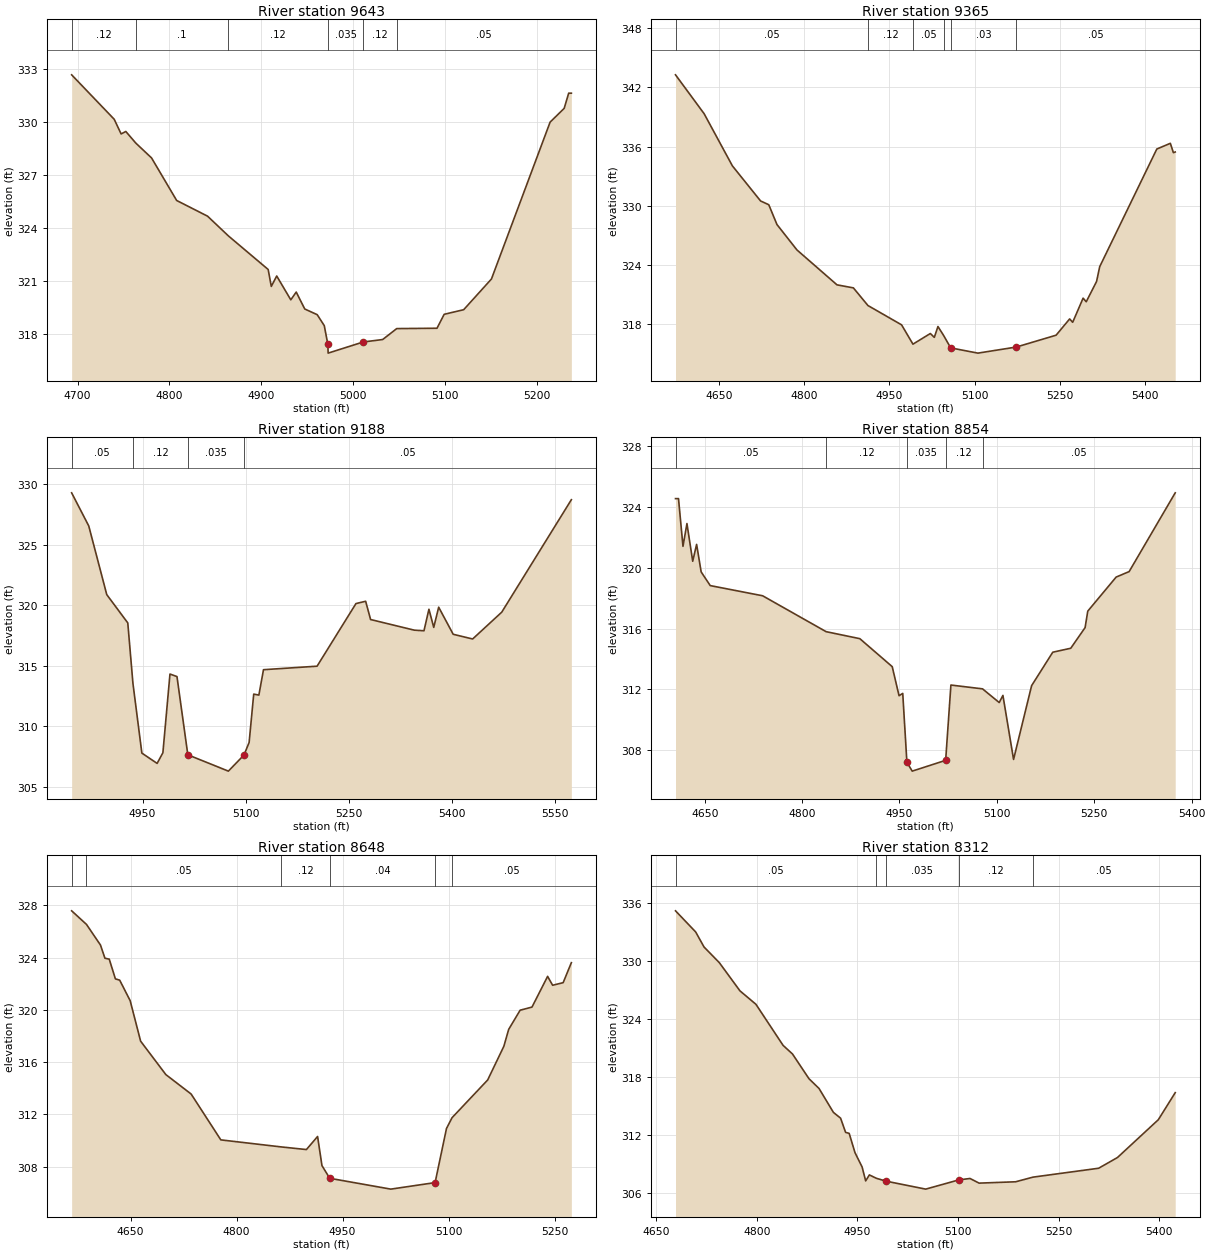
Type RM Length L Ch R = 1 ,9643    ,278,278,278
BEGIN DESCRIPTION:
Walnut79 18.0
END DESCRIPTION:
XS GIS Cut Line= 3
      2737461.67      6738726.59      2737251.03      6738762.32
      2736972.68      6738939.11
#Sta/Elev= 30
  4693.6  332.67  4739.9  330.15  4747.4  329.32  4752.5  329.46  4763.4   328.8
  4780.5  327.96  4807.8  325.55  4841.4  324.66  4864.1  323.54  4907.3  321.64
  4910.7  320.68  4916.6  321.27  4931.9  319.92  4937.8  320.36  4947.1   319.4
  4960.6  319.08  4968.3  318.46  4972.2   317.4  4972.5   316.9  5010.6  317.53
  5031.8  317.67  5047.1  318.29  5090.9  318.31  5098.7   319.1  5119.9  319.36
  5150.1   321.1  5213.9  329.99  5229.2  330.77  5234.1  331.63    5237  331.63
#Mann= 6 ,-1 , 0
  4693.6     .12       0  4763.4      .1       0  4864.1     .12       0
  4972.2    .035       0  5010.6     .12       0  5047.1     .05       0
Bank Sta=4972.2,5010.6
XS Rating Curve= 0 ,0
Exp/Cntr=0.3,0.1

Type RM Length L Ch R = 1 ,9365    ,177,177,177
BEGIN DESCRIPTION:
Walnut79 17.0
END DESCRIPTION:
XS GIS Cut Line= 3
       2737411.9      6738292.24       2736897.5      6738704.03
       2736812.2      6738907.23
#Sta/Elev= 30
  4573.7  343.28  4624.1  339.33  4673.8  334.04  4723.4  330.48  4737.8   330.1
  4752.2  328.09  4787.4  325.51  4857.8  321.97  4886.7  321.66  4912.3  319.87
  4971.5  317.91  4991.5  315.95  5022.1  317.03  5029.1  316.64  5035.5  317.74
  5045.7  316.81  5057.9  315.57  5105.8  315.04  5173.6  315.66  5243.4  316.86
  5267.2  318.51  5272.6  318.17  5290.9  320.62  5296.4  320.25  5314.6  322.31
  5320.1  323.81  5420.6  335.75  5444.4  336.33  5449.8  335.38    5453  335.45
#Mann= 6 ,-1 , 0
  4573.7     .05       0  4912.3     .12       0  4991.5     .05       0
  5045.7     .12       0  5057.9     .03       0  5173.6     .05       0
Bank Sta=5057.9,5173.6
XS Rating Curve= 0 ,0
Exp/Cntr=0.3,0.1

Type RM Length L Ch R = 1 ,9188    ,334,334,334
BEGIN DESCRIPTION:
Walnut79 16.0
END DESCRIPTION:
XS GIS Cut Line= 4
      2736891.27      6738388.62      2736835.44      6738653.26
       2736733.9       6738745.4      2736512.45      6738976.01
#Sta/Elev= 30
  4846.8  329.31  4871.7  326.57  4897.9  320.89  4928.5  318.55    4936  313.55
    4949  307.78  4971.2  306.93  4979.6  307.81  4989.9  314.32  5000.1  314.11
  5015.9  307.64  5074.9  306.29  5097.6  307.62  5105.1  308.66  5111.8  312.66
  5119.3  312.58    5126  314.68    5204  314.97  5260.6  320.15  5274.7  320.34
  5281.9  318.83  5345.5  317.95  5359.6   317.9  5366.8  319.68  5373.8  318.18
    5381  319.85  5402.1  317.61  5430.4  317.22  5472.8  319.44  5574.1  328.74
#Mann= 4 ,-1 , 0
  4846.8     .05       0    4936     .12       0  5015.9    .035       0
  5097.6     .05       0
Bank Sta=5015.9,5097.6
XS Rating Curve= 0 ,0
Exp/Cntr=0.3,0.1

Type RM Length L Ch R = 1 ,8854    ,206,206,206
BEGIN DESCRIPTION:
Walnut79 15.0
END DESCRIPTION:
XS GIS Cut Line= 4
      2736838.63      6738378.21      2736575.11      6738557.78
      2736427.17      6738839.15      2736421.96      6738971.97
#Sta/Elev= 30
    4605  324.55  4609.6  324.55  4616.5  321.41  4622.6  322.91  4631.5  320.43
  4637.5  321.54  4644.5  319.73  4658.5  318.83  4739.2  318.16    4837   315.8
  4888.9  315.34  4938.8   313.5  4949.3  311.59    4955  311.74  4961.4  307.21
  4969.6  306.63  5021.1  307.34  5029.2  312.29  5077.9  312.04  5103.6  311.14
  5109.3  311.61  5125.7   307.4  5153.5  312.25  5186.1  314.45  5213.8  314.71
  5235.9  316.07    5240  317.15  5283.7  319.39  5303.7  319.75  5374.7  324.93
#Mann= 5 ,-1 , 0
    4605     .05       0    4837     .12       0  4961.4    .035       0
  5021.1     .12       0  5077.9     .05       0
Bank Sta=4961.4,5021.1
XS Rating Curve= 0 ,0
Exp/Cntr=0.3,0.1

Type RM Length L Ch R = 1 ,8648    ,336,336,336
BEGIN DESCRIPTION:
Walnut79 14.0
END DESCRIPTION:
XS GIS Cut Line= 3
      2736578.18      6738237.63      2736461.02      6738404.26
      2736250.56      6738861.55
#Sta/Elev= 30
  4566.7  327.58  4587.7  326.54  4607.5  324.96  4613.8  323.95  4619.9  323.88
  4628.6  322.37  4634.7  322.27  4649.5   320.7  4664.3   317.6    4700  315.04
  4735.8  313.55  4777.8  310.04  4863.5   309.5  4898.9   309.3  4914.7   310.3
  4920.9  308.07  4931.9   307.1  5018.3  306.27    5081  306.77  5097.1  310.91
    5105  311.74  5155.4  314.63  5178.3  317.21  5185.1   318.5  5201.3  319.97
  5218.1  320.21  5240.2  322.56  5247.3  321.88  5262.2  322.08  5273.8  323.61
#Mann= 6 ,-1 , 0
  4566.7     .12       0  4587.7     .05       0  4863.5     .12       0
  4931.9     .04       0    5081     .12       0    5105     .05       0
Bank Sta=4931.9,5081
XS Rating Curve= 0 ,0
Exp/Cntr=0.3,0.1

Type RM Length L Ch R = 1 ,8312    ,301,301,301
BEGIN DESCRIPTION:
Walnut79 13.5
END DESCRIPTION:
XS GIS Cut Line= 3
      2736263.09      6738081.38      2736059.98      6738607.38
      2736091.02      6738785.84
#Sta/Elev= 30
  4678.8  335.15  4708.8  332.97  4721.3  331.41  4744.1  329.79  4774.9  326.87
  4798.7  325.48  4839.2  321.23  4853.2  320.34  4877.8  317.78  4892.8  316.77
  4914.2   314.3  4924.9   313.7  4932.4  312.23  4937.7  312.13  4946.4  310.13
    4957  308.65  4962.3  307.21  4967.8  307.83  4978.3  307.48  4992.3  307.19
  5051.8  306.36  5101.4  307.32  5117.9  307.46  5131.4  306.98  5185.9  307.12
  5211.7   307.6  5309.6  308.52  5337.7  309.63  5398.6  313.54  5423.8  316.34
#Mann= 5 ,-1 , 0
  4678.8     .05       0  4978.3     .12       0  4992.3    .035       0
  5101.4     .12       0  5211.7     .05       0
Bank Sta=4992.3,5101.4
XS Rating Curve= 0 ,0
Exp/Cntr=0.3,0.1

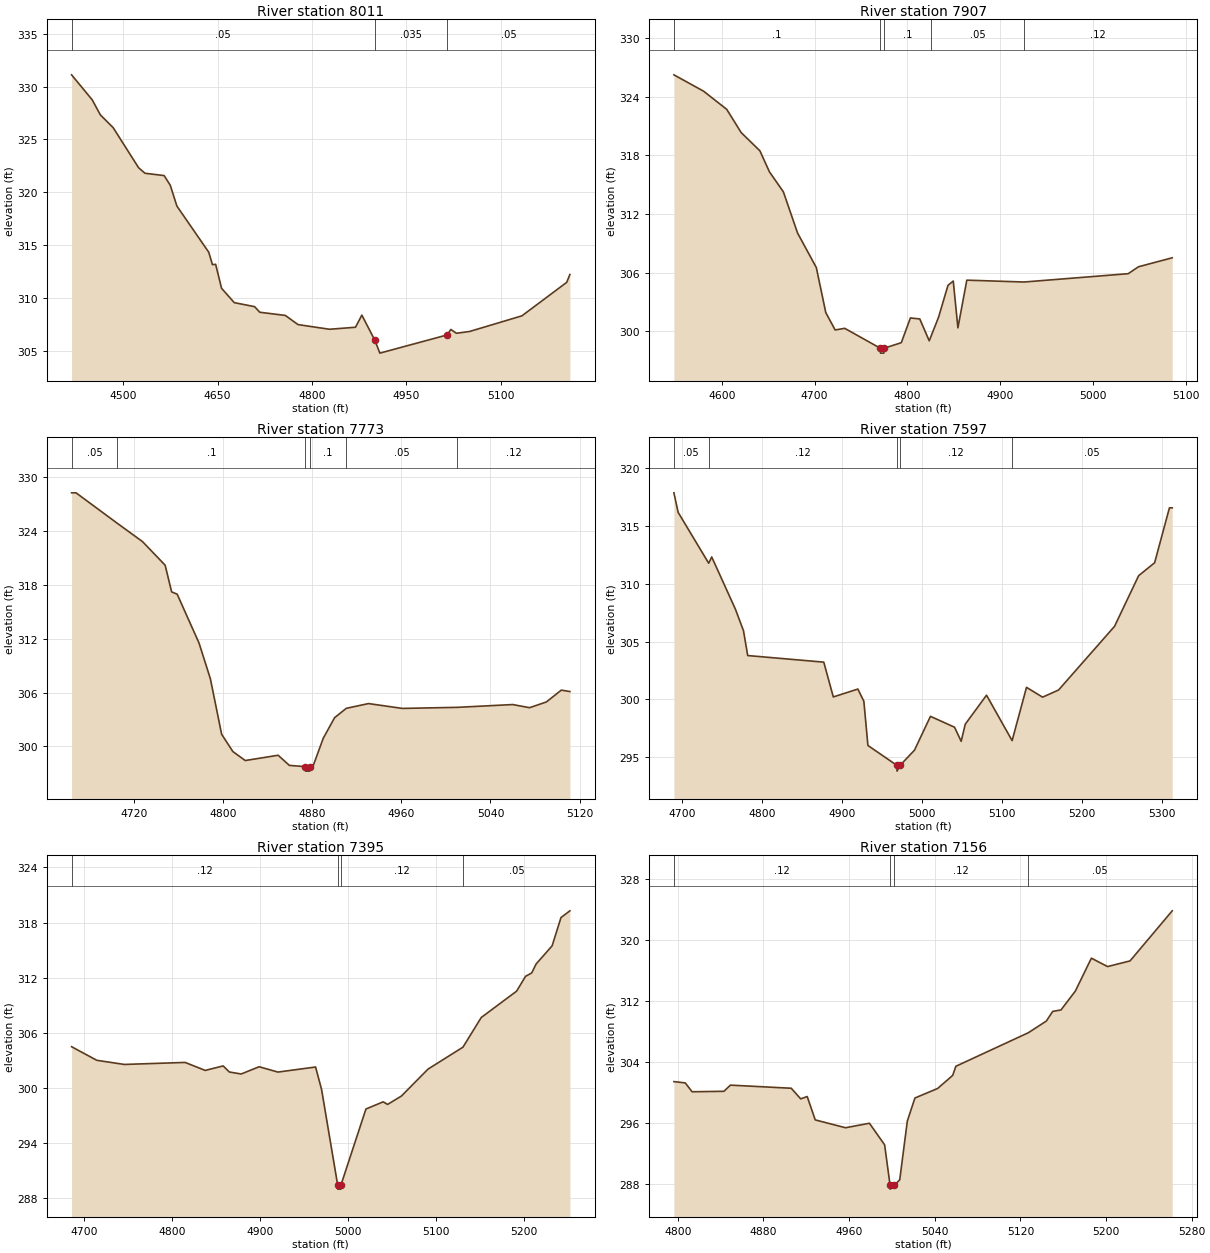
Type RM Length L Ch R = 1 ,8011    ,104,104,104
BEGIN DESCRIPTION:
Walnut79 13.0
END DESCRIPTION:
XS GIS Cut Line= 4
      2736036.54      6738005.83        2735948.       6738557.9
      2736018.72      6738659.15      2736041.08       6738765.6
#Sta/Elev= 30
  4418.2  331.12    4451  328.75  4463.9  327.33  4484.2  326.12  4524.7  322.32
  4534.8   321.8  4565.2  321.58  4574.9  320.67  4585.5  318.69  4636.1  314.32
  4641.9  313.15    4647  313.18  4656.4  310.91  4676.6  309.55  4708.9  309.17
  4717.1  308.64  4757.6  308.34  4777.9  307.47  4827.8  307.03  4869.1  307.22
  4879.2  308.37  4899.9  305.98  4907.8  304.77  5014.5  306.49  5020.6  307.01
  5029.4  306.65  5050.3  306.82  5133.4   308.3  5204.5  311.47  5209.6  312.21
#Mann= 3 ,-1 , 0
  4418.2     .05       0  4899.9    .035       0  5014.5     .05       0
Bank Sta=4899.9,5014.5
XS Rating Curve= 0 ,0
Exp/Cntr=0.3,0.1

Type RM Length L Ch R = 1 ,7907    ,134,134,134
BEGIN DESCRIPTION:
Walnut79 12.4
END DESCRIPTION:
XS GIS Cut Line= 3
      2735791.76      6738159.51      2735851.65      6738521.45
      2735890.22      6738687.27
#Sta/Elev= 30
  4548.3  326.25  4580.2  324.58  4605.2  322.72  4620.8  320.34    4641  318.47
  4651.2  316.33  4666.3  314.27  4681.6  310.05  4701.8  306.52    4712  301.91
  4722.1  300.13  4732.4   300.3  4770.8  298.26    4771  297.76  4774.5  297.76
  4774.8  298.26  4793.4  298.83  4803.2  301.36  4813.3  301.26  4823.5  299.02
  4825.8  299.57  4833.6  301.45  4843.7   304.7  4849.4  305.14  4854.4  300.35
    4864  305.23  4925.7  305.04  5037.9  305.89    5049   306.6  5085.4  307.52
#Mann= 5 ,-1 , 0
  4548.3      .1       0  4770.8     .07       0  4774.8      .1       0
  4825.8     .05       0  4925.7     .12       0
Bank Sta=4770.8,4774.8
XS Rating Curve= 0 ,0
Exp/Cntr=0.3,0.1

Type RM Length L Ch R = 1 ,7773    ,176,176,176
BEGIN DESCRIPTION:
Walnut79 12.0
END DESCRIPTION:
XS GIS Cut Line= 3
      2735716.23      6738188.11      2735776.13      6738550.09
      2735820.03      6738617.45
#Sta/Elev= 30
    4664  328.27    4668  328.27  4705.2  324.86  4727.7  322.83    4748   320.2
  4753.8  317.23  4758.8  316.97  4778.4  311.53  4788.6  307.54  4798.7  301.36
  4808.8  299.43  4819.9  298.43  4849.4  299.02  4859.5  297.89  4873.8  297.75
  4874.1  297.25  4877.6  297.25  4877.8  297.75  4880.9  297.86  4889.9  300.91
  4900.1  303.21  4910.6  304.25  4930.5  304.78  4960.9  304.24  5010.3  304.36
    5060  304.67  5075.1  304.32  5090.2  304.96  5103.6  306.28  5111.3  306.12
#Mann= 6 ,-1 , 0
    4664     .05       0  4705.2      .1       0  4873.8     .05       0
  4877.8      .1       0  4910.6     .05       0  5010.3     .12       0
Bank Sta=4873.8,4877.8
XS Rating Curve= 0 ,0
Exp/Cntr=0.3,0.1

Type RM Length L Ch R = 1 ,7597    ,202,202,202
BEGIN DESCRIPTION:
Walnut79 11.0
END DESCRIPTION:
XS GIS Cut Line= 3
      2735552.17      6738255.85      2735606.86      6738518.84
      2735622.48      6738872.98
#Sta/Elev= 30
  4689.6  317.87  4694.9  316.18  4733.1  311.78  4736.9  312.32  4766.4  307.82
  4776.6  305.94  4781.9  303.79    4877  303.22  4888.9  300.21  4919.6  300.89
  4927.1  299.84  4932.2  296.01  4968.4  294.29  4968.6  293.79  4972.4  294.29
  4990.4   295.6  5010.4  298.53  5040.5  297.59  5048.8  296.37  5053.9  297.85
  5080.5  300.36  5112.5  296.43  5130.5  301.04  5150.6  300.19  5170.6  300.81
  5240.6  306.32  5270.7   310.7  5290.7  311.82  5309.2  316.57  5312.7  316.57
#Mann= 5 ,-1 , 0
  4689.6     .05       0  4733.1     .12       0  4968.4     .07       0
  4972.4     .12       0  5112.5     .05       0
Bank Sta=4968.4,4972.4
XS Rating Curve= 0 ,0
Exp/Cntr=0.3,0.1

Type RM Length L Ch R = 1 ,7395    ,239,239,239
BEGIN DESCRIPTION:
Walnut79 10.0
END DESCRIPTION:
XS GIS Cut Line= 3
      2735487.76      6738352.38      2735437.58      6738594.36
        2735476.      6738911.01
#Sta/Elev= 30
  4685.9  304.49  4714.6  303.01  4745.8  302.56  4814.9  302.78  4837.7  301.91
  4858.1   302.4  4865.1  301.74  4878.5  301.52    4899  302.31  4920.3  301.73
  4963.1  302.28  4969.9  299.84  4988.1  289.49  4988.3  288.99  4991.8  288.99
  4992.1  289.49  5020.3  297.71  5039.9  298.49  5044.9  298.21  5060.6  299.12
  5090.8  302.05  5130.5  304.44  5151.3  307.67  5191.5  310.54  5201.6  312.15
  5208.6  312.52  5213.6  313.49  5231.8  315.47  5241.9  318.55    5252  319.28
#Mann= 4 ,-1 , 0
  4685.9     .12       0  4988.1     .07       0  4992.1     .12       0
  5130.5     .05       0
Bank Sta=4988.1,4992.1
XS Rating Curve= 0 ,0
Exp/Cntr=0.3,0.1

Type RM Length L Ch R = 1 ,7156    ,319,319,319
BEGIN DESCRIPTION:
Walnut79 9.0
END DESCRIPTION:
XS GIS Cut Line= 4
      2735350.78      6738652.28      2735250.67      6738797.76
      2735312.58      6738859.99       2735423.5      6739027.64
#Sta/Elev= 30
  4796.4  301.39    4807  301.22  4813.4  300.06  4843.1  300.12  4849.2  300.93
    4906  300.52  4914.8  299.13  4920.9  299.43  4928.4  296.37  4956.7  295.34
    4979  295.93  4993.2   293.1  4998.3  287.79  4998.5  287.29  5002.3  287.79
  5007.3  288.51  5014.4  296.22  5021.5  299.24  5042.7  300.49  5056.8  302.21
  5059.7   303.4  5127.4   307.8  5144.2  309.33  5150.2   310.6  5157.9  310.79
  5171.3  313.26  5186.3  317.58  5201.4  316.48  5222.4  317.22  5261.8  323.79
#Mann= 4 ,-1 , 0
  4796.4     .12       0  4998.3     .07       0  5002.3     .12       0
  5127.4     .05       0
Bank Sta=4998.3,5002.3
XS Rating Curve= 0 ,0
Exp/Cntr=0.3,0.1