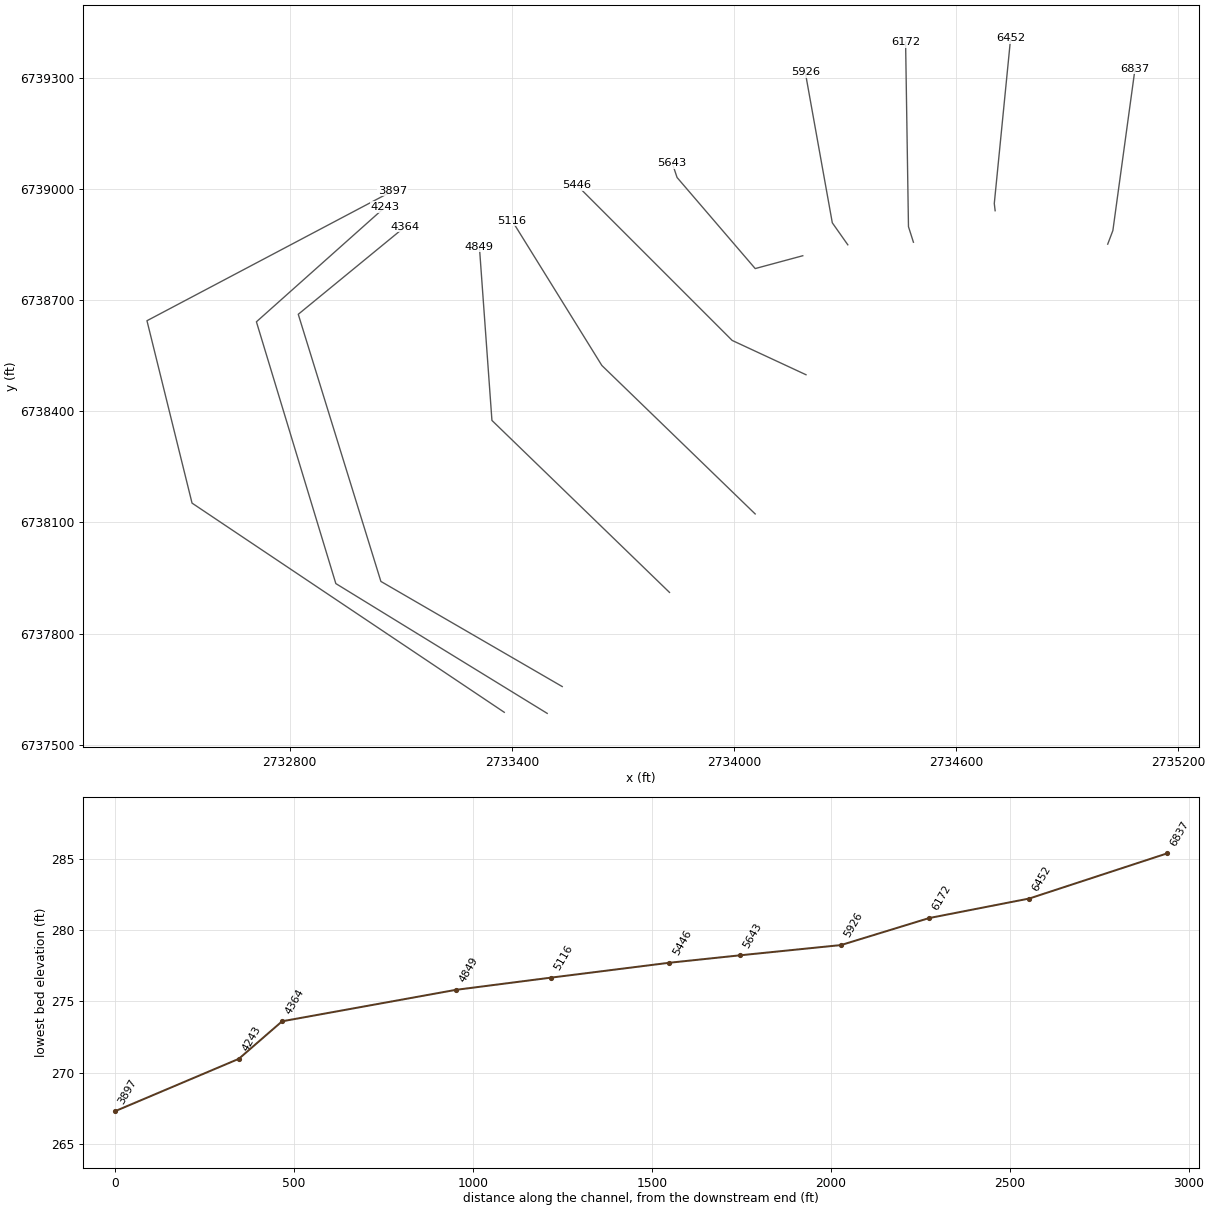
HEC-RAS study Walnut79.prj: Walnut79 Base Level Engineering

--- Walnut79.g01 (geometry) --- (continued)

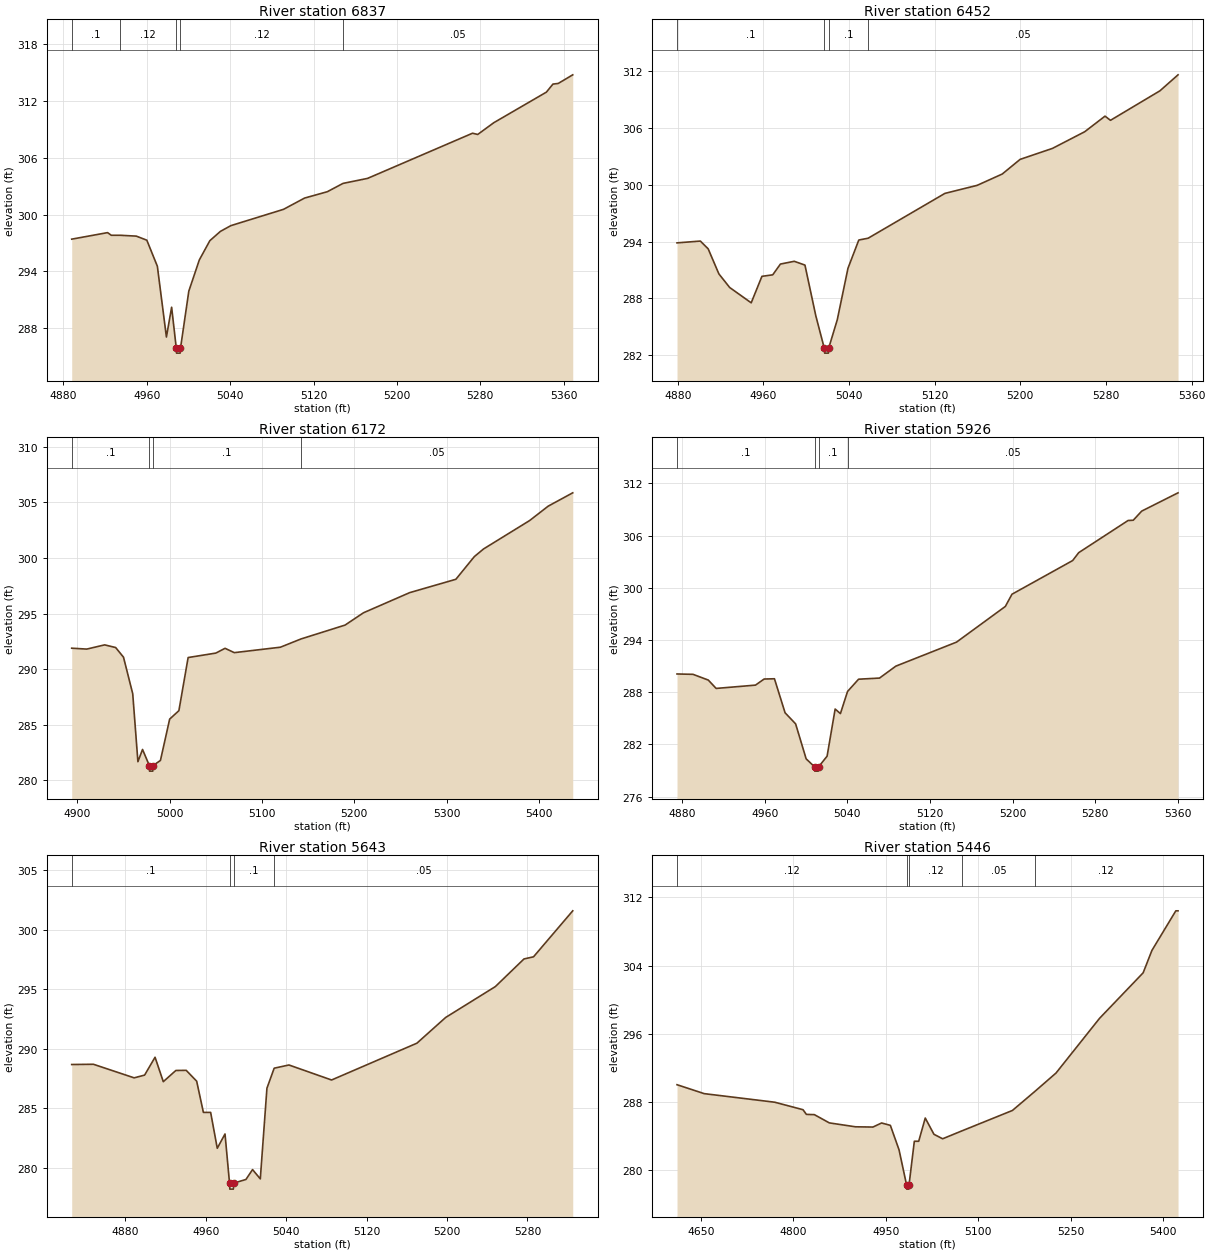
Type RM Length L Ch R = 1 ,6837    ,385,385,385
BEGIN DESCRIPTION:
Walnut79 8.0
END DESCRIPTION:
XS GIS Cut Line= 3
      2735009.56      6738851.79      2735023.52      6738888.63
      2735083.41      6739326.05
#Sta/Elev= 30
  4887.9   297.4  4922.3  298.09  4925.9  297.81  4934.6  297.81  4949.9  297.72
    4960  297.29  4970.1  294.54  4978.8  287.06  4983.8  290.21  4988.3  285.86
  4988.5  285.36    4992  285.36  4992.3  285.86  5000.3  291.91  5010.4  295.21
  5020.5  297.24  5030.6  298.22  5040.7  298.83  5091.2  300.55  5111.4  301.74
  5133.2  302.41  5148.3  303.29  5171.9  303.82  5272.6  308.59  5277.6  308.46
    5293   309.7  5343.5  312.93  5349.8  313.78  5354.9  313.85  5368.8  314.76
#Mann= 5 ,-1 , 0
  4887.9      .1       0  4934.6     .12       0  4988.3     .07       0
  4992.3     .12       0  5148.3     .05       0
Bank Sta=4988.3,4992.3
XS Rating Curve= 0 ,0
Exp/Cntr=0.3,0.1

Type RM Length L Ch R = 1 ,6452    ,280,280,280
BEGIN DESCRIPTION:
Walnut79 7.0
END DESCRIPTION:
XS GIS Cut Line= 3
      2734705.49      6738942.08      2734703.21      6738961.55
      2734747.31      6739407.78
#Sta/Elev= 30
  4879.3  293.86  4901.1  294.05  4908.4  293.23  4918.4  290.58  4928.5  289.14
  4948.6  287.52  4958.6  290.32  4968.7  290.48  4975.9  291.62  4988.8  291.91
  4998.8  291.51  5008.9  286.17  5016.9   282.7  5017.2   282.2  5020.7   282.2
  5020.9   282.7    5029  285.73    5039  291.18  5049.1  294.16  5057.8  294.35
  5129.5  299.09  5159.6  299.94  5183.1  301.14  5199.8  302.69    5230  303.85
  5260.1  305.61  5279.1  307.26  5284.2  306.82  5330.4  309.94  5347.3  311.63
#Mann= 4 ,-1 , 0
  4879.3      .1       0  5016.9     .07       0  5020.9      .1       0
  5057.8     .05       0
Bank Sta=5016.9,5020.9
XS Rating Curve= 0 ,0
Exp/Cntr=0.3,0.1

Type RM Length L Ch R = 1 ,6172    ,246,246,246
BEGIN DESCRIPTION:
Walnut79 6.5
END DESCRIPTION:
XS GIS Cut Line= 3
      2734484.81        6738857.      2734471.44      6738899.05
      2734463.65      6739397.56
#Sta/Elev= 30
  4893.9  291.89  4910.2  291.81  4929.6  292.19  4941.5  291.95    4950  291.08
    4960  287.79  4965.6  281.68  4970.6  282.78    4978  281.33  4978.2  280.83
  4981.7  280.83    4982  281.33    4990  281.79    5000  285.51    5010  286.27
    5020  291.05    5050  291.45    5060  291.88    5070  291.49    5120  291.98
  5142.2  292.72    5190  293.97    5210  295.08    5260  296.89    5310  298.09
    5330  300.13    5340  300.82    5390  303.38    5410  304.67  5436.6  305.87
#Mann= 4 ,-1 , 0
  4893.9      .1       0    4978     .07       0    4982      .1       0
  5142.2     .05       0
Bank Sta=4978,4982
XS Rating Curve= 0 ,0
Exp/Cntr=0.3,0.1

Type RM Length L Ch R = 1 ,5926    ,283,283,283
BEGIN DESCRIPTION:
Walnut79 6.0
END DESCRIPTION:
XS GIS Cut Line= 3
      2734307.59      6738850.03      2734265.71      6738909.47
       2734192.8      6739315.67
#Sta/Elev= 30
  4874.9   290.1  4890.4  290.06  4905.2   289.4  4912.8  288.44  4950.9  288.82
  4959.3  289.52  4969.3  289.55  4979.6  285.64  4989.8  284.37    5000  280.35
  5008.1  279.44  5008.4  278.94  5011.9  278.94  5012.1  279.44  5020.3  280.66
  5028.1  286.07  5033.2  285.55  5040.1  288.09  5050.8   289.5  5071.1  289.63
  5086.9     291  5145.7  293.76    5193  297.86  5199.4  299.26  5258.2  303.13
  5264.1  304.04  5311.9  307.73  5316.9  307.76  5325.1  308.81  5360.3  310.91
#Mann= 4 ,-1 , 0
  4874.9      .1       0  5008.1     .07       0  5012.1      .1       0
  5040.1     .05       0
Bank Sta=5008.1,5012.1
XS Rating Curve= 0 ,0
Exp/Cntr=0.3,0.1

Type RM Length L Ch R = 1 ,5643    ,197,197,197
BEGIN DESCRIPTION:
Walnut79 5.0
END DESCRIPTION:
XS GIS Cut Line= 4
      2734185.99      6738820.51      2734057.48      6738785.83
      2733846.44      6739031.86      2733833.43       6739070.9
#Sta/Elev= 30
  4826.7  288.68  4848.3   288.7  4888.8  287.56  4899.2  287.79  4909.6  289.29
  4917.8  287.24  4930.3  288.18  4940.6  288.19    4951  287.28  4957.7  284.66
  4964.9  284.66  4971.5  281.65  4979.2  282.85  4983.7  278.72    4984  278.22
  4987.5  278.22  4987.7  278.72    5000  279.03  5006.6  279.86  5014.3  279.08
  5020.9  286.69  5028.1  288.37  5042.8  288.64  5085.2  287.38  5170.1  290.47
  5198.7  292.63  5248.1  295.22  5276.6  297.54  5286.1  297.72  5325.1  301.58
#Mann= 4 ,-1 , 0
  4826.7      .1       0  4983.7     .07       0  4987.7      .1       0
  5028.1     .05       0
Bank Sta=4983.7,4987.7
XS Rating Curve= 0 ,0
Exp/Cntr=0.3,0.1

Type RM Length L Ch R = 1 ,5446    ,330,330,330
BEGIN DESCRIPTION:
Walnut79 4.0
END DESCRIPTION:
XS GIS Cut Line= 4
      2734194.62      6738499.06      2733995.34      6738591.66
        2733876.        6738711.      2733575.99      6739011.01
#Sta/Elev= 30
  4611.4  289.98  4655.5  288.93    4770  287.92  4815.8  287.04  4821.3  286.49
  4834.2  286.46  4858.5  285.49  4900.9  285.03  4929.2     285  4943.3  285.48
  4957.5   285.2  4971.6  282.32  4983.8   278.2    4984   277.7  4987.5   277.7
  4987.8   278.2  4996.4  283.33  5003.5  283.33  5014.1  286.06  5028.2  284.15
  5042.3  283.62  5073.9  284.56  5155.5  286.95  5191.6  289.17  5226.2  291.35
  5296.9  297.79  5367.6  303.14  5381.8  305.77  5420.6  310.43  5424.2  310.43
#Mann= 5 ,-1 , 0
  4611.4     .12       0  4983.8     .07       0  4987.8     .12       0
  5073.9     .05       0  5191.6     .12       0
Bank Sta=4983.8,4987.8
XS Rating Curve= 0 ,0
Exp/Cntr=0.3,0.1

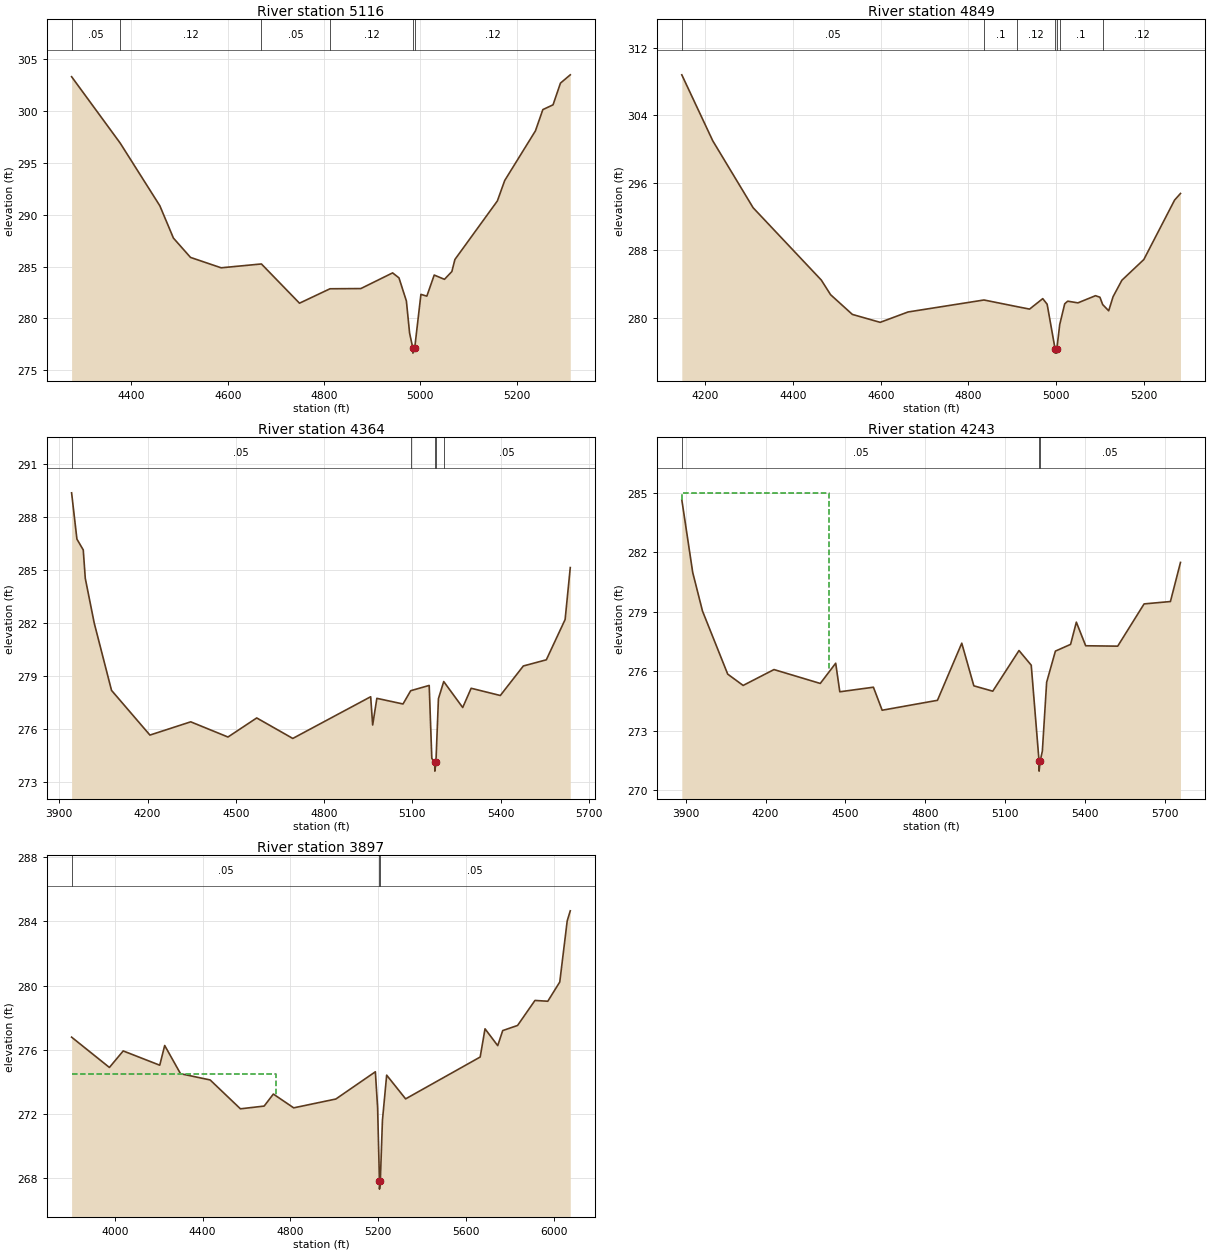
Type RM Length L Ch R = 1 ,5116    ,267,267,267
BEGIN DESCRIPTION:
Walnut79 3.0
END DESCRIPTION:
XS GIS Cut Line= 3
      2734057.38        6738123.      2733643.31      6738524.05
      2733401.11      6738914.71
#Sta/Elev= 30
  4275.6  303.29  4376.6  296.89  4458.9  290.86  4487.2  287.74  4522.7  285.88
  4586.3  284.88    4670  285.25  4749.1  281.47  4812.5  282.86  4876.6  282.88
  4942.6  284.39  4955.8  283.91  4971.2  281.68  4977.9  278.58  4984.5  277.16
  4984.8  276.66  4988.5  277.16  5001.4  282.32  5013.7  282.15    5029  284.18
  5050.3  283.77  5065.7  284.52    5072  285.68  5160.2  291.32  5175.5  293.29
  5239.3  298.07  5254.7  300.12  5275.9  300.58  5291.3  302.67  5311.7  303.47
#Mann= 6 ,-1 , 0
  4275.6     .05       0  4376.6     .12       0    4670     .05       0
  4812.5     .12       0  4984.5     .07       0  4988.5     .12       0
Bank Sta=4984.5,4988.5
XS Rating Curve= 0 ,0
Exp/Cntr=0.3,0.1

Type RM Length L Ch R = 1 ,4849    ,485,485,485
BEGIN DESCRIPTION:
Walnut79 2.0
END DESCRIPTION:
XS GIS Cut Line= 3
        2733826.        6737911.      2733346.44      6738375.61
      2733312.58      6738844.37
#Sta/Elev= 30
  4146.1   308.8  4216.7  300.98  4308.8  293.04  4464.4  284.46  4485.5  282.73
  4535.2  280.39  4598.7  279.45  4662.3  280.68  4835.5   282.1  4910.2  281.32
  4939.5  281.02  4969.6  282.26  4979.6   281.6  4997.7   276.3  4997.9   275.8
  5001.4   275.8  5001.7   276.3  5008.3  279.19  5019.7  281.65  5026.5  281.96
  5049.8  281.76  5089.9  282.61    5100  282.43  5106.3  281.56    5120  280.82
    5130  282.49  5150.1  284.44  5200.2   286.9  5270.4  293.95  5283.8  294.73
#Mann= 7 ,-1 , 0
  4146.1     .05       0  4835.5      .1       0  4910.2     .12       0
  4997.7     .07       0  5001.7     .12       0  5008.3      .1       0
  5106.3     .12       0
Bank Sta=4997.7,5001.7
XS Rating Curve= 0 ,0
Exp/Cntr=0.3,0.1

Type RM Length L Ch R = 1 ,4364    ,121,121,121
BEGIN DESCRIPTION:
Walnut79 1.5
END DESCRIPTION:
XS GIS Cut Line= 4
      2733536.25      6737656.71       2733046.5      6737940.71
      2732823.35      6738662.32      2733112.11      6738899.11
#Sta/Elev= 30
  3941.7  289.35  3959.8  286.73  3981.3  286.12  3988.2  284.51  4018.6  281.98
  4077.4  278.17  4207.9  275.64  4346.6  276.39  4473.2  275.53  4570.9  276.61
  4693.5  275.45  4958.2  277.81    4965  276.21  4979.2  277.72  5068.1   277.4
  5094.2  278.15  5157.1  278.45    5166  274.32    5176   274.1  5176.3   273.6
    5180   274.1  5188.5   277.7  5206.5  278.67    5271   277.2  5299.7  278.29
  5398.8  277.88    5477  279.55  5555.2   279.9  5619.1  282.18  5636.6  285.12
#Mann= 5 ,-1 , 0
  3941.7     .05       0  5094.2     .12       0    5176     .04       0
    5180     .12       0  5206.5     .05       0
Bank Sta=5176,5180
XS Rating Curve= 0 ,0
Exp/Cntr=0.3,0.1

Type RM Length L Ch R = 1 ,4243    ,346,346,346
BEGIN DESCRIPTION:
Walnut79 1.0
END DESCRIPTION:
XS GIS Cut Line= 4
      2733495.69      6737584.25      2732924.78      6737934.91
      2732710.32      6738642.03      2733058.11      6738952.15
#Sta/Elev= 30
    3885  284.65  3926.1  280.98  3962.8  279.04  4057.6  275.86  4115.6  275.29
  4231.6  276.09  4405.6  275.39  4463.6  276.41    4479  274.97  4605.4   275.2
  4638.3  274.04  4846.2  274.54  4937.6  277.42    4983  275.27  5054.1     275
  5152.8  277.05  5198.8  276.31  5228.2  271.47  5228.4  270.97  5232.2  271.47
  5240.6  271.98  5256.7  275.45  5289.6  277.02  5346.7  277.36  5368.4  278.48
  5403.5  277.29  5523.9  277.27  5623.1   279.4  5722.1  279.52  5759.9  281.49
#Mann= 3 ,-1 , 0
    3885     .05       0  5228.2     .04       0  5232.2     .05       0
#XS Ineff= 2 , 0
       0    4440     285               0
Permanent Ineff=
       F       F
Bank Sta=5228.2,5232.2
XS Rating Curve= 0 ,0
Exp/Cntr=0.3,0.1

Type RM Length L Ch R = 1 ,3897    ,0,0,0
BEGIN DESCRIPTION:
Walnut79 0.7
END DESCRIPTION:
XS GIS Cut Line= 4
      2733379.75      6737587.16      2732536.44      6738152.27
      2732414.72      6738644.93      2733078.36      6738995.59
#Sta/Elev= 30
  3803.1  276.78  3975.4  274.89  4038.4  275.92  4204.9  275.03  4227.5  276.26
  4299.6   274.5  4434.7  274.11  4572.7  272.31  4680.8  272.48  4722.8  273.23
  4815.5  272.37  5007.6  272.92  5187.8  274.62  5198.1  272.38  5206.4   267.8
  5206.6   267.3  5210.4   267.8    5220  271.58  5239.3  274.41  5325.7  272.93
  5665.6  275.54  5687.7   277.3  5745.6  276.25  5768.3  277.19  5836.1  277.51
  5915.3  279.07  5973.8  279.02  6028.4  280.22  6062.3  284.03  6076.3  284.66
#Mann= 3 ,-1 , 0
  3803.1     .05       0  5206.4     .05       0  5210.4     .05       0
#XS Ineff= 2 , 0
       0    4735   274.5               0
Permanent Ineff=
       F       F
Bank Sta=5206.4,5210.4
XS Rating Curve= 0 ,0
Exp/Cntr=0.3,0.1

Chan Stop Cuts=-1
Use User Specified Reach Order=0
Composite Channel Slope=5