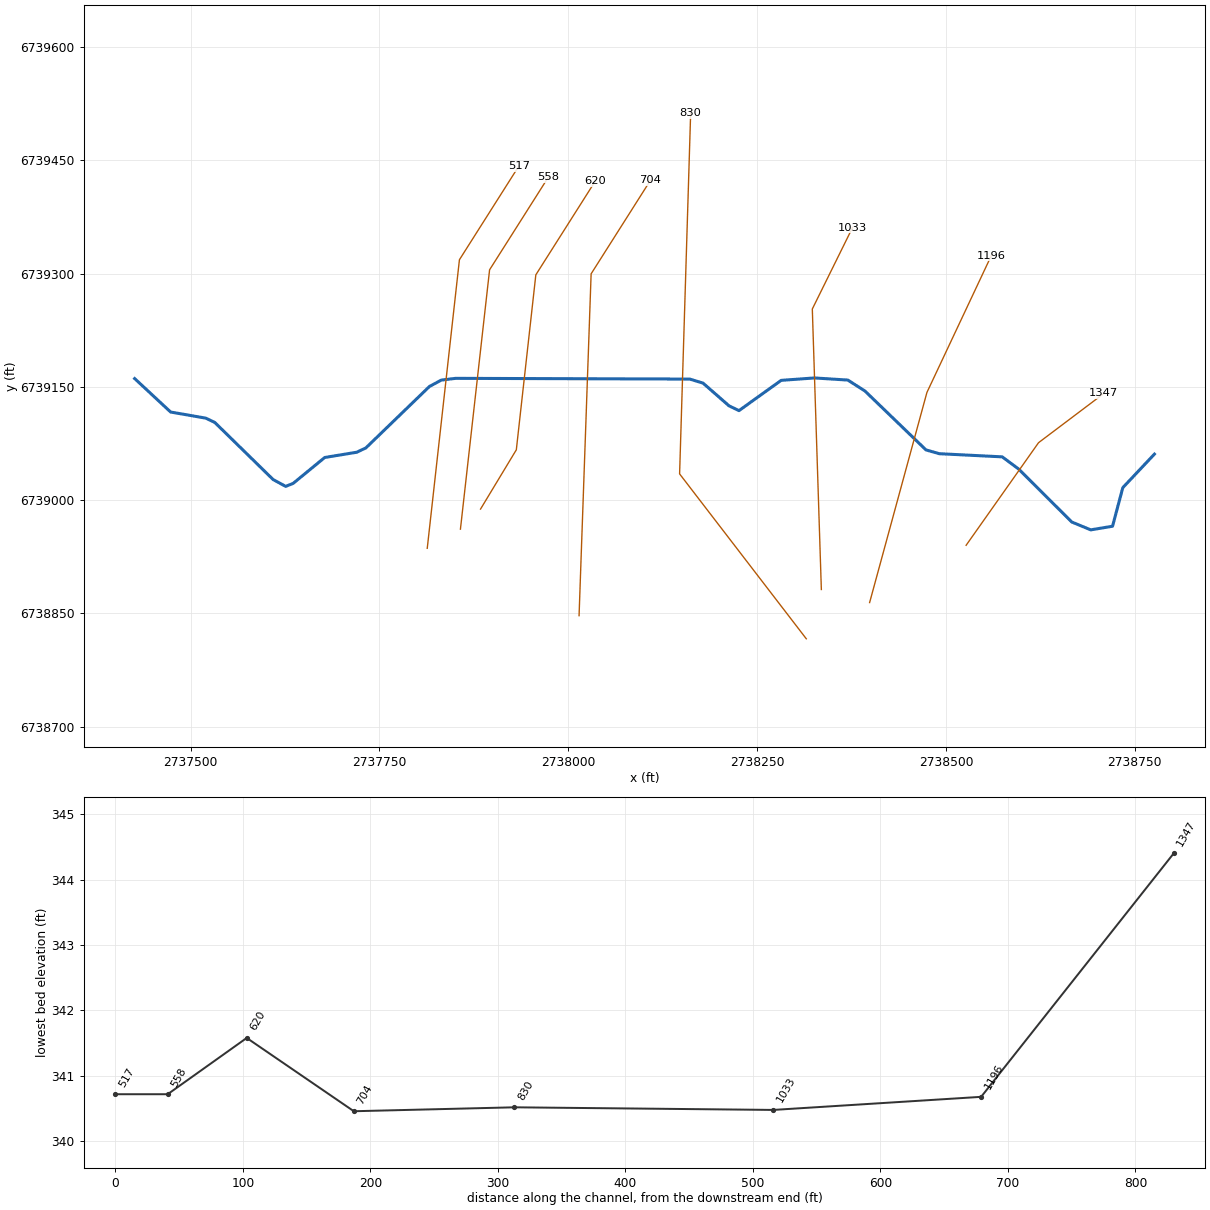
--- Walnut81.prj (project) ---

Proj Title=Walnut81 Base Level Engineering
Current Plan=p01
Default Exp/Contr=0.3,0.1
English Units
Geom File=g01
Flow File=f01
Plan File=p01
Y Axis Title=Elevation
X Axis Title(PF)=Main Channel Distance
X Axis Title(XS)=Station
BEGIN DESCRIPTION:
Walnut81
END DESCRIPTION:
DSS Export Rating Curves= 0
DSS Export Rating Curve Sorted= 0
DSS Export Volume Flow Curves= 0
DXF OffsetX= 0
DXF OffsetY= 0
DXF ScaleX= 1
DXF ScaleY= 10

--- Walnut81.p01 (plan) ---

Plan Title=Multiple Run
Program Version=4.10
Short Identifier=Multiple
Geom File=g01
Flow File=f01
Subcritical Flow
K Sum by GR= 0
Std Step Tol= 0.01
Critical Tol= 0.01
Num of Std Step Trials= 20
Max Error Tol= 0.3
Flow Tol Ratio= 0.001
Split Flow NTrial= 30
Split Flow Tol= 0.02
Split Flow Ratio= 0.02
Log Output Level= 0
Friction Slope Method= 1
Unsteady Friction Slope Method= 2
Unsteady Bridges Friction Slope Method= 1
Parabolic Critical Depth
Global Vel Dist= 1 , 1 , 1
Global Log Level= 0
CheckData=True
Encroach Param=-1 ,0,0, 0
BEGIN DESCRIPTION:
Multiple Run
END DESCRIPTION:
Computation Interval=1HOUR
Output Interval=1HOUR
Run HTab= 0
Run UNet= 0
Run PostProcess= 0
Run WQNet= 0
UNET Theta= 1
UNET Theta Warmup= 1
UNET ZTol= 0.02
UNET ZSATol= 0.05
UNET MxIter= 20
UNET MaxInSteps= 0
UNET DtIC= 0
UNET DtMin= 0
UNET MaxCRTS= 20
UNET WFStab= 2
UNET SFStab= 1
UNET WFX= 1
UNET SFX= 1
UNET DSS MLevel= 4
UNET DZMax Abort= 100
UNET Convert EG Bridges= 0
UNET Use Existing IB Tables=-1
UNET Froude Reduction=False
UNET Froude Limit= 1
UNET Froude Power= 10
UNET Time Slicing=0,0, 5
UNET Junction Losses=0
Instantaneous Interval=1HOUR
Write IC File= 0
Write IC File at Sim End=0
Echo Input=False
Echo Parameters=False
Echo Output=False
Write Detailed= 0
WQ AD Non Conservative
WQ ULTIMATE=-1
WQ Max Comp Step=1HOUR
WQ Output Interval=15MIN
WQ Output Selected Increments= 0
WQ Output face flow=0
WQ Output face velocity=0
WQ Output face area=0
WQ Output face dispersion=0
WQ Output cell volume=0
WQ Output cell surface area=0
WQ Output cell continuity=0
WQ Output cumulative cell continuity=0
WQ Output face conc=0
WQ Output face dconc_dx=0
WQ Output face courant=0
WQ Output face peclet=0
WQ Output face adv mass=0
WQ Output face disp mass=0
WQ Output cell mass=0
WQ Output cell source sink temp=0
WQ Output cell source sink nsm=0
WQ Output MaxMinRange=-1
WQ Daily Max Min Mean=-1
WQ Daily Range=0
WQ Daily Time=0
WQ Create Restart=0
WQ Fixed Restart=0
WQ System Summary=0
WQ Use Fixed Temperature=0
Sorting and Armoring Iterations= 10
XS Update Threshold= 0.02
Hydraulics Update Threshold= 0.02
Energy Slope Method= 1
Volume Change Method= 0
XS Weighting Method= 0
Number of US Weighted Cross Sections= 1
Number of DS Weighted Cross Sections= 1
Upstream XS Weight=0.25
Main XS Weight=0.5
Downstream XS Weight=0.25
Number of DS XS's Weighted with US Boundary= 1
Upstream Boundary Weight= 1
Weight of XSs Associated with US Boundary= 0
Number of US XS's Weighted with DS Boundary= 1
Downstream Boundary Weight= 0.5
Weight of XSs Associated with DS Boundary= 0.5
Sediment Output Level= 4
Mass or Volume Output= 0
Output Increment Type= 1
Profile and TS Output Increment= 10
XS Output Flag= 0
XS Output Increment= 10
Disregard all LS=0
Disregard all Conn=0
Disregard all Breaches=0
Disregard all Pumps=0

--- Walnut81.f01 (steady flow) ---

Flow Title=Multiple
Number of Profiles=7
Profile Names=10-year,25-year,50-year,1pct_min,100-year,1pct_plu,500-year
River Rch & RM= Walnut81,Reach-1,1347
      98     118     132      74     148     296     186
Boundary for River Rch & Prof#=Walnut81,Reach-1,1
Up Type=0
Dn Type=3
Dn Slope=0.005
Boundary for River Rch & Prof#=Walnut81,Reach-1,2
Up Type=0
Dn Type=3
Dn Slope=0.005
Boundary for River Rch & Prof#=Walnut81,Reach-1,3
Up Type=0
Dn Type=3
Dn Slope=0.005
Boundary for River Rch & Prof#=Walnut81,Reach-1,4
Up Type=0
Dn Type=3
Dn Slope=0.005
Boundary for River Rch & Prof#=Walnut81,Reach-1,5
Up Type=0
Dn Type=3
Dn Slope=0.005
Boundary for River Rch & Prof#=Walnut81,Reach-1,6
Up Type=0
Dn Type=3
Dn Slope=0.005
Boundary for River Rch & Prof#=Walnut81,Reach-1,7
Up Type=0
Dn Type=3
Dn Slope=0.005

--- Walnut81.g01 (geometry) ---

Geom Title=Existing Conditions

River Reach=Walnut81,Reach-1
Reach XY= 30
      2738776.00      6739061.00      2738734.12      6739016.56
      2738720.56      6738965.53      2738691.71      6738960.72
      2738666.59      6738971.09      2738596.14      6739041.32
      2738574.50      6739057.37      2738491.22      6739061.53
      2738473.58      6739066.54      2738392.74      6739144.56
      2738370.10      6739159.02      2738326.00      6739161.82
      2738281.90      6739158.64      2738226.00      6739118.56
      2738212.79      6739124.95      2738178.45      6739154.98
      2738160.84      6739160.34      2737850.88      6739161.29
      2737831.86      6739158.94      2737816.21      6739150.50
      2737732.04      6739069.14      2737719.95      6739063.46
      2737677.65      6739056.54      2737635.87      6739022.27
      2737625.92      6739018.29      2737609.31      6739027.31
      2737532.09      6739102.91      2737520.03      6739108.64
      2737473.65      6739116.70      2737426.00      6739161.00

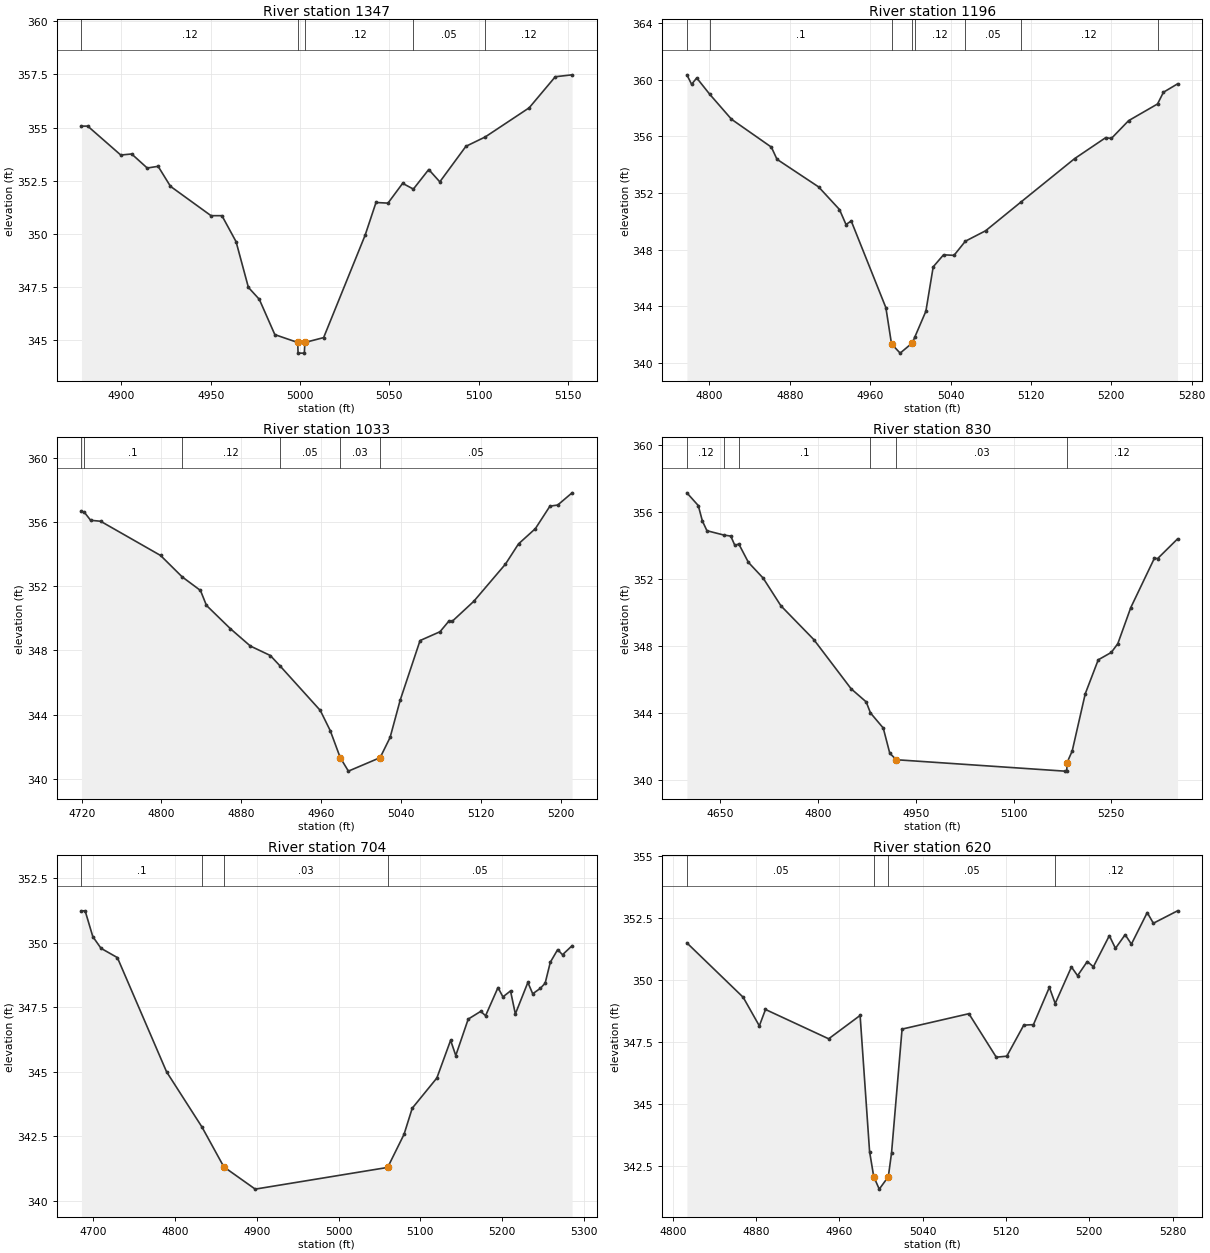
Type RM Length L Ch R = 1,1347,151,151,151
BEGIN DESCRIPTION:
Walnut81 4.0
END DESCRIPTION:
XS GIS Cut Line= 3
      2738526.73      6738940.32      2738622.56      6739076.08
      2738709.06      6739141.28
#Sta/Elev= 30
  4877.7  355.07  4881.2  355.07  4899.7  353.71  4905.8  353.76  4914.5  353.10
  4920.6  353.18  4927.5  352.24  4950.2  350.86  4956.3  350.86  4964.2  349.64
  4971.1  347.49  4977.2  346.93  4985.9  345.27  4998.7  344.90  4998.9  344.40
  5002.4  344.40  5002.7  344.90  5013.2  345.13  5036.4  349.94  5042.5  351.48
  5049.2  351.45  5057.4  352.38  5063.4  352.11  5072.0  353.03  5078.2  352.45
  5092.8  354.12  5103.6  354.56  5128.2  355.93  5142.8  357.39  5152.2  357.48
#Mann=5,-1,0
  4877.7    0.12       0  4998.7    0.07       0  5002.7    0.12       0
  5063.4    0.05       0  5103.6    0.12       0
Bank Sta=4998.7,5002.7
Exp/Cntr=0.3,0.1

Type RM Length L Ch R = 1,1196,163,163,163
BEGIN DESCRIPTION:
Walnut81 3.5
END DESCRIPTION:
XS GIS Cut Line= 3
      2738398.96      6738864.47      2738474.82      6739142.62
      2738560.02      6739323.67
#Sta/Elev= 30
  4777.5  360.35  4782.2  359.68  4787.3  360.13  4800.2  358.98  4821.9  357.21
  4861.6  355.24  4867.2  354.38  4908.6  352.43  4929.4  350.83  4935.9  349.77
  4941.1  350.02  4975.6  343.89  4981.2  341.33  4989.8  340.68  5001.9  341.40
  5004.6  341.85  5015.4  343.64  5022.7  346.78  5033.0  347.63  5043.4  347.59
  5054.7  348.59  5074.9  349.33  5109.7  351.34  5163.5  354.43  5194.4  355.91
  5200.0  355.85  5217.2  357.11  5246.0  358.29  5251.9  359.12  5265.9  359.71
#Mann=8,-1,0
  4777.5    0.12       0  4800.2     0.1       0  4981.2    0.05       0
  5001.9     0.1       0  5004.6    0.12       0  5054.7    0.05       0
  5109.7    0.12       0  5246.0     0.1       0
Bank Sta=4981.2,5001.9
Exp/Cntr=0.3,0.1

Type RM Length L Ch R = 1,1033,203,203,203
BEGIN DESCRIPTION:
Walnut81 3.0
END DESCRIPTION:
XS GIS Cut Line= 3
      2738335.07      6738881.76      2738323.10      6739253.09
      2738376.35      6739360.94
#Sta/Elev= 30
  4719.8  356.66  4722.7  356.60  4729.0  356.10  4739.0  356.04  4799.1  353.91
  4820.7  352.58  4839.1  351.73  4845.1  350.80  4869.1  349.35  4889.1  348.27
  4909.1  347.68  4918.6  347.05  4959.2  344.26  4969.2  343.00  4979.2  341.32
  4987.4  340.48  5019.2  341.32  5029.2  342.58  5039.2  344.88  5059.2  348.61
  5079.2  349.16  5087.8  349.80  5091.3  349.80  5113.0  351.05  5144.8  353.37
  5157.9  354.63  5174.8  355.58  5189.4  356.98  5197.2  357.05  5211.6  357.81
#Mann=6,-1,0
  4719.8    0.12       0  4722.7     0.1       0  4820.7    0.12       0
  4918.6    0.05       0  4979.2    0.03       0  5019.2    0.05       0
Bank Sta=4979.2,5019.2
Exp/Cntr=0.3,0.1

Type RM Length L Ch R = 1,830,126,126,126
BEGIN DESCRIPTION:
Walnut81 2.0
END DESCRIPTION:
XS GIS Cut Line= 3
      2738315.11      6738816.54      2738147.41      6739034.82
      2738162.05      6739512.64
#Sta/Elev= 30
  4598.4  357.12  4615.9  356.36  4622.2  355.44  4629.2  354.86  4655.3  354.60
  4665.8  354.54  4672.1  353.98  4678.1  354.07  4692.9  352.97  4715.6  352.03
  4742.8  350.38  4793.2  348.37  4850.6  345.43  4873.7  344.65  4880.3  343.99
  4899.9  343.09  4909.9  341.59  4919.9  341.20  5178.2  340.52  5181.7  340.52
  5182.0  341.02  5190.0  341.72  5210.0  345.13  5230.0  347.16  5250.0  347.60
  5260.0  348.12  5280.0  350.28  5316.2  353.22  5321.2  353.20  5351.7  354.37
#Mann=6,-1,0
  4598.4    0.12       0  4655.3    0.05       0  4678.1     0.1       0
  4880.3    0.05       0  4919.9    0.03       0  5182.0    0.12       0
Bank Sta=4919.9,5182
Exp/Cntr=0.3,0.1

Type RM Length L Ch R = 1,704,84,84,84
BEGIN DESCRIPTION:
Walnut81 1.6
END DESCRIPTION:
XS GIS Cut Line= 3
      2738014.32      6738847.11      2738030.29      6739299.67
      2738108.80      6739423.42
#Sta/Elev= 30
  4685.9  351.23  4690.4  351.23  4699.8  350.23  4709.8  349.78  4729.8  349.42
  4789.9  345.00  4833.2  342.86  4859.9  341.32  4898.2  340.46  5060.0  341.30
  5080.0  342.58  5090.0  343.59  5120.1  344.76  5136.9  346.22  5143.2  345.63
  5158.4  347.04  5173.7  347.34  5179.6  347.17  5194.8  348.26  5200.8  347.90
  5210.1  348.13  5216.0  347.24  5231.3  348.46  5237.2  348.02  5246.5  348.23
  5252.4  348.43  5258.7  349.24  5267.7  349.73  5273.6  349.53  5285.3  349.88
#Mann=4,-1,0
  4685.9     0.1       0  4833.2    0.05       0  4859.9    0.03       0
  5060.0    0.05       0
Bank Sta=4859.9,5060
Exp/Cntr=0.3,0.1

Type RM Length L Ch R = 1,620,62,62,62
BEGIN DESCRIPTION:
Walnut81 1.4
END DESCRIPTION:
XS GIS Cut Line= 4
      2737883.89      6738988.24      2737931.26      6739066.67
      2737957.09      6739298.34      2738035.60      6739422.10
#Sta/Elev= 30
  4813.4  351.49  4867.5  349.30  4883.0  348.15  4888.9  348.81  4949.6  347.63
  4979.8  348.57  4988.9  343.09  4992.9  342.08  4998.2  341.58  5006.9  342.08
  5010.0  343.04  5020.1  348.02  5084.3  348.64  5110.6  346.89  5120.7  346.93
  5137.0  348.18  5146.3  348.20  5161.6  349.70  5167.2  349.05  5182.8  350.52
  5188.7  350.17  5198.0  350.74  5203.9  350.53  5219.2  351.78  5225.1  351.27
  5234.4  351.82  5240.4  351.44  5255.6  352.71  5261.5  352.28  5284.7  352.78
#Mann=4,-1,0
  4813.4    0.05       0  4992.9    0.03       0  5006.9    0.05       0
  5167.2    0.12       0
Bank Sta=4992.9,5006.9
Exp/Cntr=0.3,0.1

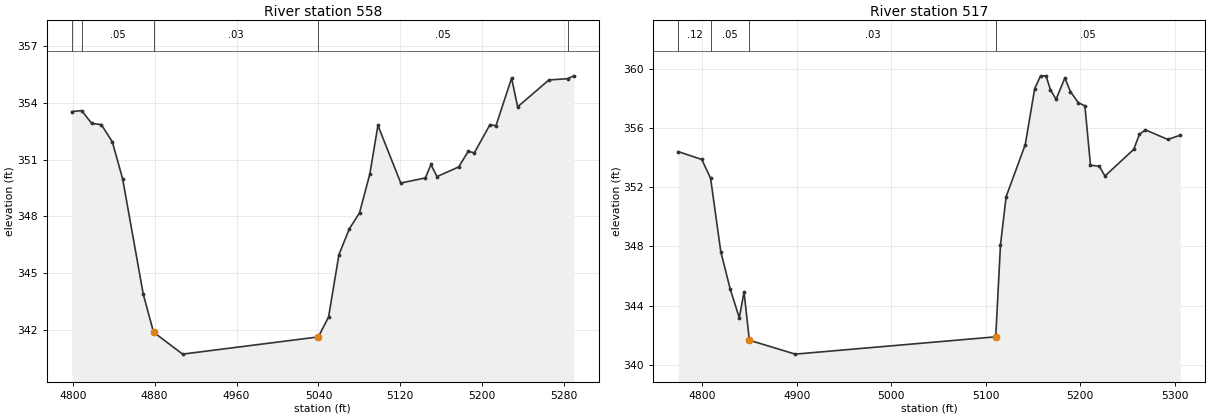
Type RM Length L Ch R = 1,558,41,41,41
BEGIN DESCRIPTION:
Walnut81 1.2
END DESCRIPTION:
XS GIS Cut Line= 3
      2737857.27      6738961.64      2737895.87      6739305.00
      2737973.53      6739427.42
#Sta/Elev= 30
  4799.0  353.55  4808.7  353.60  4818.5  352.92  4827.9  352.86  4838.6  351.95
  4848.7  349.99  4868.8  343.90  4878.9  341.88  4907.3  340.72  5039.9  341.63
  5049.9  342.69  5060.0  345.98  5070.1  347.34  5080.1  348.19  5090.2  350.25
  5098.1  352.82  5120.4  349.77  5144.5  350.04  5149.9  350.75  5155.8  350.11
  5177.0  350.62  5186.3  351.44  5192.3  351.37  5207.5  352.85  5213.4  352.80
  5228.7  355.32  5234.6  353.80  5265.1  355.22  5283.4  355.29  5289.5  355.44
#Mann=5,-1,0
  4799.0    0.12       0  4808.7    0.05       0  4878.9    0.03       0
  5039.9    0.05       0  5283.4    0.12       0
Bank Sta=4878.9,5039.9
Exp/Cntr=0.3,0.1

Type RM Length L Ch R = 1,517,0,0,0
BEGIN DESCRIPTION:
Walnut81 1.0
END DESCRIPTION:
XS GIS Cut Line= 3
      2737813.34      6738936.30      2737855.94      6739318.31
      2737934.48      6739442.12
#Sta/Elev= 30
  4774.7  354.40  4799.6  353.87  4808.9  352.61  4819.7  347.64  4829.7  345.11
  4839.3  343.17  4844.3  344.92  4849.9  341.66  4898.4  340.72  5110.5  341.89
  5115.5  348.10  5121.5  351.36  5141.7  354.87  5151.7  358.65  5157.9  359.52
  5163.6  359.52  5168.4  358.57  5174.3  357.93  5183.6  359.38  5189.5  358.45
  5197.8  357.71  5204.8  357.49  5210.7  353.48  5220.0  353.41  5226.0  352.75
  5256.5  354.56  5262.4  355.56  5268.8  355.87  5292.5  355.22  5305.7  355.51
#Mann=4,-1,0
  4774.7    0.12       0  4808.9    0.05       0  4849.9    0.03       0
  5110.5    0.05       0
Bank Sta=4849.9,5110.5
Exp/Cntr=0.3,0.1

Chan Stop Cuts=-1