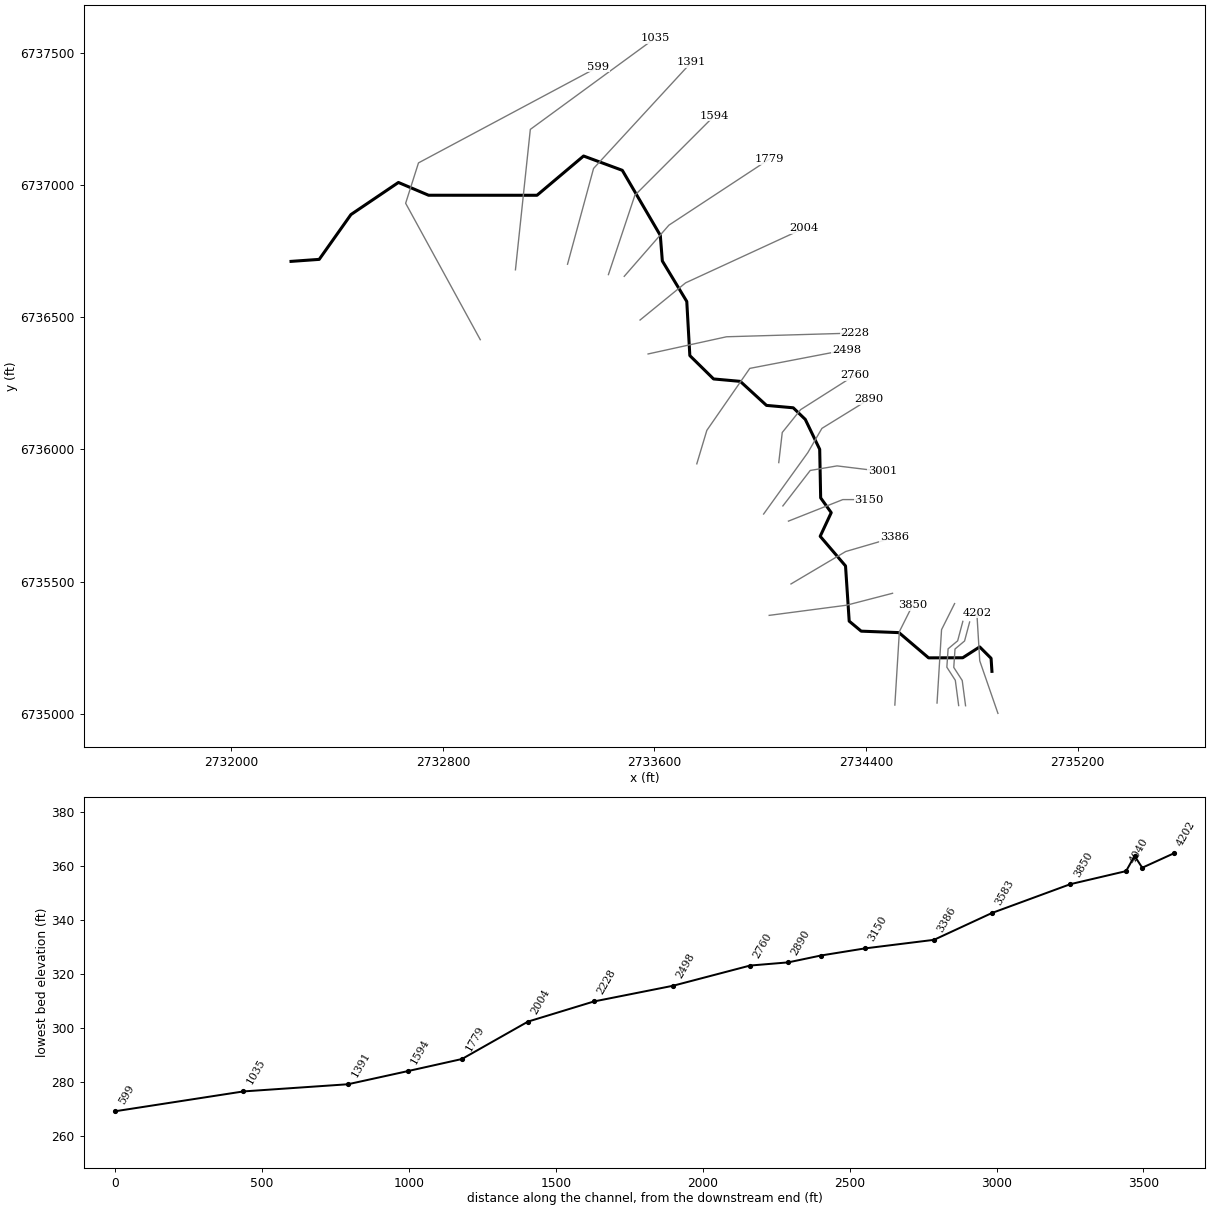
--- Walnut83.prj (project) ---

Proj Title=Walnut83 Base Level Engineering
Current Plan=p01
Default Exp/Contr=0.3,0.1
English Units
Geom File=g01
Flow File=f01
Plan File=p01
Y Axis Title=Elevation
X Axis Title(PF)=Main Channel Distance
X Axis Title(XS)=Station
BEGIN DESCRIPTION:
Walnut83
END DESCRIPTION:
DSS Export Rating Curves= 0
DSS Export Rating Curve Sorted= 0
DSS Export Volume Flow Curves= 0
DXF OffsetX= 0
DXF OffsetY= 0
DXF ScaleX= 1
DXF ScaleY= 10

--- Walnut83.p01 (plan) ---

Plan Title=Multiple Run
Program Version=4.10
Short Identifier=Multiple
Geom File=g01
Flow File=f01
Subcritical Flow
K Sum by GR= 0
Std Step Tol= 0.01
Critical Tol= 0.01
Num of Std Step Trials= 20
Max Error Tol= 0.3
Flow Tol Ratio= 0.001
Split Flow NTrial= 30
Split Flow Tol= 0.02
Split Flow Ratio= 0.02
Log Output Level= 0
Friction Slope Method= 1
Unsteady Friction Slope Method= 2
Unsteady Bridges Friction Slope Method= 1
Parabolic Critical Depth
Global Vel Dist= 1 , 1 , 1
Global Log Level= 0
CheckData=True
Encroach Param=-1 ,0,0, 0
BEGIN DESCRIPTION:
Multiple Run
END DESCRIPTION:
Computation Interval=1HOUR
Output Interval=1HOUR
Run HTab= 0
Run UNet= 0
Run PostProcess= 0
Run WQNet= 0
UNET Theta= 1
UNET Theta Warmup= 1
UNET ZTol= 0.02
UNET ZSATol= 0.05
UNET MxIter= 20
UNET MaxInSteps= 0
UNET DtIC= 0
UNET DtMin= 0
UNET MaxCRTS= 20
UNET WFStab= 2
UNET SFStab= 1
UNET WFX= 1
UNET SFX= 1
UNET DSS MLevel= 4
UNET DZMax Abort= 100
UNET Convert EG Bridges= 0
UNET Use Existing IB Tables=-1
UNET Froude Reduction=False
UNET Froude Limit= 1
UNET Froude Power= 10
UNET Time Slicing=0,0, 5
UNET Junction Losses=0
Instantaneous Interval=1HOUR
Write IC File= 0
Write IC File at Sim End=0
Echo Input=False
Echo Parameters=False
Echo Output=False
Write Detailed= 0
WQ AD Non Conservative
WQ ULTIMATE=-1
WQ Max Comp Step=1HOUR
WQ Output Interval=15MIN
WQ Output Selected Increments= 0
WQ Output face flow=0
WQ Output face velocity=0
WQ Output face area=0
WQ Output face dispersion=0
WQ Output cell volume=0
WQ Output cell surface area=0
WQ Output cell continuity=0
WQ Output cumulative cell continuity=0
WQ Output face conc=0
WQ Output face dconc_dx=0
WQ Output face courant=0
WQ Output face peclet=0
WQ Output face adv mass=0
WQ Output face disp mass=0
WQ Output cell mass=0
WQ Output cell source sink temp=0
WQ Output cell source sink nsm=0
WQ Output MaxMinRange=-1
WQ Daily Max Min Mean=-1
WQ Daily Range=0
WQ Daily Time=0
WQ Create Restart=0
WQ Fixed Restart=0
WQ System Summary=0
WQ Use Fixed Temperature=0
Sorting and Armoring Iterations= 10
XS Update Threshold= 0.02
Hydraulics Update Threshold= 0.02
Energy Slope Method= 1
Volume Change Method= 0
XS Weighting Method= 0
Number of US Weighted Cross Sections= 1
Number of DS Weighted Cross Sections= 1
Upstream XS Weight=0.25
Main XS Weight=0.5
Downstream XS Weight=0.25
Number of DS XS's Weighted with US Boundary= 1
Upstream Boundary Weight= 1
Weight of XSs Associated with US Boundary= 0
Number of US XS's Weighted with DS Boundary= 1
Downstream Boundary Weight= 0.5
Weight of XSs Associated with DS Boundary= 0.5
Sediment Output Level= 4
Mass or Volume Output= 0
Output Increment Type= 1
Profile and TS Output Increment= 10
XS Output Flag= 0
XS Output Increment= 10
Disregard all LS=0
Disregard all Conn=0
Disregard all Breaches=0
Disregard all Pumps=0

--- Walnut83.f01 (steady flow) ---

Flow Title=Multiple
Number of Profiles=7
Profile Names=10-year,25-year,50-year,1pct_min,100-year,1pct_plu,500-year
River Rch & RM= Walnut83,Reach-1,4202
     271     354     420     249     497     991     695
Boundary for River Rch & Prof#=Walnut83,Reach-1,1
Up Type=0
Dn Type=3
Dn Slope=0.005
Boundary for River Rch & Prof#=Walnut83,Reach-1,2
Up Type=0
Dn Type=3
Dn Slope=0.005
Boundary for River Rch & Prof#=Walnut83,Reach-1,3
Up Type=0
Dn Type=3
Dn Slope=0.005
Boundary for River Rch & Prof#=Walnut83,Reach-1,4
Up Type=0
Dn Type=3
Dn Slope=0.005
Boundary for River Rch & Prof#=Walnut83,Reach-1,5
Up Type=0
Dn Type=3
Dn Slope=0.005
Boundary for River Rch & Prof#=Walnut83,Reach-1,6
Up Type=0
Dn Type=3
Dn Slope=0.005
Boundary for River Rch & Prof#=Walnut83,Reach-1,7
Up Type=0
Dn Type=3
Dn Slope=0.005

--- Walnut83.g01 (geometry) ---

Geom Title=Existing Conditions

River Reach=Walnut83,Reach-1
Reach XY= 30
      2734876.00      6735161.00      2734872.73      6735210.37
      2734829.62      6735253.50      2734765.57      6735212.37
      2734636.44      6735212.04      2734524.53      6735307.44
      2734381.65      6735312.98      2734336.32      6735350.82
      2734322.45      6735559.53      2734226.65      6735671.64
      2734268.41      6735760.99      2734228.46      6735816.86
      2734224.80      6736000.50      2734170.29      6736113.58
      2734124.72      6736157.47      2734023.58      6736166.54
      2733924.50      6736257.37      2733823.56      6736266.52
      2733733.80      6736354.79      2733722.25      6736559.45
      2733629.83      6736712.58      2733622.17      6736809.42
      2733478.55      6737055.28      2733332.04      6737109.39
      2733156.02      6736960.96      2732746.03      6736961.09
      2732632.04      6737009.37      2732452.49      6736888.01
      2732332.55      6736718.60      2732226.00      6736711.00

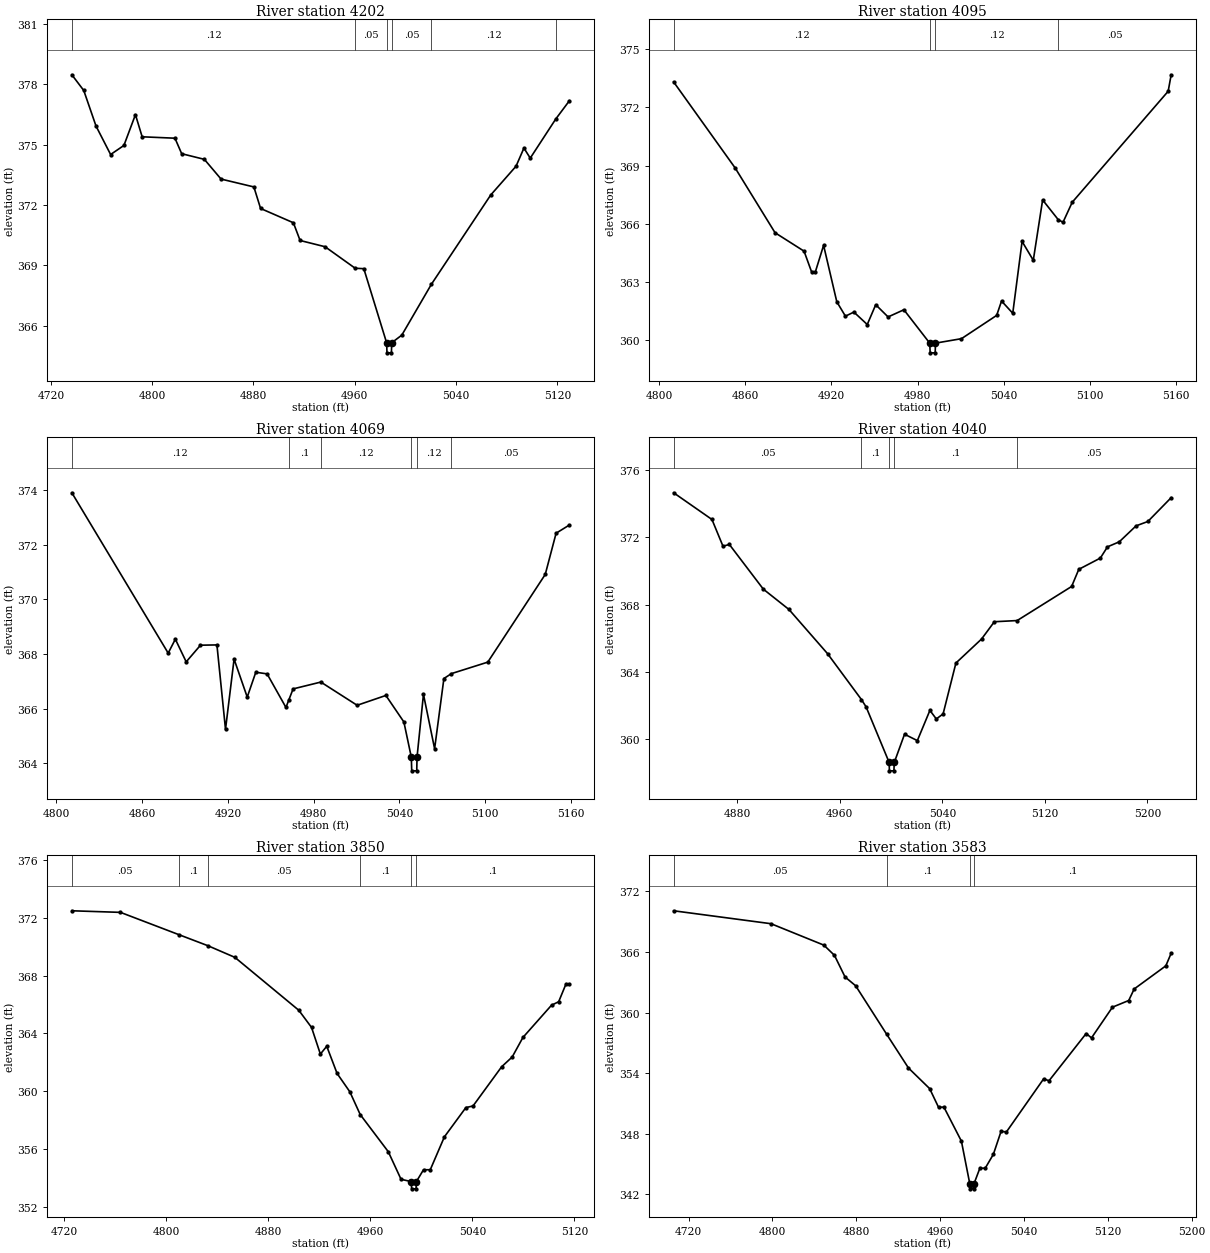
Type RM Length L Ch R = 1,4202,107,107,107
BEGIN DESCRIPTION:
Walnut83 11.0
END DESCRIPTION:
XS GIS Cut Line= 3
      2734898.66      6735002.12      2734829.91      6735200.82
      2734818.90      6735383.03
#Sta/Elev= 30
  4736.6  378.47  4746.0  377.69  4755.7  375.92  4767.2  374.51  4777.7  374.96
  4786.8  376.49  4792.1  375.39  4818.0  375.32  4823.3  374.55  4841.2  374.27
  4854.4  373.29  4880.3  372.90  4885.6  371.83  4911.5  371.12  4916.8  370.24
  4936.5  369.93  4960.3  368.86  4967.1  368.84  4985.1  365.16  4985.4  364.66
  4988.9  364.66  4989.1  365.16  4997.1  365.54  5020.5  368.07  5067.3  372.50
  5087.3  373.93  5093.5  374.83  5098.5  374.33  5118.6  376.27  5129.4  377.18
#Mann=6,-1,0
  4736.6    0.12       0  4960.3    0.05       0  4985.1    0.04       0
  4989.1    0.05       0  5020.5    0.12       0  5118.6    0.05       0
Bank Sta=4985.1,4989.1
Exp/Cntr=0.3,0.1

Type RM Length L Ch R = 1,4095,26,26,26
BEGIN DESCRIPTION:
Walnut83 10.7
END DESCRIPTION:
XS GIS Cut Line= 6
      2734776.29      6735030.99      2734763.68      6735126.43
      2734731.68      6735175.98      2734736.41      6735245.51
      2734772.55      6735275.84      2734791.64      6735347.62
#Sta/Elev= 30
  4810.1  373.31  4853.0  368.87  4880.7  365.54  4900.9  364.59  4906.1  363.53
  4908.8  363.53  4914.5  364.89  4923.7  361.98  4929.7  361.24  4935.6  361.45
  4944.9  360.81  4950.8  361.83  4959.4  361.20  4970.4  361.57  4988.4  359.85
  4988.7  359.35  4992.2  359.35  4992.4  359.85  5010.5  360.08  5035.0  361.28
  5038.4  362.02  5046.2  361.39  5052.7  365.09  5060.5  364.12  5067.0  367.23
  5077.9  366.21  5081.2  366.08  5087.6  367.11  5154.4  372.83  5156.5  373.68
#Mann=4,-1,0
  4810.1    0.12       0  4988.4    0.07       0  4992.4    0.12       0
  5077.9    0.05       0
Bank Sta=4988.4,4992.4
Exp/Cntr=0.3,0.1

Type RM Length L Ch R = 1,4069,29,29,29
BEGIN DESCRIPTION:
Walnut83 10.6
END DESCRIPTION:
XS GIS Cut Line= 6
      2734750.16      6735031.73      2734737.55      6735127.12
      2734705.55      6735176.66      2734710.29      6735246.20
      2734746.43      6735276.53      2734765.97      6735350.00
#Sta/Elev= 30
  4810.8  373.90  4878.2  368.03  4883.2  368.54  4890.8  367.71  4900.8  368.32
  4912.3  368.33  4918.3  365.24  4924.3  367.81  4933.5  366.42  4939.5  367.33
  4947.4  367.27  4960.6  366.04  4962.7  366.33  4965.6  366.72  4985.0  366.97
  5010.4  366.12  5030.5  366.48  5043.1  365.51  5048.3  364.22  5048.6  363.72
  5052.1  363.72  5052.3  364.22  5056.8  366.52  5064.6  364.53  5071.1  367.10
  5076.4  367.28  5101.8  367.70  5142.0  370.91  5149.6  372.42  5158.9  372.72
#Mann=6,-1,0
  4810.8    0.12       0  4962.7     0.1       0  4985.0    0.12       0
  5048.3    0.07       0  5052.3    0.12       0  5076.4    0.05       0
Bank Sta=5048.3,5052.3
Exp/Cntr=0.3,0.1

Type RM Length L Ch R = 1,4040,190,190,190
BEGIN DESCRIPTION:
Walnut83 10.5
END DESCRIPTION:
XS GIS Cut Line= 3
      2734668.42      6735041.13      2734685.49      6735318.56
      2734734.84      6735417.25
#Sta/Elev= 30
  4830.3  374.66  4860.2  373.07  4868.8  371.48  4873.8  371.58  4900.3  368.92
  4920.3  367.71  4950.4  365.08  4976.9  362.34  4980.5  361.91  4998.5  358.60
  4998.7  358.10  5002.2  358.10  5002.5  358.60  5010.5  360.28  5020.5  359.90
  5030.3  361.70  5035.3  361.19  5040.6  361.49  5050.6  364.52  5070.6  365.95
  5080.6  366.98  5098.4  367.05  5140.9  369.08  5146.5  370.10  5163.3  370.77
  5168.9  371.44  5178.1  371.74  5191.2  372.69  5200.4  372.95  5218.6  374.37
#Mann=5,-1,0
  4830.3    0.05       0  4976.9     0.1       0  4998.5    0.07       0
  5002.5     0.1       0  5098.4    0.05       0
Bank Sta=4998.5,5002.5
Exp/Cntr=0.3,0.1

Type RM Length L Ch R = 1,3850,267,267,267
BEGIN DESCRIPTION:
Walnut83 10.0
END DESCRIPTION:
XS GIS Cut Line= 3
      2734508.93      6735033.56      2734526.00      6735311.00
      2734576.02      6735411.03
#Sta/Elev= 30
  4726.2  372.48  4764.3  372.37  4810.0  370.83  4832.9  370.06  4853.9  369.26
  4904.0  365.60  4914.0  364.41  4920.9  362.57  4925.9  363.11  4934.0  361.23
  4944.0  359.96  4952.1  358.39  4974.1  355.82  4984.1  353.91  4992.1  353.75
  4992.4  353.25  4995.9  353.25  4996.1  353.75  5001.7  354.57  5007.0  354.57
  5018.1  356.85  5034.9  358.87  5040.5  358.98  5062.9  361.69  5071.2  362.37
  5079.6  363.72  5102.0  365.95  5107.6  366.19  5113.2  367.39  5116.0  367.39
#Mann=6,-1,0
  4726.2    0.05       0  4810.0     0.1       0  4832.9    0.05       0
  4952.1     0.1       0  4992.1    0.07       0  4996.1     0.1       0
Bank Sta=4992.1,4996.1
Exp/Cntr=0.3,0.1

Type RM Length L Ch R = 1,3583,197,197,197
BEGIN DESCRIPTION:
Walnut83 9.0
END DESCRIPTION:
XS GIS Cut Line= 3
      2734033.87      6735372.68      2734326.00      6735411.00
      2734500.20      6735456.19
#Sta/Elev= 30
  4705.8  370.08  4798.7  368.80  4849.1  366.68  4859.2  365.67  4869.3  363.53
  4879.4  362.66  4909.0  357.86  4929.8  354.52  4950.0  352.48  4958.5  350.63
  4963.6  350.65  4980.3  347.28  4988.3  343.06  4988.6  342.56  4992.1  342.56
  4992.3  343.06  4997.9  344.60  5003.0  344.60  5010.8  345.98  5018.1  348.24
  5023.3  348.20  5058.7  353.44  5063.9  353.26  5099.3  357.93  5104.4  357.50
  5124.4  360.54  5139.9  361.20  5145.1  362.34  5175.3  364.63  5180.4  365.88
#Mann=4,-1,0
  4705.8    0.05       0  4909.0     0.1       0  4988.3    0.07       0
  4992.3     0.1       0
Bank Sta=4988.3,4992.3
Exp/Cntr=0.3,0.1

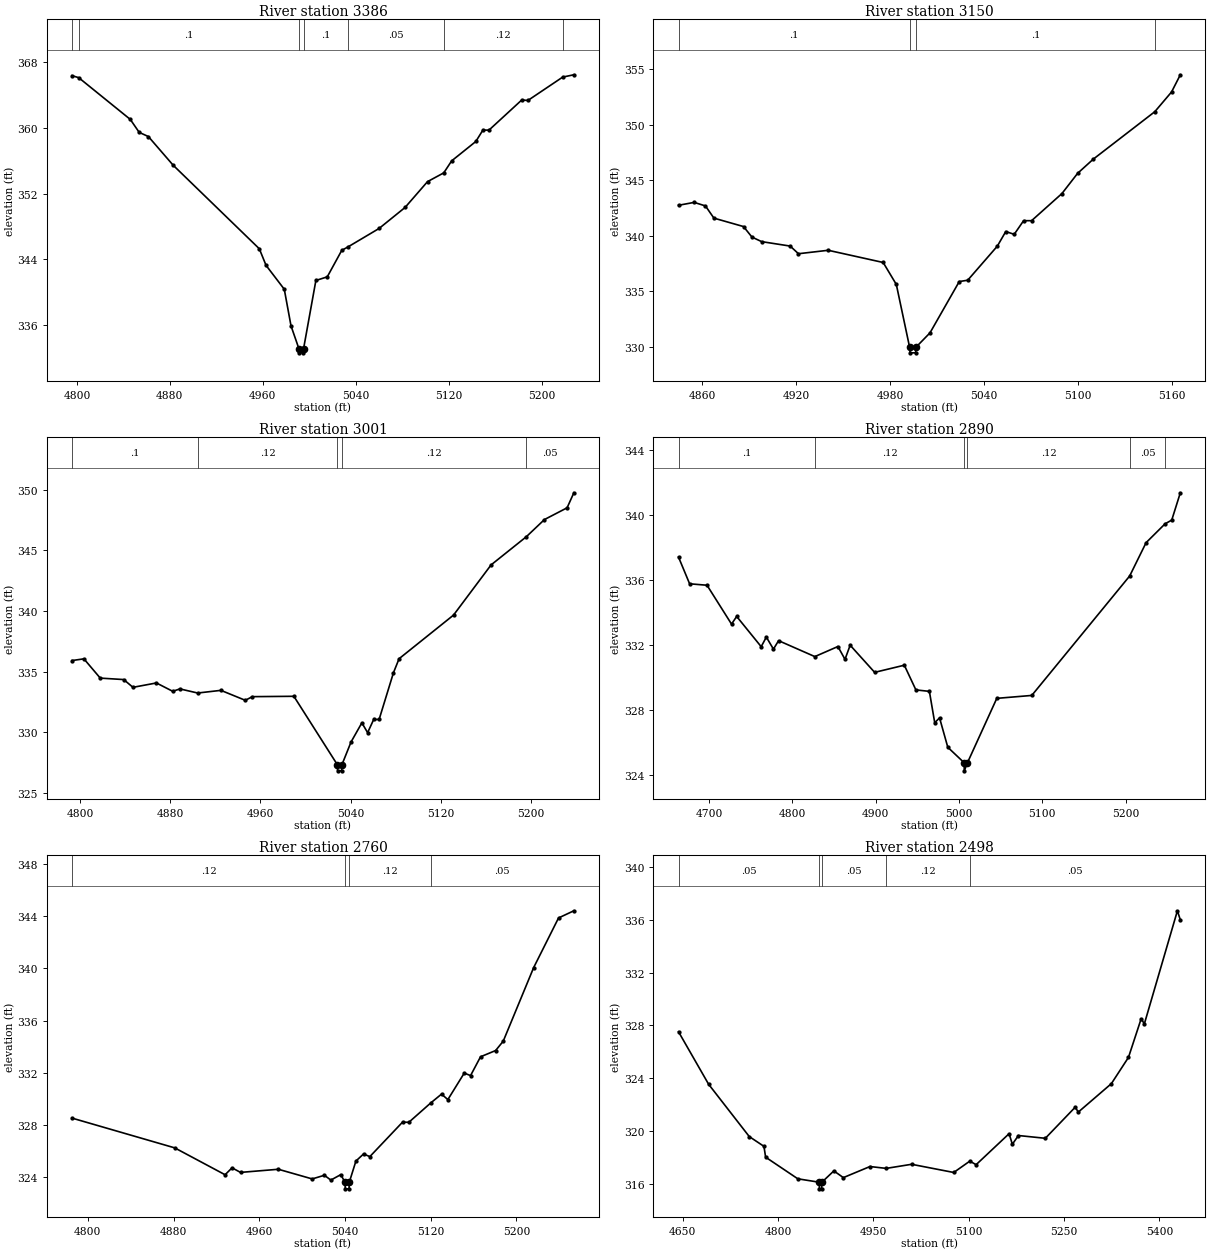
Type RM Length L Ch R = 1,3386,236,236,236
BEGIN DESCRIPTION:
Walnut83 8.5
END DESCRIPTION:
XS GIS Cut Line= 3
      2734116.24      6735491.46      2734323.11      6735614.05
      2734506.98      6735667.68
#Sta/Elev= 30
  4795.8  366.37  4801.5  366.13  4845.9  361.05  4853.6  359.47  4861.5  358.96
  4882.9  355.46  4957.0  345.30  4962.8  343.28  4978.5  340.37  4984.3  335.91
  4991.1  333.13  4991.4  332.63  4994.9  332.63  4995.1  333.13  5005.7  341.44
  5015.5  341.88  5028.0  345.11  5033.4  345.53  5060.1  347.77  5082.5  350.33
  5101.8  353.47  5115.8  354.54  5122.6  356.00  5143.4  358.36  5149.5  359.75
  5154.7  359.74  5183.0  363.42  5188.2  363.35  5218.2  366.20  5227.8  366.48
#Mann=7,-1,0
  4795.8    0.05       0  4801.5     0.1       0  4991.1    0.07       0
  4995.1     0.1       0  5033.4    0.05       0  5115.8    0.12       0
  5218.2    0.05       0
Bank Sta=4991.1,4995.1
Exp/Cntr=0.3,0.1

Type RM Length L Ch R = 1,3150,149,149,149
BEGIN DESCRIPTION:
Walnut83 8.0
END DESCRIPTION:
XS GIS Cut Line= 3
      2734106.67      6735729.00      2734312.21      6735810.42
      2734411.63      6735810.42
#Sta/Elev= 30
  4844.7  342.75  4854.7  343.01  4861.9  342.69  4867.3  341.59  4886.2  340.83
  4891.6  339.88  4897.8  339.47  4916.0  339.07  4921.3  338.38  4940.3  338.69
  4975.4  337.59  4983.8  335.61  4992.3  329.94  4992.6  329.44  4996.1  329.44
  4996.3  329.94  5005.3  331.24  5024.0  335.87  5029.4  335.99  5048.3  339.06
  5053.7  340.38  5059.1  340.13  5065.1  341.36  5070.2  341.36  5089.6  343.81
  5099.6  345.63  5109.6  346.91  5148.9  351.19  5159.6  352.97  5165.2  354.52
#Mann=4,-1,0
  4844.7     0.1       0  4992.3    0.07       0  4996.3     0.1       0
  5148.9    0.12       0
Bank Sta=4992.3,4996.3
Exp/Cntr=0.3,0.1

Type RM Length L Ch R = 1,3001,111,111,111
BEGIN DESCRIPTION:
Walnut83 7.8
END DESCRIPTION:
XS GIS Cut Line= 4
      2734085.58      6735786.48      2734189.01      6735920.56
      2734290.55      6735937.80      2734461.94      6735916.85
#Sta/Elev= 30
  4793.0  335.92  4803.5  336.06  4818.0  334.47  4838.8  334.35  4847.0  333.71
  4867.8  334.07  4882.3  333.38  4888.6  333.58  4904.4  333.24  4925.0  333.46
  4946.6  332.64  4952.9  332.94  4989.7  332.97  5028.3  327.32  5028.5  326.82
  5032.0  326.82  5032.3  327.32  5040.4  329.20  5050.0  330.78  5055.1  329.97
  5060.5  331.06  5065.3  331.06  5078.0  334.91  5083.0  336.07  5131.3  339.67
  5164.6  343.81  5195.8  346.13  5211.9  347.55  5232.0  348.52  5238.0  349.76
#Mann=5,-1,0
  4793.0     0.1       0  4904.4    0.12       0  5028.3    0.07       0
  5032.3    0.12       0  5195.8    0.05       0
Bank Sta=5028.3,5032.3
Exp/Cntr=0.3,0.1

Type RM Length L Ch R = 1,2890,130,130,130
BEGIN DESCRIPTION:
Walnut83 7.6
END DESCRIPTION:
XS GIS Cut Line= 4
      2734012.79      6735755.83      2734180.01      6735988.08
      2734233.08      6736079.56      2734412.09      6736190.02
#Sta/Elev= 30
  4663.4  337.43  4676.7  335.79  4697.6  335.70  4727.0  333.31  4733.2  333.78
  4762.6  331.92  4768.8  332.51  4777.3  331.77  4783.5  332.29  4827.0  331.31
  4854.7  331.93  4863.2  331.14  4869.4  332.01  4898.8  330.34  4934.4  330.78
  4948.3  329.26  4964.5  329.17  4970.9  327.24  4976.7  327.54  4986.6  325.73
  5006.2  324.78  5006.4  324.28  5010.2  324.78  5045.4  328.74  5087.4  328.92
  5204.9  336.27  5224.6  338.32  5247.4  339.48  5255.4  339.71  5265.7  341.39
#Mann=6,-1,0
  4663.4     0.1       0  4827.0    0.12       0  5006.2    0.07       0
  5010.2    0.12       0  5204.9    0.05       0  5247.4    0.12       0
Bank Sta=5006.2,5010.2
Exp/Cntr=0.3,0.1

Type RM Length L Ch R = 1,2760,262,262,262
BEGIN DESCRIPTION:
Walnut83 7.3
END DESCRIPTION:
XS GIS Cut Line= 4
      2734070.02      6735950.23      2734083.23      6736064.06
      2734152.62      6736150.44      2734357.63      6736280.73
#Sta/Elev= 30
  4785.3  328.52  4881.1  326.24  4928.1  324.18  4934.6  324.71  4942.5  324.36
  4977.8  324.60  5009.4  323.86  5020.8  324.14  5026.8  323.77  5036.1  324.19
  5040.0  323.60  5040.3  323.10  5043.8  323.10  5044.0  323.60  5050.2  325.23
  5057.3  325.77  5063.2  325.57  5093.7  328.21  5099.6  328.20  5120.0  329.68
  5130.1  330.36  5136.0  329.94  5151.3  331.97  5157.2  331.78  5166.5  333.22
  5180.6  333.70  5187.7  334.42  5216.1  340.06  5239.3  343.86  5253.6  344.41
#Mann=4,-1,0
  4785.3    0.12       0  5040.0    0.07       0  5044.0    0.12       0
  5120.0    0.05       0
Bank Sta=5040,5044
Exp/Cntr=0.3,0.1

Type RM Length L Ch R = 1,2498,270,270,270
BEGIN DESCRIPTION:
Walnut83 7.0
END DESCRIPTION:
XS GIS Cut Line= 4
      2733760.14      6735945.61      2733798.08      6736072.12
      2733960.49      6736306.45      2734326.10      6736376.76
#Sta/Elev= 30
  4643.4  327.52  4690.8  323.54  4754.7  319.58  4777.8  318.84  4780.4  318.02
  4831.1  316.38  4864.9  316.12  4865.1  315.62  4868.6  315.62  4868.9  316.12
  4887.8  316.98  4902.7  316.47  4944.6  317.31  4970.2  317.17  5010.1  317.48
  5076.4  316.86  5101.7  317.72  5111.6  317.45  5163.5  319.80  5168.6  319.00
  5178.2  319.66  5220.5  319.45  5267.4  321.80  5272.5  321.44  5324.4  323.59
  5351.3  325.58  5371.3  328.51  5376.3  328.12  5428.3  336.69  5432.9  336.00
#Mann=5,-1,0
  4643.4    0.05       0  4864.9    0.07       0  4868.9    0.05       0
  4970.2    0.12       0  5101.7    0.05       0
Bank Sta=4864.9,4868.9
Exp/Cntr=0.3,0.1

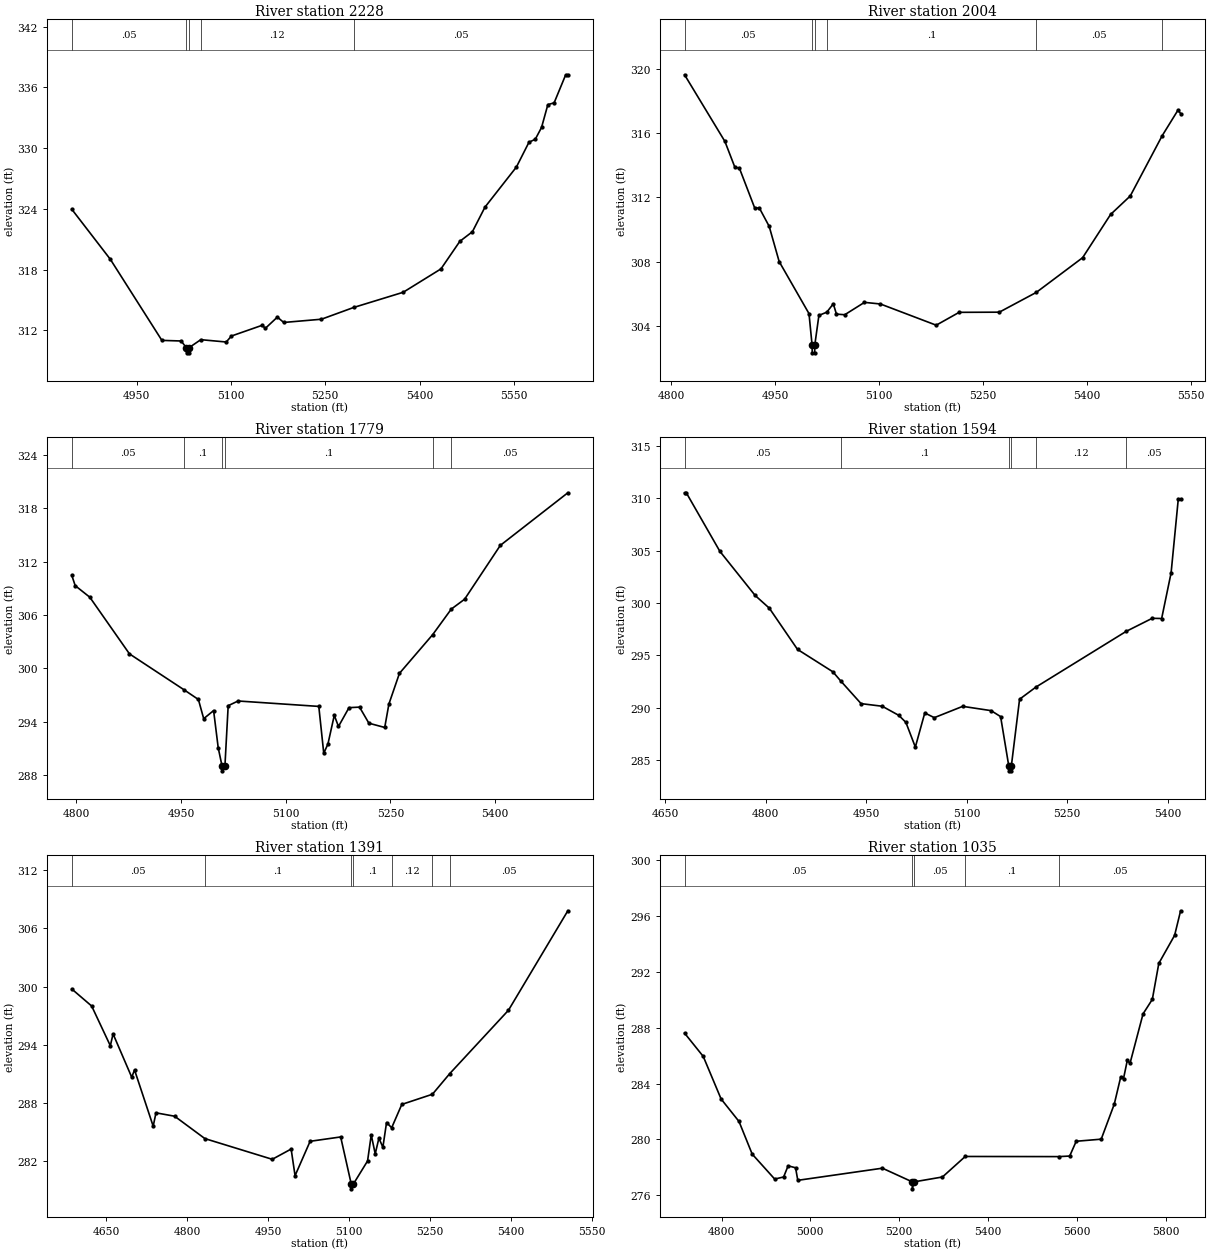
Type RM Length L Ch R = 1,2228,224,224,224
BEGIN DESCRIPTION:
Walnut83 6.0
END DESCRIPTION:
XS GIS Cut Line= 3
      2733576.00      6736361.00      2733872.59      6736426.00
      2734357.76      6736440.06
#Sta/Elev= 30
  4846.9  323.96  4908.3  319.01  4990.2  311.01  5020.9  310.95  5029.2  310.28
  5029.4  309.78  5032.9  309.78  5033.2  310.28  5052.1  311.08  5092.6  310.85
  5100.8  311.44  5149.7  312.50  5154.8  312.20  5173.9  313.31  5184.0  312.78
  5244.0  313.10  5295.2  314.26  5374.0  315.76  5434.1  318.07  5464.1  320.79
  5484.1  321.74  5504.1  324.17  5554.1  328.13  5574.1  330.58  5584.1  330.87
  5594.1  332.04  5604.1  334.29  5614.1  334.47  5632.5  337.24  5635.9  337.24
#Mann=5,-1,0
  4846.9    0.05       0  5029.2    0.04       0  5033.2    0.05       0
  5052.1    0.12       0  5295.2    0.05       0
Bank Sta=5029.2,5033.2
Exp/Cntr=0.3,0.1

Type RM Length L Ch R = 1,2004,225,225,225
BEGIN DESCRIPTION:
Walnut83 5.5
END DESCRIPTION:
XS GIS Cut Line= 3
      2733545.62      6736489.29      2733717.89      6736629.92
      2734166.45      6736836.68
#Sta/Elev= 30
  4819.3  319.63  4877.6  315.48  4892.0  313.87  4898.4  313.83  4920.7  311.33
  4927.2  311.35  4941.5  310.20  4955.9  308.01  4999.0  304.77  5003.4  302.83
  5003.7  302.33  5007.2  302.33  5007.4  302.83  5013.3  304.66  5024.7  304.86
  5034.1  305.38  5038.6  304.74  5050.6  304.70  5079.1  305.47  5102.1  305.37
  5182.7  304.05  5215.8  304.85  5273.8  304.86  5327.2  306.09  5394.1  308.25
  5434.5  310.94  5462.9  312.09  5509.0  315.84  5531.8  317.43  5535.6  317.22
#Mann=6,-1,0
  4819.3    0.05       0  5003.4    0.04       0  5007.4    0.05       0
  5024.7     0.1       0  5327.2    0.05       0  5509.0    0.12       0
Bank Sta=5003.4,5007.4
Exp/Cntr=0.3,0.1

Type RM Length L Ch R = 1,1779,185,185,185
BEGIN DESCRIPTION:
Walnut83 5.0
END DESCRIPTION:
XS GIS Cut Line= 3
      2733485.84      6736654.53      2733654.60      6736847.90
      2734034.33      6737097.54
#Sta/Elev= 30
  4793.3  310.46  4798.2  309.30  4819.1  308.00  4876.0  301.62  4954.8  297.55
  4974.8  296.49  4982.4  294.33  4996.6  295.24  5003.2  291.06  5008.8  288.96
  5009.1  288.46  5012.8  288.96  5017.5  295.79  5031.7  296.32  5147.4  295.71
  5154.5  290.44  5160.5  291.48  5169.6  294.71  5175.6  293.45  5190.7  295.57
  5205.8  295.63  5219.2  293.82  5241.9  293.34  5247.9  295.98  5263.0  299.43
  5310.7  303.79  5337.3  306.66  5356.4  307.77  5407.6  313.83  5504.4  319.75
#Mann=6,-1,0
  4793.3    0.05       0  4954.8     0.1       0  5008.8    0.07       0
  5012.8     0.1       0  5310.7    0.12       0  5337.3    0.05       0
Bank Sta=5008.8,5012.8
Exp/Cntr=0.3,0.1

Type RM Length L Ch R = 1,1594,203,203,203
BEGIN DESCRIPTION:
Walnut83 4.0
END DESCRIPTION:
XS GIS Cut Line= 3
      2733426.00      6736661.01      2733526.00      6736961.00
      2733826.01      6737261.01
#Sta/Elev= 30
  4678.7  310.52  4681.3  310.52  4731.4  304.93  4784.1  300.71  4805.2  299.50
  4847.3  295.56  4900.1  293.42  4911.9  292.54  4942.2  290.38  4973.8  290.13
  4998.5  289.26  5009.1  288.59  5023.2  286.23  5037.3  289.49  5051.5  289.04
  5093.9  290.12  5136.3  289.71  5150.5  289.14  5162.6  284.46  5162.9  283.96
  5166.4  283.96  5166.6  284.46  5178.8  290.80  5203.2  291.96  5337.9  297.28
  5376.8  298.53  5390.9  298.51  5405.0  302.87  5415.7  309.91  5419.2  309.91
#Mann=6,-1,0
  4678.7    0.05       0  4911.9     0.1       0  5162.6    0.07       0
  5166.6     0.1       0  5203.2    0.12       0  5337.9    0.05       0
Bank Sta=5162.6,5166.6
Exp/Cntr=0.3,0.1

Type RM Length L Ch R = 1,1391,356,356,356
BEGIN DESCRIPTION:
Walnut83 3.0
END DESCRIPTION:
XS GIS Cut Line= 3
      2733271.38      6736700.26      2733369.82      6737062.38
      2733739.00      6737463.21
#Sta/Elev= 30
  4585.9  299.75  4622.8  297.99  4657.4  293.89  4662.5  295.11  4697.1  290.64
  4702.3  291.39  4736.9  285.58  4742.1  286.96  4776.7  286.61  4832.8  284.30
  4957.8  282.16  4992.8  283.22  5000.1  280.47  5028.0  284.02  5084.7  284.47
  5104.3  279.61  5104.5  279.11  5108.3  279.61  5134.6  281.99  5141.4  284.68
  5148.8  282.72  5155.6  284.34  5163.0  283.41  5169.8  285.96  5179.3  285.42
  5198.1  287.83  5254.9  288.88  5287.2  291.02  5396.0  297.56  5506.1  307.83
#Mann=7,-1,0
  4585.9    0.05       0  4832.8     0.1       0  5104.3    0.07       0
  5108.3     0.1       0  5179.3    0.12       0  5254.9     0.1       0
  5287.2    0.05       0
Bank Sta=5104.3,5108.3
Exp/Cntr=0.3,0.1

Type RM Length L Ch R = 1,1035,436,436,436
BEGIN DESCRIPTION:
Walnut83 2.0
END DESCRIPTION:
XS GIS Cut Line= 3
      2733074.48      6736679.11      2733130.73      6737210.04
      2733601.47      6737554.31
#Sta/Elev= 30
  4716.8  287.61  4758.9  285.94  4799.1  282.89  4839.4  281.28  4869.1  278.94
  4919.8  277.15  4939.9  277.30  4950.0  278.10  4966.8  277.96  4971.8  277.06
  5162.3  277.93  5229.6  276.95  5229.8  276.45  5233.6  276.95  5297.6  277.30
  5348.9  278.77  5559.3  278.76  5584.1  278.80  5598.8  279.86  5655.1  280.01
  5684.5  282.52  5699.1  284.48  5705.3  284.35  5713.8  285.65  5720.0  285.45
  5749.3  288.99  5770.2  290.03  5784.8  292.61  5820.4  294.62  5833.9  296.38
#Mann=5,-1,0
  4716.8    0.05       0  5229.6    0.04       0  5233.6    0.05       0
  5348.9     0.1       0  5559.3    0.05       0
Bank Sta=5229.6,5233.6
Exp/Cntr=0.3,0.1

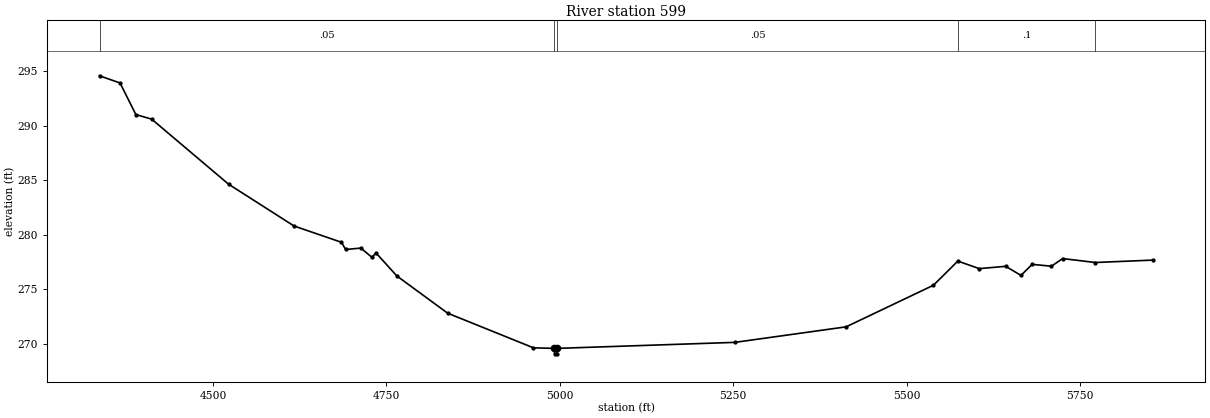
Type RM Length L Ch R = 1,599,0,0,0
BEGIN DESCRIPTION:
Walnut83 1.0
END DESCRIPTION:
XS GIS Cut Line= 4
      2732941.49      6736415.01      2732659.34      6736930.75
      2732707.90      6737083.38      2733387.34      6737446.22
#Sta/Elev= 30
  4336.4  294.56  4366.0  293.90  4388.8  291.01  4411.6  290.59  4522.4  284.64
  4616.8  280.81  4685.2  279.32  4691.2  278.66  4713.1  278.79  4729.2  277.94
  4734.9  278.35  4765.0  276.24  4838.3  272.83  4962.0  269.66  4992.2  269.61
  4992.5  269.11  4996.0  269.11  4996.2  269.61  5252.3  270.16  5412.6  271.58
  5538.6  275.39  5573.7  277.60  5604.5  276.91  5642.7  277.12  5664.7  276.29
  5680.9  277.30  5708.6  277.13  5724.8  277.83  5771.9  277.47  5854.7  277.69
#Mann=5,-1,0
  4336.4    0.05       0  4992.2    0.04       0  4996.2    0.05       0
  5573.7     0.1       0  5771.9    0.05       0
Bank Sta=4992.2,4996.2
Exp/Cntr=0.3,0.1

Chan Stop Cuts=-1