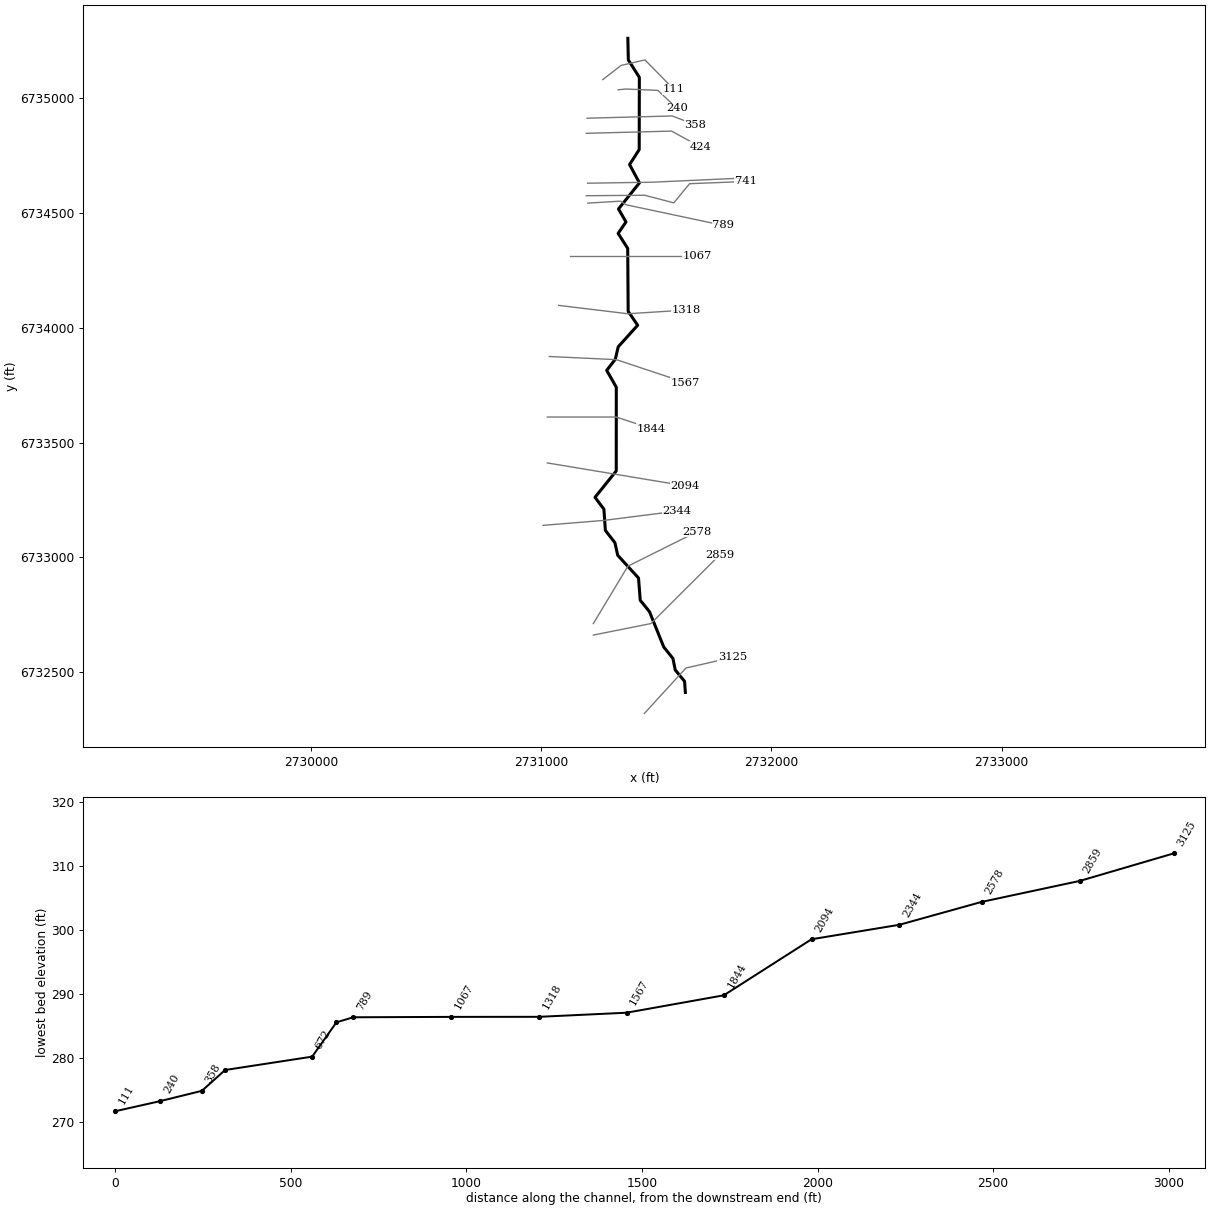
--- Walnut84.prj (project) ---

Proj Title=Walnut84 Base Level Engineering
Current Plan=p01
Default Exp/Contr=0.3,0.1
English Units
Geom File=g01
Flow File=f01
Plan File=p01
Y Axis Title=Elevation
X Axis Title(PF)=Main Channel Distance
X Axis Title(XS)=Station
BEGIN DESCRIPTION:
Walnut84
END DESCRIPTION:
DSS Export Rating Curves= 0
DSS Export Rating Curve Sorted= 0
DSS Export Volume Flow Curves= 0
DXF OffsetX= 0
DXF OffsetY= 0
DXF ScaleX= 1
DXF ScaleY= 10

--- Walnut84.p01 (plan) ---

Plan Title=Multiple Run
Program Version=4.10
Short Identifier=Multiple
Geom File=g01
Flow File=f01
Subcritical Flow
K Sum by GR= 0
Std Step Tol= 0.01
Critical Tol= 0.01
Num of Std Step Trials= 20
Max Error Tol= 0.3
Flow Tol Ratio= 0.001
Split Flow NTrial= 30
Split Flow Tol= 0.02
Split Flow Ratio= 0.02
Log Output Level= 0
Friction Slope Method= 1
Unsteady Friction Slope Method= 2
Unsteady Bridges Friction Slope Method= 1
Parabolic Critical Depth
Global Vel Dist= 1 , 1 , 1
Global Log Level= 0
CheckData=True
Encroach Param=-1 ,0,0, 0
BEGIN DESCRIPTION:
Multiple Run
END DESCRIPTION:
Computation Interval=1HOUR
Output Interval=1HOUR
Run HTab= 0
Run UNet= 0
Run PostProcess= 0
Run WQNet= 0
UNET Theta= 1
UNET Theta Warmup= 1
UNET ZTol= 0.02
UNET ZSATol= 0.05
UNET MxIter= 20
UNET MaxInSteps= 0
UNET DtIC= 0
UNET DtMin= 0
UNET MaxCRTS= 20
UNET WFStab= 2
UNET SFStab= 1
UNET WFX= 1
UNET SFX= 1
UNET DSS MLevel= 4
UNET DZMax Abort= 100
UNET Convert EG Bridges= 0
UNET Use Existing IB Tables=-1
UNET Froude Reduction=False
UNET Froude Limit= 1
UNET Froude Power= 10
UNET Time Slicing=0,0, 5
UNET Junction Losses=0
Instantaneous Interval=1HOUR
Write IC File= 0
Write IC File at Sim End=0
Echo Input=False
Echo Parameters=False
Echo Output=False
Write Detailed= 0
WQ AD Non Conservative
WQ ULTIMATE=-1
WQ Max Comp Step=1HOUR
WQ Output Interval=15MIN
WQ Output Selected Increments= 0
WQ Output face flow=0
WQ Output face velocity=0
WQ Output face area=0
WQ Output face dispersion=0
WQ Output cell volume=0
WQ Output cell surface area=0
WQ Output cell continuity=0
WQ Output cumulative cell continuity=0
WQ Output face conc=0
WQ Output face dconc_dx=0
WQ Output face courant=0
WQ Output face peclet=0
WQ Output face adv mass=0
WQ Output face disp mass=0
WQ Output cell mass=0
WQ Output cell source sink temp=0
WQ Output cell source sink nsm=0
WQ Output MaxMinRange=-1
WQ Daily Max Min Mean=-1
WQ Daily Range=0
WQ Daily Time=0
WQ Create Restart=0
WQ Fixed Restart=0
WQ System Summary=0
WQ Use Fixed Temperature=0
Sorting and Armoring Iterations= 10
XS Update Threshold= 0.02
Hydraulics Update Threshold= 0.02
Energy Slope Method= 1
Volume Change Method= 0
XS Weighting Method= 0
Number of US Weighted Cross Sections= 1
Number of DS Weighted Cross Sections= 1
Upstream XS Weight=0.25
Main XS Weight=0.5
Downstream XS Weight=0.25
Number of DS XS's Weighted with US Boundary= 1
Upstream Boundary Weight= 1
Weight of XSs Associated with US Boundary= 0
Number of US XS's Weighted with DS Boundary= 1
Downstream Boundary Weight= 0.5
Weight of XSs Associated with DS Boundary= 0.5
Sediment Output Level= 4
Mass or Volume Output= 0
Output Increment Type= 1
Profile and TS Output Increment= 10
XS Output Flag= 0
XS Output Increment= 10
Disregard all LS=0
Disregard all Conn=0
Disregard all Breaches=0
Disregard all Pumps=0

--- Walnut84.f01 (steady flow) ---

Flow Title=Multiple
Program Version=4.10
Number of Profiles= 7
Profile Names=10-year,25-year,50-year,1pct_min,100-year,1pct_plu,500-year
River Rch & RM=Walnut84,Reach-1         ,3125
     146     182     208     119     238     475     311
Boundary for River Rch & Prof#=Walnut84,Reach-1         , 1
Up Type= 0
Dn Type= 3
Dn Slope=0.012
Boundary for River Rch & Prof#=Walnut84,Reach-1         , 2
Up Type= 0
Dn Type= 3
Dn Slope=0.012
Boundary for River Rch & Prof#=Walnut84,Reach-1         , 3
Up Type= 0
Dn Type= 3
Dn Slope=0.012
Boundary for River Rch & Prof#=Walnut84,Reach-1         , 4
Up Type= 0
Dn Type= 3
Dn Slope=0.012
Boundary for River Rch & Prof#=Walnut84,Reach-1         , 5
Up Type= 0
Dn Type= 3
Dn Slope=0.012
Boundary for River Rch & Prof#=Walnut84,Reach-1         , 6
Up Type= 0
Dn Type= 3
Dn Slope=0.012
Boundary for River Rch & Prof#=Walnut84,Reach-1         , 7
Up Type= 0
Dn Type= 3
Dn Slope=0.012
DSS Import GetInterval= 0
DSS Import GetPeak= 0
DSS Import FillOption= 0

--- Walnut84.g01 (geometry) ---

Geom Title=Existing Conditions

River Reach=Walnut84,Reach-1
Reach XY= 30
      2731626.00      6732411.00      2731622.40      6732459.51
      2731581.95      6732508.75      2731571.86      6732559.28
      2731532.08      6732608.80      2731469.88      6732763.18
      2731429.83      6732812.59      2731422.38      6732909.50
      2731331.85      6733008.71      2731319.86      6733063.17
      2731278.33      6733116.97      2731271.90      6733209.50
      2731233.33      6733261.10      2731325.61      6733376.16
      2731325.82      6733741.02      2731284.04      6733814.32
      2731321.55      6733862.65      2731334.16      6733917.05
      2731418.67      6734010.90      2731377.39      6734071.43
      2731375.35      6734345.84      2731333.78      6734411.10
      2731367.96      6734461.00      2731335.31      6734517.66
      2731426.32      6734631.16      2731383.59      6734710.99
      2731425.34      6734776.16      2731425.94      6735090.97
      2731378.10      6735166.87      2731376.00      6735261.00

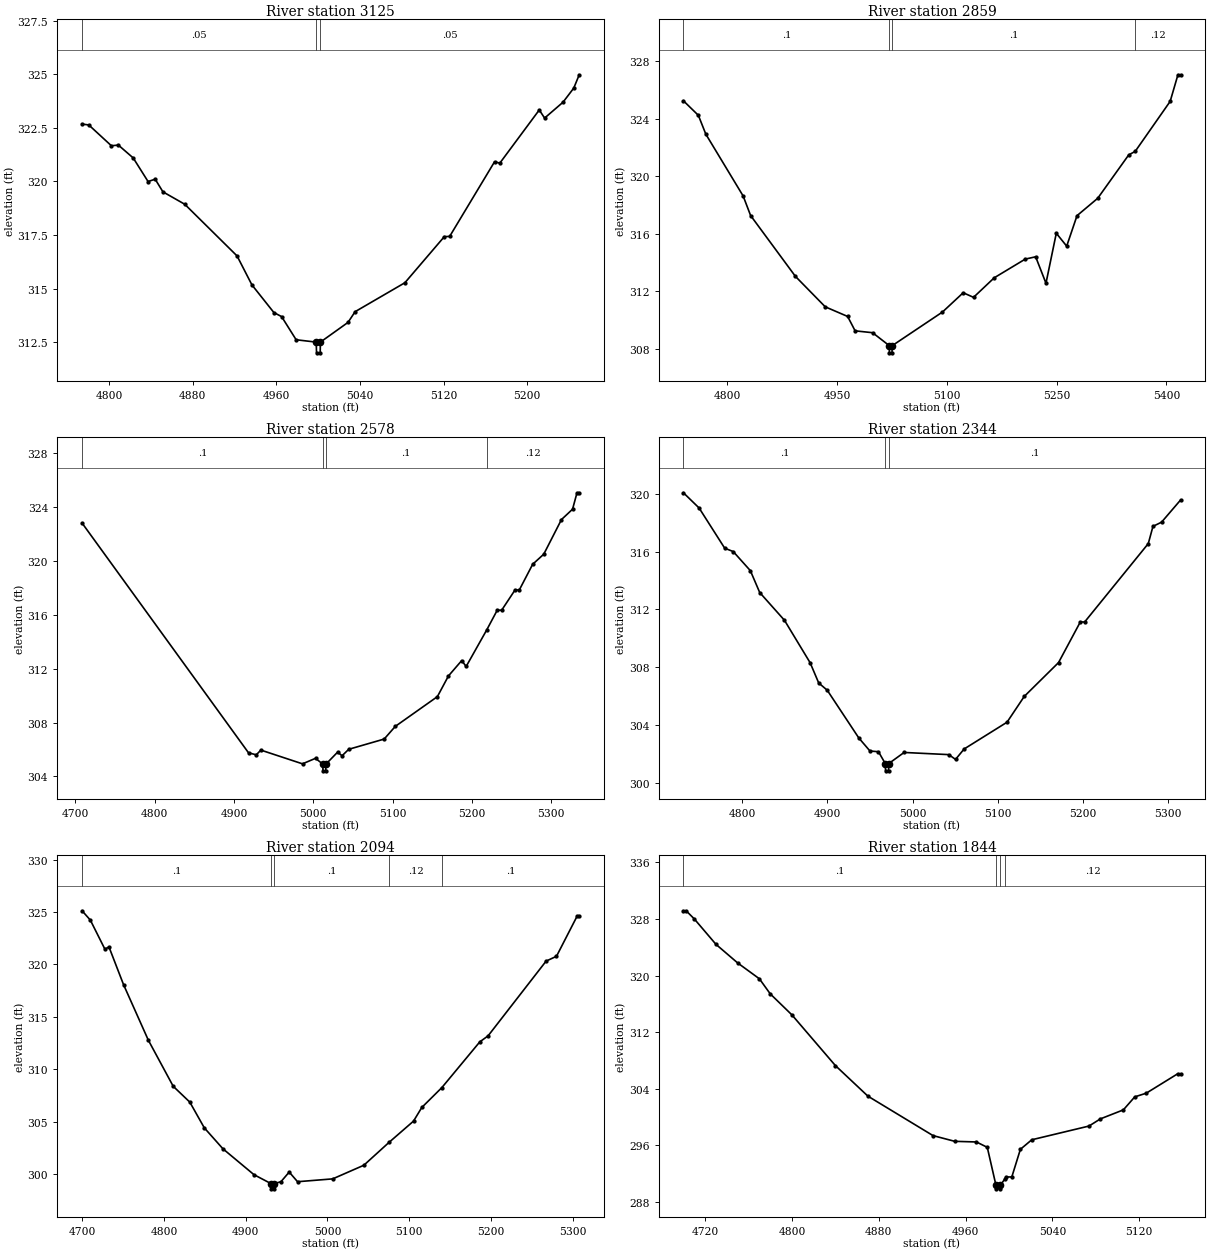
Type RM Length L Ch R = 1,3125,266,266,266
BEGIN DESCRIPTION:
Walnut84 12.0
END DESCRIPTION:
XS GIS Cut Line= 3
      2731448.13      6732319.76      2731628.29      6732517.28
      2731831.06      6732563.90
#Sta/Elev= 30
  4774.3  322.67  4780.7  322.63  4802.3  321.66  4809.0  321.69  4823.2  321.09
  4837.4  319.99  4844.2  320.10  4851.6  319.51  4872.5  318.93  4922.5  316.52
  4936.7  315.17  4957.7  313.88  4965.1  313.69  4979.0  312.61  4998.2  312.50
  4998.5  312.00  5002.0  312.00  5002.2  312.50  5028.6  313.42  5035.4  313.92
  5083.0  315.27  5120.7  317.42  5125.8  317.43  5168.7  320.91  5173.8  320.85
  5211.5  323.33  5216.6  322.95  5234.2  323.69  5244.5  324.35  5249.7  324.97
#Mann=3,-1,0
  4774.3    0.05       0  4998.2    0.04       0  5002.2    0.05       0
Bank Sta=4998.2,5002.2
Exp/Cntr=0.3,0.1

Type RM Length L Ch R = 1,2859,281,281,281
BEGIN DESCRIPTION:
Walnut84 11.0
END DESCRIPTION:
XS GIS Cut Line= 3
      2731225.96      6732660.99      2731476.00      6732711.00
      2731776.03      6733011.03
#Sta/Elev= 30
  4740.0  325.25  4760.4  324.24  4770.6  322.93  4821.6  318.63  4831.8  317.27
  4893.0  313.04  4933.8  310.92  4964.4  310.25  4974.6  309.25  4998.5  309.12
  5021.3  308.22  5021.5  307.72  5025.0  307.72  5025.3  308.22  5094.0  310.56
  5122.3  311.90  5136.4  311.58  5164.7  312.94  5207.1  314.24  5221.3  314.40
  5235.4  312.56  5249.5  316.04  5263.7  315.14  5277.8  317.26  5306.1  318.47
  5348.5  321.49  5357.3  321.73  5405.1  325.21  5415.7  327.06  5419.3  327.06
#Mann=4,-1,0
  4740.0     0.1       0  5021.3    0.07       0  5025.3     0.1       0
  5357.3    0.12       0
Bank Sta=5021.3,5025.3
Exp/Cntr=0.3,0.1

Type RM Length L Ch R = 1,2578,234,234,234
BEGIN DESCRIPTION:
Walnut84 10.0
END DESCRIPTION:
XS GIS Cut Line= 3
      2731225.99      6732710.98      2731376.00      6732961.00
      2731676.01      6733111.01
#Sta/Elev= 30
  4708.4  322.82  4918.3  305.76  4928.1  305.61  4933.9  305.96  4986.4  304.94
  5002.8  305.35  5012.0  304.92  5012.2  304.42  5015.7  304.42  5016.0  304.92
  5030.7  305.81  5036.3  305.54  5044.7  306.02  5089.4  306.78  5103.4  307.72
  5156.5  309.93  5170.5  311.47  5187.2  312.61  5192.8  312.17  5218.6  314.87
  5232.0  316.35  5237.6  316.35  5254.3  317.84  5259.9  317.86  5276.7  319.76
  5290.7  320.51  5313.0  323.08  5327.0  323.85  5332.6  325.07  5335.4  325.07
#Mann=4,-1,0
  4708.4     0.1       0  5012.0    0.07       0  5016.0     0.1       0
  5218.6    0.12       0
Bank Sta=5012,5016
Exp/Cntr=0.3,0.1

Type RM Length L Ch R = 1,2344,250,250,250
BEGIN DESCRIPTION:
Walnut84 9.0
END DESCRIPTION:
XS GIS Cut Line= 3
      2731007.66      6733139.02      2731276.00      6733161.00
      2731588.12      6733200.87
#Sta/Elev= 30
  4730.8  320.06  4749.2  319.01  4779.3  316.23  4789.3  316.00  4809.4  314.68
  4820.4  313.17  4849.5  311.25  4879.6  308.32  4889.7  306.92  4899.7  306.42
  4936.8  303.12  4949.9  302.22  4959.9  302.17  4967.9  301.35  4968.2  300.85
  4971.7  300.85  4971.9  301.35  4990.0  302.12  5042.5  301.97  5050.4  301.64
  5060.5  302.36  5110.9  304.21  5131.1  305.99  5171.4  308.33  5197.0  311.14
  5202.0  311.13  5276.8  316.55  5282.3  317.74  5292.4  318.03  5314.7  319.56
#Mann=3,-1,0
  4730.8     0.1       0  4967.9    0.07       0  4971.9     0.1       0
Bank Sta=4967.9,4971.9
Exp/Cntr=0.3,0.1

Type RM Length L Ch R = 1,2094,250,250,250
BEGIN DESCRIPTION:
Walnut84 8.0
END DESCRIPTION:
XS GIS Cut Line= 3
      2731026.03      6733411.00      2731326.00      6733361.00
      2731625.95      6733311.01
#Sta/Elev= 30
  4699.9  325.11  4710.0  324.22  4727.8  321.45  4732.8  321.66  4750.6  318.07
  4781.0  312.76  4811.4  308.37  4831.7  306.86  4849.4  304.41  4872.2  302.41
  4910.2  299.94  4931.0  299.09  4931.3  298.59  4934.8  298.59  4935.0  299.09
  4943.2  299.27  4953.3  300.19  4963.5  299.27  5006.5  299.54  5044.6  300.84
  5075.4  303.02  5105.4  305.05  5115.5  306.35  5140.1  308.25  5186.5  312.61
  5196.6  313.18  5267.6  320.31  5280.3  320.77  5305.6  324.61  5308.1  324.61
#Mann=5,-1,0
  4699.9     0.1       0  4931.0    0.07       0  4935.0     0.1       0
  5075.4    0.12       0  5140.1     0.1       0
Bank Sta=4931,4935
Exp/Cntr=0.3,0.1

Type RM Length L Ch R = 1,1844,277,277,277
BEGIN DESCRIPTION:
Walnut84 7.0
END DESCRIPTION:
XS GIS Cut Line= 3
      2731026.04      6733611.00      2731326.00      6733611.00
      2731476.02      6733560.99
#Sta/Elev= 30
  4700.0  329.16  4702.5  329.16  4710.0  328.01  4730.0  324.41  4750.0  321.78
  4770.0  319.54  4780.0  317.41  4800.0  314.43  4840.0  307.27  4870.0  302.94
  4930.0  297.36  4950.0  296.55  4970.0  296.46  4980.0  295.70  4988.0  290.33
  4988.2  289.83  4991.7  289.83  4992.0  290.33  4996.1  291.21  4997.5  291.51
  5002.6  291.51  5010.5  295.42  5021.0  296.77  5073.7  298.71  5084.3  299.73
  5105.4  301.00  5115.9  302.84  5126.5  303.36  5155.4  306.10  5158.1  306.10
#Mann=4,-1,0
  4700.0     0.1       0  4988.0    0.07       0  4992.0     0.1       0
  4996.1    0.12       0
Bank Sta=4988,4992
Exp/Cntr=0.3,0.1

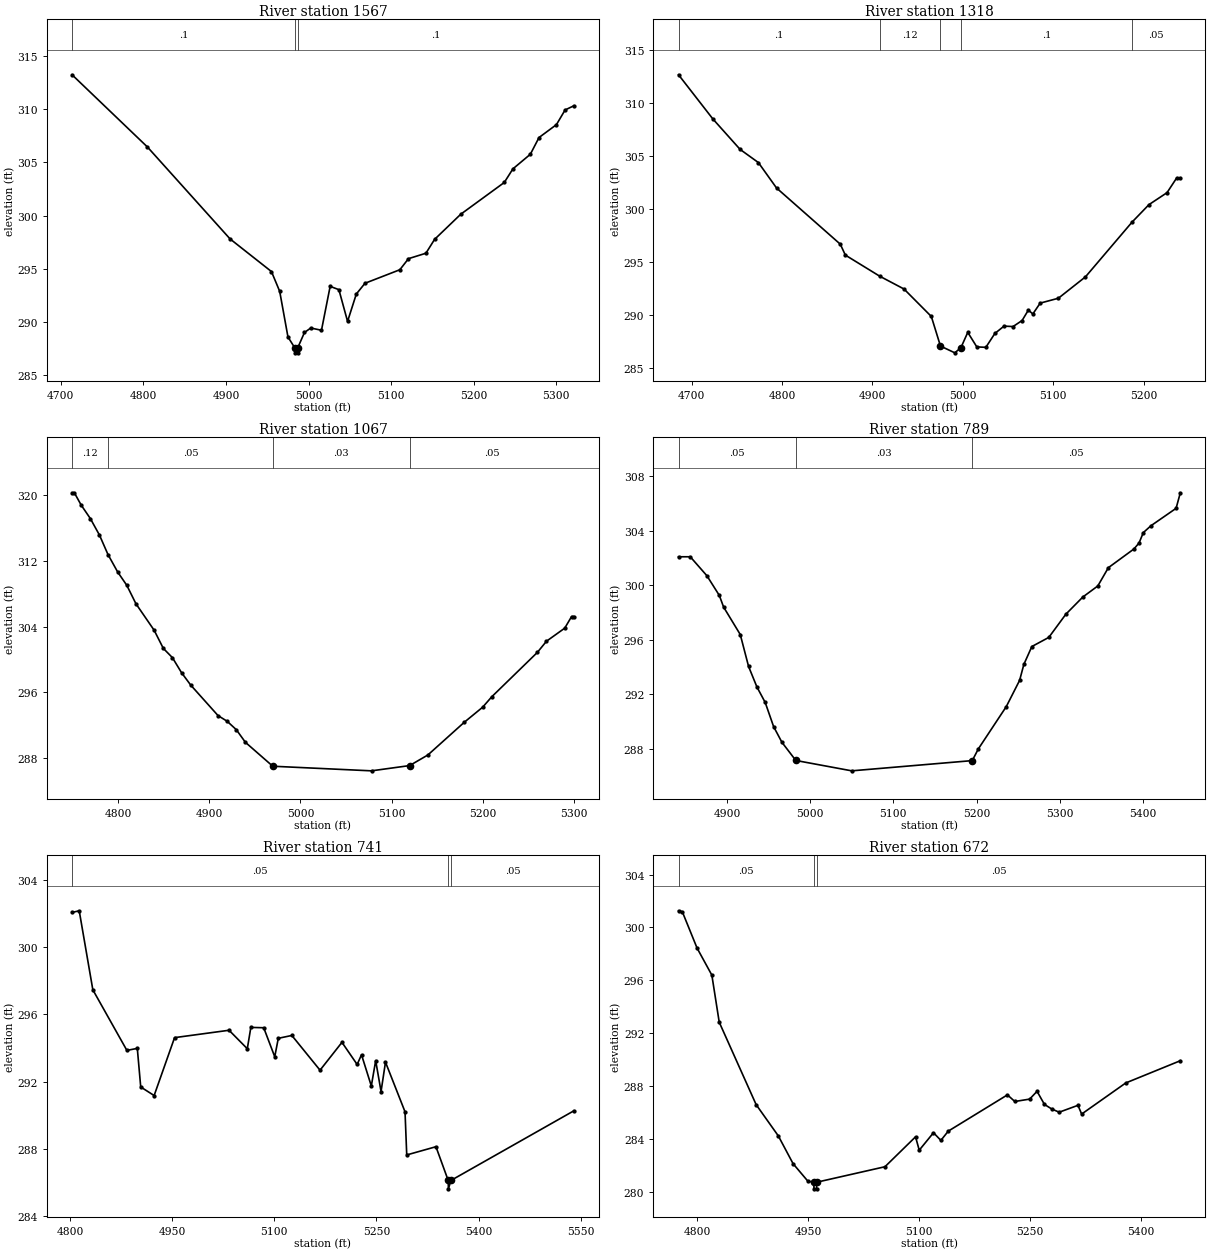
Type RM Length L Ch R = 1,1567,249,249,249
BEGIN DESCRIPTION:
Walnut84 6.0
END DESCRIPTION:
XS GIS Cut Line= 3
      2731034.76      6733874.70      2731326.00      6733861.00
      2731626.01      6733761.00
#Sta/Elev= 30
  4713.6  313.21  4804.9  306.43  4905.0  297.80  4955.1  294.74  4965.1  292.88
  4975.1  288.60  4983.1  287.61  4983.4  287.11  4986.9  287.11  4987.1  287.61
  4995.1  289.02  5002.7  289.44  5015.7  289.23  5026.2  293.35  5036.8  293.04
  5047.3  290.06  5057.9  292.63  5068.4  293.64  5110.6  294.91  5121.1  295.95
  5142.2  296.46  5152.7  297.76  5184.4  300.12  5237.1  303.10  5247.6  304.38
  5268.7  305.75  5279.2  307.32  5300.3  308.53  5310.8  309.91  5321.4  310.30
#Mann=3,-1,0
  4713.6     0.1       0  4983.1    0.07       0  4987.1     0.1       0
Bank Sta=4983.1,4987.1
Exp/Cntr=0.3,0.1

Type RM Length L Ch R = 1,1318,251,251,251
BEGIN DESCRIPTION:
Walnut84 5.0
END DESCRIPTION:
XS GIS Cut Line= 3
      2731075.33      6734097.38      2731376.00      6734061.00
      2731627.63      6734076.96
#Sta/Elev= 30
  4685.5  312.70  4723.4  308.54  4753.6  305.66  4773.8  304.42  4793.9  302.02
  4864.4  296.72  4870.0  295.69  4908.0  293.70  4934.9  292.49  4965.1  289.90
  4975.2  287.11  4991.1  286.47  4997.9  286.97  5005.4  288.40  5015.4  287.03
  5025.4  286.99  5035.4  288.30  5045.5  288.99  5055.5  288.95  5065.5  289.52
  5072.4  290.50  5077.4  290.14  5085.5  291.16  5105.6  291.62  5135.6  293.64
  5187.1  298.80  5205.8  300.45  5225.8  301.58  5236.4  302.96  5240.5  302.96
#Mann=5,-1,0
  4685.5     0.1       0  4908.0    0.12       0  4975.2    0.04       0
  4997.9     0.1       0  5187.1    0.05       0
Bank Sta=4975.2,4997.9
Exp/Cntr=0.3,0.1

Type RM Length L Ch R = 1,1067,278,278,278
BEGIN DESCRIPTION:
Walnut84 4.0
END DESCRIPTION:
XS GIS Cut Line= 3
      2731126.05      6734311.00      2731376.00      6734311.00
      2731676.05      6734311.00
#Sta/Elev= 30
  4749.7  320.29  4752.2  320.29  4759.7  318.79  4769.7  317.16  4779.7  315.15
  4789.1  312.77  4799.7  310.65  4809.7  309.03  4819.7  306.79  4839.7  303.56
  4849.7  301.36  4859.7  300.23  4869.7  298.40  4879.7  296.90  4909.7  293.18
  4919.7  292.49  4929.7  291.47  4939.7  289.93  4969.7  287.02  5077.9  286.46
  5119.7  287.10  5139.7  288.39  5179.7  292.38  5199.7  294.20  5209.7  295.47
  5259.7  300.87  5269.7  302.23  5289.7  303.82  5297.2  305.23  5299.7  305.23
#Mann=4,-1,0
  4749.7    0.12       0  4789.1    0.05       0  4969.7    0.03       0
  5119.7    0.05       0
Bank Sta=4969.7,5119.7
Exp/Cntr=0.3,0.1

Type RM Length L Ch R = 1,789,48,48,48
BEGIN DESCRIPTION:
Walnut84 3.0
END DESCRIPTION:
XS GIS Cut Line= 4
      2731201.94      6734543.06      2731344.38      6734551.63
      2731367.49      6734535.98      2731790.61      6734445.91
#Sta/Elev= 30
  4841.8  302.09  4855.9  302.09  4875.9  300.70  4890.8  299.26  4896.0  298.40
  4916.0  296.39  4926.0  294.05  4936.0  292.55  4946.0  291.41  4956.1  289.64
  4966.1  288.49  4982.8  287.16  5050.0  286.40  5194.9  287.15  5202.2  288.01
  5235.8  291.11  5251.8  293.03  5256.9  294.20  5266.5  295.51  5286.9  296.18
  5307.4  297.88  5327.8  299.14  5345.8  299.95  5358.5  301.29  5389.2  302.66
  5395.4  303.10  5400.5  303.86  5409.6  304.36  5439.9  305.64  5445.0  306.78
#Mann=3,-1,0
  4841.8    0.05       0  4982.8    0.03       0  5194.9    0.05       0
Bank Sta=4982.8,5194.9
Exp/Cntr=0.3,0.1

Type RM Length L Ch R = 1,741,69,69,69
BEGIN DESCRIPTION:
Walnut84 2.2
END DESCRIPTION:
XS GIS Cut Line= 5
      2731195.52      6734575.19      2731449.32      6734577.33
      2731575.68      6734544.13      2731644.22      6734627.66
      2731888.33      6734637.30
#Sta/Elev= 30
  4803.2  302.08  4813.7  302.18  4833.7  297.47  4883.7  293.86  4899.0  293.98
  4904.0  291.68  4923.7  291.17  4953.7  294.62  5033.7  295.06  5060.5  293.96
  5065.7  295.23  5084.6  295.21  5100.8  293.48  5106.0  294.58  5125.9  294.75
  5167.3  292.68  5199.5  294.34  5221.8  293.02  5228.2  293.60  5242.6  291.74
  5249.0  293.25  5256.9  291.41  5263.4  293.16  5292.1  290.20  5294.6  287.63
  5337.5  288.12  5355.5  286.11  5355.8  285.61  5359.5  286.11  5540.0  290.26
#Mann=3,-1,0
  4803.2    0.05       0  5355.5    0.03       0  5359.5    0.05       0
Bank Sta=5355.5,5359.5
Exp/Cntr=0.3,0.1

Type RM Length L Ch R = 1,672,248,248,248
BEGIN DESCRIPTION:
Walnut84 2.0
END DESCRIPTION:
XS GIS Cut Line= 3
      2731200.88      6734629.80      2731480.37      6734634.09
      2731879.83      6734652.29
#Sta/Elev= 30
  4774.5  301.26  4779.6  301.19  4799.6  298.44  4819.6  296.40  4829.6  292.84
  4879.6  286.61  4909.6  284.25  4929.6  282.15  4949.6  280.83  4957.6  280.75
  4957.9  280.25  4961.4  280.25  4961.6  280.75  5054.0  281.92  5095.4  284.18
  5100.4  283.17  5119.7  284.49  5129.7  283.91  5139.7  284.61  5219.8  287.35
  5229.8  286.85  5249.9  287.03  5259.9  287.62  5269.9  286.63  5279.9  286.28
  5289.9  286.04  5315.3  286.56  5320.3  285.90  5380.0  288.25  5453.9  289.93
#Mann=3,-1,0
  4774.5    0.05       0  4957.6    0.05       0  4961.6    0.05       0
Bank Sta=4957.6,4961.6
Exp/Cntr=0.3,0.1

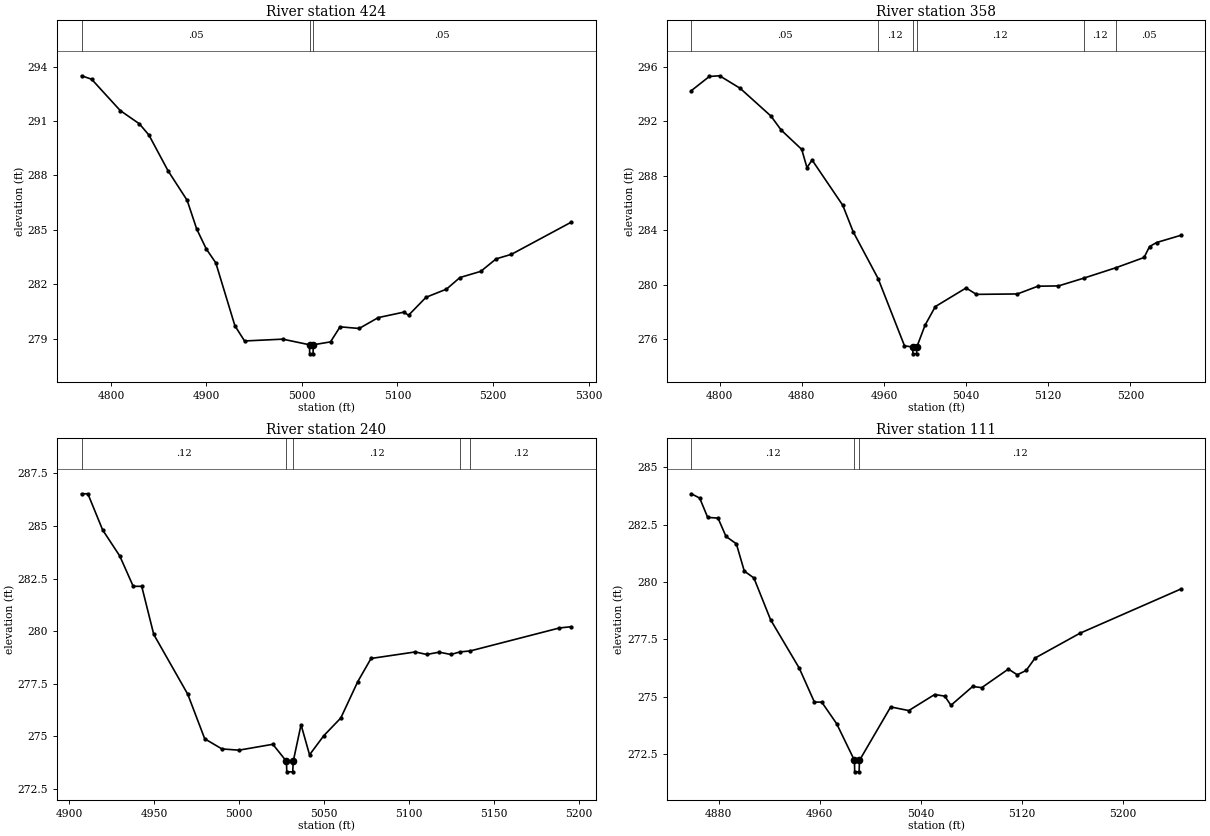
Type RM Length L Ch R = 1,424,66,66,66
BEGIN DESCRIPTION:
Walnut84 1.5
END DESCRIPTION:
XS GIS Cut Line= 3
      2731195.50      6734847.19      2731566.04      6734856.82
      2731690.23      6734788.31
#Sta/Elev= 30
  4769.3  293.50  4779.8  293.31  4809.8  291.58  4829.8  290.85  4839.8  290.23
  4859.8  288.26  4879.8  286.63  4889.8  285.05  4899.8  283.95  4909.8  283.18
  4929.8  279.71  4939.9  278.87  4979.9  278.97  5007.9  278.66  5008.1  278.16
  5011.6  278.16  5011.9  278.66  5029.9  278.82  5039.9  279.65  5059.9  279.56
  5079.9  280.16  5106.6  280.46  5111.6  280.29  5129.9  281.28  5151.3  281.73
  5165.4  282.37  5187.2  282.71  5203.3  283.40  5219.3  283.65  5281.8  285.42
#Mann=3,-1,0
  4769.3    0.05       0  5007.9    0.04       0  5011.9    0.05       0
Bank Sta=5007.9,5011.9
Exp/Cntr=0.3,0.1

Type RM Length L Ch R = 1,358,118,118,118
BEGIN DESCRIPTION:
Walnut84 1.3
END DESCRIPTION:
XS GIS Cut Line= 3
      2731198.50      6734913.07      2731569.04      6734922.71
      2731668.16      6734884.46
#Sta/Elev= 30
  4772.4  294.25  4789.9  295.29  4799.9  295.34  4819.9  294.42  4849.9  292.38
  4859.9  291.35  4879.9  289.93  4885.0  288.59  4890.0  289.15  4919.9  285.82
  4930.0  283.88  4954.3  280.44  4980.0  275.50  4988.0  275.41  4988.2  274.91
  4991.7  274.91  4992.0  275.41  5000.0  277.01  5010.0  278.38  5040.0  279.75
  5050.0  279.28  5090.0  279.31  5110.0  279.88  5130.0  279.90  5154.6  280.47
  5186.1  281.24  5213.4  281.99  5218.7  282.79  5225.6  283.09  5249.3  283.62
#Mann=6,-1,0
  4772.4    0.05       0  4954.3    0.12       0  4988.0    0.04       0
  4992.0    0.12       0  5154.6    0.12       0  5186.1    0.05       0
Bank Sta=4988,4992
Exp/Cntr=0.3,0.1

Type RM Length L Ch R = 1,240,129,129,129
BEGIN DESCRIPTION:
Walnut84 1.0
END DESCRIPTION:
XS GIS Cut Line= 4
      2731333.67      6735036.73      2731366.72      6735040.18
      2731506.47      6735034.19      2731590.28      6734955.31
#Sta/Elev= 30
  4907.2  286.53  4910.9  286.53  4919.6  284.81  4929.7  283.57  4937.6  282.13
  4942.6  282.13  4949.7  279.84  4969.7  277.00  4979.7  274.88  4989.8  274.40
  4999.8  274.34  5019.8  274.62  5027.8  273.81  5028.0  273.31  5031.5  273.31
  5031.8  273.81  5036.4  275.55  5041.4  274.12  5049.8  275.03  5059.8  275.87
  5069.8  277.60  5077.6  278.70  5103.6  279.01  5110.4  278.89  5117.7  279.00
  5124.6  278.89  5129.9  279.01  5136.1  279.06  5188.5  280.15  5195.4  280.21
#Mann=5,-1,0
  4907.2    0.12       0  5027.8    0.07       0  5031.8    0.12       0
  5129.9    0.05       0  5136.1    0.12       0
Bank Sta=5027.8,5031.8
Exp/Cntr=0.3,0.1

Type RM Length L Ch R = 1,111,0,0,0
BEGIN DESCRIPTION:
Walnut84 0.5
END DESCRIPTION:
XS GIS Cut Line= 4
      2731266.89      6735081.10      2731346.75      6735142.99
      2731450.57      6735166.95      2731576.35      6735038.17
#Sta/Elev= 30
  4858.4  283.84  4865.0  283.65  4871.3  282.81  4879.5  282.78  4885.8  281.98
  4894.0  281.66  4900.3  280.47  4907.9  280.17  4921.1  278.35  4943.8  276.24
  4955.8  274.76  4961.6  274.76  4973.4  273.82  4987.5  272.22  4987.7  271.72
  4991.2  271.72  4991.5  272.22  5016.2  274.55  5030.5  274.39  5051.0  275.09
  5059.0  275.02  5063.9  274.62  5081.1  275.44  5088.3  275.39  5109.4  276.20
  5116.4  275.95  5123.5  276.14  5130.5  276.68  5166.0  277.76  5246.0  279.69
#Mann=3,-1,0
  4858.4    0.12       0  4987.5    0.07       0  4991.5    0.12       0
Bank Sta=4987.5,4991.5
Exp/Cntr=0.3,0.1

Chan Stop Cuts=-1