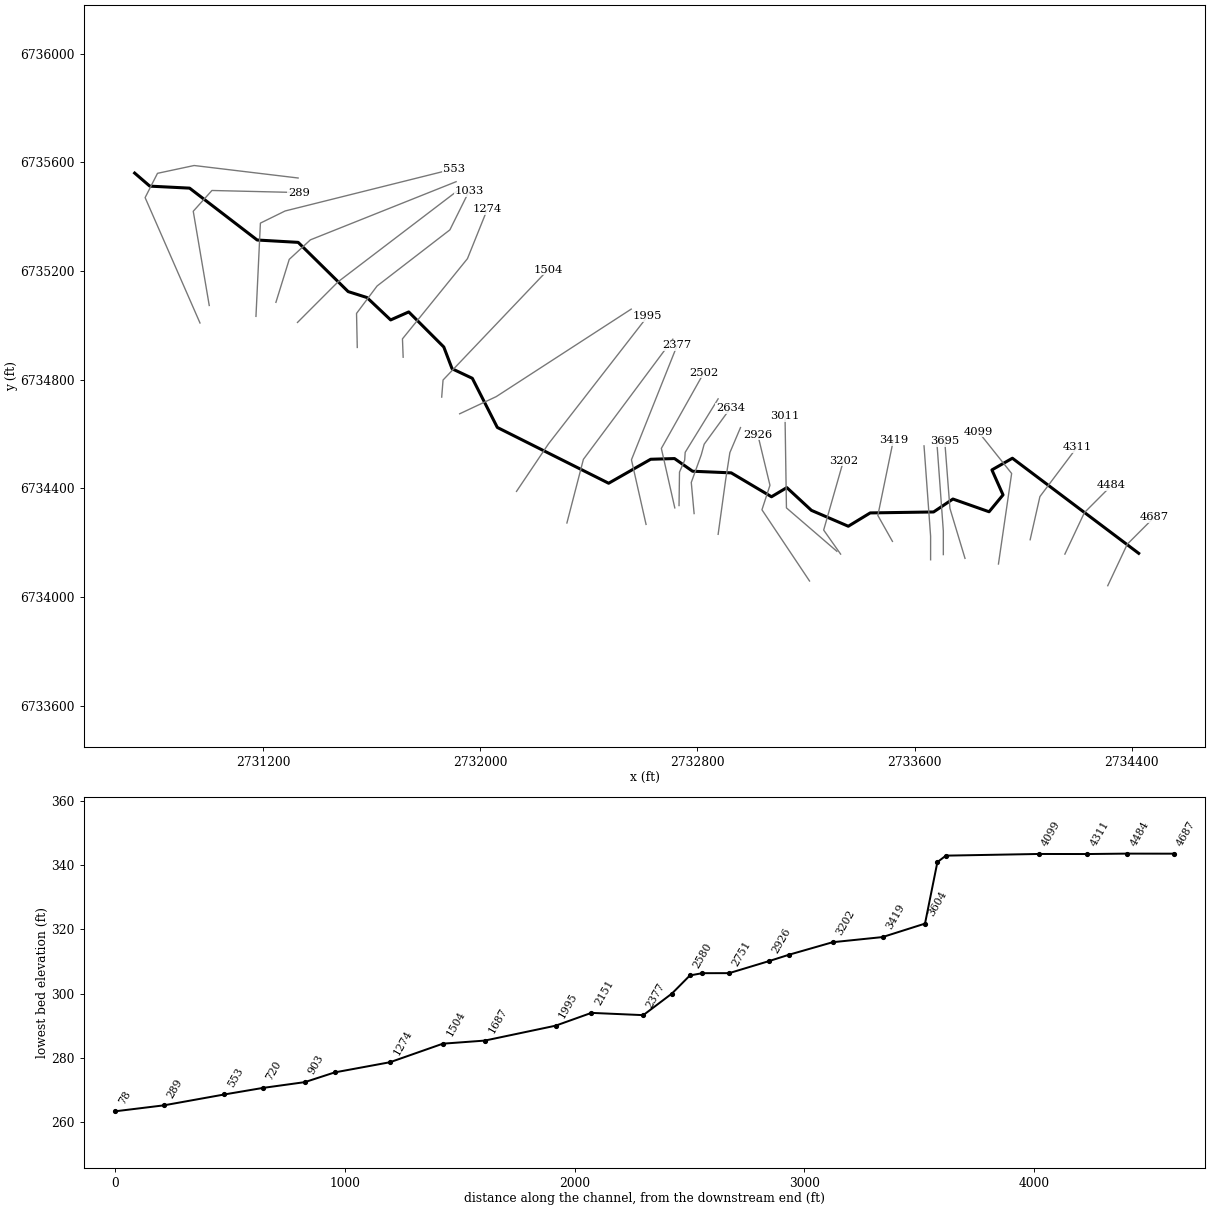
--- Walnut85.prj (project) ---

Proj Title=Walnut85 Base Level Engineering
Current Plan=p01
Default Exp/Contr=0.3,0.1
English Units
Geom File=g01
Flow File=f01
Plan File=p01
Y Axis Title=Elevation
X Axis Title(PF)=Main Channel Distance
X Axis Title(XS)=Station
BEGIN DESCRIPTION:
Walnut85
END DESCRIPTION:
DSS Export Rating Curves= 0
DSS Export Rating Curve Sorted= 0
DSS Export Volume Flow Curves= 0
DXF OffsetX= 0
DXF OffsetY= 0
DXF ScaleX= 1
DXF ScaleY= 10

--- Walnut85.p01 (plan) ---

Plan Title=Multiple Run
Program Version=4.10
Short Identifier=Multiple
Geom File=g01
Flow File=f01
Subcritical Flow
K Sum by GR= 0
Std Step Tol= 0.01
Critical Tol= 0.01
Num of Std Step Trials= 20
Max Error Tol= 0.3
Flow Tol Ratio= 0.001
Split Flow NTrial= 30
Split Flow Tol= 0.02
Split Flow Ratio= 0.02
Log Output Level= 0
Friction Slope Method= 1
Unsteady Friction Slope Method= 2
Unsteady Bridges Friction Slope Method= 1
Parabolic Critical Depth
Global Vel Dist= 1 , 1 , 1
Global Log Level= 0
CheckData=True
Encroach Param=-1 ,0,0, 0
BEGIN DESCRIPTION:
Multiple Run
END DESCRIPTION:
Computation Interval=1HOUR
Output Interval=1HOUR
Run HTab= 0
Run UNet= 0
Run PostProcess= 0
Run WQNet= 0
UNET Theta= 1
UNET Theta Warmup= 1
UNET ZTol= 0.02
UNET ZSATol= 0.05
UNET MxIter= 20
UNET MaxInSteps= 0
UNET DtIC= 0
UNET DtMin= 0
UNET MaxCRTS= 20
UNET WFStab= 2
UNET SFStab= 1
UNET WFX= 1
UNET SFX= 1
UNET DSS MLevel= 4
UNET DZMax Abort= 100
UNET Convert EG Bridges= 0
UNET Use Existing IB Tables=-1
UNET Froude Reduction=False
UNET Froude Limit= 1
UNET Froude Power= 10
UNET Time Slicing=0,0, 5
UNET Junction Losses=0
Instantaneous Interval=1HOUR
Write IC File= 0
Write IC File at Sim End=0
Echo Input=False
Echo Parameters=False
Echo Output=False
Write Detailed= 0
WQ AD Non Conservative
WQ ULTIMATE=-1
WQ Max Comp Step=1HOUR
WQ Output Interval=15MIN
WQ Output Selected Increments= 0
WQ Output face flow=0
WQ Output face velocity=0
WQ Output face area=0
WQ Output face dispersion=0
WQ Output cell volume=0
WQ Output cell surface area=0
WQ Output cell continuity=0
WQ Output cumulative cell continuity=0
WQ Output face conc=0
WQ Output face dconc_dx=0
WQ Output face courant=0
WQ Output face peclet=0
WQ Output face adv mass=0
WQ Output face disp mass=0
WQ Output cell mass=0
WQ Output cell source sink temp=0
WQ Output cell source sink nsm=0
WQ Output MaxMinRange=-1
WQ Daily Max Min Mean=-1
WQ Daily Range=0
WQ Daily Time=0
WQ Create Restart=0
WQ Fixed Restart=0
WQ System Summary=0
WQ Use Fixed Temperature=0
Sorting and Armoring Iterations= 10
XS Update Threshold= 0.02
Hydraulics Update Threshold= 0.02
Energy Slope Method= 1
Volume Change Method= 0
XS Weighting Method= 0
Number of US Weighted Cross Sections= 1
Number of DS Weighted Cross Sections= 1
Upstream XS Weight=0.25
Main XS Weight=0.5
Downstream XS Weight=0.25
Number of DS XS's Weighted with US Boundary= 1
Upstream Boundary Weight= 1
Weight of XSs Associated with US Boundary= 0
Number of US XS's Weighted with DS Boundary= 1
Downstream Boundary Weight= 0.5
Weight of XSs Associated with DS Boundary= 0.5
Sediment Output Level= 4
Mass or Volume Output= 0
Output Increment Type= 1
Profile and TS Output Increment= 10
XS Output Flag= 0
XS Output Increment= 10
Disregard all LS=0
Disregard all Conn=0
Disregard all Breaches=0
Disregard all Pumps=0

--- Walnut85.f01 (steady flow) ---

Flow Title=Multiple
Number of Profiles=7
Profile Names=10-year,25-year,50-year,1pct_min,100-year,1pct_plu,500-year
River Rch & RM= Walnut85,Reach-1,4687
     171     215     248     143     286     570     379
River Rch & RM= Walnut85,Reach-1,903
     261     337     396     233     465     927     638
Boundary for River Rch & Prof#=Walnut85,Reach-1,1
Up Type=0
Dn Type=3
Dn Slope=0.009
Boundary for River Rch & Prof#=Walnut85,Reach-1,2
Up Type=0
Dn Type=3
Dn Slope=0.009
Boundary for River Rch & Prof#=Walnut85,Reach-1,3
Up Type=0
Dn Type=3
Dn Slope=0.009
Boundary for River Rch & Prof#=Walnut85,Reach-1,4
Up Type=0
Dn Type=3
Dn Slope=0.009
Boundary for River Rch & Prof#=Walnut85,Reach-1,5
Up Type=0
Dn Type=3
Dn Slope=0.009
Boundary for River Rch & Prof#=Walnut85,Reach-1,6
Up Type=0
Dn Type=3
Dn Slope=0.009
Boundary for River Rch & Prof#=Walnut85,Reach-1,7
Up Type=0
Dn Type=3
Dn Slope=0.009

--- Walnut85.g01 (geometry) ---

Geom Title=Existing Conditions

River Reach=Walnut85,Reach-1
Reach XY= 30
      2734426.00      6734161.00      2733960.52      6734511.11
      2733885.03      6734468.11      2733926.04      6734376.21
      2733874.64      6734314.04      2733741.40      6734360.90
      2733670.07      6734313.29      2733436.50      6734309.76
      2733355.82      6734260.71      2733219.94      6734319.17
      2733129.33      6734402.99      2733072.77      6734369.25
      2732924.44      6734457.24      2732781.94      6734463.27
      2732715.45      6734509.90      2732627.58      6734507.32
      2732472.69      6734419.02      2732062.43      6734624.47
      2731970.38      6734805.38      2731895.73      6734840.57
      2731865.22      6734920.66      2731736.00      6735049.76
      2731669.34      6735020.32      2731582.05      6735102.80
      2731512.79      6735124.62      2731328.58      6735305.85
      2731177.47      6735314.55      2730928.45      6735505.52
      2730781.79      6735512.91      2730726.00      6735561.00

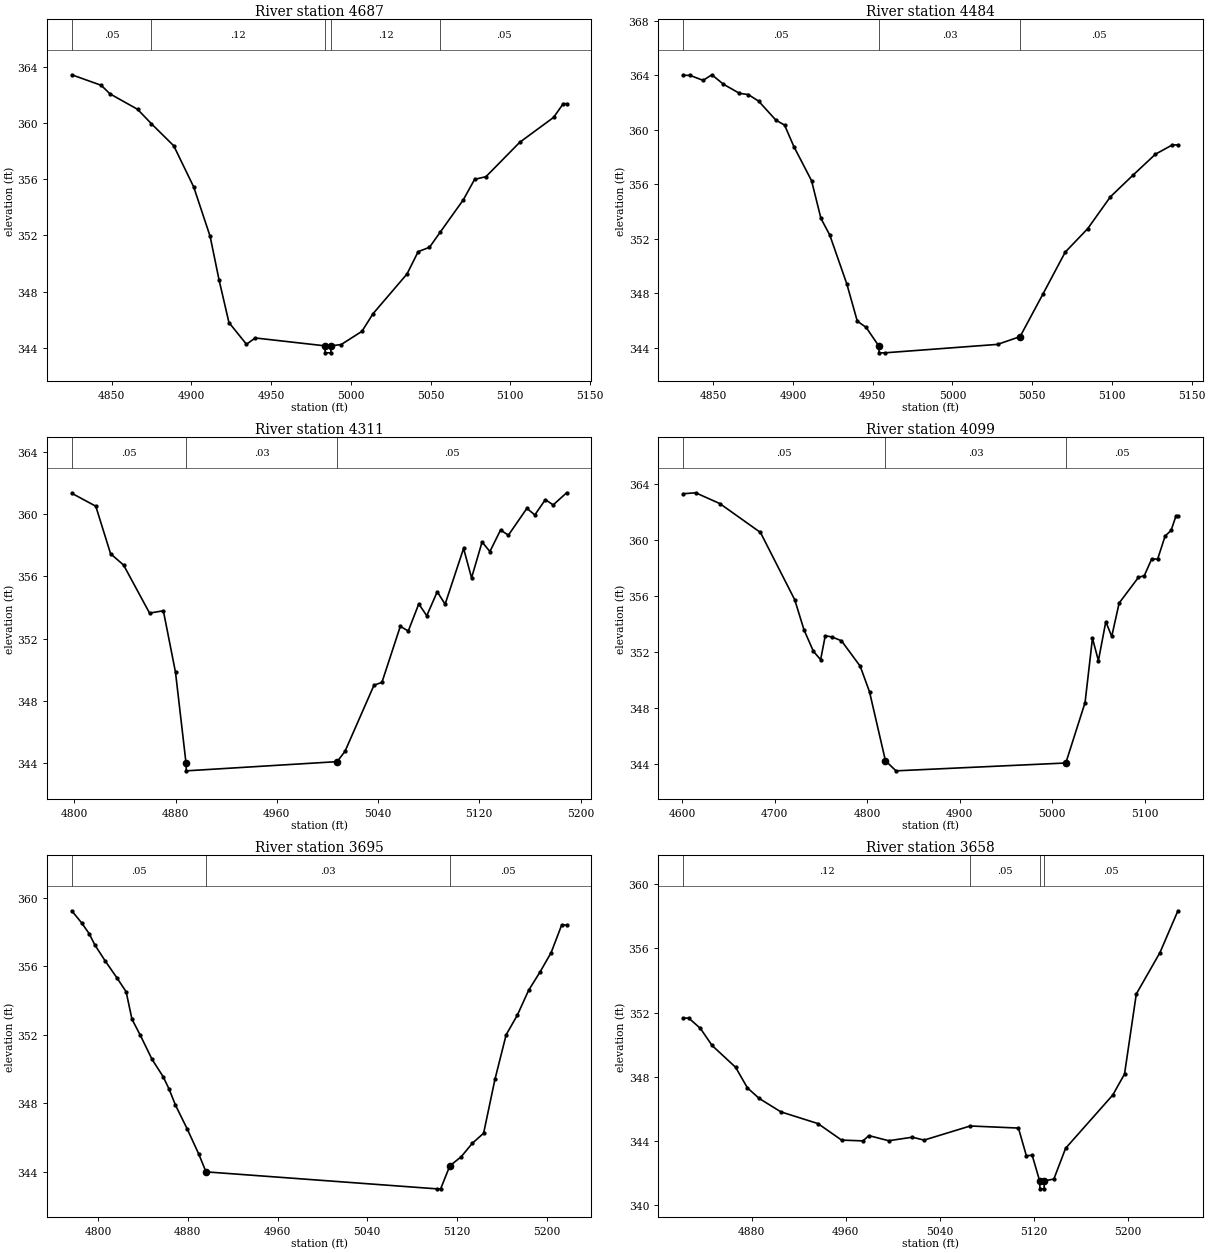
Type RM Length L Ch R = 1,4687,203,203,203
BEGIN DESCRIPTION:
Walnut85 17.0
END DESCRIPTION:
XS GIS Cut Line= 3
      2734311.95      6734041.79      2734383.99      6734194.68
      2734483.96      6734294.66
#Sta/Elev= 30
  4824.9  363.44  4843.4  362.69  4848.9  362.08  4866.2  360.98  4874.9  359.95
  4888.9  358.38  4901.4  355.45  4911.7  351.93  4917.3  348.83  4923.5  345.79
  4934.5  344.24  4940.0  344.69  4983.6  344.13  4983.9  343.63  4987.4  343.63
  4987.6  344.13  4993.9  344.22  5006.9  345.16  5013.9  346.42  5035.2  349.25
  5042.2  350.84  5049.3  351.15  5056.1  352.24  5070.5  354.53  5077.6  355.99
  5084.7  356.18  5105.9  358.63  5127.1  360.40  5133.2  361.38  5135.3  361.38
#Mann=5,-1,0
  4824.9    0.05       0  4874.9    0.12       0  4983.6    0.07       0
  4987.6    0.12       0  5056.1    0.05       0
Bank Sta=4983.6,4987.6
Exp/Cntr=0.3,0.1

Type RM Length L Ch R = 1,4484,173,173,173
BEGIN DESCRIPTION:
Walnut85 16.0
END DESCRIPTION:
XS GIS Cut Line= 3
      2734153.97      6734158.13      2734226.00      6734311.00
      2734325.99      6734410.99
#Sta/Elev= 30
  4831.0  363.99  4835.3  363.99  4843.6  363.62  4849.1  364.03  4856.3  363.34
  4866.4  362.67  4871.9  362.58  4878.4  362.10  4889.2  360.71  4894.7  360.34
  4900.5  358.77  4911.6  356.27  4917.5  353.50  4923.0  352.29  4933.7  348.71
  4940.3  345.97  4945.8  345.52  4953.8  344.15  4954.0  343.65  4957.5  343.65
  5028.3  344.27  5042.4  344.84  5056.6  347.93  5070.7  351.03  5084.8  352.75
  5099.0  355.08  5113.1  356.66  5127.3  358.21  5137.9  358.89  5141.4  358.89
#Mann=3,-1,0
  4831.0    0.05       0  4953.8    0.03       0  5042.4    0.05       0
Bank Sta=4953.8,5042.4
Exp/Cntr=0.3,0.1

Type RM Length L Ch R = 1,4311,212,212,212
BEGIN DESCRIPTION:
Walnut85 15.0
END DESCRIPTION:
XS GIS Cut Line= 3
      2734026.00      6734211.01      2734061.94      6734369.90
      2734199.07      6734552.17
#Sta/Elev= 30
  4798.0  361.33  4817.0  360.50  4828.7  357.45  4839.0  356.72  4859.5  353.64
  4870.4  353.79  4880.0  349.84  4888.3  344.02  4888.5  343.52  5007.7  344.11
  5013.9  344.77  5036.8  349.01  5043.1  349.20  5057.6  352.79  5063.9  352.49
  5072.2  354.23  5078.5  353.47  5086.8  355.01  5093.0  354.21  5107.6  357.79
  5113.9  355.90  5122.2  358.20  5128.4  357.59  5136.8  358.97  5143.0  358.64
  5157.6  360.36  5163.9  359.94  5172.2  360.92  5178.4  360.58  5189.0  361.36
#Mann=3,-1,0
  4798.0    0.05       0  4888.3    0.03       0  5007.7    0.05       0
Bank Sta=4888.3,5007.7
Exp/Cntr=0.3,0.1

Type RM Length L Ch R = 1,4099,404,404,404
BEGIN DESCRIPTION:
Walnut85 14.3
END DESCRIPTION:
XS GIS Cut Line= 3
      2733909.17      6734121.67      2733957.77      6734454.97
      2733834.50      6734609.49
#Sta/Elev= 30
  4601.2  363.31  4614.8  363.38  4640.9  362.61  4684.8  360.55  4721.8  355.75
  4731.9  353.59  4742.0  352.07  4749.8  351.47  4754.8  353.18  4762.2  353.09
  4772.3  352.82  4792.5  351.01  4802.6  349.18  4819.8  344.26  4831.2  343.54
  5014.6  344.10  5035.4  348.41  5043.4  353.00  5049.8  351.40  5057.8  354.18
  5064.2  353.13  5072.2  355.51  5093.0  357.34  5099.4  357.47  5107.4  358.66
  5113.8  358.65  5121.9  360.30  5128.3  360.69  5133.5  361.71  5135.7  361.71
#Mann=3,-1,0
  4601.2    0.05       0  4819.8    0.03       0  5014.6    0.05       0
Bank Sta=4819.8,5014.6
Exp/Cntr=0.3,0.1

Type RM Length L Ch R = 1,3695,37,37,37
BEGIN DESCRIPTION:
Walnut85 14.0
END DESCRIPTION:
XS GIS Cut Line= 3
      2733785.89      6734142.49      2733730.34      6734326.50
      2733711.25      6734574.76
#Sta/Elev= 30
  4776.5  359.23  4785.4  358.52  4792.0  357.90  4797.2  357.23  4806.3  356.31
  4816.7  355.33  4825.0  354.51  4830.2  352.91  4837.6  351.98  4848.1  350.57
  4858.0  349.56  4863.2  348.85  4869.0  347.90  4879.4  346.52  4889.8  345.04
  4896.2  344.01  5101.9  343.02  5105.4  343.02  5113.6  344.36  5123.7  344.89
  5133.7  345.68  5143.7  346.26  5153.8  349.40  5163.8  352.00  5173.8  353.15
  5183.8  354.59  5193.9  355.65  5203.9  356.79  5213.3  358.40  5217.7  358.40
#Mann=3,-1,0
  4776.5    0.05       0  4896.2    0.03       0  5113.6    0.05       0
Bank Sta=4896.2,5113.6
Exp/Cntr=0.3,0.1

Type RM Length L Ch R = 1,3658,54,54,54
BEGIN DESCRIPTION:
Walnut85 13.8
END DESCRIPTION:
XS GIS Cut Line= 3
      2733706.04      6734156.34      2733706.04      6734243.17
      2733681.75      6734576.26
#Sta/Elev= 30
  4821.6  351.66  4826.4  351.66  4836.3  351.02  4846.3  349.95  4866.3  348.59
  4876.3  347.31  4886.3  346.65  4904.8  345.81  4936.3  345.08  4956.4  344.05
  4974.6  344.00  4979.6  344.33  4996.5  344.01  5016.5  344.23  5026.6  344.05
  5065.8  344.93  5106.8  344.80  5113.5  343.08  5118.5  343.10  5124.8  341.51
  5125.1  341.01  5128.6  341.01  5128.8  341.51  5136.9  341.62  5146.9  343.54
  5187.0  346.86  5197.0  348.17  5207.0  353.16  5227.1  355.74  5242.4  358.35
#Mann=4,-1,0
  4821.6    0.12       0  5065.8    0.05       0  5124.8    0.07       0
  5128.8    0.05       0
Bank Sta=5124.8,5128.8
Exp/Cntr=0.3,0.1

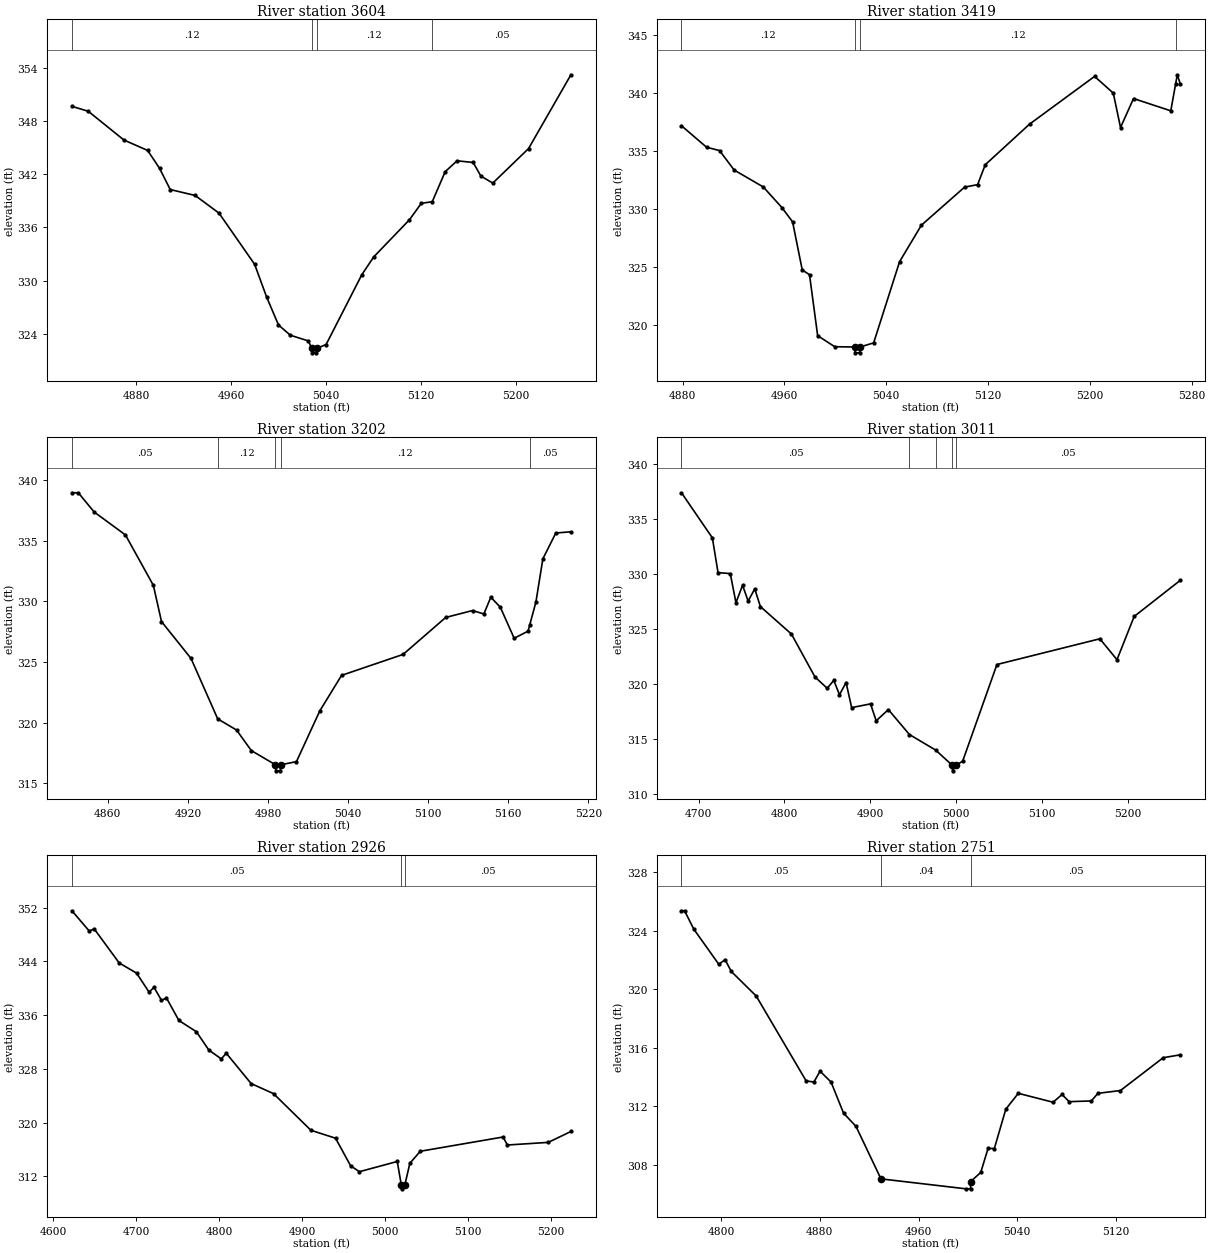
Type RM Length L Ch R = 1,3604,185,185,185
BEGIN DESCRIPTION:
Walnut85 13.6
END DESCRIPTION:
XS GIS Cut Line= 3
      2733659.16      6734137.24      2733659.16      6734224.07
      2733634.91      6734556.65
#Sta/Elev= 30
  4826.1  349.70  4839.9  349.14  4869.9  345.89  4889.9  344.71  4899.9  342.69
  4908.9  340.29  4929.9  339.62  4950.0  337.62  4980.0  331.83  4990.1  328.13
  5000.1  324.97  5010.1  323.81  5025.2  323.17  5028.2  322.32  5028.4  321.82
  5031.9  321.82  5032.2  322.32  5040.2  322.76  5070.3  330.66  5080.3  332.67
  5110.4  336.87  5120.4  338.73  5129.6  338.91  5140.5  342.31  5150.5  343.54
  5164.1  343.35  5170.5  341.82  5180.6  341.02  5210.7  344.92  5246.4  353.27
#Mann=4,-1,0
  4826.1    0.12       0  5028.2    0.07       0  5032.2    0.12       0
  5129.6    0.05       0
Bank Sta=5028.2,5032.2
Exp/Cntr=0.3,0.1

Type RM Length L Ch R = 1,3419,217,217,217
BEGIN DESCRIPTION:
Walnut85 13.0
END DESCRIPTION:
XS GIS Cut Line= 3
      2733518.53      6734204.99      2733464.72      6734300.46
      2733521.79      6734577.15
#Sta/Elev= 30
  4879.2  337.21  4898.9  335.36  4909.1  335.07  4920.6  333.39  4943.5  331.93
  4958.2  330.14  4966.5  328.92  4974.1  324.77  4979.8  324.36  4986.2  319.10
  4999.6  318.15  5015.4  318.12  5015.6  317.62  5019.1  317.62  5019.4  318.12
  5030.2  318.48  5050.6  325.49  5067.7  328.63  5101.7  331.92  5111.9  332.13
  5117.9  333.85  5152.7  337.35  5203.8  341.47  5218.5  340.03  5224.2  337.06
  5234.4  339.56  5263.7  338.50  5267.5  340.82  5268.8  341.61  5271.3  340.78
#Mann=4,-1,0
  4879.2    0.12       0  5015.4    0.07       0  5019.4    0.12       0
  5267.5    0.05       0
Bank Sta=5015.4,5019.4
Exp/Cntr=0.3,0.1

Type RM Length L Ch R = 1,3202,191,191,191
BEGIN DESCRIPTION:
Walnut85 12.0
END DESCRIPTION:
XS GIS Cut Line= 3
      2733327.54      6734158.13      2733265.07      6734246.64
      2733337.99      6734501.89
#Sta/Elev= 30
  4833.1  338.97  4837.9  338.97  4849.7  337.39  4873.2  335.49  4894.1  331.33
  4900.2  328.34  4922.3  325.30  4942.3  320.31  4956.4  319.39  4967.5  317.69
  4985.6  316.52  4985.8  316.02  4989.3  316.02  4989.6  316.52  5001.3  316.78
  5018.8  320.97  5035.1  323.90  5081.2  325.63  5113.1  328.68  5133.2  329.25
  5141.7  328.97  5146.9  330.35  5154.0  329.53  5164.4  326.96  5174.8  327.55
  5176.1  328.08  5180.7  329.96  5185.9  333.52  5195.6  335.65  5206.9  335.75
#Mann=5,-1,0
  4833.1    0.05       0  4942.3    0.12       0  4985.6    0.07       0
  4989.6    0.12       0  5176.1    0.05       0
Bank Sta=4985.6,4989.6
Exp/Cntr=0.3,0.1

Type RM Length L Ch R = 1,3011,85,85,85
BEGIN DESCRIPTION:
Walnut85 11.2
END DESCRIPTION:
XS GIS Cut Line= 3
      2733313.68      6734168.51      2733127.91      6734328.24
      2733122.70      6734665.01
#Sta/Elev= 30
  4679.9  337.39  4715.9  333.29  4722.5  330.13  4736.8  330.04  4743.4  327.39
  4751.1  328.98  4757.6  327.54  4765.3  328.65  4771.9  327.04  4808.1  324.54
  4835.6  320.63  4849.8  319.61  4857.5  320.33  4864.1  319.02  4871.8  320.13
  4878.3  317.85  4900.3  318.19  4906.9  316.65  4921.1  317.67  4945.7  315.40
  4976.2  313.99  4995.7  312.60  4995.9  312.10  4999.7  312.60  5007.7  312.97
  5047.7  321.77  5167.7  324.11  5187.7  322.21  5207.7  326.14  5261.7  329.44
#Mann=5,-1,0
  4679.9    0.05       0  4945.7    0.12       0  4976.2    0.05       0
  4995.7    0.04       0  4999.7    0.05       0
Bank Sta=4995.7,4999.7
Exp/Cntr=0.3,0.1

Type RM Length L Ch R = 1,2926,175,175,175
BEGIN DESCRIPTION:
Walnut85 11.0
END DESCRIPTION:
XS GIS Cut Line= 4
      2733212.99      6734059.13      2733037.63      6734321.29
      2733067.15      6734411.57      2733022.37      6734597.57
#Sta/Elev= 30
  4622.7  351.52  4643.6  348.51  4649.6  348.82  4679.7  343.76  4700.7  342.24
  4715.7  339.42  4721.7  340.13  4730.7  338.20  4736.7  338.55  4751.7  335.20
  4772.8  333.53  4787.8  330.80  4802.8  329.49  4808.8  330.33  4838.8  325.82
  4865.8  324.32  4910.9  318.87  4940.6  317.69  4958.8  313.58  4969.4  312.71
  5015.0  314.23  5020.0  310.66  5020.2  310.16  5024.0  310.66  5030.2  313.96
  5042.8  315.75  5142.6  317.87  5147.8  316.68  5197.1  317.07  5224.4  318.69
#Mann=3,-1,0
  4622.7    0.05       0  5020.0    0.04       0  5024.0    0.05       0
Bank Sta=5020,5024
Exp/Cntr=0.3,0.1

Type RM Length L Ch R = 1,2751,117,117,117
BEGIN DESCRIPTION:
Walnut85 10.0
END DESCRIPTION:
XS GIS Cut Line= 4
      2732876.18      6734231.05      2732903.95      6734432.40
      2732919.45      6734531.82      2732958.60      6734623.97
#Sta/Elev= 30
  4768.1  325.35  4770.6  325.35  4778.1  324.09  4798.3  321.70  4803.4  322.01
  4808.4  321.21  4828.6  319.53  4869.0  313.74  4875.3  313.66  4880.3  314.40
  4889.2  313.66  4899.3  311.54  4909.4  310.63  4929.6  307.05  4998.6  306.37
  5002.1  306.37  5002.3  306.87  5010.4  307.49  5016.3  309.13  5021.4  309.12
  5030.7  311.81  5040.8  312.89  5069.0  312.28  5076.2  312.81  5082.0  312.32
  5099.9  312.37  5105.3  312.89  5123.5  313.08  5158.1  315.32  5172.1  315.52
#Mann=3,-1,0
  4768.1    0.05       0  4929.6    0.04       0  5002.3    0.05       0
Bank Sta=4929.6,5002.3
Exp/Cntr=0.3,0.1

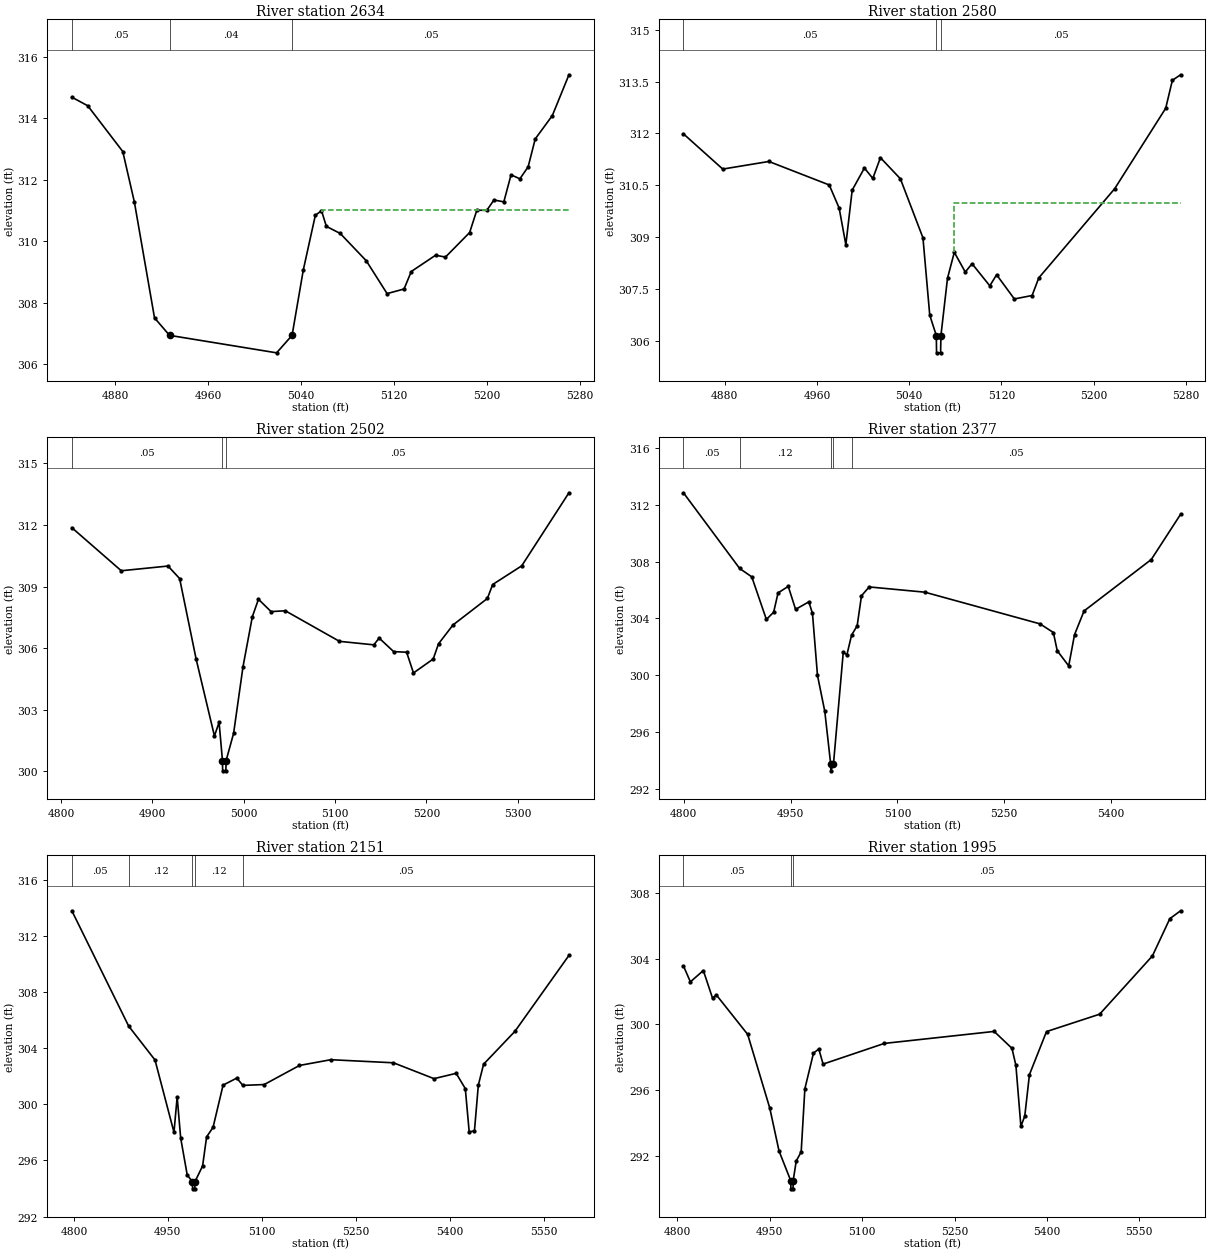
Type RM Length L Ch R = 1,2634,54,54,54
BEGIN DESCRIPTION:
Walnut85 9.6
END DESCRIPTION:
XS GIS Cut Line= 5
      2732787.64      6734307.39      2732777.22      6734421.99
      2732813.89      6734523.33      2732824.75      6734562.81
      2732921.18      6734695.11
#Sta/Elev= 30
  4842.9  314.69  4856.6  314.41  4886.7  312.92  4896.7  311.27  4914.0  307.50
  4926.9  306.93  5019.0  306.36  5032.3  306.93  5042.0  309.07  5052.3  310.84
  5057.6  310.99  5061.8  310.48  5073.7  310.25  5096.1  309.36  5114.0  308.29
  5128.6  308.44  5134.8  309.01  5155.7  309.54  5164.2  309.48  5185.0  310.28
  5191.2  311.01  5199.7  311.00  5205.9  311.34  5214.4  311.28  5220.6  312.16
  5228.2  312.03  5235.3  312.42  5241.4  313.33  5256.1  314.09  5270.4  315.42
#Mann=3,-1,0
  4842.9    0.05       0  4926.9    0.04       0  5032.3    0.05       0
#XS Ineff=2,0
       0                 5058.00    0.00  311.00
Permanent Ineff=
       F       F
Bank Sta=4926.9,5032.3
Exp/Cntr=0.3,0.1

Type RM Length L Ch R = 1,2580,78,78,78
BEGIN DESCRIPTION:
Walnut85 9.5
END DESCRIPTION:
XS GIS Cut Line= 5
      2732732.08      6734336.88      2732733.82      6734460.18
      2732752.88      6734503.77      2732754.75      6734532.86
      2732876.12      6734729.71
#Sta/Elev= 30
  4844.1  311.99  4878.2  310.97  4918.2  311.19  4970.6  310.51  4979.2  309.84
  4985.0  308.78  4990.5  310.36  5001.1  311.00  5008.4  310.70  5015.0  311.30
  5032.3  310.69  5051.9  308.98  5057.8  306.74  5063.5  306.15  5063.7  305.65
  5067.2  305.65  5067.5  306.15  5073.2  307.81  5079.1  308.56  5088.6  307.99
  5094.5  308.23  5109.9  307.59  5115.8  307.91  5131.2  307.21  5146.6  307.31
  5152.4  307.82  5218.2  310.40  5262.5  312.73  5268.3  313.54  5275.4  313.70
#Mann=3,-1,0
  4844.1    0.05       0  5063.5    0.04       0  5067.5    0.05       0
#XS Ineff=2,0
       0                 5079.10    0.00  310.00
Permanent Ineff=
       F       F
Bank Sta=5063.5,5067.5
Exp/Cntr=0.3,0.1

Type RM Length L Ch R = 1,2502,125,125,125
BEGIN DESCRIPTION:
Walnut85 9.4
END DESCRIPTION:
XS GIS Cut Line= 3
      2732716.45      6734328.26      2732666.90      6734547.23
      2732823.59      6734825.89
#Sta/Elev= 30
  4811.8  311.87  4865.9  309.77  4917.1  310.00  4929.8  309.39  4947.9  305.46
  4967.9  301.72  4973.0  302.38  4976.7  300.52  4976.9  300.02  4980.4  300.02
  4980.7  300.52  4988.9  301.85  4999.2  305.10  5009.4  307.53  5016.1  308.38
  5029.9  307.78  5045.5  307.82  5104.8  306.33  5142.4  306.16  5148.2  306.49
  5164.1  305.83  5178.3  305.80  5185.8  304.79  5207.4  305.47  5213.2  306.21
  5229.1  307.13  5266.7  308.42  5272.5  309.10  5304.3  310.01  5356.0  313.57
#Mann=3,-1,0
  4811.8    0.05       0  4976.7    0.04       0  4980.7    0.05       0
Bank Sta=4976.7,4980.7
Exp/Cntr=0.3,0.1

Type RM Length L Ch R = 1,2377,226,226,226
BEGIN DESCRIPTION:
Walnut85 9.0
END DESCRIPTION:
XS GIS Cut Line= 3
      2732610.54      6734267.50      2732556.73      6734505.32
      2732725.23      6734926.75
#Sta/Elev= 30
  4799.7  312.85  4878.6  307.52  4895.6  306.93  4916.1  303.93  4926.3  304.44
  4932.5  305.80  4946.8  306.26  4957.1  304.64  4975.7  305.17  4980.8  304.35
  4987.8  300.00  4998.1  297.45  5006.3  293.77  5006.6  293.27  5010.3  293.77
  5024.0  301.62  5029.1  301.44  5035.7  302.83  5043.5  303.48  5049.6  305.60
  5060.4  306.22  5138.5  305.85  5300.1  303.62  5318.9  303.01  5324.3  301.73
  5340.4  300.66  5348.6  302.86  5362.0  304.53  5456.3  308.15  5497.4  311.33
#Mann=5,-1,0
  4799.7    0.05       0  4878.6    0.12       0  5006.3    0.07       0
  5010.3    0.12       0  5035.7    0.05       0
Bank Sta=5006.3,5010.3
Exp/Cntr=0.3,0.1

Type RM Length L Ch R = 1,2151,156,156,156
BEGIN DESCRIPTION:
Walnut85 8.0
END DESCRIPTION:
XS GIS Cut Line= 3
      2732318.90      6734272.72      2732379.65      6734507.05
      2732709.38      6734949.40
#Sta/Elev= 30
  4796.7  313.79  4887.5  305.57  4929.5  303.16  4959.8  298.01  4964.9  300.53
  4970.5  297.60  4980.9  294.98  4989.2  294.48  4989.5  293.98  4993.0  293.98
  4993.2  294.48  5005.5  295.61  5011.9  297.68  5022.2  298.36  5038.2  301.37
  5060.1  301.87  5069.8  301.35  5103.9  301.41  5160.2  302.77  5210.2  303.18
  5310.3  302.96  5375.0  301.83  5410.4  302.21  5425.0  301.12  5431.2  298.04
  5439.6  298.11  5445.8  301.37  5454.2  302.86  5504.2  305.20  5590.5  310.61
#Mann=5,-1,0
  4796.7    0.05       0  4887.5    0.12       0  4989.2    0.07       0
  4993.2    0.12       0  5069.8    0.05       0
Bank Sta=4989.2,4993.2
Exp/Cntr=0.3,0.1

Type RM Length L Ch R = 1,1995,308,308,308
BEGIN DESCRIPTION:
Walnut85 7.0
END DESCRIPTION:
XS GIS Cut Line= 3
      2732133.13      6734389.01      2732251.18      6734564.35
      2732617.03      6735034.75
#Sta/Elev= 30
  4809.8  303.56  4821.1  302.59  4842.1  303.28  4857.1  301.59  4863.1  301.80
  4914.1  299.39  4950.0  294.90  4965.0  292.29  4984.0  290.48  4984.3  289.98
  4987.8  289.98  4988.0  290.48  4993.0  291.68  5001.0  292.23  5007.0  296.08
  5021.0  298.25  5029.6  298.50  5036.6  297.58  5136.1  298.84  5314.4  299.57
  5343.3  298.54  5349.7  297.50  5357.8  293.79  5364.1  294.41  5371.7  296.94
  5399.4  299.56  5485.7  300.62  5571.4  304.17  5599.7  306.44  5617.1  306.92
#Mann=3,-1,0
  4809.8    0.05       0  4984.0    0.04       0  4988.0    0.05       0
Bank Sta=4984,4988
Exp/Cntr=0.3,0.1

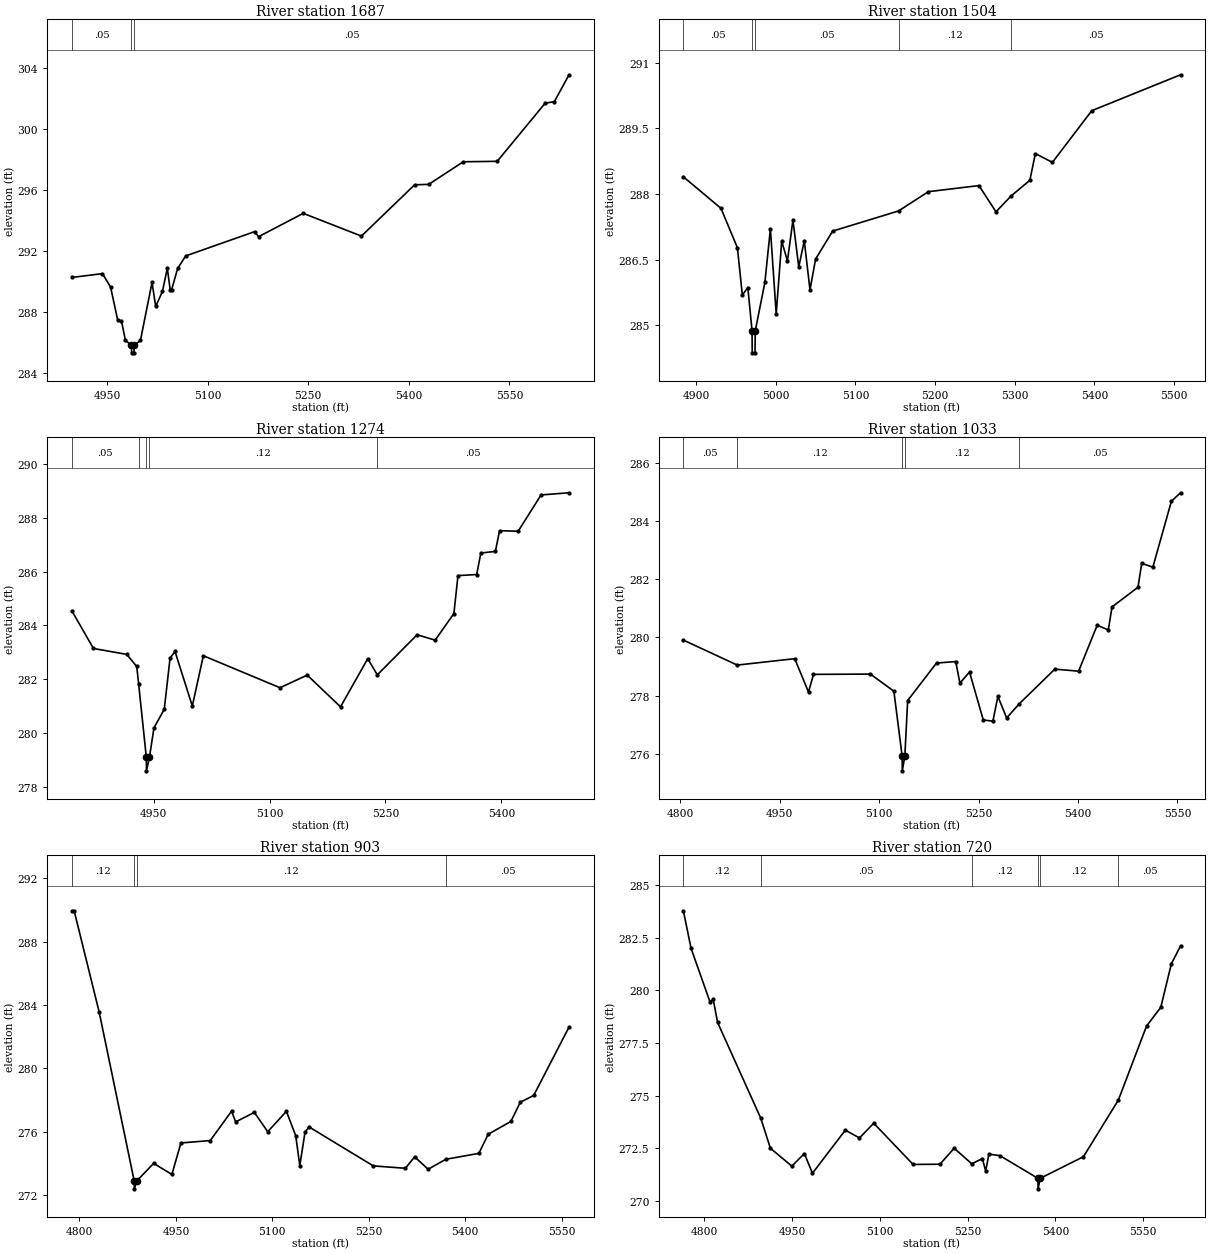
Type RM Length L Ch R = 1,1687,183,183,183
BEGIN DESCRIPTION:
Walnut85 6.0
END DESCRIPTION:
XS GIS Cut Line= 3
      2731923.71      6734674.70      2732058.47      6734737.96
      2732555.87      6735060.14
#Sta/Elev= 30
  4897.4  290.28  4943.1  290.53  4955.2  289.65  4965.9  287.46  4971.4  287.43
  4977.3  286.16  4986.3  285.84  4986.6  285.34  4990.1  285.34  4990.3  285.84
  4999.7  286.15  5017.0  289.95  5022.5  288.38  5032.5  289.36  5039.8  290.89
  5044.0  289.49  5046.3  289.49  5055.2  290.87  5067.2  291.69  5169.9  293.28
  5175.9  292.95  5242.5  294.48  5329.3  292.99  5408.6  296.35  5429.7  296.38
  5481.2  297.86  5531.8  297.89  5603.3  301.70  5617.0  301.80  5638.9  303.56
#Mann=3,-1,0
  4897.4    0.05       0  4986.3    0.04       0  4990.3    0.05       0
Bank Sta=4986.3,4990.3
Exp/Cntr=0.3,0.1

Type RM Length L Ch R = 1,1504,230,230,230
BEGIN DESCRIPTION:
Walnut85 5.0
END DESCRIPTION:
XS GIS Cut Line= 3
      2731857.48      6734736.21      2731862.47      6734799.03
      2732249.42      6735205.05
#Sta/Elev= 30
  4884.1  288.39  4931.3  287.67  4951.9  286.77  4958.1  285.69  4965.0  285.86
  4970.3  284.87  4970.5  284.37  4974.0  284.37  4974.3  284.87  4986.4  285.98
  4993.3  287.20  5000.6  285.26  5007.5  286.92  5014.7  286.47  5021.6  287.40
  5028.9  286.33  5035.8  286.93  5043.0  285.81  5050.0  286.51  5071.4  287.15
  5154.1  287.61  5191.5  288.05  5255.0  288.19  5276.4  287.59  5295.2  287.95
  5318.9  288.31  5325.8  288.92  5347.2  288.72  5396.6  289.90  5508.0  290.72
#Mann=5,-1,0
  4884.1    0.05       0  4970.3    0.04       0  4974.3    0.05       0
  5154.1    0.12       0  5295.2    0.05       0
Bank Sta=4970.3,4974.3
Exp/Cntr=0.3,0.1

Type RM Length L Ch R = 1,1274,241,241,241
BEGIN DESCRIPTION:
Walnut85 4.5
END DESCRIPTION:
XS GIS Cut Line= 4
      2731715.44      6734883.02      2731712.90      6734950.64
      2731952.40      6735245.94      2732025.48      6735427.29
#Sta/Elev= 30
  4844.1  284.54  4872.1  283.14  4915.2  282.92  4928.1  282.47  4930.5  281.83
  4940.5  279.09  4940.7  278.59  4944.5  279.09  4950.4  280.19  4963.7  280.88
  4971.2  282.78  4977.6  283.03  5000.0  281.00  5014.3  282.87  5113.5  281.68
  5148.7  282.15  5191.8  280.97  5227.0  282.76  5239.4  282.16  5290.9  283.65
  5314.3  283.45  5338.5  284.44  5343.8  285.85  5368.0  285.89  5373.4  286.69
  5392.2  286.75  5397.6  287.52  5421.7  287.50  5451.3  288.85  5487.5  288.93
#Mann=5,-1,0
  4844.1    0.05       0  4930.5    0.12       0  4940.5    0.07       0
  4944.5    0.12       0  5239.4    0.05       0
Bank Sta=4940.5,4944.5
Exp/Cntr=0.3,0.1

Type RM Length L Ch R = 1,1033,130,130,130
BEGIN DESCRIPTION:
Walnut85 4.0
END DESCRIPTION:
XS GIS Cut Line= 5
      2731546.36      6734918.95      2731543.64      6735044.29
      2731619.36      6735145.25      2731887.63      6735351.89
      2731958.79      6735495.09
#Sta/Elev= 30
  4804.7  279.91  4886.0  279.05  4972.7  279.27  4993.5  278.12  5001.0  278.73
  5086.9  278.74  5122.3  278.15  5134.8  275.91  5135.0  275.41  5138.8  275.91
  5143.1  277.83  5186.6  279.12  5215.6  279.17  5221.9  278.43  5236.4  278.81
  5257.2  277.16  5271.7  277.12  5279.2  277.97  5292.5  277.23  5311.1  277.71
  5365.1  278.91  5401.0  278.84  5429.0  280.42  5445.8  280.26  5451.4  281.05
  5490.6  281.73  5496.2  282.55  5513.0  282.42  5541.0  284.69  5554.8  284.98
#Mann=5,-1,0
  4804.7    0.05       0  4886.0    0.12       0  5134.8    0.07       0
  5138.8    0.12       0  5311.1    0.05       0
Bank Sta=5134.8,5138.8
Exp/Cntr=0.3,0.1

Type RM Length L Ch R = 1,903,183,183,183
BEGIN DESCRIPTION:
Walnut85 3.0
END DESCRIPTION:
XS GIS Cut Line= 3
      2731325.99      6735010.99      2731476.00      6735161.00
      2731922.55      6735501.00
#Sta/Elev= 30
  4788.1  289.95  4791.7  289.95  4830.5  283.57  4885.1  272.88  4885.4  272.38
  4889.1  272.88  4915.4  273.99  4943.7  273.29  4957.8  275.28  5003.4  275.43
  5036.6  277.29  5042.9  276.61  5072.0  277.21  5092.8  275.99  5121.9  277.28
  5136.4  275.73  5142.7  273.85  5150.9  275.97  5157.2  276.29  5257.0  273.83
  5306.9  273.68  5321.4  274.40  5342.3  273.62  5370.1  274.25  5421.2  274.62
  5435.8  275.83  5471.1  276.64  5485.7  277.85  5506.5  278.28  5561.5  282.60
#Mann=4,-1,0
  4788.1    0.12       0  4885.1    0.07       0  4889.1    0.12       0
  5370.1    0.05       0
Bank Sta=4885.1,4889.1
Exp/Cntr=0.3,0.1

Type RM Length L Ch R = 1,720,167,167,167
BEGIN DESCRIPTION:
Walnut85 2.0
END DESCRIPTION:
XS GIS Cut Line= 4
      2731246.59      6735085.12      2731295.66      6735243.22
      2731373.52      6735315.09      2731910.60      6735529.23
#Sta/Elev= 30
  4764.2  283.79  4777.3  282.01  4809.9  279.44  4815.1  279.59  4822.7  278.48
  4896.6  273.92  4912.9  272.50  4949.6  271.65  4971.0  272.25  4984.8  271.31
  5041.0  273.36  5065.2  272.99  5089.5  273.69  5156.8  271.73  5202.7  271.74
  5227.0  272.50  5257.1  271.76  5275.2  272.01  5280.9  271.41  5286.3  272.22
  5305.1  272.15  5370.1  271.07  5370.4  270.57  5374.1  271.07  5448.0  272.10
  5507.6  274.79  5555.8  278.31  5580.1  279.20  5598.2  281.27  5613.9  282.12
#Mann=6,-1,0
  4764.2    0.12       0  4896.6    0.05       0  5257.1    0.12       0
  5370.1    0.04       0  5374.1    0.12       0  5507.6    0.05       0
Bank Sta=5370.1,5374.1
Exp/Cntr=0.3,0.1

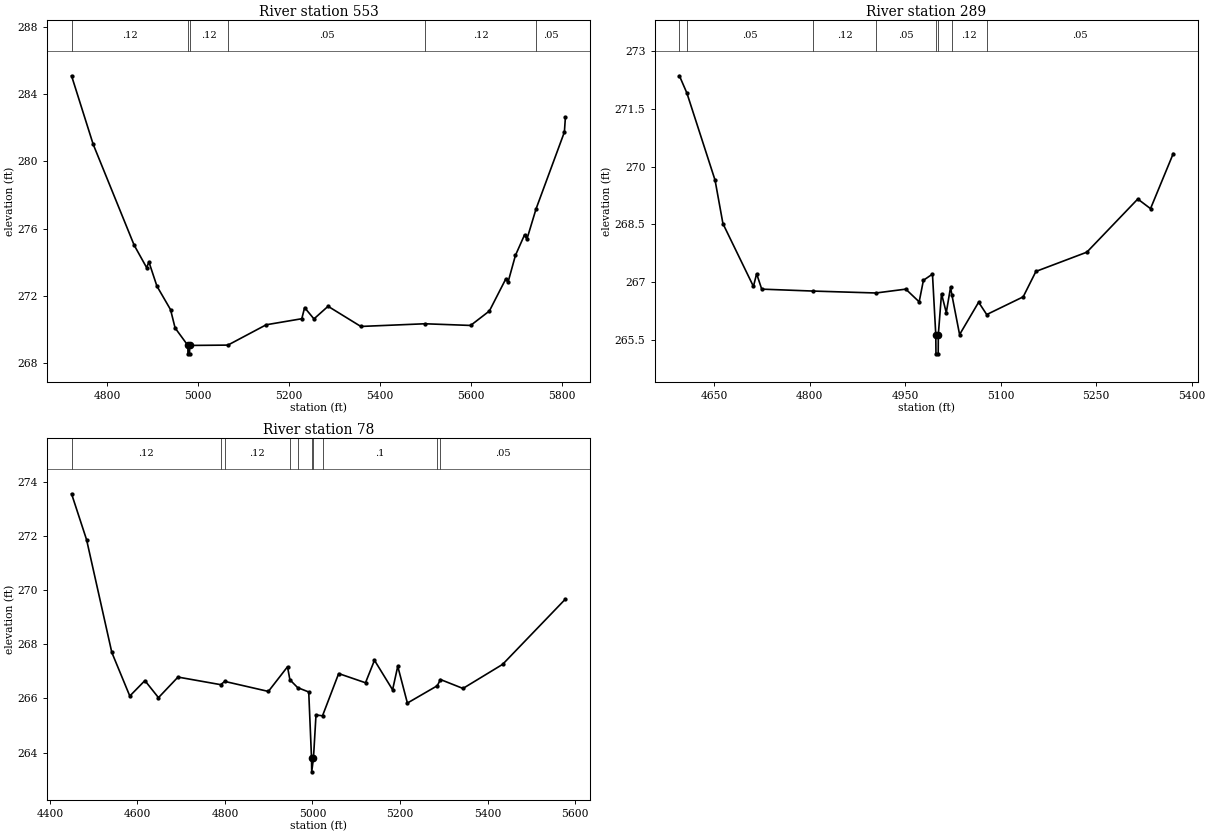
Type RM Length L Ch R = 1,553,264,264,264
BEGIN DESCRIPTION:
Walnut85 1.0
END DESCRIPTION:
XS GIS Cut Line= 4
      2731173.03      6735033.41      2731189.38      6735376.74
      2731280.42      6735421.41      2731902.61      6735576.65
#Sta/Elev= 30
  4721.0  285.09  4768.6  281.01  4858.7  275.01  4886.2  273.67  4891.2  274.01
  4908.8  272.57  4938.8  271.17  4948.8  270.08  4976.9  269.04  4977.1  268.54
  4980.6  268.54  4980.9  269.04  5065.0  269.06  5149.2  270.27  5227.5  270.63
  5233.7  271.29  5254.3  270.62  5285.3  271.37  5357.4  270.17  5498.2  270.33
  5598.9  270.23  5640.2  271.09  5676.3  273.00  5681.4  272.82  5697.5  274.40
  5717.5  275.62  5722.7  275.36  5742.9  277.17  5805.2  281.74  5807.4  282.61
#Mann=6,-1,0
  4721.0    0.12       0  4976.9    0.07       0  4980.9    0.12       0
  5065.0    0.05       0  5498.2    0.12       0  5742.9    0.05       0
Bank Sta=4976.9,4980.9
Exp/Cntr=0.3,0.1

Type RM Length L Ch R = 1,289,211,211,211
BEGIN DESCRIPTION:
Walnut85 0.7
END DESCRIPTION:
XS GIS Cut Line= 4
      2731000.84      6735073.54      2730941.92      6735420.38
      2731010.80      6735496.91      2731331.64      6735489.27
#Sta/Elev= 30
  4595.3  272.36  4607.1  271.91  4651.3  269.65  4663.7  268.52  4711.6  266.89
  4716.6  267.22  4724.6  266.82  4805.1  266.77  4904.0  266.72  4950.9  266.82
  4971.9  266.49  4978.6  267.05  4992.8  267.21  4998.0  265.64  4998.3  265.14
  5001.8  265.14  5002.0  265.64  5007.0  266.70  5014.5  266.21  5021.2  266.87
  5023.2  266.68  5035.4  265.64  5065.3  266.48  5078.0  266.16  5135.3  266.62
  5155.3  267.28  5235.3  267.78  5315.3  269.16  5335.3  268.91  5371.0  270.34
#Mann=8,-1,0
  4595.3    0.12       0  4607.1    0.05       0  4805.1    0.12       0
  4904.0    0.05       0  4998.0    0.04       0  5002.0    0.05       0
  5023.2    0.12       0  5078.0    0.05       0
Bank Sta=4998,5002
Exp/Cntr=0.3,0.1

Type RM Length L Ch R = 1,78,0,0,0
BEGIN DESCRIPTION:
Walnut85 0.4
END DESCRIPTION:
XS GIS Cut Line= 5
      2730966.78      6735009.07      2730764.55      6735470.64
      2730810.18      6735560.08      2730945.25      6735588.83
      2731328.36      6735542.84
#Sta/Elev= 30
  4449.5  273.56  4483.9  271.86  4541.5  267.70  4582.6  266.09  4617.1  266.66
  4648.1  266.03  4692.7  266.79  4790.2  266.51  4799.5  266.63  4899.2  266.26
  4942.9  267.17  4948.4  266.69  4966.1  266.40  4991.4  266.24  4997.8  263.79
  4998.2  263.29  5002.2  263.79  5008.0  265.39  5022.9  265.36  5059.8  266.92
  5121.1  266.58  5141.6  267.41  5183.0  266.32  5194.8  267.19  5216.8  265.83
  5285.1  266.47  5292.3  266.70  5343.8  266.37  5434.4  267.26  5577.8  269.67
#Mann=10,-1,0
  4449.5    0.12       0  4790.2    0.05       0  4799.5    0.12       0
  4948.4     0.1       0  4966.1    0.12       0  4997.8    0.07       0
  5002.2    0.12       0  5022.9     0.1       0  5285.1    0.12       0
  5292.3    0.05       0
Bank Sta=4997.8,5002.2
Exp/Cntr=0.3,0.1

Chan Stop Cuts=-1