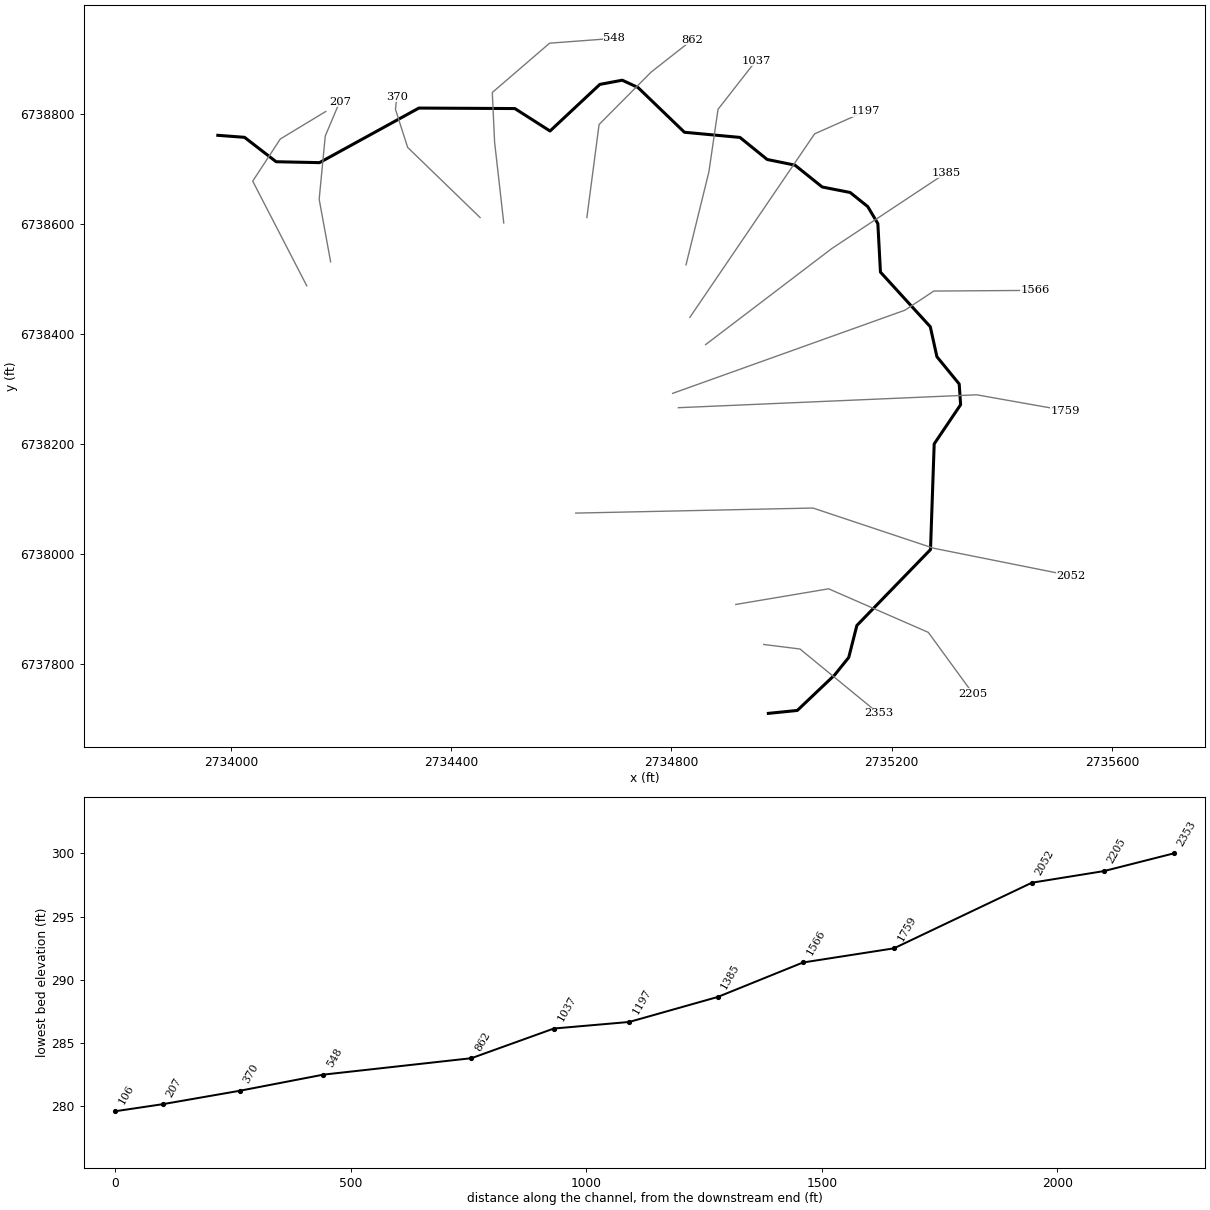
--- Walnut88.prj (project) ---

Proj Title=Walnut88 Base Level Engineering
Current Plan=p01
Default Exp/Contr=0.3,0.1
English Units
Geom File=g01
Flow File=f01
Plan File=p01
Y Axis Title=Elevation
X Axis Title(PF)=Main Channel Distance
X Axis Title(XS)=Station
BEGIN DESCRIPTION:
Walnut88
END DESCRIPTION:
DSS Export Rating Curves= 0
DSS Export Rating Curve Sorted= 0
DSS Export Volume Flow Curves= 0
DXF OffsetX= 0
DXF OffsetY= 0
DXF ScaleX= 1
DXF ScaleY= 10

--- Walnut88.p01 (plan) ---

Plan Title=Multiple Run
Program Version=4.10
Short Identifier=Multiple
Geom File=g01
Flow File=f01
Subcritical Flow
K Sum by GR= 0
Std Step Tol= 0.01
Critical Tol= 0.01
Num of Std Step Trials= 20
Max Error Tol= 0.3
Flow Tol Ratio= 0.001
Split Flow NTrial= 30
Split Flow Tol= 0.02
Split Flow Ratio= 0.02
Log Output Level= 0
Friction Slope Method= 1
Unsteady Friction Slope Method= 2
Unsteady Bridges Friction Slope Method= 1
Parabolic Critical Depth
Global Vel Dist= 1 , 1 , 1
Global Log Level= 0
CheckData=True
Encroach Param=-1 ,0,0, 0
BEGIN DESCRIPTION:
Multiple Run
END DESCRIPTION:
Computation Interval=1HOUR
Output Interval=1HOUR
Run HTab= 0
Run UNet= 0
Run PostProcess= 0
Run WQNet= 0
UNET Theta= 1
UNET Theta Warmup= 1
UNET ZTol= 0.02
UNET ZSATol= 0.05
UNET MxIter= 20
UNET MaxInSteps= 0
UNET DtIC= 0
UNET DtMin= 0
UNET MaxCRTS= 20
UNET WFStab= 2
UNET SFStab= 1
UNET WFX= 1
UNET SFX= 1
UNET DSS MLevel= 4
UNET DZMax Abort= 100
UNET Convert EG Bridges= 0
UNET Use Existing IB Tables=-1
UNET Froude Reduction=False
UNET Froude Limit= 1
UNET Froude Power= 10
UNET Time Slicing=0,0, 5
UNET Junction Losses=0
Instantaneous Interval=1HOUR
Write IC File= 0
Write IC File at Sim End=0
Echo Input=False
Echo Parameters=False
Echo Output=False
Write Detailed= 0
WQ AD Non Conservative
WQ ULTIMATE=-1
WQ Max Comp Step=1HOUR
WQ Output Interval=15MIN
WQ Output Selected Increments= 0
WQ Output face flow=0
WQ Output face velocity=0
WQ Output face area=0
WQ Output face dispersion=0
WQ Output cell volume=0
WQ Output cell surface area=0
WQ Output cell continuity=0
WQ Output cumulative cell continuity=0
WQ Output face conc=0
WQ Output face dconc_dx=0
WQ Output face courant=0
WQ Output face peclet=0
WQ Output face adv mass=0
WQ Output face disp mass=0
WQ Output cell mass=0
WQ Output cell source sink temp=0
WQ Output cell source sink nsm=0
WQ Output MaxMinRange=-1
WQ Daily Max Min Mean=-1
WQ Daily Range=0
WQ Daily Time=0
WQ Create Restart=0
WQ Fixed Restart=0
WQ System Summary=0
WQ Use Fixed Temperature=0
Sorting and Armoring Iterations= 10
XS Update Threshold= 0.02
Hydraulics Update Threshold= 0.02
Energy Slope Method= 1
Volume Change Method= 0
XS Weighting Method= 0
Number of US Weighted Cross Sections= 1
Number of DS Weighted Cross Sections= 1
Upstream XS Weight=0.25
Main XS Weight=0.5
Downstream XS Weight=0.25
Number of DS XS's Weighted with US Boundary= 1
Upstream Boundary Weight= 1
Weight of XSs Associated with US Boundary= 0
Number of US XS's Weighted with DS Boundary= 1
Downstream Boundary Weight= 0.5
Weight of XSs Associated with DS Boundary= 0.5
Sediment Output Level= 4
Mass or Volume Output= 0
Output Increment Type= 1
Profile and TS Output Increment= 10
XS Output Flag= 0
XS Output Increment= 10
Disregard all LS=0
Disregard all Conn=0
Disregard all Breaches=0
Disregard all Pumps=0

--- Walnut88.f01 (steady flow) ---

Flow Title=Multiple
Number of Profiles=7
Profile Names=10-year,25-year,50-year,1pct_min,100-year,1pct_plu,500-year
River Rch & RM= Walnut88,Reach-1,2353
     217     277     323     189     377     752     511
Boundary for River Rch & Prof#=Walnut88,Reach-1,1
Up Type=0
Dn Type=3
Dn Slope=0.005
Boundary for River Rch & Prof#=Walnut88,Reach-1,2
Up Type=0
Dn Type=3
Dn Slope=0.005
Boundary for River Rch & Prof#=Walnut88,Reach-1,3
Up Type=0
Dn Type=3
Dn Slope=0.005
Boundary for River Rch & Prof#=Walnut88,Reach-1,4
Up Type=0
Dn Type=3
Dn Slope=0.005
Boundary for River Rch & Prof#=Walnut88,Reach-1,5
Up Type=0
Dn Type=3
Dn Slope=0.005
Boundary for River Rch & Prof#=Walnut88,Reach-1,6
Up Type=0
Dn Type=3
Dn Slope=0.005
Boundary for River Rch & Prof#=Walnut88,Reach-1,7
Up Type=0
Dn Type=3
Dn Slope=0.005

--- Walnut88.g01 (geometry) ---

Geom Title=Existing Conditions

River Reach=Walnut88,Reach-1
Reach XY= 30
      2734976.00      6737711.00      2735028.54      6737716.30
      2735096.43      6737780.78      2735122.03      6737812.64
      2735136.78      6737870.68      2735270.54      6738008.55
      2735277.24      6738200.50      2735325.24      6738271.69
      2735322.66      6738309.28      2735282.18      6738358.81
      2735270.16      6738413.29      2735179.63      6738512.50
      2735174.90      6738600.67      2735156.53      6738631.54
      2735124.61      6738657.15      2735073.84      6738667.12
      2735024.28      6738706.84      2734973.82      6738717.12
      2734924.41      6738757.17      2734823.58      6738766.54
      2734739.20      6738847.86      2734710.64      6738861.10
      2734669.95      6738853.50      2734579.41      6738768.81
      2734515.57      6738809.61      2734341.21      6738810.49
      2734160.73      6738711.36      2734081.92      6738713.02
      2734024.49      6738757.35      2733976.00      6738761.00

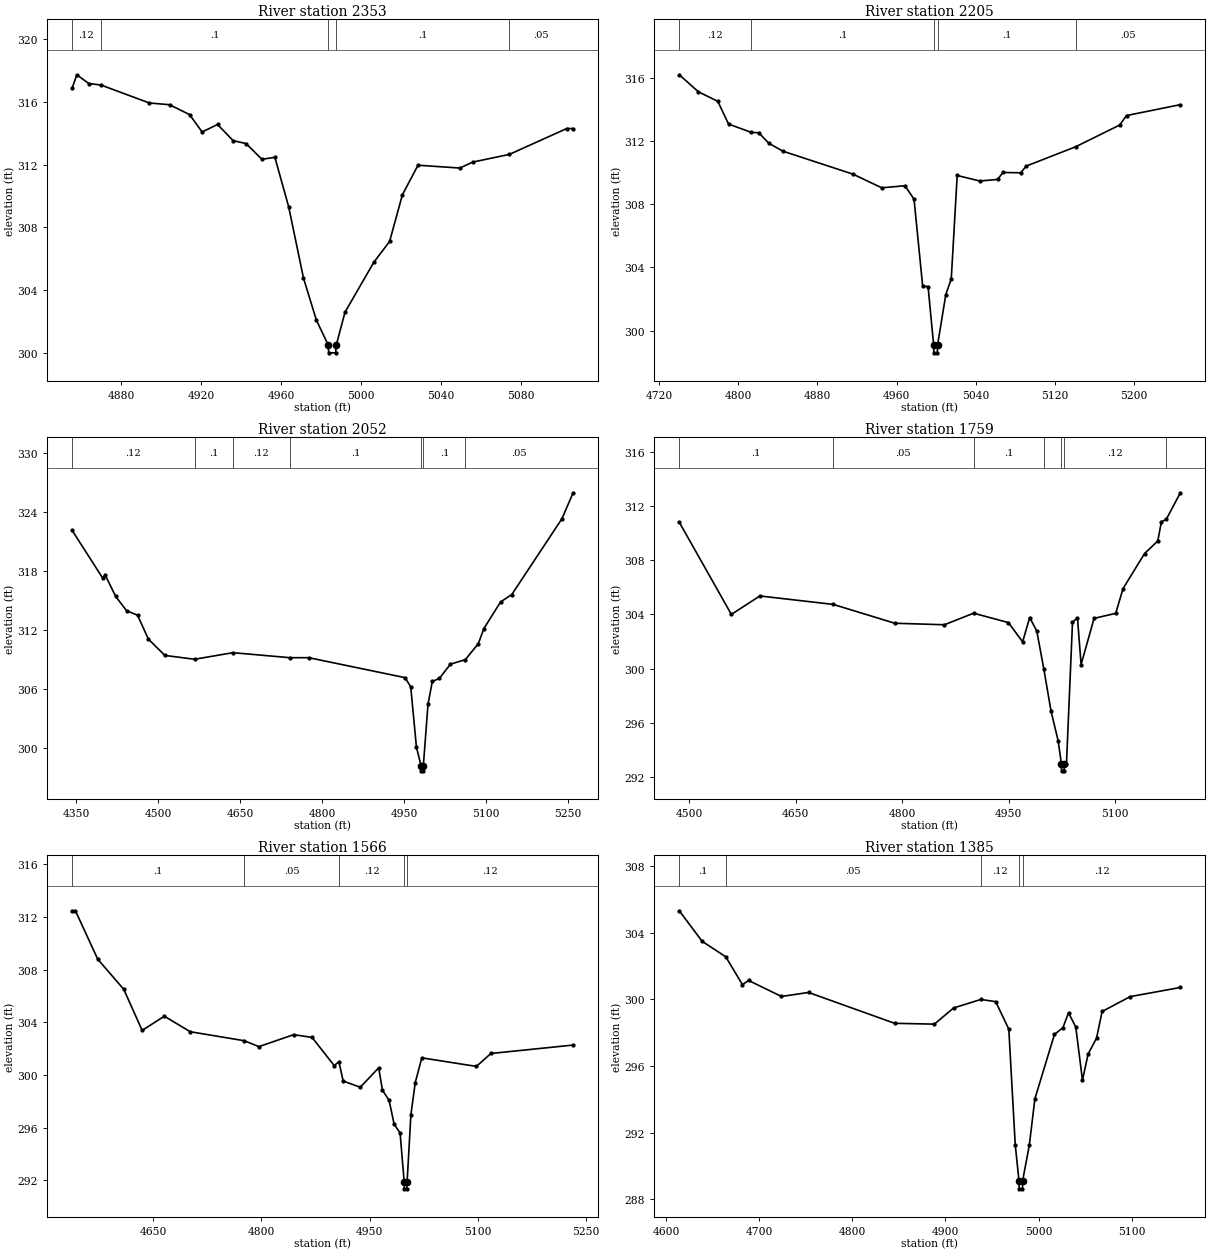
Type RM Length L Ch R = 1,2353,148,148,148
BEGIN DESCRIPTION:
Walnut88 3.0
END DESCRIPTION:
XS GIS Cut Line= 3
      2734967.62      6737836.16      2735033.46      6737827.93
      2735175.98      6737711.01
#Sta/Elev= 30
  4855.4  316.87  4857.8  317.74  4863.8  317.18  4869.8  317.09  4894.1  315.94
  4904.2  315.83  4914.2  315.20  4920.5  314.09  4928.2  314.57  4936.0  313.54
  4942.5  313.35  4950.4  312.35  4956.9  312.47  4963.8  309.31  4971.2  304.77
  4977.7  302.07  4983.6  300.50  4983.8  300.00  4987.3  300.00  4987.6  300.50
  4992.0  302.60  5006.4  305.78  5014.3  307.11  5020.7  310.09  5028.5  311.97
  5049.4  311.79  5055.9  312.17  5074.2  312.66  5102.9  314.31  5106.1  314.31
#Mann=5,-1,0
  4855.4    0.12       0  4869.8     0.1       0  4983.6    0.07       0
  4987.6     0.1       0  5074.2    0.05       0
Bank Sta=4983.6,4987.6
Exp/Cntr=0.3,0.1

Type RM Length L Ch R = 1,2205,153,153,153
BEGIN DESCRIPTION:
Walnut88 2.5
END DESCRIPTION:
XS GIS Cut Line= 4
      2734916.84      6737908.84      2735085.57      6737937.25
      2735266.60      6737858.10      2735347.51      6737747.03
#Sta/Elev= 30
  4740.6  316.19  4760.0  315.11  4779.5  314.51  4790.4  313.07  4813.2  312.55
  4820.9  312.52  4831.0  311.86  4845.1  311.36  4916.2  309.90  4945.1  309.04
  4968.5  309.17  4977.7  308.32  4986.4  302.84  4991.9  302.78  4997.5  299.10
  4997.7  298.60  5001.2  298.60  5001.5  299.10  5009.8  302.29  5015.3  303.28
  5021.3  309.82  5044.1  309.47  5062.1  309.57  5067.5  310.01  5085.5  309.99
  5090.9  310.41  5141.1  311.64  5185.4  313.01  5192.3  313.61  5246.7  314.30
#Mann=5,-1,0
  4740.6    0.12       0  4813.2     0.1       0  4997.5    0.07       0
  5001.5     0.1       0  5141.1    0.05       0
Bank Sta=4997.5,5001.5
Exp/Cntr=0.3,0.1

Type RM Length L Ch R = 1,2052,293,293,293
BEGIN DESCRIPTION:
Walnut88 2.0
END DESCRIPTION:
XS GIS Cut Line= 4
      2734626.18      6738074.79      2735057.09      6738083.97
      2735276.00      6738011.00      2735525.99      6737961.00
#Sta/Elev= 30
  4342.1  322.18  4398.0  317.32  4403.0  317.60  4421.9  315.44  4441.9  313.98
  4461.9  313.53  4481.9  311.08  4512.0  309.43  4566.4  309.04  4636.4  309.71
  4740.7  309.20  4775.2  309.20  4951.2  307.17  4961.7  306.25  4972.2  300.07
  4980.8  298.18  4981.0  297.68  4984.5  297.68  4984.8  298.18  4993.3  304.44
  5001.2  306.78  5014.1  307.09  5034.4  308.54  5061.6  309.00  5085.4  310.63
  5095.6  312.17  5126.2  314.88  5146.6  315.63  5238.4  323.35  5258.8  325.99
#Mann=7,-1,0
  4342.1    0.12       0  4566.4     0.1       0  4636.4    0.12       0
  4740.7     0.1       0  4980.8    0.07       0  4984.8     0.1       0
  5061.6    0.05       0
Bank Sta=4980.8,4984.8
Exp/Cntr=0.3,0.1

Type RM Length L Ch R = 1,1759,193,193,193
BEGIN DESCRIPTION:
Walnut88 1.0
END DESCRIPTION:
XS GIS Cut Line= 3
      2734812.63      6738266.24      2735354.25      6738289.68
      2735515.71      6738261.03
#Sta/Elev= 30
  4485.8  310.79  4559.2  304.00  4599.3  305.36  4702.6  304.74  4789.5  303.35
  4859.5  303.24  4900.5  304.09  4949.6  303.40  4969.6  301.98  4979.6  303.77
  4989.6  302.77  4999.4  300.01  5009.7  296.87  5019.7  294.69  5024.3  292.98
  5024.5  292.48  5028.0  292.48  5028.3  292.98  5031.4  292.98  5039.9  303.42
  5046.9  303.76  5052.0  300.31  5070.3  303.71  5100.8  304.08  5111.1  305.90
  5141.4  308.48  5160.1  309.41  5165.1  310.81  5172.2  311.02  5191.9  312.96
#Mann=7,-1,0
  4485.8     0.1       0  4702.6    0.05       0  4900.5     0.1       0
  4999.4    0.12       0  5024.3    0.07       0  5028.3    0.12       0
  5172.2    0.05       0
Bank Sta=5024.3,5028.3
Exp/Cntr=0.3,0.1

Type RM Length L Ch R = 1,1566,181,181,181
BEGIN DESCRIPTION:
Walnut88 0.8
END DESCRIPTION:
XS GIS Cut Line= 4
      2734802.20      6738292.29      2735224.04      6738443.32
      2735276.56      6738478.11      2735460.00      6738479.35
#Sta/Elev= 30
  4537.6  312.46  4542.3  312.46  4573.2  308.79  4609.3  306.50  4634.8  303.38
  4665.5  304.46  4701.6  303.28  4776.3  302.60  4796.6  302.15  4844.8  303.06
  4870.3  302.85  4901.0  300.71  4907.5  301.01  4913.4  299.54  4937.1  299.07
  4962.6  300.54  4967.9  298.84  4977.1  298.07  4984.0  296.27  4992.3  295.60
  4998.0  291.86  4998.3  291.36  5001.8  291.36  5002.0  291.86  5007.3  297.00
  5013.3  299.42  5022.4  301.30  5098.1  300.65  5118.1  301.63  5232.1  302.27
#Mann=5,-1,0
  4537.6     0.1       0  4776.3    0.05       0  4907.5    0.12       0
  4998.0    0.07       0  5002.0    0.12       0
Bank Sta=4998,5002
Exp/Cntr=0.3,0.1

Type RM Length L Ch R = 1,1385,188,188,188
BEGIN DESCRIPTION:
Walnut88 0.7
END DESCRIPTION:
XS GIS Cut Line= 3
      2734862.04      6738380.81      2735091.23      6738555.30
      2735299.60      6738693.34
#Sta/Elev= 30
  4614.3  305.31  4638.8  303.48  4664.2  302.55  4682.1  300.88  4688.7  301.13
  4724.0  300.17  4753.1  300.41  4845.5  298.56  4888.2  298.51  4908.8  299.48
  4938.1  299.99  4954.0  299.86  4968.1  298.21  4975.0  291.28  4979.0  289.13
  4979.3  288.63  4982.8  288.63  4983.0  289.13  4990.1  291.24  4996.1  294.03
  5017.1  297.89  5026.2  298.30  5032.2  299.19  5040.0  298.34  5047.2  295.14
  5053.2  296.71  5062.3  297.67  5068.3  299.27  5098.4  300.16  5152.3  300.71
#Mann=5,-1,0
  4614.3     0.1       0  4664.2    0.05       0  4938.1    0.12       0
  4979.0    0.07       0  4983.0    0.12       0
Bank Sta=4979,4983
Exp/Cntr=0.3,0.1

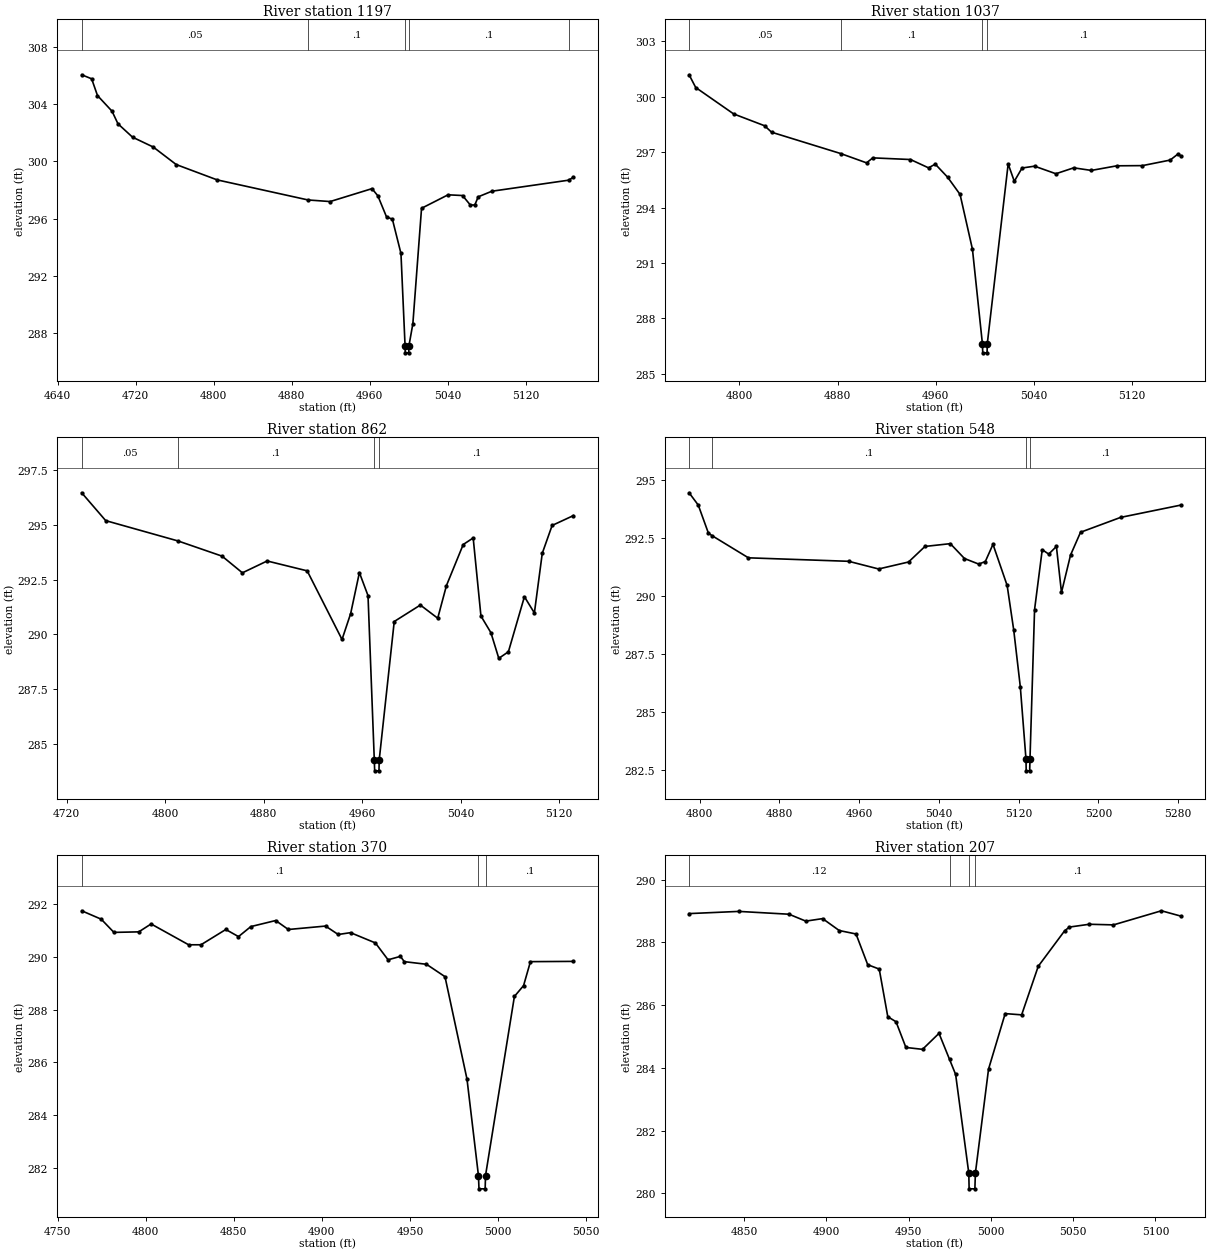
Type RM Length L Ch R = 1,1197,160,160,160
BEGIN DESCRIPTION:
Walnut88 0.5
END DESCRIPTION:
XS GIS Cut Line= 3
      2734833.44      6738430.33      2735059.98      6738763.63
      2735152.36      6738804.69
#Sta/Elev= 30
  4664.7  306.04  4674.9  305.76  4680.9  304.59  4695.8  303.50  4701.9  302.62
  4716.8  301.69  4738.1  301.00  4761.6  299.78  4803.6  298.71  4896.8  297.31
  4919.4  297.20  4962.3  298.10  4968.3  297.60  4977.2  296.13  4983.2  295.97
  4992.0  293.58  4996.2  287.15  4996.4  286.65  4999.9  286.65  5000.2  287.15
  5004.2  288.68  5013.1  296.73  5040.3  297.67  5055.1  297.62  5063.1  296.96
  5067.7  296.96  5071.2  297.53  5085.2  297.92  5163.9  298.69  5168.8  298.90
#Mann=5,-1,0
  4664.7    0.05       0  4896.8     0.1       0  4996.2    0.07       0
  5000.2     0.1       0  5163.9    0.12       0
Bank Sta=4996.2,5000.2
Exp/Cntr=0.3,0.1

Type RM Length L Ch R = 1,1037,175,175,175
BEGIN DESCRIPTION:
Walnut88 0.6
END DESCRIPTION:
XS GIS Cut Line= 4
      2734826.45      6738525.71      2734868.01      6738694.71
      2734884.63      6738808.31      2734953.50      6738896.46
#Sta/Elev= 30
  4759.0  301.19  4764.4  300.50  4795.3  299.07  4820.5  298.43  4826.2  298.08
  4882.7  296.92  4903.6  296.42  4908.7  296.69  4939.4  296.60  4954.1  296.15
  4959.6  296.35  4969.7  295.64  4979.8  294.71  4989.9  291.74  4998.0  286.63
  4998.3  286.13  5001.8  286.13  5002.0  286.63  5019.0  296.36  5024.0  295.42
  5030.3  296.14  5040.5  296.24  5057.9  295.83  5072.4  296.15  5086.8  296.01
  5107.6  296.26  5128.4  296.27  5151.0  296.57  5157.4  296.90  5159.7  296.79
#Mann=4,-1,0
  4759.0    0.05       0  4882.7     0.1       0  4998.0    0.07       0
  5002.0     0.1       0
Bank Sta=4998,5002
Exp/Cntr=0.3,0.1

Type RM Length L Ch R = 1,862,314,314,314
BEGIN DESCRIPTION:
Walnut88 0.3
END DESCRIPTION:
XS GIS Cut Line= 4
      2734646.36      6738611.63      2734668.52      6738780.60
      2734762.95      6738875.71      2734837.51      6738934.36
#Sta/Elev= 30
  4732.3  296.46  4751.8  295.19  4810.7  294.26  4846.3  293.57  4862.8  292.81
  4882.9  293.35  4915.4  292.90  4943.7  289.77  4950.7  290.95  4957.8  292.82
  4964.8  291.77  4969.9  284.28  4970.2  283.78  4973.7  283.78  4973.9  284.28
  4986.1  290.59  5007.3  291.34  5021.4  290.74  5028.5  292.23  5042.1  294.10
  5050.2  294.40  5056.5  290.84  5064.6  290.08  5071.0  288.91  5078.8  289.21
  5091.8  291.72  5099.9  290.98  5106.3  293.70  5114.3  294.97  5131.6  295.42
#Mann=4,-1,0
  4732.3    0.05       0  4810.7     0.1       0  4969.9    0.07       0
  4973.9     0.1       0
Bank Sta=4969.9,4973.9
Exp/Cntr=0.3,0.1

Type RM Length L Ch R = 1,548,178,178,178
BEGIN DESCRIPTION:
Walnut88 0.1
END DESCRIPTION:
XS GIS Cut Line= 5
      2734495.36      6738601.87      2734478.73      6738748.74
      2734474.58      6738838.79      2734578.70      6738928.35
      2734696.27      6738937.15
#Sta/Elev= 30
  4789.5  294.45  4798.7  293.92  4808.8  292.72  4812.3  292.61  4849.0  291.65
  4949.6  291.50  4979.6  291.17  5009.6  291.47  5026.1  292.14  5051.5  292.26
  5065.7  291.62  5080.0  291.38  5086.6  291.49  5094.3  292.23  5108.5  290.46
  5115.1  288.54  5121.7  286.10  5127.4  282.98  5127.6  282.48  5131.1  282.48
  5131.4  282.98  5136.0  289.42  5143.7  292.00  5150.2  291.81  5157.9  292.14
  5163.0  290.16  5172.1  291.77  5182.1  292.75  5222.3  293.39  5282.7  293.92
#Mann=4,-1,0
  4789.5    0.05       0  4812.3     0.1       0  5127.4    0.07       0
  5131.4     0.1       0
Bank Sta=5127.4,5131.4
Exp/Cntr=0.3,0.1

Type RM Length L Ch R = 1,370,163,163,163
BEGIN DESCRIPTION:
Walnut88 0.06
END DESCRIPTION:
XS GIS Cut Line= 4
      2734452.40      6738611.60      2734320.81      6738739.04
      2734298.64      6738808.31      2734301.20      6738831.35
#Sta/Elev= 30
  4763.7  291.75  4774.8  291.43  4782.0  290.93  4796.1  290.95  4803.1  291.25
  4824.4  290.46  4831.4  290.46  4845.5  291.04  4852.7  290.77  4859.7  291.15
  4873.8  291.38  4881.0  291.04  4902.1  291.17  4909.3  290.85  4916.3  290.92
  4930.4  290.53  4937.6  289.89  4944.6  290.02  4946.8  289.82  4959.4  289.72
  4969.9  289.25  4982.4  285.36  4988.9  281.70  4989.2  281.20  4992.7  281.20
  4992.9  281.70  5009.3  288.50  5014.5  288.91  5018.4  289.82  5042.8  289.83
#Mann=3,-1,0
  4763.7     0.1       0  4988.9    0.07       0  4992.9     0.1       0
Bank Sta=4988.9,4992.9
Exp/Cntr=0.3,0.1

Type RM Length L Ch R = 1,207,101,101,101
BEGIN DESCRIPTION:
Walnut88 0.03
END DESCRIPTION:
XS GIS Cut Line= 4
      2734180.89      6738531.25      2734160.11      6738644.84
      2734171.19      6738759.82      2734197.53      6738822.20
#Sta/Elev= 30
  4816.7  288.92  4846.9  288.99  4877.4  288.90  4887.6  288.68  4897.8  288.76
  4907.9  288.38  4918.1  288.27  4925.2  287.29  4932.2  287.15  4937.4  285.63
  4942.4  285.47  4948.4  284.65  4958.5  284.59  4968.5  285.10  4974.9  284.27
  4978.6  283.79  4986.6  280.64  4986.8  280.14  4990.3  280.14  4990.6  280.64
  4998.6  283.96  5008.7  285.73  5018.7  285.69  5028.8  287.24  5044.8  288.37
  5047.7  288.49  5059.8  288.58  5074.5  288.56  5103.6  289.01  5115.4  288.84
#Mann=4,-1,0
  4816.7    0.12       0  4974.9     0.1       0  4986.6    0.07       0
  4990.6     0.1       0
Bank Sta=4986.6,4990.6
Exp/Cntr=0.3,0.1

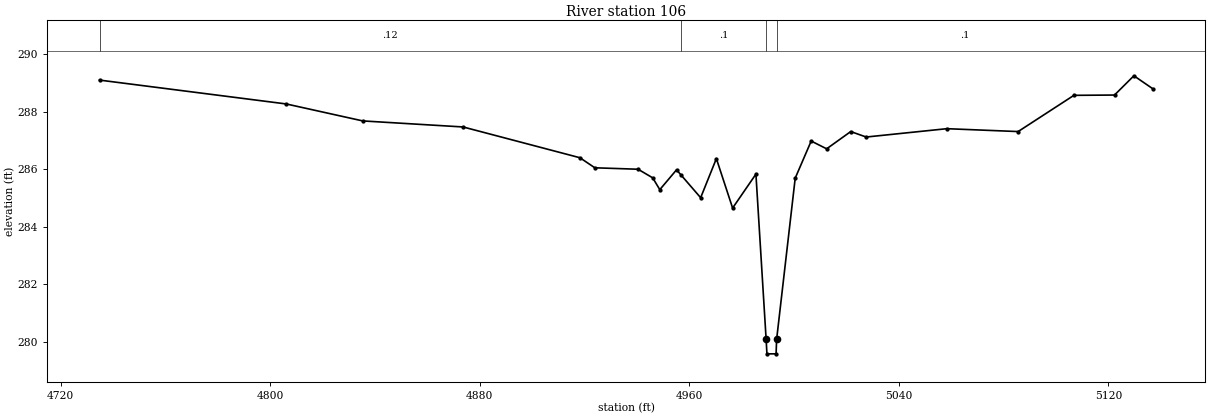
Type RM Length L Ch R = 1,106,0,0,0
BEGIN DESCRIPTION:
Walnut88 0.01
END DESCRIPTION:
XS GIS Cut Line= 4
      2734137.56      6738487.64      2734039.40      6738677.73
      2734089.46      6738754.28      2734172.17      6738804.36
#Sta/Elev= 30
  4734.8  289.10  4806.1  288.27  4835.3  287.68  4873.6  287.47  4918.2  286.40
  4923.9  286.05  4940.4  286.00  4946.0  285.70  4948.7  285.29  4955.1  285.98
  4956.8  285.80  4964.3  285.01  4970.3  286.37  4976.5  284.65  4985.4  285.83
  4989.3  280.08  4989.6  279.58  4993.1  279.58  4993.3  280.08  5000.4  285.69
  5006.5  286.98  5012.4  286.71  5021.6  287.31  5027.5  287.12  5058.3  287.41
  5085.5  287.31  5106.8  288.57  5122.3  288.58  5129.7  289.25  5136.9  288.80
#Mann=4,-1,0
  4734.8    0.12       0  4956.8     0.1       0  4989.3    0.07       0
  4993.3     0.1       0
Bank Sta=4989.3,4993.3
Exp/Cntr=0.3,0.1

Chan Stop Cuts=-1