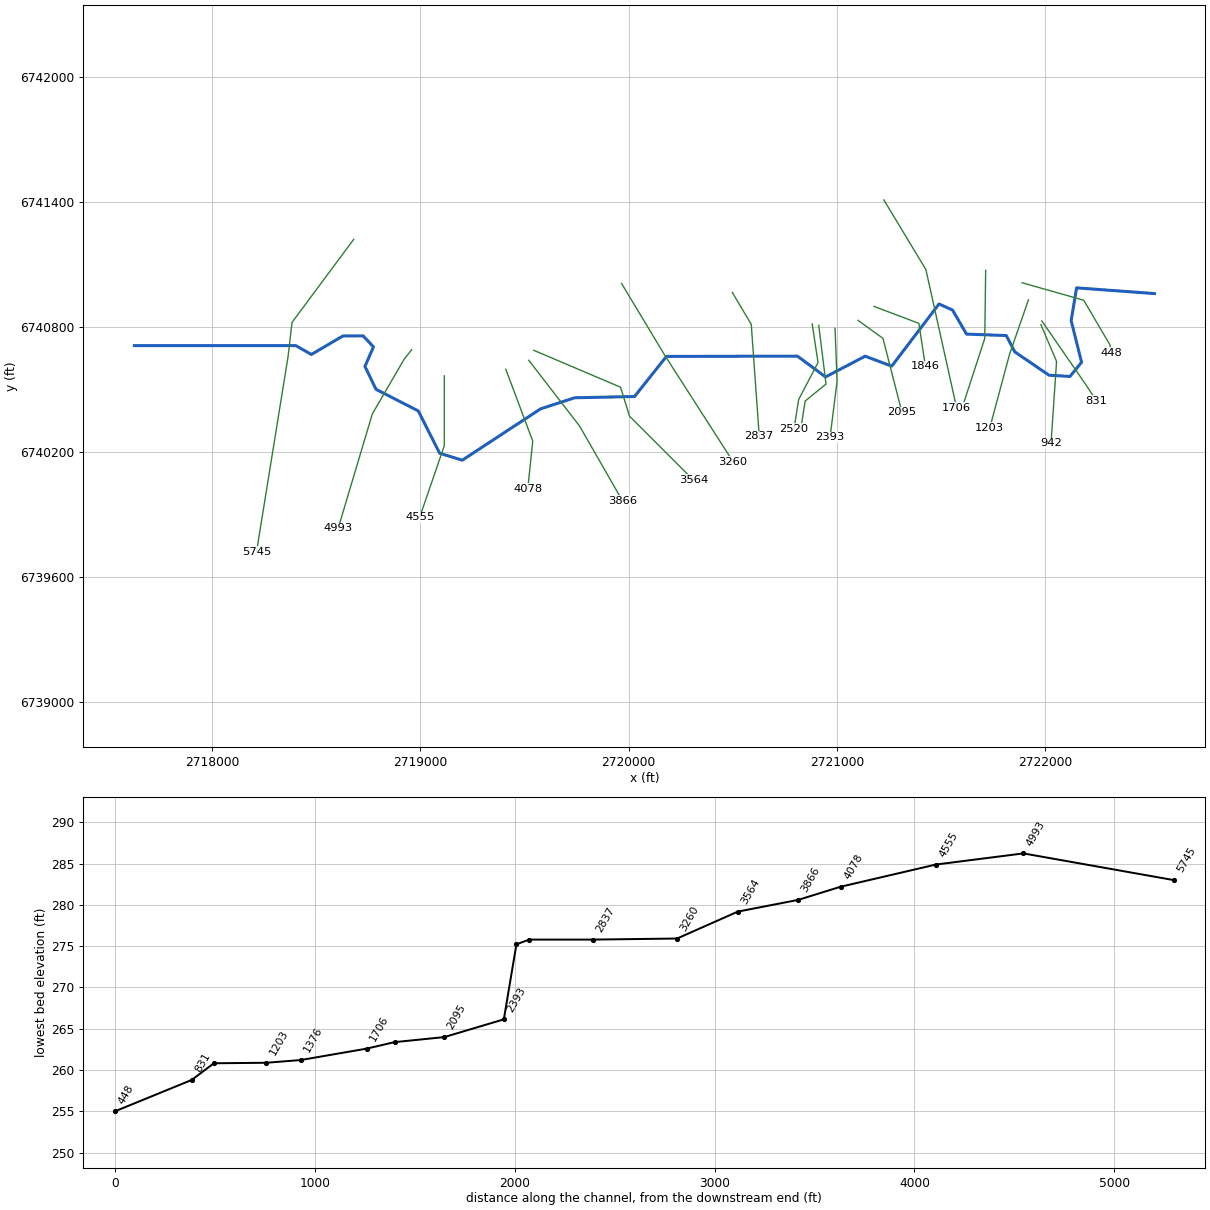
--- Walnut9.prj (project) ---

Proj Title=Walnut9 Base Level Engineering
Current Plan=p01
Default Exp/Contr=0.3,0.1
English Units
Geom File=g01
Flow File=f01
Plan File=p01
Y Axis Title=Elevation
X Axis Title(PF)=Main Channel Distance
X Axis Title(XS)=Station
BEGIN DESCRIPTION:
Walnut9
END DESCRIPTION:
DSS Export Rating Curves= 0
DSS Export Rating Curve Sorted= 0
DSS Export Volume Flow Curves= 0
DXF OffsetX= 0
DXF OffsetY= 0
DXF ScaleX= 1
DXF ScaleY= 10

--- Walnut9.p01 (plan) ---

Plan Title=Multiple Run
Program Version=4.10
Short Identifier=Multiple
Geom File=g01
Flow File=f01
Subcritical Flow
K Sum by GR= 0
Std Step Tol= 0.01
Critical Tol= 0.01
Num of Std Step Trials= 20
Max Error Tol= 0.3
Flow Tol Ratio= 0.001
Split Flow NTrial= 30
Split Flow Tol= 0.02
Split Flow Ratio= 0.02
Log Output Level= 0
Friction Slope Method= 1
Unsteady Friction Slope Method= 2
Unsteady Bridges Friction Slope Method= 1
Parabolic Critical Depth
Global Vel Dist= 1 , 1 , 1
Global Log Level= 0
CheckData=True
Encroach Param=-1 ,0,0, 0
BEGIN DESCRIPTION:
Multiple Run
END DESCRIPTION:
Computation Interval=1HOUR
Output Interval=1HOUR
Run HTab= 0
Run UNet= 0
Run PostProcess= 0
Run WQNet= 0
UNET Theta= 1
UNET Theta Warmup= 1
UNET ZTol= 0.02
UNET ZSATol= 0.05
UNET MxIter= 20
UNET MaxInSteps= 0
UNET DtIC= 0
UNET DtMin= 0
UNET MaxCRTS= 20
UNET WFStab= 2
UNET SFStab= 1
UNET WFX= 1
UNET SFX= 1
UNET DSS MLevel= 4
UNET DZMax Abort= 100
UNET Convert EG Bridges= 0
UNET Use Existing IB Tables=-1
UNET Froude Reduction=False
UNET Froude Limit= 1
UNET Froude Power= 10
UNET Time Slicing=0,0, 5
UNET Junction Losses=0
Instantaneous Interval=1HOUR
Write IC File= 0
Write IC File at Sim End=0
Echo Input=False
Echo Parameters=False
Echo Output=False
Write Detailed= 0
WQ AD Non Conservative
WQ ULTIMATE=-1
WQ Max Comp Step=1HOUR
WQ Output Interval=15MIN
WQ Output Selected Increments= 0
WQ Output face flow=0
WQ Output face velocity=0
WQ Output face area=0
WQ Output face dispersion=0
WQ Output cell volume=0
WQ Output cell surface area=0
WQ Output cell continuity=0
WQ Output cumulative cell continuity=0
WQ Output face conc=0
WQ Output face dconc_dx=0
WQ Output face courant=0
WQ Output face peclet=0
WQ Output face adv mass=0
WQ Output face disp mass=0
WQ Output cell mass=0
WQ Output cell source sink temp=0
WQ Output cell source sink nsm=0
WQ Output MaxMinRange=-1
WQ Daily Max Min Mean=-1
WQ Daily Range=0
WQ Daily Time=0
WQ Create Restart=0
WQ Fixed Restart=0
WQ System Summary=0
WQ Use Fixed Temperature=0
Sorting and Armoring Iterations= 10
XS Update Threshold= 0.02
Hydraulics Update Threshold= 0.02
Energy Slope Method= 1
Volume Change Method= 0
XS Weighting Method= 0
Number of US Weighted Cross Sections= 1
Number of DS Weighted Cross Sections= 1
Upstream XS Weight=0.25
Main XS Weight=0.5
Downstream XS Weight=0.25
Number of DS XS's Weighted with US Boundary= 1
Upstream Boundary Weight= 1
Weight of XSs Associated with US Boundary= 0
Number of US XS's Weighted with DS Boundary= 1
Downstream Boundary Weight= 0.5
Weight of XSs Associated with DS Boundary= 0.5
Sediment Output Level= 4
Mass or Volume Output= 0
Output Increment Type= 1
Profile and TS Output Increment= 10
XS Output Flag= 0
XS Output Increment= 10
Disregard all LS=0
Disregard all Conn=0
Disregard all Breaches=0
Disregard all Pumps=0

--- Walnut9.f01 (steady flow) ---

Flow Title=Multiple
Number of Profiles=7
Profile Names=10-year,25-year,50-year,1pct_min,100-year,1pct_plu,500-year
River Rch & RM= Walnut9,Reach-1,5745
     239     295     337     190     380     758     485
River Rch & RM= Walnut9,Reach-1,3564
     497     650     770     452     903    1801    1243
Boundary for River Rch & Prof#=Walnut9,Reach-1,1
Up Type=0
Dn Type=3
Dn Slope=0.005
Boundary for River Rch & Prof#=Walnut9,Reach-1,2
Up Type=0
Dn Type=3
Dn Slope=0.005
Boundary for River Rch & Prof#=Walnut9,Reach-1,3
Up Type=0
Dn Type=3
Dn Slope=0.005
Boundary for River Rch & Prof#=Walnut9,Reach-1,4
Up Type=0
Dn Type=3
Dn Slope=0.005
Boundary for River Rch & Prof#=Walnut9,Reach-1,5
Up Type=0
Dn Type=3
Dn Slope=0.005
Boundary for River Rch & Prof#=Walnut9,Reach-1,6
Up Type=0
Dn Type=3
Dn Slope=0.005
Boundary for River Rch & Prof#=Walnut9,Reach-1,7
Up Type=0
Dn Type=3
Dn Slope=0.005

--- Walnut9.g01 (geometry) ---

Geom Title=Existing Conditions

River Reach=Walnut9,Reach-1
Reach XY= 30
      2717626.00      6740711.00      2718401.12      6740711.11
      2718476.01      6740668.53      2718627.59      6740757.33
      2718724.78      6740757.63      2718774.43      6740705.16
      2718733.56      6740611.00      2718786.61      6740501.00
      2718989.57      6740397.53      2719092.45      6740193.85
      2719200.99      6740160.57      2719577.50      6740407.38
      2719741.22      6740460.48      2720028.47      6740466.45
      2720181.67      6740659.02      2720810.84      6740660.61
      2720946.13      6740560.60      2721136.69      6740660.24
      2721263.98      6740612.20      2721491.29      6740911.19
      2721556.36      6740881.68      2721623.30      6740766.36
      2721814.17      6740759.36      2721855.57      6740680.74
      2722019.84      6740568.77      2722120.31      6740562.87
      2722176.11      6740630.87      2722126.05      6740831.04
      2722152.03      6740988.50      2722526.00      6740961.00

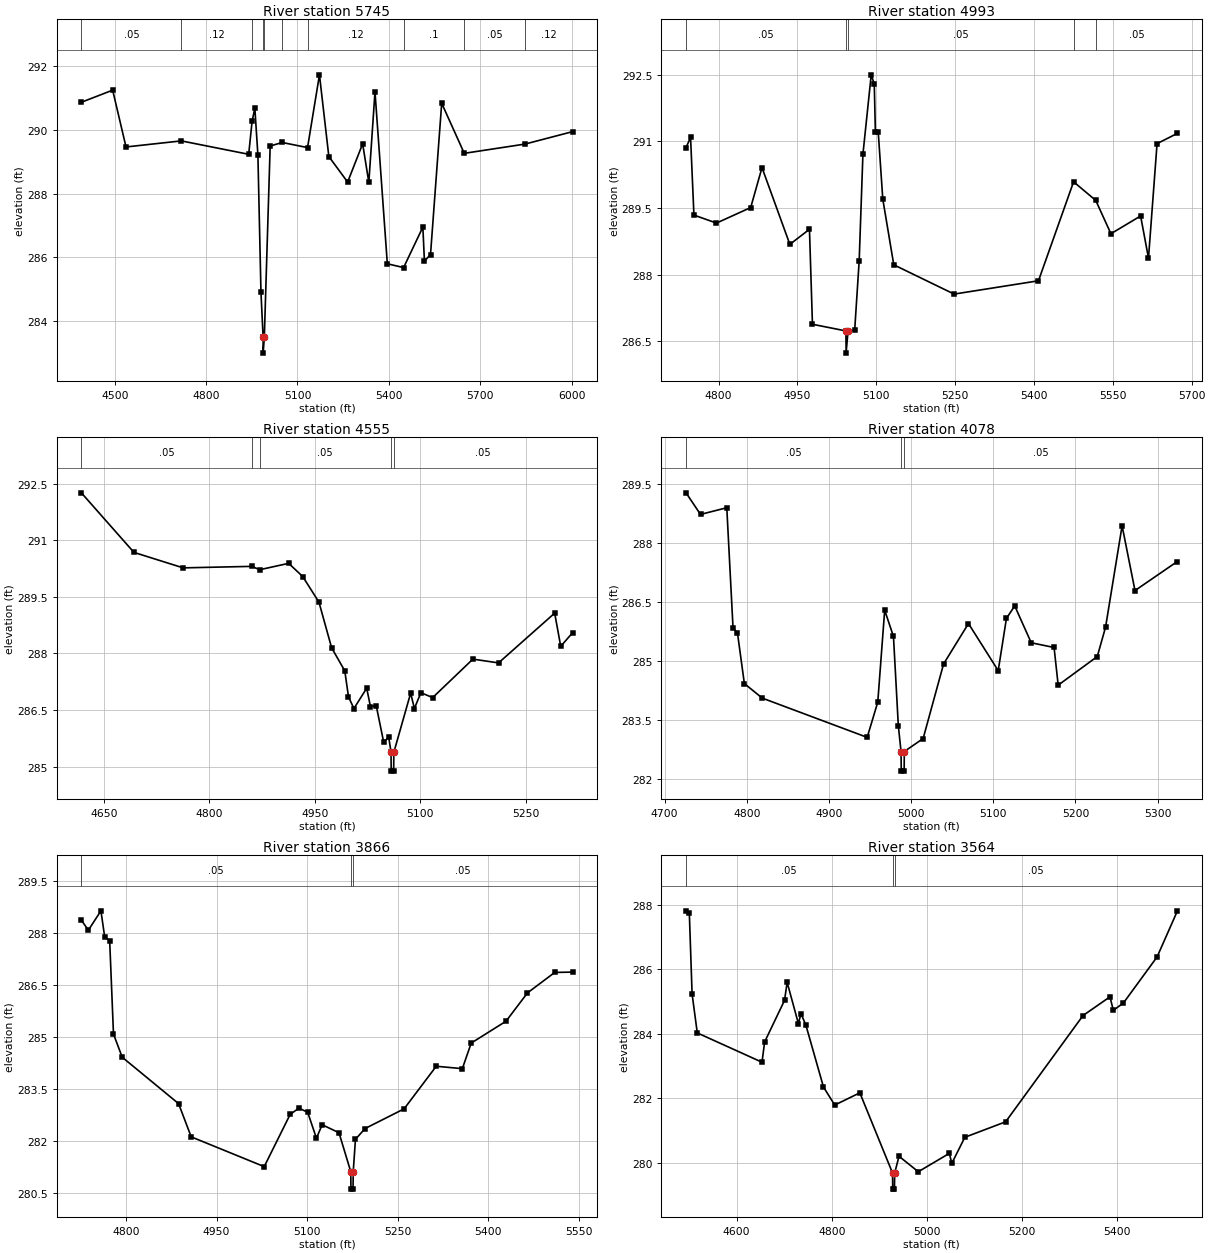
Type RM Length L Ch R = 1,5745,752,752,752
BEGIN DESCRIPTION:
Walnut9 10.5
END DESCRIPTION:
XS GIS Cut Line= 4
      2718679.71      6741221.98      2718382.94      6740822.19
      2718364.18      6740658.73      2718212.64      6739720.52
#Sta/Elev= 30
  4390.5  290.86  4493.3  291.24  4537.1  289.46  4718.7  289.65  4939.9  289.23
  4951.1  290.27  4960.1  290.67  4970.1  289.21  4980.2  284.90  4987.2  283.50
  4987.4  283.00  4991.2  283.50  5010.4  289.49  5050.0  289.60  5133.1  289.44
  5172.2  291.72  5203.0  289.16  5264.7  288.36  5314.0  289.56  5334.3  288.35
  5354.5  291.19  5395.0  285.80  5448.4  285.68  5511.7  286.95  5516.8  285.88
  5536.8  286.09  5573.5  290.83  5647.6  289.26  5846.9  289.55  6003.3  289.94
#Mann=10,-1,0
  4390.5    0.05       0  4718.7    0.12       0  4951.1    0.05       0
  4987.2    0.04       0  4991.2    0.05       0  5050.0     0.1       0
  5133.1    0.12       0  5448.4     0.1       0  5647.6    0.05       0
  5846.9    0.12       0
Bank Sta=4987.2,4991.2
Exp/Cntr=0.3,0.1

Type RM Length L Ch R = 1,4993,438,438,438
BEGIN DESCRIPTION:
Walnut9 10.0
END DESCRIPTION:
XS GIS Cut Line= 4
      2718957.67      6740691.12      2718921.58      6740645.33
      2718768.84      6740382.71      2718605.11      6739834.13
#Sta/Elev= 30
  4738.1  290.86  4746.7  291.09  4753.1  289.34  4796.0  289.16  4861.1  289.51
  4882.6  290.41  4935.6  288.68  4972.9  289.02  4978.6  286.88  5042.3  286.73
  5042.6  286.23  5046.3  286.73  5058.9  286.74  5067.5  288.31  5074.6  290.71
  5090.4  292.50  5096.2  292.29  5098.3  291.22  5103.7  291.22  5112.4  289.70
  5133.3  288.22  5248.1  287.56  5408.6  287.86  5475.4  290.09  5517.6  289.67
  5546.4  288.92  5602.9  289.32  5617.9  288.37  5634.2  290.95  5672.7  291.18
#Mann=5,-1,0
  4738.1    0.05       0  5042.3    0.04       0  5046.3    0.05       0
  5475.4    0.12       0  5517.6    0.05       0
Bank Sta=5042.3,5046.3
Exp/Cntr=0.3,0.1

Type RM Length L Ch R = 1,4555,477,477,477
BEGIN DESCRIPTION:
Walnut9 9.5
END DESCRIPTION:
XS GIS Cut Line= 3
      2719114.87      6740565.80      2719114.53      6740229.96
      2718996.60      6739886.90
#Sta/Elev= 30
  4618.0  292.26  4692.8  290.68  4762.8  290.27  4860.7  290.31  4871.4  290.22
  4912.8  290.39  4932.8  290.04  4955.9  289.36  4973.9  288.15  4992.6  287.54
  4997.9  286.85  5005.6  286.54  5023.8  287.08  5029.1  286.59  5037.3  286.62
  5047.9  285.65  5055.1  285.78  5058.4  285.38  5058.6  284.88  5062.1  284.88
  5062.4  285.38  5086.3  286.95  5091.6  286.54  5100.8  286.96  5117.6  286.83
  5174.8  287.85  5211.3  287.75  5291.1  289.07  5299.7  288.19  5316.6  288.55
#Mann=5,-1,0
  4618.0    0.05       0  4860.7    0.12       0  4871.4    0.05       0
  5058.4    0.04       0  5062.4    0.05       0
Bank Sta=5058.4,5062.4
Exp/Cntr=0.3,0.1

Type RM Length L Ch R = 1,4078,212,212,212
BEGIN DESCRIPTION:
Walnut9 9.2
END DESCRIPTION:
XS GIS Cut Line= 3
      2719410.11      6740597.44      2719539.51      6740252.37
      2719515.74      6740024.14
#Sta/Elev= 30
  4726.0  289.28  4743.6  288.73  4775.6  288.90  4783.2  285.84  4788.6  285.71
  4797.0  284.42  4818.8  284.05  4946.5  283.05  4959.4  283.95  4967.8  286.29
  4978.5  285.62  4984.4  283.35  4987.7  282.69  4988.0  282.19  4991.5  282.19
  4991.7  282.69  5014.6  283.02  5039.5  284.92  5069.8  285.95  5106.0  284.75
  5116.0  286.08  5126.1  286.40  5146.2  285.46  5174.0  285.34  5179.0  284.38
  5226.6  285.11  5236.7  285.86  5256.8  288.44  5272.5  286.79  5324.0  287.53
#Mann=3,-1,0
  4726.0    0.05       0  4987.7    0.03       0  4991.7    0.05       0
Bank Sta=4987.7,4991.7
Exp/Cntr=0.3,0.1

Type RM Length L Ch R = 1,3866,302,302,302
BEGIN DESCRIPTION:
Walnut9 9.0
END DESCRIPTION:
XS GIS Cut Line= 3
      2719520.35      6740640.60      2719764.79      6740324.27
      2719970.57      6739965.35
#Sta/Elev= 30
  4726.0  288.37  4737.6  288.08  4758.4  288.64  4764.7  287.88  4772.9  287.78
  4779.2  285.08  4793.7  284.41  4887.0  283.07  4907.9  282.11  5028.8  281.25
  5071.8  282.76  5086.3  282.94  5100.8  282.82  5115.3  282.07  5124.7  282.46
  5152.6  282.23  5172.2  281.10  5172.4  280.60  5175.9  280.60  5176.2  281.10
  5179.9  282.04  5195.8  282.35  5260.5  282.92  5313.7  284.15  5356.9  284.08
  5371.6  284.82  5429.2  285.45  5464.8  286.27  5509.9  286.86  5539.5  286.87
#Mann=3,-1,0
  4726.0    0.05       0  5172.2    0.03       0  5176.2    0.05       0
Bank Sta=5172.2,5176.2
Exp/Cntr=0.3,0.1

Type RM Length L Ch R = 1,3564,304,304,304
BEGIN DESCRIPTION:
Walnut9 8.0
END DESCRIPTION:
XS GIS Cut Line= 4
      2719544.29      6740688.56      2719961.31      6740511.21
      2720004.45      6740372.20      2720310.83      6740065.82
#Sta/Elev= 30
  4493.8  287.82  4500.7  287.75  4506.5  285.24  4517.4  284.03  4653.4  283.12
  4658.9  283.75  4700.7  285.04  4706.2  285.60  4729.8  284.32  4735.2  284.63
  4745.6  284.27  4782.5  282.35  4806.2  281.79  4858.9  282.17  4927.6  279.68
  4928.0  279.18  4931.6  279.18  4932.1  279.68  4941.2  280.20  4981.7  279.72
  5046.9  280.29  5052.1  279.98  5079.5  280.79  5165.2  281.27  5327.8  284.57
  5384.4  285.15  5391.4  284.73  5412.7  284.96  5483.4  286.39  5525.8  287.81
#Mann=3,-1,0
  4493.8    0.05       0  4927.6    0.04       0  4932.1    0.05       0
Bank Sta=4927.6,4932.1
Exp/Cntr=0.3,0.1

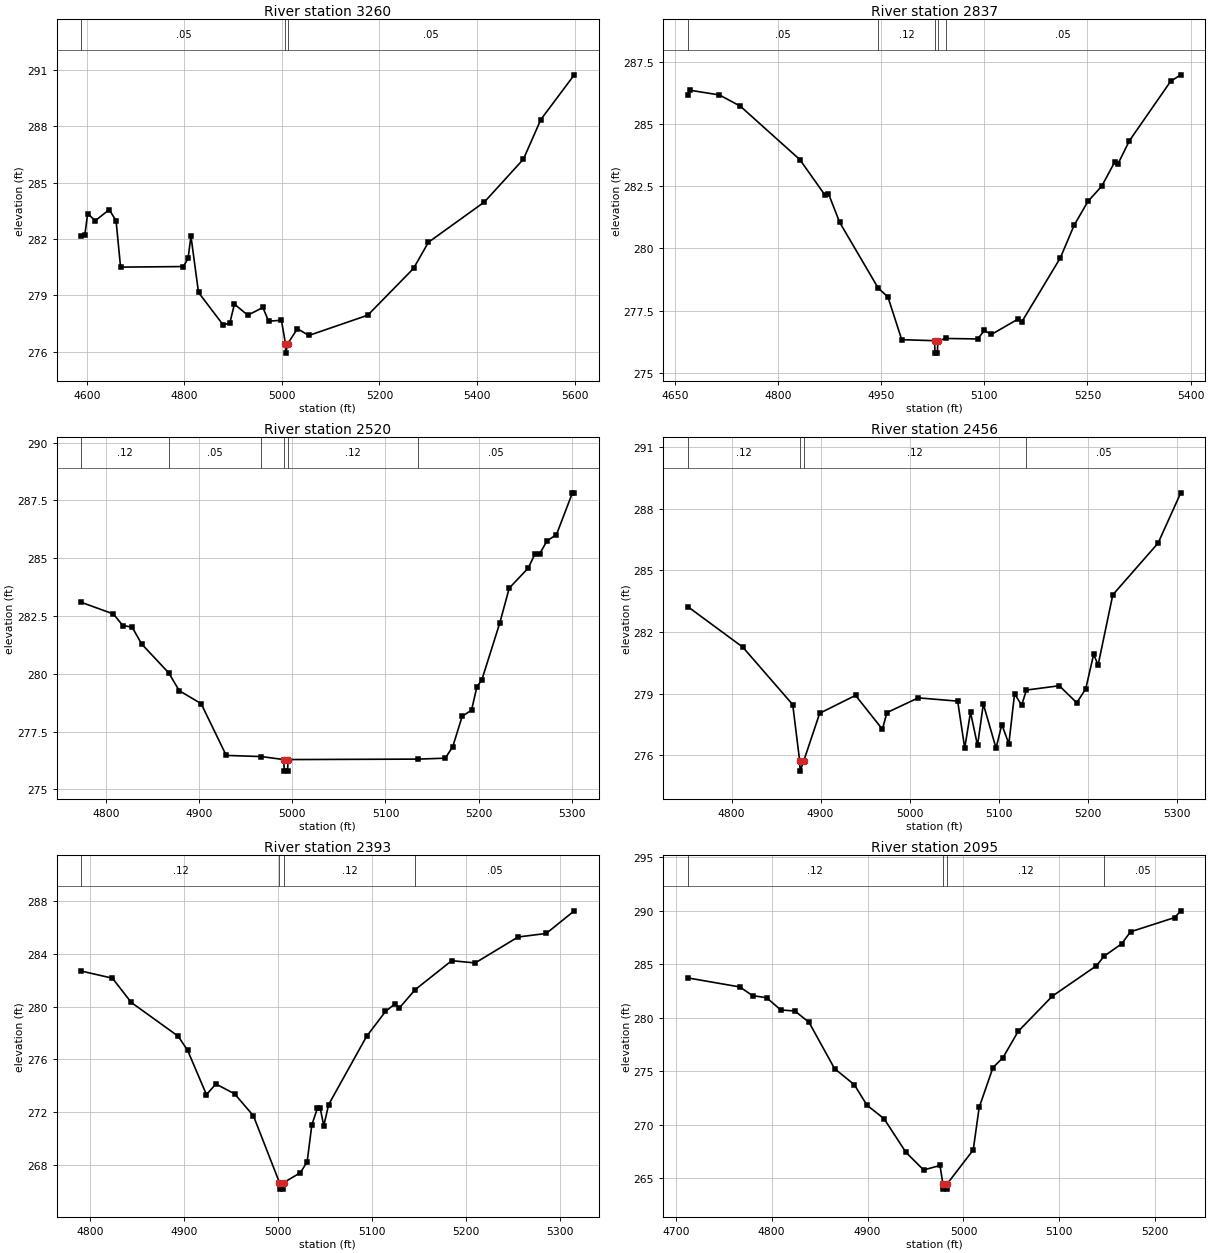
Type RM Length L Ch R = 1,3260,423,423,423
BEGIN DESCRIPTION:
Walnut9 7.0
END DESCRIPTION:
XS GIS Cut Line= 3
      2719966.10      6741009.72      2720176.00      6740661.00
      2720501.97      6740153.24
#Sta/Elev= 30
  4589.2  282.15  4596.1  282.20  4602.0  283.35  4617.5  282.97  4646.1  283.56
  4660.2  282.97  4669.4  280.50  4798.1  280.53  4807.8  280.96  4813.7  282.15
  4829.2  279.15  4879.5  277.43  4893.3  277.51  4902.8  278.53  4930.2  277.94
  4961.2  278.35  4972.9  277.62  4999.2  277.67  5007.5  276.42  5008.0  275.92
  5012.1  276.42  5031.9  277.22  5055.3  276.86  5176.2  277.94  5270.0  280.43
  5300.4  281.82  5415.4  283.97  5495.3  286.25  5531.0  288.36  5599.6  290.74
#Mann=3,-1,0
  4589.2    0.05       0  5007.5    0.05       0  5012.1    0.05       0
Bank Sta=5007.5,5012.1
Exp/Cntr=0.3,0.1

Type RM Length L Ch R = 1,2837,317,317,317
BEGIN DESCRIPTION:
Walnut9 6.0
END DESCRIPTION:
XS GIS Cut Line= 3
      2720498.17      6740966.54      2720589.23      6740813.18
      2720627.58      6740276.30
#Sta/Elev= 30
  4669.1  286.17  4672.2  286.36  4715.0  286.17  4745.3  285.72  4831.9  283.57
  4868.5  282.14  4873.5  282.20  4889.7  281.05  4945.9  278.40  4959.9  278.05
  4980.0  276.33  5027.8  276.29  5028.3  275.79  5031.9  275.79  5032.4  276.29
  5044.0  276.38  5090.2  276.36  5100.3  276.70  5110.3  276.54  5149.2  277.16
  5154.2  277.03  5210.6  279.62  5230.6  280.93  5250.7  281.89  5270.7  282.50
  5289.6  283.47  5294.6  283.41  5310.8  284.32  5371.0  286.72  5385.7  286.98
#Mann=5,-1,0
  4669.1    0.05       0  4945.9    0.12       0  5027.8    0.07       0
  5032.4    0.12       0  5044.0    0.05       0
Bank Sta=5027.8,5032.4
Exp/Cntr=0.3,0.1

Type RM Length L Ch R = 1,2520,64,64,64
BEGIN DESCRIPTION:
Walnut9 5.2
END DESCRIPTION:
XS GIS Cut Line= 4
      2720882.07      6740814.88      2720910.01      6740629.81
      2720816.87      6740451.68      2720794.75      6740312.00
#Sta/Elev= 30
  4773.3  283.09  4807.6  282.59  4817.7  282.09  4827.8  282.02  4838.0  281.29
  4867.1  280.04  4878.4  279.27  4901.9  278.71  4928.9  276.47  4966.6  276.42
  4990.7  276.29  4991.2  275.79  4994.8  275.79  4995.3  276.29  5134.9  276.31
  5164.3  276.35  5172.3  276.85  5182.4  278.16  5192.5  278.43  5198.3  279.45
  5203.4  279.72  5222.9  282.21  5233.0  283.71  5253.3  284.57  5260.6  285.18
  5265.7  285.19  5273.5  285.75  5283.7  286.02  5300.9  287.83  5302.9  287.83
#Mann=6,-1,0
  4773.3    0.12       0  4867.1    0.05       0  4966.6    0.12       0
  4990.7    0.07       0  4995.3    0.12       0  5134.9    0.05       0
Bank Sta=4990.7,4995.3
Exp/Cntr=0.3,0.1

Type RM Length L Ch R = 1,2456,63,63,63
BEGIN DESCRIPTION:
Walnut9 5.1
END DESCRIPTION:
XS GIS Cut Line= 4
      2720913.50      6740807.95      2720948.43      6740526.19
      2720848.30      6740444.70      2720826.27      6740305.54
#Sta/Elev= 30
  4750.9  283.23  4812.6  281.26  4868.7  278.46  4876.5  275.72  4877.0  275.22
  4881.1  275.72  4899.0  278.04  4939.3  278.91  4969.5  277.26  4974.5  278.07
  5009.8  278.79  5054.1  278.63  5062.0  276.34  5068.5  278.09  5076.4  276.47
  5082.9  278.49  5097.2  276.34  5103.7  277.49  5111.6  276.55  5118.0  278.99
  5126.0  278.43  5131.3  279.17  5168.3  279.38  5187.9  278.55  5198.0  279.23
  5206.9  280.91  5211.9  280.39  5228.4  283.81  5279.3  286.33  5304.8  288.78
#Mann=4,-1,0
  4750.9    0.12       0  4876.5    0.07       0  4881.1    0.12       0
  5131.3    0.05       0
Bank Sta=4876.5,4881.1
Exp/Cntr=0.3,0.1

Type RM Length L Ch R = 1,2393,298,298,298
BEGIN DESCRIPTION:
Walnut9 5.0
END DESCRIPTION:
XS GIS Cut Line= 3
      2720991.86      6740793.97      2721001.44      6740539.96
      2720967.89      6740271.54
#Sta/Elev= 30
  4790.4  282.70  4823.4  282.16  4843.4  280.32  4893.4  277.75  4903.4  276.68
  4923.5  273.31  4933.5  274.12  4953.5  273.37  4973.5  271.70  5001.2  266.63
  5001.7  266.13  5005.4  266.13  5005.8  266.63  5023.5  267.38  5030.7  268.21
  5035.7  271.02  5041.6  272.27  5044.6  272.27  5048.4  270.95  5053.6  272.56
  5093.9  277.73  5114.1  279.63  5124.0  280.20  5129.0  279.91  5145.7  281.29
  5184.6  283.49  5209.6  283.32  5255.2  285.29  5285.2  285.56  5315.1  287.28
#Mann=4,-1,0
  4790.4    0.12       0  5001.2    0.07       0  5005.8    0.12       0
  5145.7    0.05       0
Bank Sta=5001.2,5005.8
Exp/Cntr=0.3,0.1

Type RM Length L Ch R = 1,2095,249,249,249
BEGIN DESCRIPTION:
Walnut9 4.5
END DESCRIPTION:
XS GIS Cut Line= 3
      2721102.09      6740832.36      2721221.93      6740746.07
      2721313.01      6740391.35
#Sta/Elev= 30
  4712.7  283.71  4766.8  282.87  4780.1  282.06  4794.8  281.86  4809.5  280.72
  4824.3  280.62  4839.0  279.56  4865.6  275.24  4886.3  273.73  4899.3  271.83
  4917.2  270.56  4940.0  267.42  4958.5  265.77  4975.6  266.19  4978.5  264.48
  4978.9  263.98  4982.6  263.98  4983.1  264.48  5010.2  267.64  5016.4  271.61
  5030.8  275.34  5041.1  276.25  5057.1  278.72  5092.7  282.01  5138.7  284.85
  5146.6  285.74  5165.0  286.90  5174.2  288.02  5220.2  289.35  5226.6  289.98
#Mann=4,-1,0
  4712.7    0.12       0  4978.5    0.07       0  4983.1    0.12       0
  5146.6    0.05       0
Bank Sta=4978.5,4983.1
Exp/Cntr=0.3,0.1

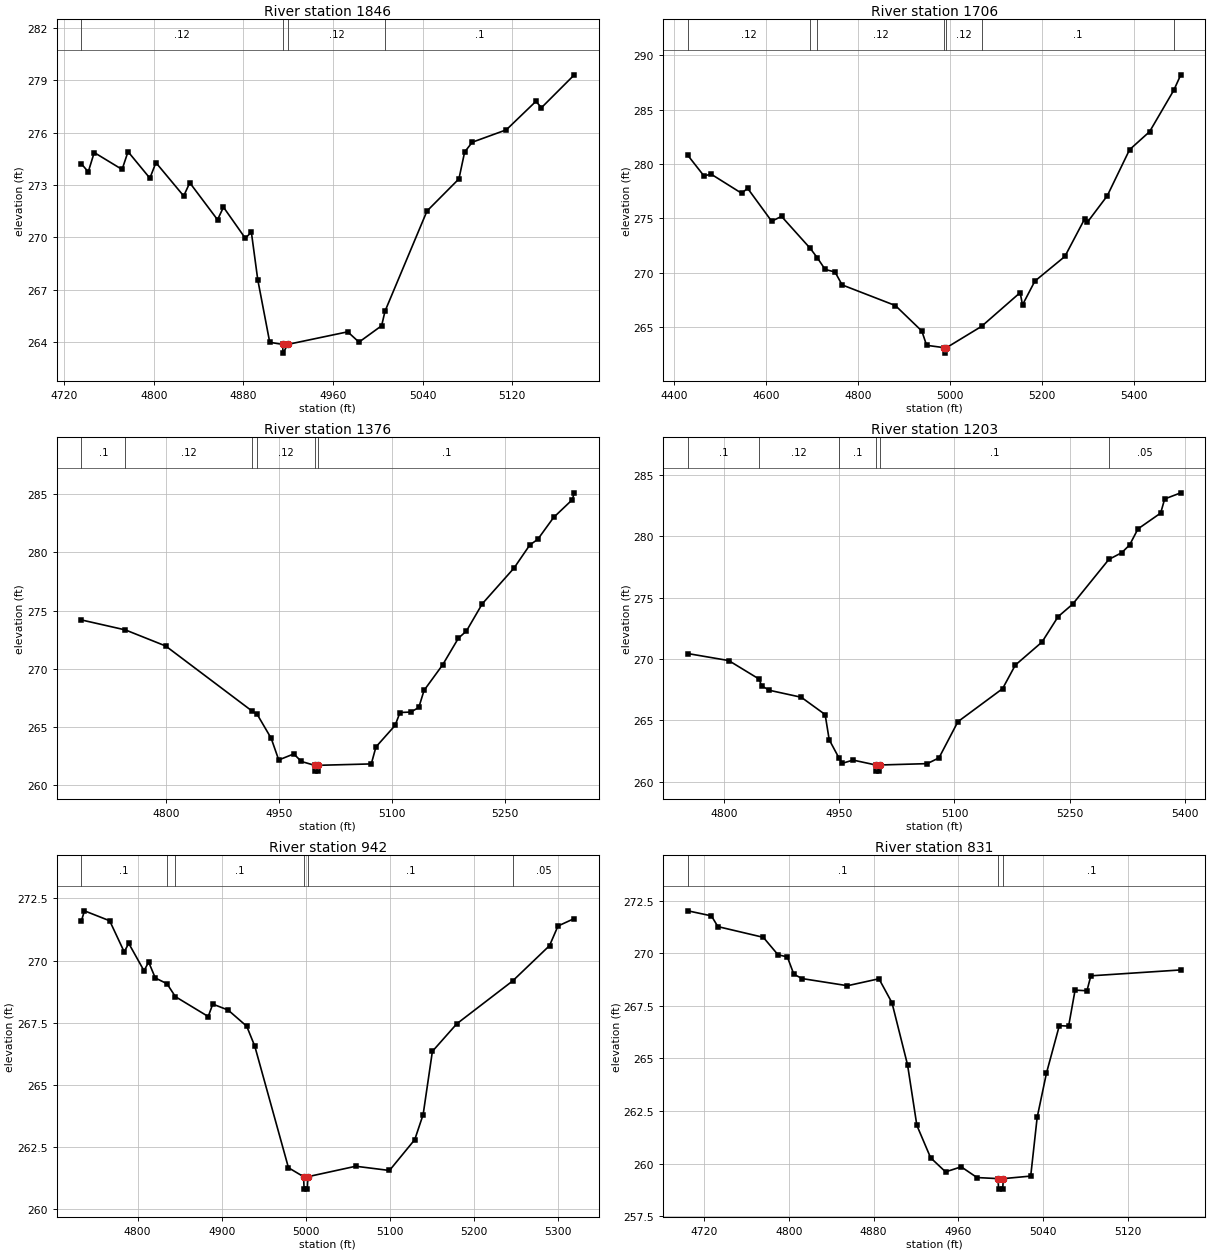
Type RM Length L Ch R = 1,1846,140,140,140
BEGIN DESCRIPTION:
Walnut9 4.0
END DESCRIPTION:
XS GIS Cut Line= 3
      2721178.76      6740899.47      2721394.49      6740817.97
      2721426.01      6740610.96
#Sta/Elev= 30
  4735.4  274.21  4741.5  273.75  4746.8  274.86  4771.7  273.89  4777.0  274.91
  4796.5  273.39  4801.9  274.28  4826.7  272.37  4832.1  273.13  4856.9  271.01
  4862.2  271.73  4881.7  269.95  4887.1  270.30  4892.8  267.58  4903.5  263.99
  4915.0  263.87  4915.4  263.37  4919.6  263.87  4973.1  264.59  4983.2  264.00
  5003.4  264.94  5006.4  265.77  5043.9  271.51  5072.4  273.35  5077.5  274.89
  5084.3  275.45  5114.7  276.16  5141.1  277.79  5146.1  277.43  5175.4  279.31
#Mann=4,-1,0
  4735.4    0.12       0  4915.0    0.07       0  4919.6    0.12       0
  5006.4     0.1       0
Bank Sta=4915,4919.6
Exp/Cntr=0.3,0.1

Type RM Length L Ch R = 1,1706,330,330,330
BEGIN DESCRIPTION:
Walnut9 3.0
END DESCRIPTION:
XS GIS Cut Line= 3
      2721226.02      6741410.97      2721428.04      6741076.81
      2721575.99      6740411.03
#Sta/Elev= 30
  4430.1  280.78  4465.1  278.89  4480.5  279.06  4546.9  277.30  4560.1  277.75
  4612.4  274.72  4633.8  275.17  4696.4  272.22  4711.3  271.38  4728.8  270.28
  4750.2  270.05  4765.7  268.86  4881.6  266.96  4939.2  264.61  4949.5  263.30
  4988.1  263.08  4988.6  262.58  4992.7  263.08  5069.3  265.05  5153.1  268.15
  5158.2  267.02  5185.1  269.21  5250.4  271.48  5293.9  274.97  5299.0  274.61
  5342.6  277.06  5391.2  281.31  5434.8  282.97  5487.5  286.79  5502.6  288.20
#Mann=7,-1,0
  4430.1    0.12       0  4696.4     0.1       0  4711.3    0.12       0
  4988.1    0.07       0  4992.7    0.12       0  5069.3     0.1       0
  5487.5    0.05       0
Bank Sta=4988.1,4992.7
Exp/Cntr=0.3,0.1

Type RM Length L Ch R = 1,1376,173,173,173
BEGIN DESCRIPTION:
Walnut9 2.5
END DESCRIPTION:
XS GIS Cut Line= 3
      2721715.41      6741072.76      2721710.99      6740745.57
      2721609.64      6740434.90
#Sta/Elev= 30
  4688.1  274.20  4746.5  273.34  4799.9  271.96  4914.0  266.39  4921.3  266.08
  4939.9  264.02  4949.9  262.16  4969.9  262.68  4979.9  262.03  4997.5  261.70
  4998.1  261.20  5001.9  261.20  5002.6  261.70  5072.7  261.82  5078.9  263.28
  5104.3  265.13  5110.8  266.24  5125.3  266.28  5135.8  266.68  5142.7  268.14
  5167.4  270.34  5188.4  272.64  5198.9  273.24  5220.0  275.59  5262.1  278.66
  5283.1  280.65  5293.6  281.13  5314.6  283.01  5339.3  284.53  5342.1  285.13
#Mann=6,-1,0
  4688.1     0.1       0  4746.5    0.12       0  4914.0     0.1       0
  4921.3    0.12       0  4997.5    0.07       0  5002.6     0.1       0
Bank Sta=4997.5,5002.6
Exp/Cntr=0.3,0.1

Type RM Length L Ch R = 1,1203,261,261,261
BEGIN DESCRIPTION:
Walnut9 2.0
END DESCRIPTION:
XS GIS Cut Line= 3
      2721921.02      6740931.26      2721830.38      6740670.39
      2721735.30      6740316.62
#Sta/Elev= 30
  4752.5  270.45  4805.7  269.88  4845.1  268.38  4848.7  267.82  4858.6  267.46
  4900.3  266.89  4931.4  265.48  4936.7  263.43  4949.7  261.91  4953.9  261.51
  4967.8  261.77  4997.5  261.37  4998.1  260.87  5001.9  260.87  5002.6  261.37
  5064.5  261.48  5079.8  261.95  5104.5  264.90  5162.7  267.59  5179.3  269.51
  5214.1  271.39  5235.1  273.46  5254.1  274.48  5301.2  278.12  5318.0  278.67
  5328.3  279.30  5339.2  280.61  5368.8  281.90  5374.0  283.05  5395.0  283.55
#Mann=6,-1,0
  4752.5     0.1       0  4845.1    0.12       0  4949.7     0.1       0
  4997.5    0.07       0  5002.6     0.1       0  5301.2    0.05       0
Bank Sta=4997.5,5002.6
Exp/Cntr=0.3,0.1

Type RM Length L Ch R = 1,942,111,111,111
BEGIN DESCRIPTION:
Walnut9 1.7
END DESCRIPTION:
XS GIS Cut Line= 3
      2721980.71      6740811.92      2722055.89      6740635.02
      2722029.36      6740241.52
#Sta/Elev= 30
  4733.1  271.60  4736.7  272.00  4766.7  271.60  4784.0  270.35  4789.4  270.69
  4807.6  269.59  4813.1  269.94  4821.0  269.30  4834.9  269.07  4844.9  268.55
  4884.0  267.75  4889.4  268.25  4907.7  268.01  4929.8  267.36  4939.4  266.56
  4979.5  261.67  4997.5  261.31  4998.1  260.81  5001.9  260.81  5002.6  261.31
  5059.6  261.73  5099.7  261.56  5129.8  262.80  5139.8  263.81  5150.8  266.35
  5179.9  267.46  5246.3  269.18  5290.2  270.60  5300.3  271.39  5319.7  271.69
#Mann=6,-1,0
  4733.1     0.1       0  4834.9    0.12       0  4844.9     0.1       0
  4997.5    0.07       0  5002.6     0.1       0  5246.3    0.05       0
Bank Sta=4997.5,5002.6
Exp/Cntr=0.3,0.1

Type RM Length L Ch R = 1,831,383,383,383
BEGIN DESCRIPTION:
Walnut9 1.4
END DESCRIPTION:
XS GIS Cut Line= 3
      2721985.13      6740829.59      2722197.39      6740522.26
      2722247.86      6740445.47
#Sta/Elev= 30
  4704.7  272.02  4726.9  271.78  4733.0  271.27  4775.9  270.76  4789.8  269.93
  4798.6  269.83  4804.7  269.01  4812.4  268.80  4855.4  268.46  4885.1  268.79
  4897.4  267.65  4912.1  264.70  4920.9  261.82  4933.9  260.28  4948.0  259.61
  4962.8  259.85  4977.7  259.34  4997.5  259.29  4998.1  258.79  5001.9  258.79
  5002.6  259.29  5028.4  259.41  5034.5  262.20  5043.3  264.31  5055.4  266.56
  5064.2  266.54  5070.3  268.25  5081.5  268.22  5085.2  268.93  5170.1  269.21
#Mann=3,-1,0
  4704.7     0.1       0  4997.5    0.07       0  5002.6     0.1       0
Bank Sta=4997.5,5002.6
Exp/Cntr=0.3,0.1

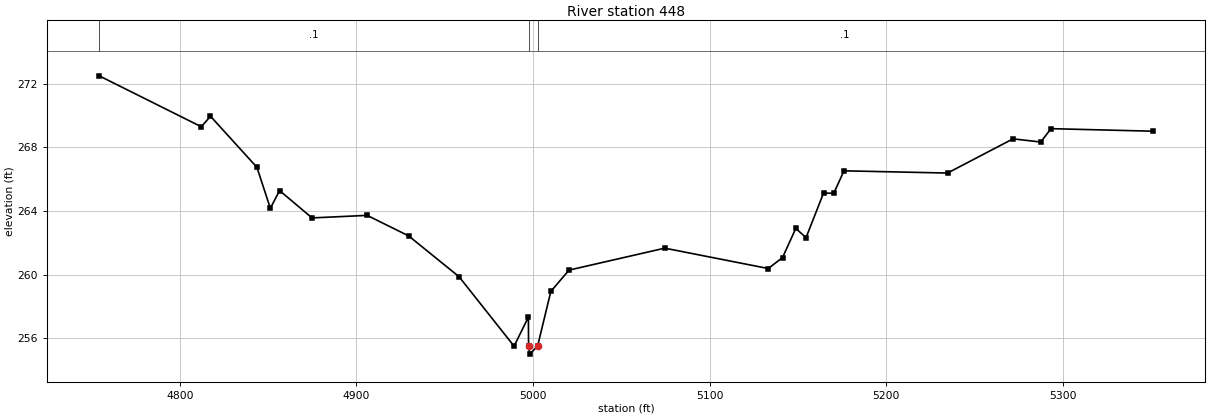
Type RM Length L Ch R = 1,448,0,0,0
BEGIN DESCRIPTION:
Walnut9 1.0
END DESCRIPTION:
XS GIS Cut Line= 4
      2721890.04      6741013.10      2722186.34      6740929.07
      2722312.36      6740714.61      2722318.90      6740675.38
#Sta/Elev= 30
  4754.4  272.49  4812.2  269.29  4817.4  269.95  4843.7  266.74  4851.3  264.16
  4856.5  265.28  4874.9  263.56  4906.1  263.72  4929.6  262.43  4958.1  259.87
  4989.3  255.50  4997.4  257.33  4997.5  255.50  4998.1  255.00  5002.6  255.50
  5010.1  258.94  5020.4  260.28  5074.6  261.66  5133.2  260.38  5141.3  261.07
  5148.8  262.90  5154.6  262.32  5164.5  265.12  5170.3  265.11  5176.1  266.52
  5234.7  266.38  5271.8  268.53  5287.5  268.33  5293.3  269.17  5350.9  269.01
#Mann=3,-1,0
  4754.4     0.1       0  4997.5    0.07       0  5002.6     0.1       0
Bank Sta=4997.5,5002.6
Exp/Cntr=0.3,0.1

Chan Stop Cuts=-1