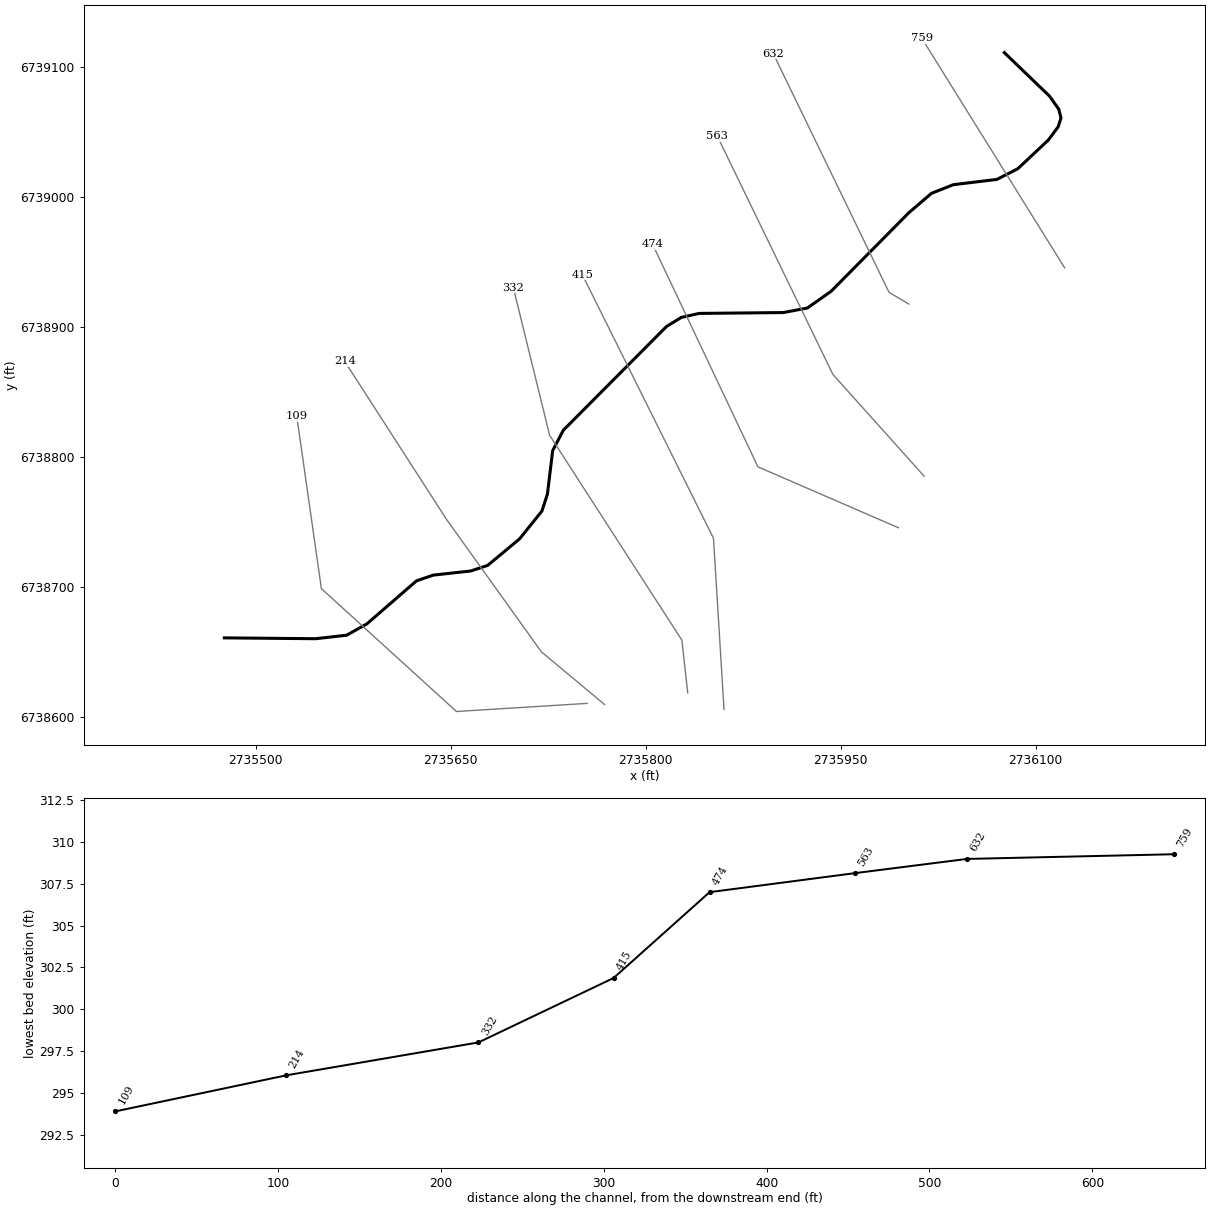
--- Walnut90.prj (project) ---

Proj Title=Walnut90 Base Level Engineering
Current Plan=p01
Default Exp/Contr=0.3,0.1
English Units
Geom File=g01
Flow File=f01
Plan File=p01
Y Axis Title=Elevation
X Axis Title(PF)=Main Channel Distance
X Axis Title(XS)=Station
BEGIN DESCRIPTION:
Walnut90
END DESCRIPTION:
DSS Export Rating Curves= 0
DSS Export Rating Curve Sorted= 0
DSS Export Volume Flow Curves= 0
DXF OffsetX= 0
DXF OffsetY= 0
DXF ScaleX= 1
DXF ScaleY= 10

--- Walnut90.p01 (plan) ---

Plan Title=Multiple Run
Program Version=4.10
Short Identifier=Multiple
Geom File=g01
Flow File=f01
Subcritical Flow
K Sum by GR= 0
Std Step Tol= 0.01
Critical Tol= 0.01
Num of Std Step Trials= 20
Max Error Tol= 0.3
Flow Tol Ratio= 0.001
Split Flow NTrial= 30
Split Flow Tol= 0.02
Split Flow Ratio= 0.02
Log Output Level= 0
Friction Slope Method= 1
Unsteady Friction Slope Method= 2
Unsteady Bridges Friction Slope Method= 1
Parabolic Critical Depth
Global Vel Dist= 1 , 1 , 1
Global Log Level= 0
CheckData=True
Encroach Param=-1 ,0,0, 0
BEGIN DESCRIPTION:
Multiple Run
END DESCRIPTION:
Computation Interval=1HOUR
Output Interval=1HOUR
Run HTab= 0
Run UNet= 0
Run PostProcess= 0
Run WQNet= 0
UNET Theta= 1
UNET Theta Warmup= 1
UNET ZTol= 0.02
UNET ZSATol= 0.05
UNET MxIter= 20
UNET MaxInSteps= 0
UNET DtIC= 0
UNET DtMin= 0
UNET MaxCRTS= 20
UNET WFStab= 2
UNET SFStab= 1
UNET WFX= 1
UNET SFX= 1
UNET DSS MLevel= 4
UNET DZMax Abort= 100
UNET Convert EG Bridges= 0
UNET Use Existing IB Tables=-1
UNET Froude Reduction=False
UNET Froude Limit= 1
UNET Froude Power= 10
UNET Time Slicing=0,0, 5
UNET Junction Losses=0
Instantaneous Interval=1HOUR
Write IC File= 0
Write IC File at Sim End=0
Echo Input=False
Echo Parameters=False
Echo Output=False
Write Detailed= 0
WQ AD Non Conservative
WQ ULTIMATE=-1
WQ Max Comp Step=1HOUR
WQ Output Interval=15MIN
WQ Output Selected Increments= 0
WQ Output face flow=0
WQ Output face velocity=0
WQ Output face area=0
WQ Output face dispersion=0
WQ Output cell volume=0
WQ Output cell surface area=0
WQ Output cell continuity=0
WQ Output cumulative cell continuity=0
WQ Output face conc=0
WQ Output face dconc_dx=0
WQ Output face courant=0
WQ Output face peclet=0
WQ Output face adv mass=0
WQ Output face disp mass=0
WQ Output cell mass=0
WQ Output cell source sink temp=0
WQ Output cell source sink nsm=0
WQ Output MaxMinRange=-1
WQ Daily Max Min Mean=-1
WQ Daily Range=0
WQ Daily Time=0
WQ Create Restart=0
WQ Fixed Restart=0
WQ System Summary=0
WQ Use Fixed Temperature=0
Sorting and Armoring Iterations= 10
XS Update Threshold= 0.02
Hydraulics Update Threshold= 0.02
Energy Slope Method= 1
Volume Change Method= 0
XS Weighting Method= 0
Number of US Weighted Cross Sections= 1
Number of DS Weighted Cross Sections= 1
Upstream XS Weight=0.25
Main XS Weight=0.5
Downstream XS Weight=0.25
Number of DS XS's Weighted with US Boundary= 1
Upstream Boundary Weight= 1
Weight of XSs Associated with US Boundary= 0
Number of US XS's Weighted with DS Boundary= 1
Downstream Boundary Weight= 0.5
Weight of XSs Associated with DS Boundary= 0.5
Sediment Output Level= 4
Mass or Volume Output= 0
Output Increment Type= 1
Profile and TS Output Increment= 10
XS Output Flag= 0
XS Output Increment= 10
Disregard all LS=0
Disregard all Conn=0
Disregard all Breaches=0
Disregard all Pumps=0

--- Walnut90.f01 (steady flow) ---

Flow Title=Multiple
Number of Profiles=7
Profile Names=10-year,25-year,50-year,1pct_min,100-year,1pct_plu,500-year
River Rch & RM= Walnut90,Reach-1,759
      81      96     107      60     119     237     147
Boundary for River Rch & Prof#=Walnut90,Reach-1,1
Up Type=0
Dn Type=3
Dn Slope=0.005
Boundary for River Rch & Prof#=Walnut90,Reach-1,2
Up Type=0
Dn Type=3
Dn Slope=0.005
Boundary for River Rch & Prof#=Walnut90,Reach-1,3
Up Type=0
Dn Type=3
Dn Slope=0.005
Boundary for River Rch & Prof#=Walnut90,Reach-1,4
Up Type=0
Dn Type=3
Dn Slope=0.005
Boundary for River Rch & Prof#=Walnut90,Reach-1,5
Up Type=0
Dn Type=3
Dn Slope=0.005
Boundary for River Rch & Prof#=Walnut90,Reach-1,6
Up Type=0
Dn Type=3
Dn Slope=0.005
Boundary for River Rch & Prof#=Walnut90,Reach-1,7
Up Type=0
Dn Type=3
Dn Slope=0.005

--- Walnut90.g01 (geometry) ---

Geom Title=Existing Conditions
Program Version=4.10

River Reach=Walnut90        ,Reach-1
Reach XY= 30
        2736076.        6739111.      2736110.67      6739077.64
       2736117.9      6739067.45      2736119.55      6739060.71
      2736117.39      6739053.96      2736109.91      6739043.86
      2736086.33      6739021.72       2736070.3      6739013.52
      2736036.72      6739009.46      2736019.99      6739002.83
      2736002.57      6738987.93      2735942.74      6738927.49
       2735924.5      6738914.63      2735905.94      6738911.14
      2735841.21      6738910.48      2735827.49      6738907.39
      2735816.19      6738900.49      2735736.78      6738820.69
      2735728.55      6738804.92      2735724.51      6738771.49
      2735720.25      6738758.46      2735703.14      6738737.16
      2735678.55      6738716.73      2735665.53      6738712.43
      2735636.75      6738709.27      2735623.84      6738704.88
      2735585.67      6738671.79      2735570.14      6738663.07
      2735546.27      6738660.36        2735476.        6738661.

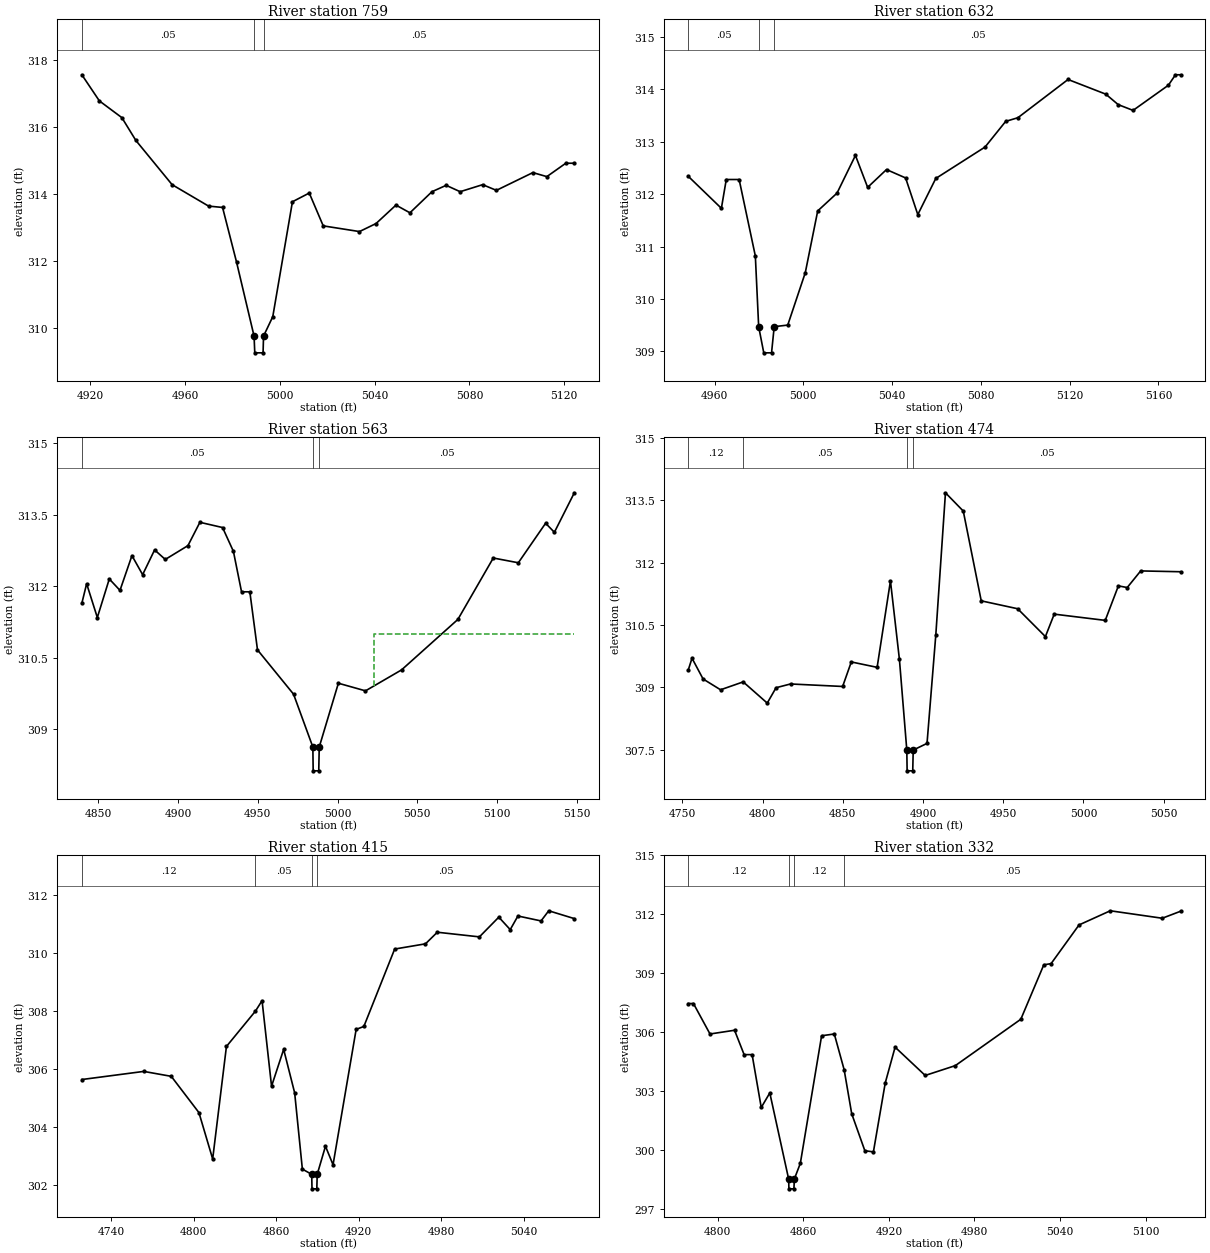
Type RM Length L Ch R = 1 ,759     ,127,127,127
BEGIN DESCRIPTION:
Walnut90 10.0
END DESCRIPTION:
XS GIS Cut Line= 2
      2736122.36      6738945.56       2736012.5      6739122.06
#Sta/Elev= 29
  4916.4  317.55  4923.8  316.77  4933.3  316.27  4939.2  315.59  4954.5  314.27
  4969.9  313.63  4975.8  313.59  4981.7  311.96  4989.1  309.75  4989.4  309.25
  4992.9  309.25  4993.1  309.75    4997  310.33  5005.3  313.76  5012.4  314.02
  5018.3  313.04  5033.6  312.87  5040.6  313.11    5049  313.66  5054.9  313.43
  5064.2  314.06  5070.2  314.25  5076.1  314.06  5085.6  314.27  5091.4   314.1
  5106.8  314.63  5112.7  314.51  5120.7  314.91  5124.3  314.91
#Mann= 3 ,-1 , 0
  4916.4     .05       0  4989.1    .035       0  4993.1     .05       0
Bank Sta=4989.1,4993.1
XS Rating Curve= 0 ,0
Exp/Cntr=0.3,0.1

Type RM Length L Ch R = 1 ,632     ,69,69,69
BEGIN DESCRIPTION:
Walnut90 4.8
END DESCRIPTION:
XS GIS Cut Line= 3
      2736002.59      6738917.66      2735987.31      6738926.65
      2735898.17      6739110.33
#Sta/Elev= 29
  4948.2  312.34  4963.1  311.73  4965.3  312.28  4971.1  312.28  4978.4  310.82
  4979.9  309.47  4982.2  308.97  4985.7  308.97  4986.9  309.47    4993   309.5
  5000.9   310.5  5006.5  311.68  5015.2  312.02  5023.5  312.74    5029  312.13
  5037.5  312.47  5046.1  312.31  5051.6  311.61  5059.7   312.3  5081.9   312.9
  5091.2  313.39  5096.7  313.46  5119.3  314.19  5136.3  313.91  5141.9  313.71
  5148.6   313.6  5164.5  314.08  5167.7  314.28  5170.1  314.28
#Mann= 3 ,-1 , 0
  4948.2     .05       0  4979.9    .035       0  4986.9     .05       0
Bank Sta=4979.9,4986.9
XS Rating Curve= 0 ,0
Exp/Cntr=0.3,0.1

Type RM Length L Ch R = 1 ,563     ,89,89,89
BEGIN DESCRIPTION:
Walnut90 4.5
END DESCRIPTION:
XS GIS Cut Line= 3
      2736014.35      6738785.26      2735944.09      6738863.63
      2735855.27      6739046.66
#Sta/Elev= 30
  4839.7  311.64  4842.7  312.05  4849.4  311.34  4856.9  312.15  4863.6  311.91
  4871.1  312.64  4877.8  312.24  4885.3  312.76    4892  312.56  4906.2  312.85
  4913.7  313.34  4927.9  313.23  4934.7  312.73  4939.8  311.88    4945  311.88
  4949.8  310.66  4972.4  309.73  4984.5  308.62  4984.7  308.12  4988.2  308.12
  4988.5  308.62  5000.5  309.96  5017.5   309.8  5040.1  310.24  5075.4   311.3
  5097.6  312.59  5113.3  312.49  5130.4  313.32  5135.9  313.13  5148.4  313.96
#Mann= 3 ,-1 , 0
  4839.7     .05       0  4984.5     .05       0  4988.5     .05       0
#XS Ineff= 2 , 0
       0                    5023       0     311
Permanent Ineff=
       F       F
Bank Sta=4984.5,4988.5
XS Rating Curve= 0 ,0
Exp/Cntr=0.3,0.1

Type RM Length L Ch R = 1 ,474     ,59,59,59
BEGIN DESCRIPTION:
Walnut90 4.3
END DESCRIPTION:
XS GIS Cut Line= 3
      2735994.49      6738745.69      2735886.47       6738792.5
      2735805.44      6738963.56
#Sta/Elev= 30
  4753.7  309.42    4756   309.7  4762.9   309.2  4773.8  308.94  4787.9  309.13
  4802.9  308.62  4808.4  308.99  4817.4  309.08  4849.9  309.02  4855.3  309.61
  4871.4  309.48  4879.7  311.56  4885.3  309.67  4889.9  307.49  4890.1  306.99
  4893.6  306.99  4893.9  307.49  4902.5  307.65    4908  310.27    4914  313.68
  4925.1  313.24  4936.3  311.08    4959  310.89  4976.3  310.22  4981.8  310.76
  5013.6  310.61  5021.8  311.44  5027.3   311.4  5035.7   311.8  5060.7  311.78
#Mann= 4 ,-1 , 0
  4753.7     .12       0  4787.9     .05       0  4889.9     .05       0
  4893.9     .05       0
Bank Sta=4889.9,4893.9
XS Rating Curve= 0 ,0
Exp/Cntr=0.3,0.1

Type RM Length L Ch R = 1 ,415     ,83,83,83
BEGIN DESCRIPTION:
Walnut90 4.0
END DESCRIPTION:
XS GIS Cut Line= 3
      2735860.36      6738606.08      2735852.26      6738737.58
      2735751.43      6738940.12
#Sta/Elev= 30
  4718.8  305.64  4763.8  305.92  4783.8  305.75  4803.9   304.5  4813.9   302.9
  4823.9  306.78    4845     308  4849.8  308.36  4856.7  305.41  4865.5  306.68
  4873.5  305.18  4879.1  302.55  4885.9  302.37  4886.1  301.87  4889.6  301.87
  4889.9  302.37  4895.9  303.34  4901.4   302.7  4918.2  307.37  4923.8  307.47
  4946.2  310.14  4968.6  310.32  4977.2  310.72  5007.8  310.56  5021.9  311.24
  5030.2  310.81  5035.8  311.28  5052.6  311.11  5058.2  311.46  5076.8  311.19
#Mann= 4 ,-1 , 0
  4718.8     .12       0    4845     .05       0  4885.9    .035       0
  4889.9     .05       0
Bank Sta=4885.9,4889.9
XS Rating Curve= 0 ,0
Exp/Cntr=0.3,0.1

Type RM Length L Ch R = 1 ,332     ,118,118,118
BEGIN DESCRIPTION:
Walnut90 1.6
END DESCRIPTION:
XS GIS Cut Line= 4
      2735832.45      6738618.77      2735827.95      6738659.25
      2735726.21      6738816.81       2735698.3      6738930.25
#Sta/Elev= 30
  4779.5  307.46  4783.1  307.46  4794.7  305.91  4811.9   306.1  4818.6  304.86
  4824.2  304.86  4830.6  302.17  4836.6  302.91  4849.8  298.53    4850  298.03
  4853.5  298.03  4853.8  298.53    4858  299.33  4872.9  305.82  4881.8  305.91
  4888.7  304.09    4894  301.85  4903.2  299.97  4909.2  299.91  4917.5  303.42
  4924.4  305.24  4945.5   303.8  4966.6   304.3  5012.5  306.66  5028.6  309.43
  5033.7  309.49  5053.3  311.46  5075.2  312.18  5111.6   311.8  5124.6  312.16
#Mann= 4 ,-1 , 0
  4779.5     .12       0  4849.8    .035       0  4853.8     .12       0
  4888.7     .05       0
Bank Sta=4849.8,4853.8
XS Rating Curve= 0 ,0
Exp/Cntr=0.3,0.1

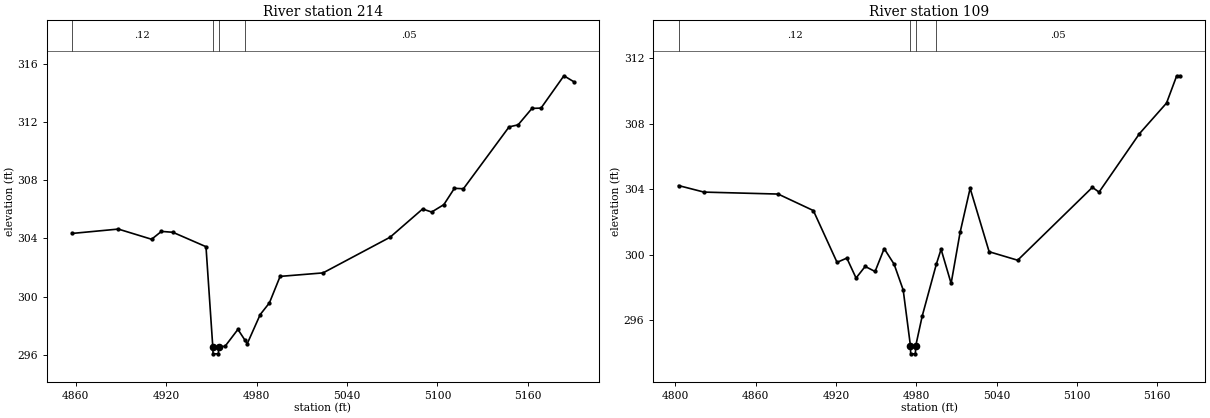
Type RM Length L Ch R = 1 ,214     ,105,105,105
BEGIN DESCRIPTION:
Walnut90 1.3
END DESCRIPTION:
XS GIS Cut Line= 4
      2735768.55       6738609.7      2735719.91      6738650.24
      2735646.98      6738751.98      2735568.65      6738873.53
#Sta/Elev= 30
  4857.5  304.34  4888.2  304.64  4910.3  303.94  4916.8  304.48  4924.4  304.42
  4946.4  303.43  4950.9  296.57  4951.1  296.07  4954.6  296.07  4954.9  296.57
    4959  296.58  4967.6  297.75    4972  297.05  4973.8  296.77  4982.4  298.77
  4988.5  299.57  4995.6  301.39  5024.1  301.63  5068.6  304.08  5090.2  306.02
  5096.2  305.81  5104.3  306.32  5111.3  307.44  5117.3  307.41  5147.6  311.66
  5153.6   311.8  5162.8  312.93  5168.8  312.95    5184  315.17  5190.6  314.76
#Mann= 4 ,-1 , 0
  4857.5     .12       0  4950.9    .035       0  4954.9     .12       0
    4972     .05       0
Bank Sta=4950.9,4954.9
XS Rating Curve= 0 ,0
Exp/Cntr=0.3,0.1

Type RM Length L Ch R = 1 ,109     ,0,0,0
BEGIN DESCRIPTION:
Walnut90 1.0
END DESCRIPTION:
XS GIS Cut Line= 4
        2735755.      6738610.63      2735654.54      6738604.39
      2735550.64      6738698.86      2735531.73      6738831.23
#Sta/Elev= 30
  4802.4  304.22  4821.4  303.82  4876.8   303.7  4903.1  302.69  4920.8  299.52
  4928.1  299.78    4935  298.56  4941.8  299.27  4949.2  298.96    4956  300.36
  4963.4  299.41  4970.2  297.83  4975.6  294.42  4975.8  293.92  4979.3  293.92
  4979.6  294.42  4984.4  296.23    4995  299.42  4998.5  300.32    5006  298.23
  5012.7  301.35  5020.2  304.05  5034.4  300.17  5055.7  299.65  5111.5  304.11
  5116.5  303.82  5146.7   307.4  5166.9  309.27  5174.5  310.94  5177.2  310.94
#Mann= 4 ,-1 , 0
  4802.4     .12       0  4975.6    .035       0  4979.6     .12       0
    4995     .05       0
Bank Sta=4975.6,4979.6
XS Rating Curve= 0 ,0
Exp/Cntr=0.3,0.1

Chan Stop Cuts=-1
Use User Specified Reach Order=0
Composite Channel Slope=5