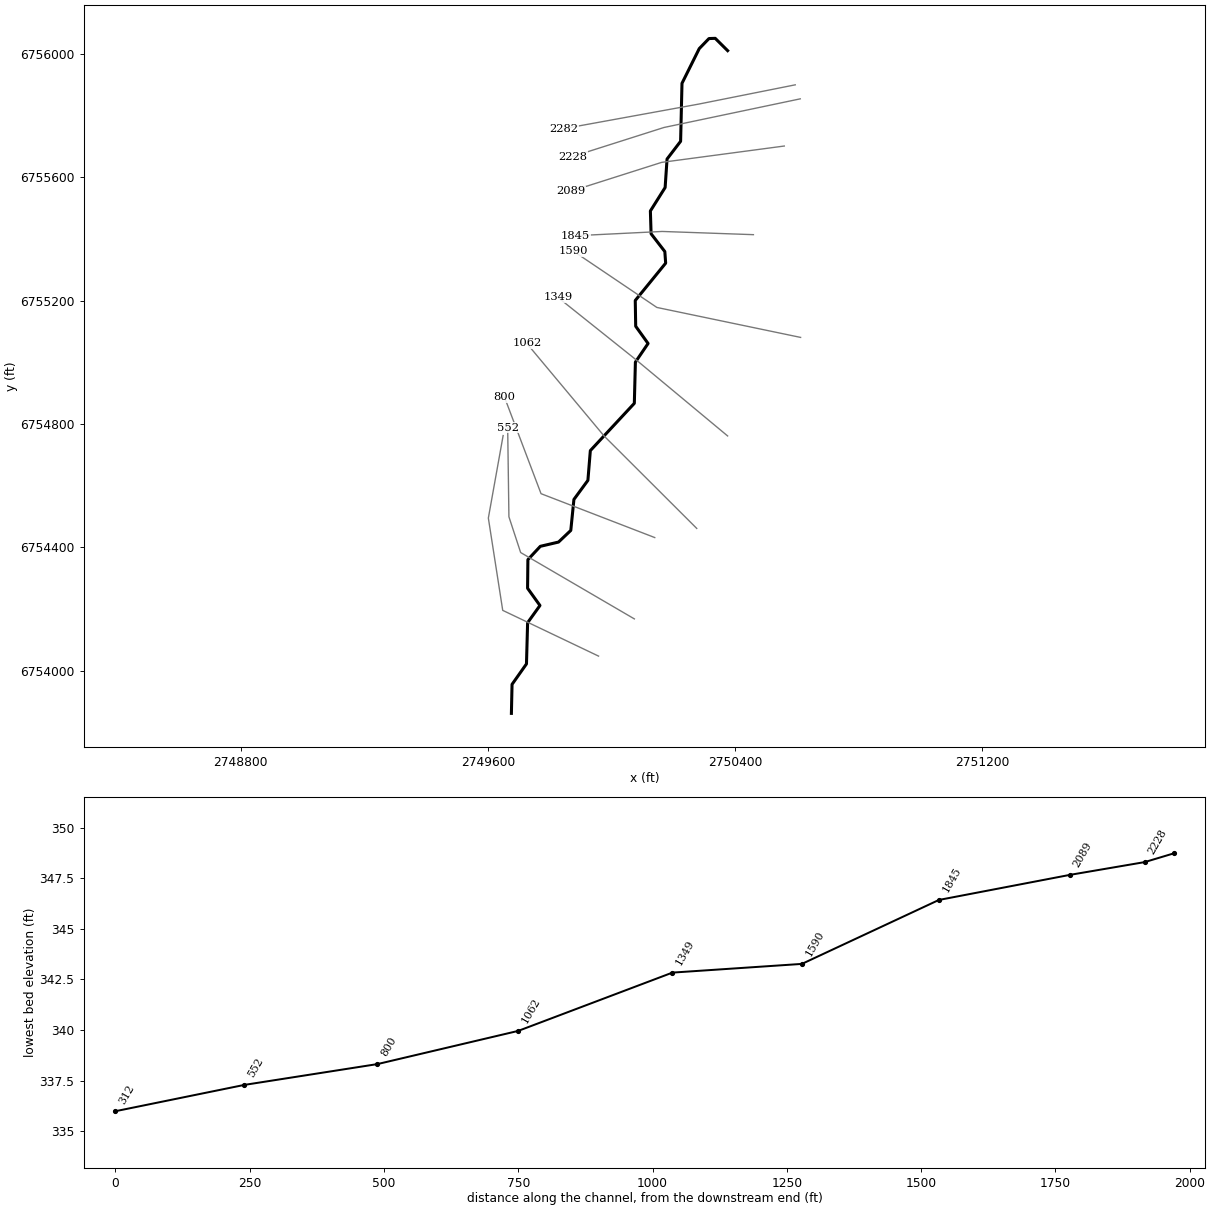
--- Walnut93.prj (project) ---

Proj Title=Walnut93 Base Level Engineering
Current Plan=p01
Default Exp/Contr=0.3,0.1
English Units
Geom File=g01
Flow File=f01
Plan File=p01
Y Axis Title=Elevation
X Axis Title(PF)=Main Channel Distance
X Axis Title(XS)=Station
BEGIN DESCRIPTION:
Walnut93
END DESCRIPTION:
DSS Export Rating Curves= 0
DSS Export Rating Curve Sorted= 0
DSS Export Volume Flow Curves= 0
DXF OffsetX= 0
DXF OffsetY= 0
DXF ScaleX= 1
DXF ScaleY= 10

--- Walnut93.p01 (plan) ---

Plan Title=Multiple Run
Program Version=4.10
Short Identifier=Multiple
Geom File=g01
Flow File=f01
Subcritical Flow
K Sum by GR= 0
Std Step Tol= 0.01
Critical Tol= 0.01
Num of Std Step Trials= 20
Max Error Tol= 0.3
Flow Tol Ratio= 0.001
Split Flow NTrial= 30
Split Flow Tol= 0.02
Split Flow Ratio= 0.02
Log Output Level= 0
Friction Slope Method= 1
Unsteady Friction Slope Method= 2
Unsteady Bridges Friction Slope Method= 1
Parabolic Critical Depth
Global Vel Dist= 1 , 1 , 1
Global Log Level= 0
CheckData=True
Encroach Param=-1 ,0,0, 0
BEGIN DESCRIPTION:
Multiple Run
END DESCRIPTION:
Computation Interval=1HOUR
Output Interval=1HOUR
Run HTab= 0
Run UNet= 0
Run PostProcess= 0
Run WQNet= 0
UNET Theta= 1
UNET Theta Warmup= 1
UNET ZTol= 0.02
UNET ZSATol= 0.05
UNET MxIter= 20
UNET MaxInSteps= 0
UNET DtIC= 0
UNET DtMin= 0
UNET MaxCRTS= 20
UNET WFStab= 2
UNET SFStab= 1
UNET WFX= 1
UNET SFX= 1
UNET DSS MLevel= 4
UNET DZMax Abort= 100
UNET Convert EG Bridges= 0
UNET Use Existing IB Tables=-1
UNET Froude Reduction=False
UNET Froude Limit= 1
UNET Froude Power= 10
UNET Time Slicing=0,0, 5
UNET Junction Losses=0
Instantaneous Interval=1HOUR
Write IC File= 0
Write IC File at Sim End=0
Echo Input=False
Echo Parameters=False
Echo Output=False
Write Detailed= 0
WQ AD Non Conservative
WQ ULTIMATE=-1
WQ Max Comp Step=1HOUR
WQ Output Interval=15MIN
WQ Output Selected Increments= 0
WQ Output face flow=0
WQ Output face velocity=0
WQ Output face area=0
WQ Output face dispersion=0
WQ Output cell volume=0
WQ Output cell surface area=0
WQ Output cell continuity=0
WQ Output cumulative cell continuity=0
WQ Output face conc=0
WQ Output face dconc_dx=0
WQ Output face courant=0
WQ Output face peclet=0
WQ Output face adv mass=0
WQ Output face disp mass=0
WQ Output cell mass=0
WQ Output cell source sink temp=0
WQ Output cell source sink nsm=0
WQ Output MaxMinRange=-1
WQ Daily Max Min Mean=-1
WQ Daily Range=0
WQ Daily Time=0
WQ Create Restart=0
WQ Fixed Restart=0
WQ System Summary=0
WQ Use Fixed Temperature=0
Sorting and Armoring Iterations= 10
XS Update Threshold= 0.02
Hydraulics Update Threshold= 0.02
Energy Slope Method= 1
Volume Change Method= 0
XS Weighting Method= 0
Number of US Weighted Cross Sections= 1
Number of DS Weighted Cross Sections= 1
Upstream XS Weight=0.25
Main XS Weight=0.5
Downstream XS Weight=0.25
Number of DS XS's Weighted with US Boundary= 1
Upstream Boundary Weight= 1
Weight of XSs Associated with US Boundary= 0
Number of US XS's Weighted with DS Boundary= 1
Downstream Boundary Weight= 0.5
Weight of XSs Associated with DS Boundary= 0.5
Sediment Output Level= 4
Mass or Volume Output= 0
Output Increment Type= 1
Profile and TS Output Increment= 10
XS Output Flag= 0
XS Output Increment= 10
Disregard all LS=0
Disregard all Conn=0
Disregard all Breaches=0
Disregard all Pumps=0

--- Walnut93.f01 (steady flow) ---

Flow Title=Multiple
Program Version=4.10
Number of Profiles= 7
Profile Names=10-year,25-year,50-year,1pct_min,100-year,1pct_plu,500-year
River Rch & RM=Walnut93,Reach-1         ,2282
     305     395     466     274     547    1091     752
Boundary for River Rch & Prof#=Walnut93,Reach-1         , 1
Up Type= 0
Dn Type= 3
Dn Slope=0.006
Boundary for River Rch & Prof#=Walnut93,Reach-1         , 2
Up Type= 0
Dn Type= 3
Dn Slope=0.006
Boundary for River Rch & Prof#=Walnut93,Reach-1         , 3
Up Type= 0
Dn Type= 3
Dn Slope=0.006
Boundary for River Rch & Prof#=Walnut93,Reach-1         , 4
Up Type= 0
Dn Type= 3
Dn Slope=0.006
Boundary for River Rch & Prof#=Walnut93,Reach-1         , 5
Up Type= 0
Dn Type= 3
Dn Slope=0.006
Boundary for River Rch & Prof#=Walnut93,Reach-1         , 6
Up Type= 0
Dn Type= 3
Dn Slope=0.006
Boundary for River Rch & Prof#=Walnut93,Reach-1         , 7
Up Type= 0
Dn Type= 3
Dn Slope=0.006
DSS Import GetInterval= 0
DSS Import GetPeak= 0
DSS Import FillOption= 0

--- Walnut93.g01 (geometry) ---

Geom Title=Existing Conditions

River Reach=Walnut93,Reach-1
Reach XY= 30
      2750376.00      6756011.00      2750335.81      6756050.98
      2750315.59      6756050.28      2750284.09      6756017.63
      2750228.24      6755905.07      2750223.74      6755716.94
      2750179.86      6755659.40      2750173.64      6755566.97
      2750125.90      6755490.90      2750128.19      6755416.97
      2750172.66      6755359.25      2750175.39      6755321.62
      2750076.95      6755200.51      2750078.36      6755116.90
      2750118.44      6755061.00      2750077.40      6755000.56
      2750073.93      6754866.86      2749931.52      6754713.43
      2749923.64      6754616.98      2749878.36      6754555.02
      2749868.25      6754454.55      2749828.55      6754416.75
      2749769.64      6754402.97      2749729.38      6754359.72
      2749728.36      6754266.90      2749768.44      6754211.00
      2749728.47      6754155.14      2749724.79      6754021.50
      2749678.10      6753955.13      2749676.00      6753861.00

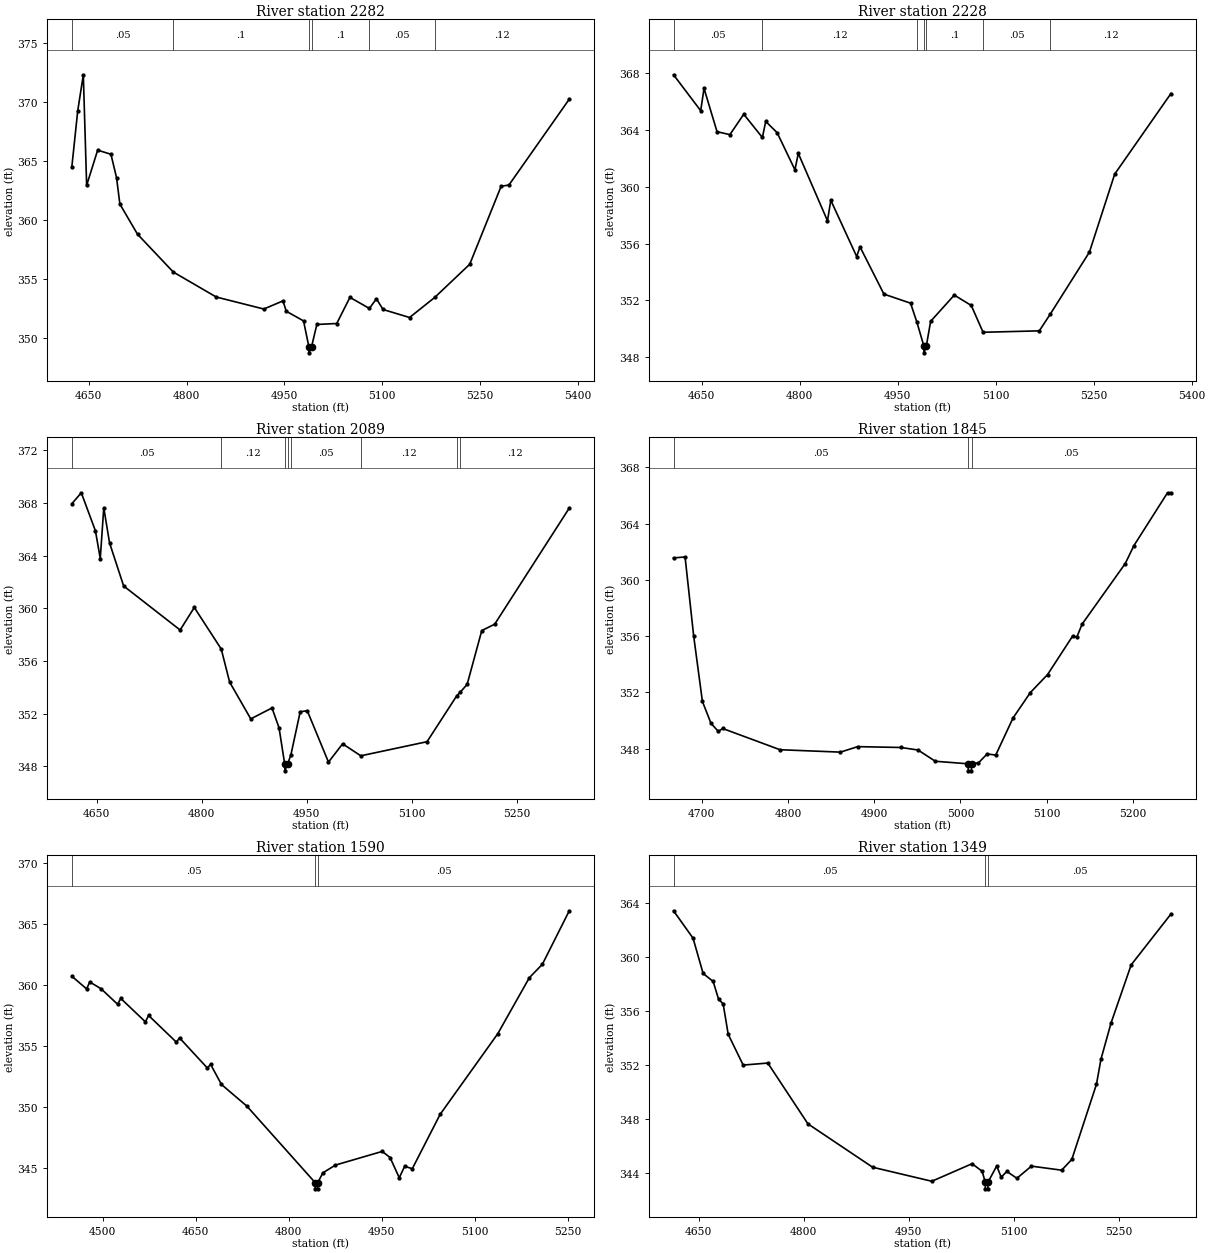
Type RM Length L Ch R = 1,2282,54,54,54
BEGIN DESCRIPTION:
Walnut93 7.0
END DESCRIPTION:
XS GIS Cut Line= 3
      2750594.84      6755900.15      2750282.34      6755837.65
      2749844.86      6755757.79
#Sta/Elev= 30
  4623.9  364.53  4632.9  369.27  4641.5  372.34  4646.6  362.95  4663.5  365.94
  4683.9  365.59  4692.5  363.60  4697.6  361.36  4724.7  358.80  4779.6  355.59
  4845.5  353.47  4918.5  352.45  4947.9  353.14  4953.0  352.26  4979.5  351.44
  4987.7  349.23  4987.9  348.73  4991.7  349.23  4999.9  351.14  5030.4  351.22
  5050.7  353.44  5080.5  352.50  5091.3  353.32  5101.5  352.41  5142.2  351.73
  5180.7  353.43  5234.5  356.25  5282.7  362.87  5294.7  362.98  5387.3  370.27
#Mann=6,-1,0
  4623.9    0.05       0  4779.6     0.1       0  4987.7    0.07       0
  4991.7     0.1       0  5080.5    0.05       0  5180.7    0.12       0
Bank Sta=4987.7,4991.7
Exp/Cntr=0.3,0.1

Type RM Length L Ch R = 1,2228,139,139,139
BEGIN DESCRIPTION:
Walnut93 6.3
END DESCRIPTION:
XS GIS Cut Line= 3
      2750611.14      6755854.71      2750169.57      6755761.68
      2749873.99      6755667.47
#Sta/Elev= 30
  4606.7  367.90  4648.3  365.37  4653.4  366.94  4673.3  363.89  4693.0  363.68
  4714.2  365.12  4742.7  363.48  4747.9  364.61  4765.3  363.82  4792.6  361.20
  4797.7  362.36  4842.4  357.61  4847.5  359.05  4887.1  355.09  4892.2  355.77
  4928.8  352.44  4969.6  351.80  4979.4  350.44  4989.8  348.80  4990.1  348.30
  4993.8  348.80  5000.3  350.52  5036.5  352.37  5062.5  351.64  5080.6  349.75
  5166.7  349.85  5183.6  351.04  5243.4  355.40  5282.1  360.90  5368.2  366.58
#Mann=7,-1,0
  4606.7    0.05       0  4742.7    0.12       0  4979.4     0.1       0
  4989.8    0.07       0  4993.8     0.1       0  5080.6    0.05       0
  5183.6    0.12       0
Bank Sta=4989.8,4993.8
Exp/Cntr=0.3,0.1

Type RM Length L Ch R = 1,2089,244,244,244
BEGIN DESCRIPTION:
Walnut93 6.0
END DESCRIPTION:
XS GIS Cut Line= 3
      2750559.38      6755701.62      2750162.50      6755648.62
      2749866.95      6755554.42
#Sta/Elev= 30
  4614.6  367.93  4628.1  368.76  4648.3  365.87  4655.2  363.77  4660.2  367.62
  4668.5  364.95  4688.6  361.69  4769.3  358.35  4789.5  360.06  4828.0  356.91
  4840.0  354.40  4870.2  351.61  4900.5  352.44  4910.6  350.93  4918.7  348.17
  4918.9  347.67  4922.7  348.17  4927.5  348.88  4940.8  352.15  4950.9  352.23
  4981.2  348.33  5001.4  349.72  5027.4  348.81  5122.0  349.88  5164.3  353.35
  5169.4  353.63  5179.3  354.23  5200.2  358.31  5218.6  358.79  5325.2  367.60
#Mann=8,-1,0
  4614.6    0.05       0  4828.0    0.12       0  4918.7    0.03       0
  4922.7    0.12       0  4927.5    0.05       0  5027.4    0.12       0
  5164.3    0.05       0  5169.4    0.12       0
Bank Sta=4918.7,4922.7
Exp/Cntr=0.3,0.1

Type RM Length L Ch R = 1,1845,255,255,255
BEGIN DESCRIPTION:
Walnut93 5.0
END DESCRIPTION:
XS GIS Cut Line= 3
      2750459.43      6755414.04      2750164.28      6755424.46
      2749883.06      6755410.57
#Sta/Elev= 30
  4667.3  361.56  4680.7  361.63  4690.7  356.00  4700.8  351.36  4710.8  349.80
  4719.3  349.23  4724.3  349.44  4790.8  347.93  4860.9  347.76  4880.9  348.15
  4930.9  348.09  4950.9  347.91  4970.9  347.11  5009.0  346.93  5009.2  346.43
  5012.7  346.43  5013.0  346.93  5021.0  347.00  5031.0  347.63  5041.0  347.55
  5061.0  350.18  5081.1  351.99  5101.1  353.27  5130.1  356.00  5135.1  355.94
  5141.1  356.85  5191.2  361.16  5201.2  362.43  5240.2  366.19  5244.2  366.19
#Mann=3,-1,0
  4667.3    0.05       0  5009.0    0.04       0  5013.0    0.05       0
Bank Sta=5009,5013
Exp/Cntr=0.3,0.1

Type RM Length L Ch R = 1,1590,241,241,241
BEGIN DESCRIPTION:
Walnut93 4.0
END DESCRIPTION:
XS GIS Cut Line= 3
      2750612.21      6755080.70      2750146.92      6755177.93
      2749876.02      6755360.99
#Sta/Elev= 30
  4450.5  360.71  4474.3  359.67  4479.4  360.24  4497.7  359.68  4524.3  358.41
  4529.4  358.89  4569.1  356.97  4574.3  357.49  4619.1  355.30  4624.2  355.65
  4669.1  353.18  4674.2  353.49  4691.8  351.83  4732.7  350.06  4843.1  343.77
  4843.3  343.27  4846.8  343.27  4847.1  343.77  4855.3  344.58  4875.7  345.22
  4951.1  346.34  4963.7  345.84  4978.6  344.18  4987.3  345.12  4999.6  344.92
  5044.5  349.38  5137.4  355.99  5188.4  360.59  5209.4  361.69  5252.8  366.08
#Mann=3,-1,0
  4450.5    0.05       0  4843.1    0.04       0  4847.1    0.05       0
Bank Sta=4843.1,4847.1
Exp/Cntr=0.3,0.1

Type RM Length L Ch R = 1,1349,287,287,287
BEGIN DESCRIPTION:
Walnut93 3.0
END DESCRIPTION:
XS GIS Cut Line= 3
      2750375.96      6754761.03      2750076.00      6755011.00
      2749826.02      6755210.99
#Sta/Elev= 30
  4614.1  363.42  4642.0  361.39  4656.4  358.78  4670.7  358.19  4678.5  356.87
  4685.0  356.53  4692.2  354.28  4713.6  352.00  4748.8  352.15  4806.1  347.65
  4898.5  344.44  4983.1  343.40  5040.6  344.70  5055.0  344.14  5059.4  343.34
  5059.6  342.84  5063.1  342.84  5063.4  343.34  5075.8  344.53  5082.2  343.70
  5090.2  344.13  5104.6  343.62  5125.4  344.52  5168.6  344.22  5183.1  345.02
  5218.3  350.58  5224.7  352.43  5239.1  355.11  5267.9  359.42  5324.7  363.18
#Mann=3,-1,0
  4614.1    0.05       0  5059.4    0.04       0  5063.4    0.05       0
Bank Sta=5059.4,5063.4
Exp/Cntr=0.3,0.1

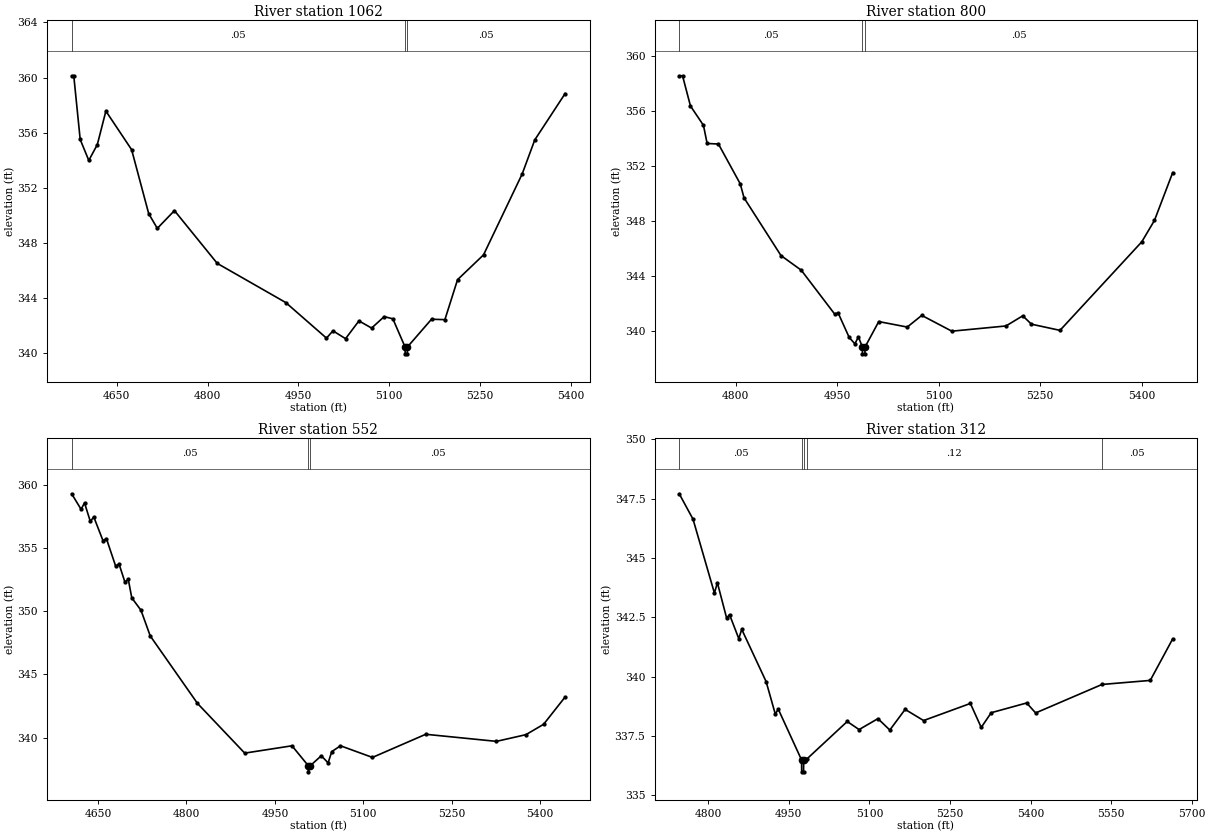
Type RM Length L Ch R = 1,1062,262,262,262
BEGIN DESCRIPTION:
Walnut93 2.0
END DESCRIPTION:
XS GIS Cut Line= 3
      2750275.98      6754461.02      2749976.00      6754761.00
      2749726.03      6755060.97
#Sta/Elev= 30
  4575.5  360.13  4579.0  360.13  4589.6  355.51  4603.8  353.99  4617.9  355.14
  4632.0  357.57  4674.5  354.77  4702.7  350.13  4716.9  349.06  4745.2  350.35
  4815.9  346.52  4929.0  343.68  4996.2  341.10  5006.9  341.63  5027.7  341.06
  5049.8  342.35  5070.7  341.83  5091.5  342.66  5105.8  342.50  5125.9  340.46
  5126.2  339.96  5129.7  339.96  5129.9  340.46  5169.6  342.47  5191.7  342.44
  5212.6  345.34  5255.5  347.14  5319.3  353.01  5340.1  355.48  5390.2  358.84
#Mann=3,-1,0
  4575.5    0.05       0  5125.9    0.04       0  5129.9    0.05       0
Bank Sta=5125.9,5129.9
Exp/Cntr=0.3,0.1

Type RM Length L Ch R = 1,800,248,248,248
BEGIN DESCRIPTION:
Walnut93 1.0
END DESCRIPTION:
XS GIS Cut Line= 3
      2750140.01      6754431.39      2749771.92      6754573.76
      2749653.91      6754886.14
#Sta/Elev= 30
  4716.9  358.57  4721.8  358.57  4733.5  356.37  4752.7  354.96  4758.1  353.64
  4774.8  353.60  4807.0  350.70  4812.6  349.68  4867.1  345.48  4897.1  344.41
  4946.2  341.23  4951.6  341.29  4967.8  339.52  4976.2  339.05  4981.5  339.55
  4987.3  338.82  4987.5  338.32  4991.0  338.32  4991.3  338.82  5011.5  340.67
  5053.6  340.27  5075.0  341.12  5119.4  339.97  5199.3  340.35  5224.1  341.09
  5236.9  340.48  5279.1  340.03  5399.9  346.48  5418.6  348.04  5445.5  351.52
#Mann=3,-1,0
  4716.9    0.05       0  4987.3    0.04       0  4991.3    0.05       0
Bank Sta=4987.3,4991.3
Exp/Cntr=0.3,0.1

Type RM Length L Ch R = 1,552,240,240,240
BEGIN DESCRIPTION:
Walnut93 0.3
END DESCRIPTION:
XS GIS Cut Line= 4
      2750074.04      6754167.49      2749705.95      6754382.79
      2749667.95      6754498.79      2749663.96      6754787.46
#Sta/Elev= 30
  4605.2  359.28  4621.2  358.05  4627.0  358.56  4636.9  357.09  4642.7  357.45
  4658.4  355.57  4664.2  355.73  4679.9  353.55  4685.6  353.73  4695.5  352.30
  4701.3  352.51  4707.2  351.05  4722.8  350.07  4738.5  348.04  4818.7  342.70
  4898.8  338.77  4979.0  339.35  5006.4  337.79  5006.7  337.29  5010.4  337.79
  5028.7  338.56  5040.3  338.00  5046.5  338.89  5061.3  339.35  5115.5  338.43
  5205.9  340.26  5325.9  339.70  5375.9  340.23  5405.9  341.05  5442.4  343.21
#Mann=3,-1,0
  4605.2    0.05       0  5006.4    0.04       0  5010.4    0.05       0
Bank Sta=5006.4,5010.4
Exp/Cntr=0.3,0.1

Type RM Length L Ch R = 1,312,0,0,0
BEGIN DESCRIPTION:
Walnut93 0.2
END DESCRIPTION:
XS GIS Cut Line= 4
      2749958.15      6754046.78      2749647.89      6754195.22
      2749601.38      6754494.61      2749649.23      6754762.25
#Sta/Elev= 30
  4745.9  347.70  4771.6  346.63  4811.4  343.52  4817.0  343.95  4834.1  342.47
  4839.6  342.61  4856.8  341.60  4862.3  341.99  4907.7  339.79  4924.8  338.42
  4930.3  338.63  4973.7  336.49  4973.9  335.99  4977.4  335.99  4977.7  336.49
  4983.5  336.53  5058.7  338.11  5080.8  337.77  5115.9  338.23  5138.0  337.75
  5166.5  338.62  5200.9  338.15  5288.0  338.87  5308.2  337.86  5326.8  338.48
  5392.8  338.89  5409.5  338.47  5533.1  339.67  5622.9  339.84  5664.7  341.59
#Mann=5,-1,0
  4745.9    0.05       0  4973.7    0.07       0  4977.7    0.05       0
  4983.5    0.12       0  5533.1    0.05       0
Bank Sta=4973.7,4977.7
Exp/Cntr=0.3,0.1

Chan Stop Cuts=-1