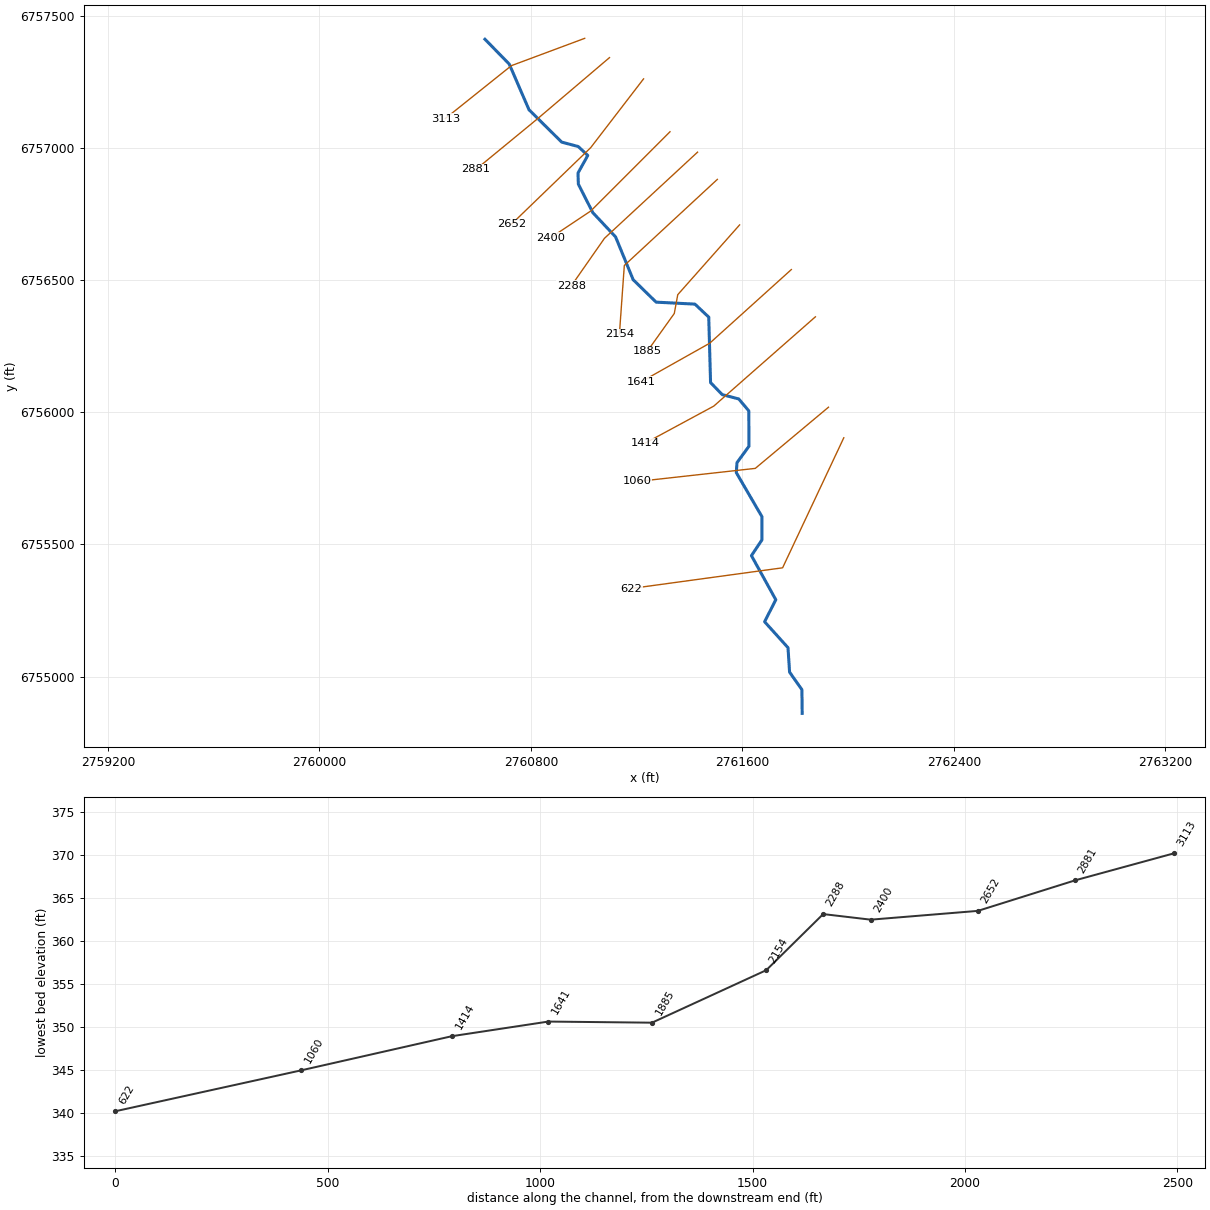
--- Walnut95.prj (project) ---

Proj Title=Walnut95 Base Level Engineering
Current Plan=p01
Default Exp/Contr=0.3,0.1
English Units
Geom File=g01
Flow File=f01
Plan File=p01
BEGIN DESCRIPTION:
Walnut95
END DESCRIPTION:

--- Walnut95.p01 (plan) ---

Plan Title=Multiple Run
Short Identifier=Multiple
Geom File=g01
Flow File=f01
Subcritical Flow
K Sum by GR= 0
Std Step Tol= 0.01
Critical Tol= 0.01
Num of Std Step Trials= 20
Max Error Tol= 0.3
Flow Tol Ratio= 0.001
Split Flow NTrial= 30
Split Flow Tol= 0.02
Split Flow Ratio= 0.02
Log Output Level= 0
Friction Slope Method= 1
Unsteady Friction Slope Method= 2
Unsteady Bridges Friction Slope Method= 1
Parabolic Critical Depth
Global Vel Dist=  1 , 1 , 1
Global Log Level= 0
CheckData=True
Encroach Param= -1, 0, 0, 0
BEGIN DESCRIPTION:
Multiple Run
END DESCRIPTION:

--- Walnut95.f01 (steady flow) ---

Flow Title=Multiple
Number of Profiles=7
Profile Names=10-year,25-year,50-year,1pct_min,100-year,1pct_plu,500-year
River Rch & RM= Walnut95,Reach-1,3113
     362     476     567     337     672    1341     944
Boundary for River Rch & Prof#=Walnut95,Reach-1,1
Up Type=0
Dn Type=3
Dn Slope=0.005
Boundary for River Rch & Prof#=Walnut95,Reach-1,2
Up Type=0
Dn Type=3
Dn Slope=0.005
Boundary for River Rch & Prof#=Walnut95,Reach-1,3
Up Type=0
Dn Type=3
Dn Slope=0.005
Boundary for River Rch & Prof#=Walnut95,Reach-1,4
Up Type=0
Dn Type=3
Dn Slope=0.005
Boundary for River Rch & Prof#=Walnut95,Reach-1,5
Up Type=0
Dn Type=3
Dn Slope=0.005
Boundary for River Rch & Prof#=Walnut95,Reach-1,6
Up Type=0
Dn Type=3
Dn Slope=0.005
Boundary for River Rch & Prof#=Walnut95,Reach-1,7
Up Type=0
Dn Type=3
Dn Slope=0.005

--- Walnut95.g01 (geometry) ---

Geom Title=Existing Conditions

River Reach=Walnut95,Reach-1
Reach XY= 30
      2760626.00      6757411.00      2760717.91      6757317.08
      2760792.64      6757144.32      2760916.35      6757021.78
      2760978.85      6757005.15      2761015.02      6756971.37
      2760978.03      6756904.97      2760979.37      6756862.74
      2761034.15      6756754.95      2761120.15      6756663.29
      2761186.75      6756501.29      2761273.54      6756416.46
      2761420.35      6756409.02      2761472.57      6756359.78
      2761479.45      6756112.25      2761523.45      6756066.75
      2761586.04      6756050.37      2761624.03      6756005.32
      2761624.77      6755871.50      2761579.37      6755809.26
      2761576.75      6755771.68      2761673.85      6755605.03
      2761673.63      6755516.89      2761634.05      6755457.68
      2761726.22      6755290.80      2761683.83      6755207.60
      2761772.36      6755109.50      2761778.34      6755016.97
      2761824.98      6754950.58      2761826.00      6754861.00

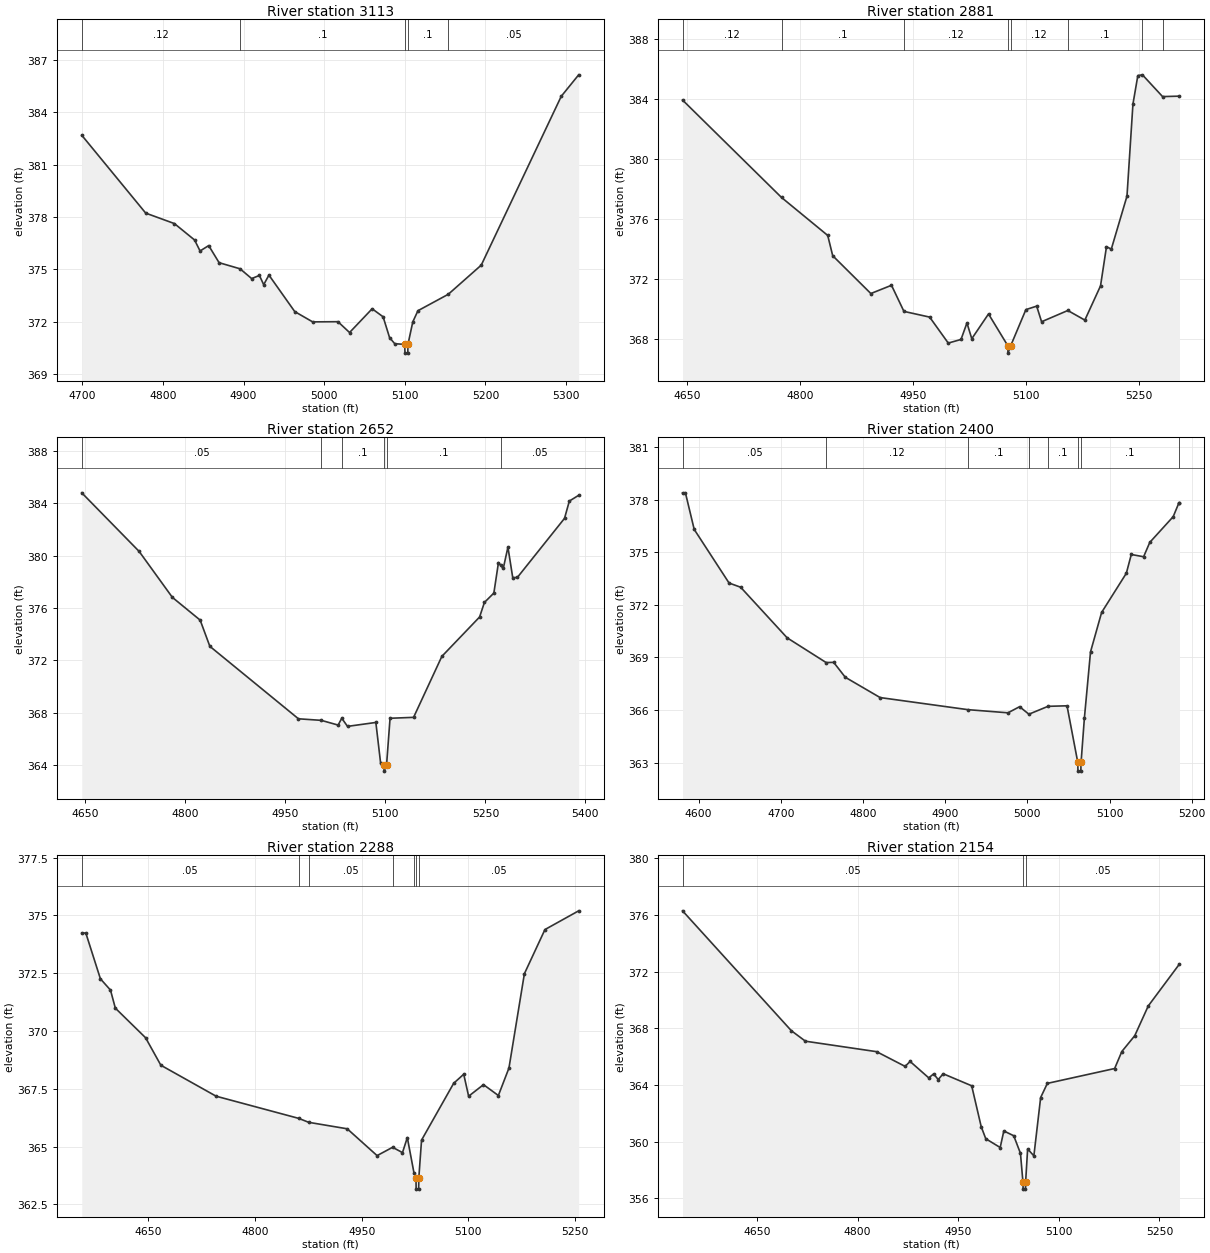
Type RM Length L Ch R = 1,3113,232,232,232
BEGIN DESCRIPTION:
Walnut95 9.0
END DESCRIPTION:
XS GIS Cut Line= 3
      2761003.46      6757414.36      2760726.00      6757311.00
      2760476.03      6757111.02
#Sta/Elev= 30
  4699.4  382.69  4778.7  378.23  4814.3  377.63  4839.3  376.69  4846.1  376.06
  4856.8  376.37  4869.7  375.39  4895.7  375.04  4910.1  374.48  4919.7  374.66
  4925.0  374.13  4931.5  374.68  4963.5  372.59  4985.7  372.00  5017.1  372.01
  5031.5  371.39  5059.5  372.75  5073.1  372.29  5081.1  371.10  5087.5  370.75
  5099.9  370.71  5100.2  370.21  5103.7  370.21  5103.9  370.71  5109.9  372.00
  5116.3  372.64  5153.9  373.58  5194.8  375.25  5294.0  384.92  5315.6  386.15
#Mann=5,-1,0
  4699.4    0.12       0  4895.7     0.1       0  5099.9    0.07       0
  5103.9     0.1       0  5153.9    0.05       0
Bank Sta=5099.9,5103.9
Exp/Cntr=0.3,0.1

Type RM Length L Ch R = 1,2881,229,229,229
BEGIN DESCRIPTION:
Walnut95 8.0
END DESCRIPTION:
XS GIS Cut Line= 3
      2761097.06      6757341.38      2760826.00      6757111.00
      2760591.59      6756918.28
#Sta/Elev= 30
  4644.0  383.94  4775.3  377.45  4836.6  374.92  4843.2  373.57  4893.8  371.05
  4921.2  371.60  4937.7  369.86  4971.8  369.48  4996.5  367.75  5013.4  367.99
  5021.3  369.09  5027.7  368.04  5049.9  369.69  5075.4  367.58  5075.7  367.08
  5079.4  367.58  5099.5  369.98  5113.8  370.21  5120.3  369.17  5155.1  369.92
  5177.7  369.28  5198.5  371.56  5206.4  374.17  5212.8  374.01  5233.6  377.54
  5241.5  383.67  5248.0  385.57  5254.1  385.62  5280.8  384.17  5303.2  384.20
#Mann=8,-1,0
  4644.0    0.12       0  4775.3     0.1       0  4937.7    0.12       0
  5075.4    0.07       0  5079.4    0.12       0  5155.1     0.1       0
  5254.1    0.12       0  5280.8     0.1       0
Bank Sta=5075.4,5079.4
Exp/Cntr=0.3,0.1

Type RM Length L Ch R = 1,2652,252,252,252
BEGIN DESCRIPTION:
Walnut95 7.0
END DESCRIPTION:
XS GIS Cut Line= 3
      2761225.99      6757260.99      2761025.90      6757000.67
      2760725.99      6756710.99
#Sta/Elev= 30
  4644.6  384.80  4730.7  380.32  4780.5  376.81  4822.2  375.07  4836.7  373.07
  4969.6  367.53  5003.9  367.41  5029.1  367.05  5034.6  367.57  5043.2  366.95
  5085.7  367.25  5092.9  364.12  5097.8  364.03  5098.1  363.53  5101.8  364.03
  5107.0  367.57  5142.3  367.64  5184.7  372.30  5241.3  375.31  5248.5  376.42
  5262.7  377.14  5269.6  379.47  5272.9  379.26  5276.8  379.02  5283.8  380.65
  5291.0  378.32  5297.9  378.33  5368.7  382.85  5375.9  384.17  5389.9  384.61
#Mann=6,-1,0
  4644.6    0.05       0  5003.9    0.12       0  5034.6     0.1       0
  5097.8    0.04       0  5101.8     0.1       0  5272.9    0.05       0
Bank Sta=5097.8,5101.8
Exp/Cntr=0.3,0.1

Type RM Length L Ch R = 1,2400,112,112,112
BEGIN DESCRIPTION:
Walnut95 6.0
END DESCRIPTION:
XS GIS Cut Line= 3
      2761326.01      6757061.01      2761026.00      6756761.00
      2760875.96      6756660.98
#Sta/Elev= 30
  4580.5  378.40  4584.0  378.40  4594.7  376.31  4637.1  373.25  4651.2  373.01
  4707.8  370.12  4755.2  368.71  4764.4  368.72  4778.5  367.87  4820.9  366.71
  4927.6  366.02  4976.5  365.84  4990.6  366.19  5001.9  365.76  5025.2  366.21
  5048.3  366.24  5061.4  363.01  5061.6  362.51  5065.1  362.51  5065.4  363.01
  5069.4  365.52  5076.9  369.32  5090.4  371.57  5120.5  373.81  5126.5  374.88
  5141.5  374.75  5149.0  375.57  5177.5  377.04  5184.2  377.80  5185.1  377.80
#Mann=8,-1,0
  4580.5    0.05       0  4755.2    0.12       0  4927.6     0.1       0
  5001.9    0.12       0  5025.2     0.1       0  5061.4    0.07       0
  5065.4     0.1       0  5184.2    0.05       0
Bank Sta=5061.4,5065.4
Exp/Cntr=0.3,0.1

Type RM Length L Ch R = 1,2288,134,134,134
BEGIN DESCRIPTION:
Walnut95 5.3
END DESCRIPTION:
XS GIS Cut Line= 3
      2761430.21      6756983.82      2761078.31      6756658.12
      2760952.91      6756478.45
#Sta/Elev= 30
  4556.5  374.24  4562.2  374.24  4582.7  372.26  4596.9  371.77  4603.7  370.99
  4646.2  369.71  4667.7  368.52  4745.4  367.18  4861.6  366.22  4875.6  366.05
  4929.7  365.77  4971.7  364.61  4993.5  364.97  5007.4  364.74  5014.2  365.39
  5023.7  363.84  5026.4  363.66  5026.6  363.16  5030.1  363.16  5030.4  363.66
  5034.2  365.28  5079.4  367.74  5093.5  368.13  5100.4  367.18  5121.3  367.68
  5142.2  367.21  5157.1  368.40  5178.8  372.48  5207.7  374.39  5255.1  375.20
#Mann=7,-1,0
  4556.5    0.05       0  4861.6    0.12       0  4875.6    0.05       0
  4993.5    0.12       0  5023.7    0.05       0  5026.4    0.07       0
  5030.4    0.05       0
Bank Sta=5026.4,5030.4
Exp/Cntr=0.3,0.1

Type RM Length L Ch R = 1,2154,269,269,269
BEGIN DESCRIPTION:
Walnut95 5.0
END DESCRIPTION:
XS GIS Cut Line= 3
      2761505.07      6756880.85      2761153.18      6756555.17
      2761134.57      6756294.60
#Sta/Elev= 30
  4539.2  376.30  4701.4  367.83  4722.4  367.09  4828.5  366.35  4871.0  365.31
  4878.4  365.66  4906.2  364.50  4913.5  364.78  4920.3  364.38  4927.7  364.79
  4970.2  363.94  4984.4  361.05  4991.2  360.20  5012.7  359.58  5018.1  360.75
  5032.9  360.41  5042.9  359.17  5046.6  357.14  5046.9  356.64  5050.4  356.64
  5050.6  357.14  5053.6  359.48  5062.9  358.99  5073.0  363.11  5083.0  364.11
  5183.3  365.16  5194.0  366.36  5213.3  367.48  5233.4  369.58  5279.9  372.54
#Mann=3,-1,0
  4539.2    0.05       0  5046.6    0.04       0  5050.6    0.05       0
Bank Sta=5046.6,5050.6
Exp/Cntr=0.3,0.1

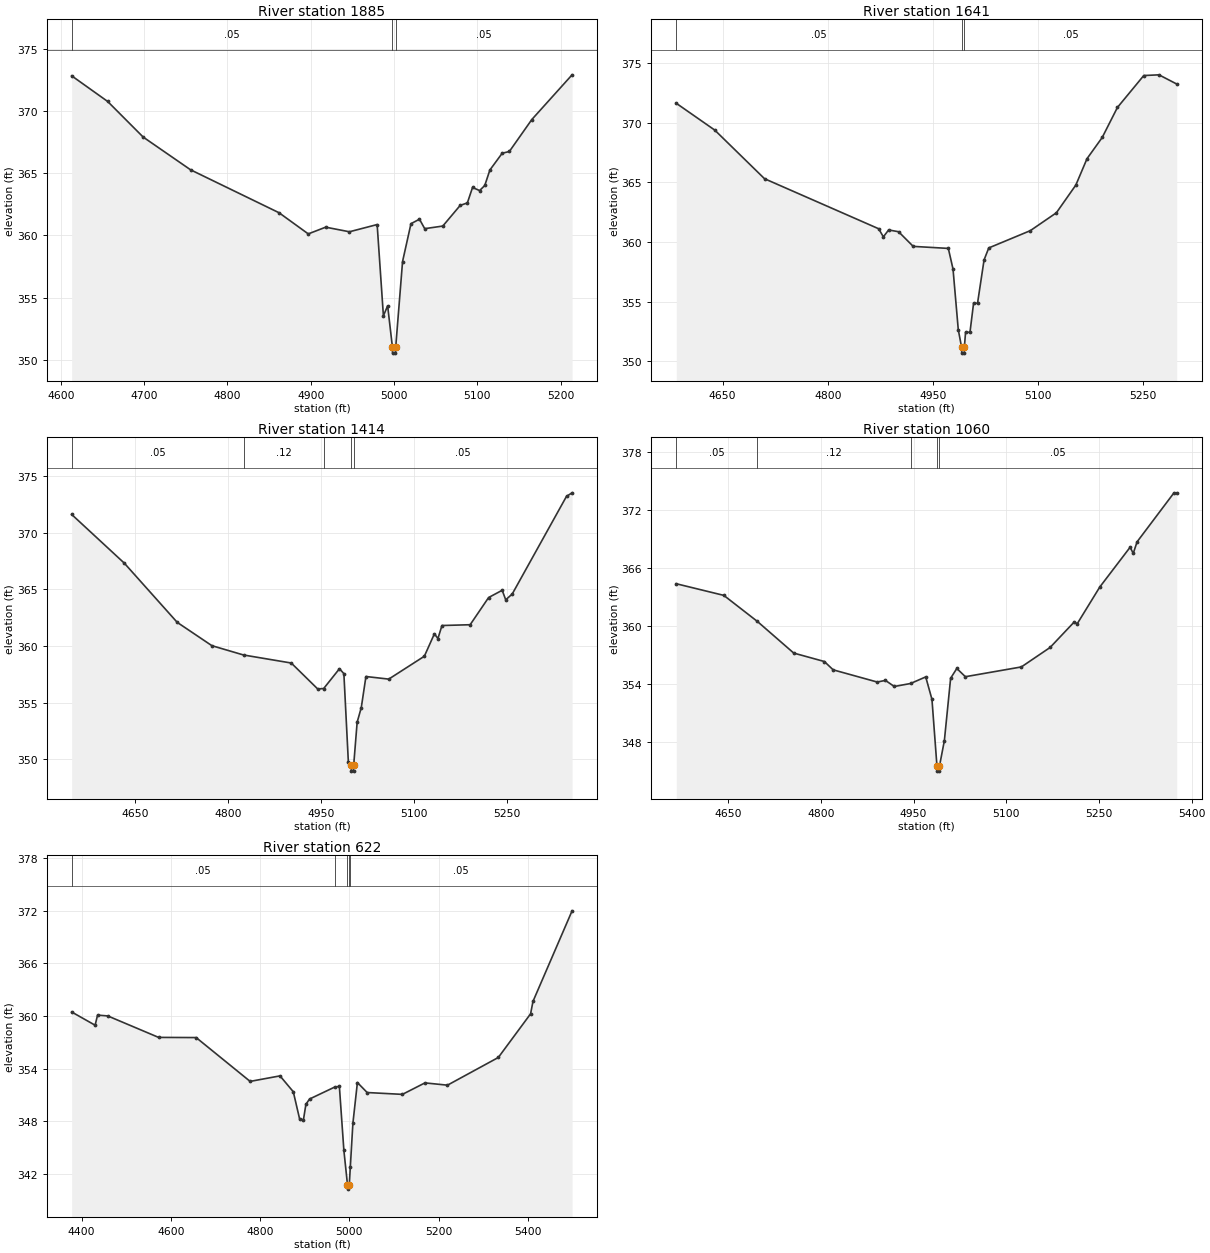
Type RM Length L Ch R = 1,1885,244,244,244
BEGIN DESCRIPTION:
Walnut95 4.0
END DESCRIPTION:
XS GIS Cut Line= 4
      2761589.32      6756708.65      2761355.34      6756444.73
      2761342.24      6756373.60      2761240.13      6756230.65
#Sta/Elev= 30
  4613.0  372.82  4656.2  370.76  4698.8  367.90  4755.7  365.27  4861.9  361.82
  4897.0  360.12  4917.9  360.66  4946.4  360.29  4979.7  360.87  4987.2  353.54
  4992.3  354.34  4998.0  351.04  4998.2  350.54  5001.7  350.54  5002.0  351.04
  5010.2  357.90  5020.3  360.94  5030.5  361.30  5036.8  360.54  5058.5  360.75
  5079.4  362.41  5088.0  362.61  5094.2  363.85  5102.7  363.60  5108.9  364.01
  5115.0  365.25  5129.8  366.60  5138.4  366.74  5165.4  369.31  5213.7  372.90
#Mann=3,-1,0
  4613.0    0.05       0  4998.0    0.04       0  5002.0    0.05       0
Bank Sta=4998,5002
Exp/Cntr=0.3,0.1

Type RM Length L Ch R = 1,1641,227,227,227
BEGIN DESCRIPTION:
Walnut95 3.0
END DESCRIPTION:
XS GIS Cut Line= 3
      2761785.02      6756539.82      2761476.00      6756261.00
      2761216.31      6756115.06
#Sta/Elev= 30
  4583.9  371.64  4638.8  369.39  4709.8  365.31  4872.7  361.11  4879.4  360.43
  4886.9  361.01  4901.1  360.86  4922.0  359.63  4972.1  359.46  4978.8  357.73
  4986.3  352.64  4991.0  351.17  4991.3  350.67  4994.8  350.67  4995.0  351.17
  4996.7  352.42  5003.0  352.42  5008.1  354.84  5013.8  354.86  5023.1  358.49
  5029.8  359.50  5089.1  360.95  5126.3  362.45  5154.1  364.78  5170.0  366.99
  5191.7  368.77  5213.4  371.29  5251.0  373.97  5272.7  374.03  5298.0  373.26
#Mann=3,-1,0
  4583.9    0.05       0  4991.0    0.04       0  4995.0    0.05       0
Bank Sta=4991,4995
Exp/Cntr=0.3,0.1

Type RM Length L Ch R = 1,1414,354,354,354
BEGIN DESCRIPTION:
Walnut95 2.0
END DESCRIPTION:
XS GIS Cut Line= 3
      2761876.02      6756361.02      2761491.60      6756023.25
      2761231.23      6755882.73
#Sta/Elev= 30
  4547.8  371.62  4632.8  367.32  4718.1  362.10  4774.1  360.04  4825.1  359.22
  4902.2  358.51  4944.9  356.22  4954.5  356.26  4980.0  358.01  4987.1  357.57
  4994.3  349.81  4998.9  349.47  4999.2  348.97  5002.7  348.97  5002.9  349.47
  5008.5  353.28  5015.2  354.58  5022.7  357.32  5059.5  357.09  5117.0  359.11
  5133.2  361.09  5138.9  360.67  5145.4  361.82  5190.9  361.89  5220.7  364.29
  5242.6  364.93  5248.3  364.09  5258.8  364.60  5346.4  373.22  5355.4  373.53
#Mann=5,-1,0
  4547.8    0.05       0  4825.1    0.12       0  4954.5    0.05       0
  4998.9    0.04       0  5002.9    0.05       0
Bank Sta=4998.9,5002.9
Exp/Cntr=0.3,0.1

Type RM Length L Ch R = 1,1060,438,438,438
BEGIN DESCRIPTION:
Walnut95 1.0
END DESCRIPTION:
XS GIS Cut Line= 3
      2761925.51      6756019.10      2761648.64      6755787.69
      2761202.33      6755738.10
#Sta/Elev= 30
  4565.9  364.36  4642.8  363.16  4697.1  360.47  4756.0  357.20  4805.5  356.33
  4819.8  355.47  4891.1  354.21  4904.4  354.38  4918.7  353.75  4945.1  354.06
  4969.6  354.74  4979.7  352.42  4987.8  345.51  4988.0  345.01  4991.5  345.01
  4991.8  345.51  4999.8  348.17  5009.9  354.60  5019.9  355.61  5033.8  354.76
  5124.4  355.77  5170.9  357.78  5209.9  360.41  5214.9  360.24  5251.4  364.03
  5300.4  368.13  5305.5  367.50  5311.7  368.69  5371.4  373.75  5375.8  373.75
#Mann=5,-1,0
  4565.9    0.05       0  4697.1    0.12       0  4945.1    0.05       0
  4987.8    0.04       0  4991.8    0.05       0
Bank Sta=4987.8,4991.8
Exp/Cntr=0.3,0.1

Type RM Length L Ch R = 1,622,0,0,0
BEGIN DESCRIPTION:
Walnut95 0.5
END DESCRIPTION:
XS GIS Cut Line= 3
      2761983.40      6755903.45      2761751.95      6755411.63
      2761179.23      6755333.34
#Sta/Elev= 30
  4377.8  360.46  4430.3  358.95  4435.8  360.10  4458.6  360.01  4572.6  357.56
  4656.8  357.54  4777.8  352.54  4844.7  353.17  4874.5  351.36  4888.9  348.21
  4897.3  348.17  4902.8  349.93  4911.0  350.53  4967.2  351.89  4977.8  351.97
  4987.9  344.67  4996.0  340.75  4996.3  340.25  5000.0  340.75  5002.3  342.74
  5008.1  347.75  5018.2  352.41  5040.1  351.27  5119.1  351.06  5169.6  352.37
  5220.1  352.11  5334.1  355.27  5406.4  360.25  5411.8  361.67  5499.4  372.00
#Mann=5,-1,0
  4377.8    0.05       0  4967.2    0.12       0  4996.0    0.07       0
  5000.0    0.12       0  5002.3    0.05       0
Bank Sta=4996,5000
Exp/Cntr=0.3,0.1

Chan Stop Cuts=-1