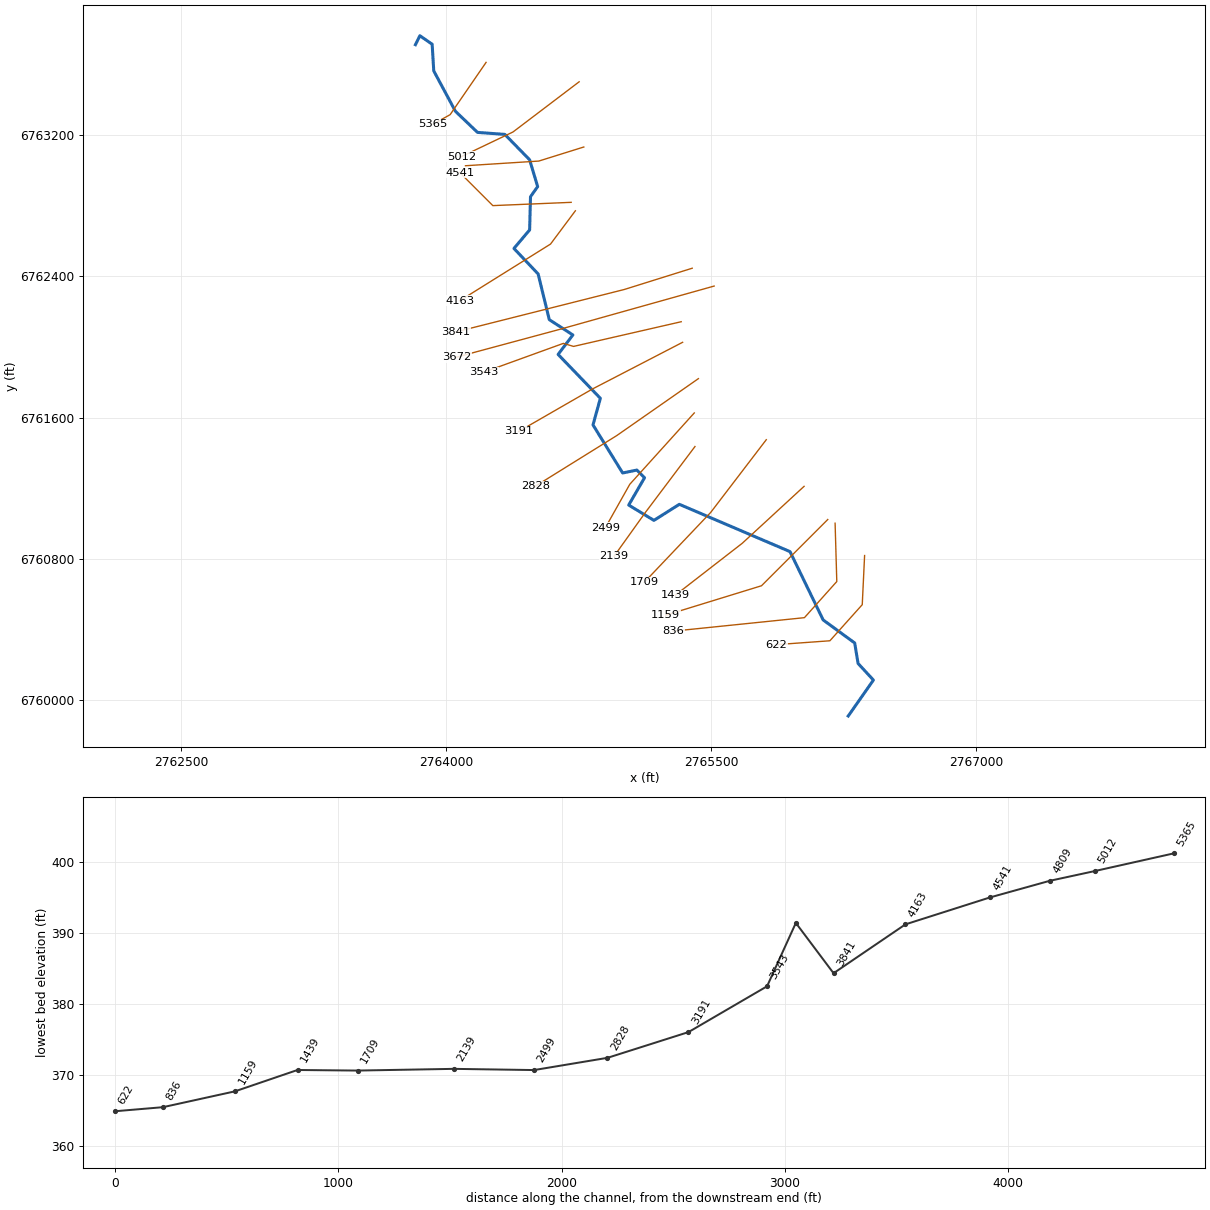
--- Walnut96.prj (project) ---

Proj Title=Walnut96 Base Level Engineering
Current Plan=p01
Default Exp/Contr=0.3,0.1
English Units
Geom File=g01
Flow File=f01
Plan File=p01
BEGIN DESCRIPTION:
Walnut96
END DESCRIPTION:

--- Walnut96.p01 (plan) ---

Plan Title=Multiple Run
Short Identifier=Multiple
Geom File=g01
Flow File=f01
Subcritical Flow
K Sum by GR= 0
Std Step Tol= 0.01
Critical Tol= 0.01
Num of Std Step Trials= 20
Max Error Tol= 0.3
Flow Tol Ratio= 0.001
Split Flow NTrial= 30
Split Flow Tol= 0.02
Split Flow Ratio= 0.02
Log Output Level= 0
Friction Slope Method= 1
Unsteady Friction Slope Method= 2
Unsteady Bridges Friction Slope Method= 1
Parabolic Critical Depth
Global Vel Dist=  1 , 1 , 1
Global Log Level= 0
CheckData=True
Encroach Param= -1, 0, 0, 0
BEGIN DESCRIPTION:
Multiple Run
END DESCRIPTION:

--- Walnut96.f01 (steady flow) ---

Flow Title=Multiple
Number of Profiles=7
Profile Names=10-year,25-year,50-year,1pct_min,100-year,1pct_plu,500-year
River Rch & RM= Walnut96,Reach-1,5365
     470     637     776     471     940    1876    1381
River Rch & RM= Walnut96,Reach-1,3841
     572     781     955     582    1161    2316    1717
Boundary for River Rch & Prof#=Walnut96,Reach-1,1
Up Type=0
Dn Type=3
Dn Slope=0.005
Boundary for River Rch & Prof#=Walnut96,Reach-1,2
Up Type=0
Dn Type=3
Dn Slope=0.005
Boundary for River Rch & Prof#=Walnut96,Reach-1,3
Up Type=0
Dn Type=3
Dn Slope=0.005
Boundary for River Rch & Prof#=Walnut96,Reach-1,4
Up Type=0
Dn Type=3
Dn Slope=0.005
Boundary for River Rch & Prof#=Walnut96,Reach-1,5
Up Type=0
Dn Type=3
Dn Slope=0.005
Boundary for River Rch & Prof#=Walnut96,Reach-1,6
Up Type=0
Dn Type=3
Dn Slope=0.005
Boundary for River Rch & Prof#=Walnut96,Reach-1,7
Up Type=0
Dn Type=3
Dn Slope=0.005

--- Walnut96.g01 (geometry) ---

Geom Title=Existing Conditions

River Reach=Walnut96,Reach-1
Reach XY= 30
      2763826.00      6763711.00      2763851.18      6763761.84
      2763920.63      6763713.77      2763929.76      6763562.56
      2764052.29      6763334.18      2764177.47      6763214.54
      2764332.19      6763203.18      2764472.39      6763059.50
      2764517.92      6762907.70      2764477.38      6762850.56
      2764472.44      6762662.46      2764383.60      6762557.66
      2764520.48      6762413.43      2764583.75      6762154.55
      2764717.15      6762067.95      2764633.61      6761957.67
      2764872.87      6761709.37      2764831.11      6761558.71
      2764999.01      6761286.64      2765079.65      6761303.10
      2765122.91      6761259.79      2765033.22      6761104.96
      2765176.08      6761018.30      2765319.87      6761109.22
      2765946.48      6760841.38      2766134.02      6760454.66
      2766312.61      6760324.33      2766331.55      6760208.57
      2766418.40      6760114.33      2766276.00      6759911.00

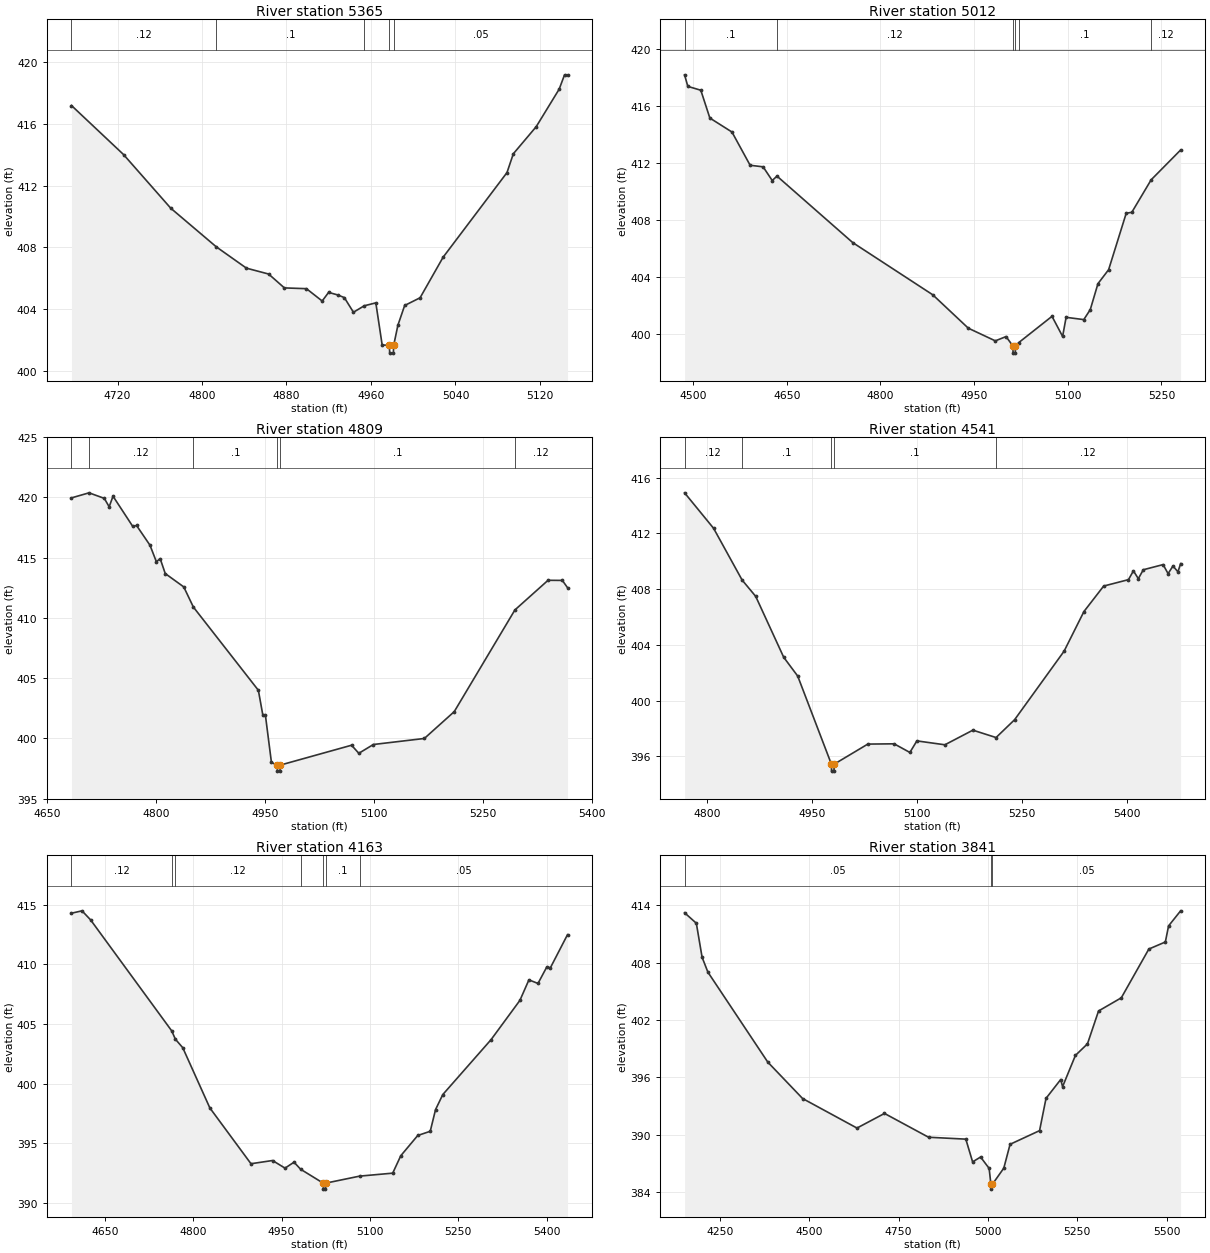
Type RM Length L Ch R = 1,5365,353,353,353
BEGIN DESCRIPTION:
Walnut96 14.0
END DESCRIPTION:
XS GIS Cut Line= 3
      2764225.98      6763610.97      2764022.56      6763315.11
      2763926.03      6763261.02
#Sta/Elev= 30
  4676.4  417.20  4725.7  414.02  4770.4  410.54  4813.6  408.03  4842.1  406.65
  4863.1  406.27  4878.0  405.37  4898.9  405.32  4913.8  404.52  4919.9  405.08
  4928.7  404.91  4934.8  404.74  4943.4  403.79  4953.6  404.21  4964.6  404.40
  4970.6  401.67  4977.5  401.64  4977.7  401.14  4981.2  401.14  4981.5  401.64
  4985.5  402.95  4991.9  404.23  5006.5  404.73  5028.3  407.36  5088.8  412.85
  5094.8  414.07  5116.5  415.83  5138.2  418.26  5143.3  419.19  5146.1  419.19
#Mann=5,-1,0
  4676.4    0.12       0  4813.6     0.1       0  4953.6    0.05       0
  4977.5    0.04       0  4981.5    0.05       0
Bank Sta=4977.5,4981.5
Exp/Cntr=0.3,0.1

Type RM Length L Ch R = 1,5012,203,203,203
BEGIN DESCRIPTION:
Walnut96 13.0
END DESCRIPTION:
XS GIS Cut Line= 3
      2764752.67      6763500.97      2764378.31      6763216.88
      2764085.42      6763077.07
#Sta/Elev= 30
  4486.3  418.17  4491.5  417.36  4512.3  417.09  4526.8  415.14  4562.2  414.16
  4591.3  411.83  4612.1  411.72  4626.7  410.76  4634.3  411.07  4755.6  406.41
  4883.8  402.75  4940.7  400.41  4984.0  399.52  5001.2  399.82  5012.2  399.16
  5012.5  398.66  5016.0  398.66  5016.2  399.16  5021.3  399.39  5074.8  401.24
  5091.8  399.83  5097.4  401.17  5125.7  401.01  5136.1  401.71  5148.4  403.53
  5165.5  404.51  5193.7  408.47  5202.6  408.53  5233.6  410.81  5280.8  412.90
#Mann=6,-1,0
  4486.3     0.1       0  4634.3    0.12       0  5012.2    0.07       0
  5016.2    0.12       0  5021.3     0.1       0  5233.6    0.12       0
Bank Sta=5012.2,5016.2
Exp/Cntr=0.3,0.1

Type RM Length L Ch R = 1,4809,268,268,268
BEGIN DESCRIPTION:
Walnut96 12.0
END DESCRIPTION:
XS GIS Cut Line= 3
      2764779.18      6763131.92      2764524.33      6763052.28
      2764109.27      6763025.84
#Sta/Elev= 30
  4683.6  419.96  4707.8  420.38  4728.8  419.92  4735.5  419.22  4740.8  420.10
  4768.0  417.59  4773.2  417.67  4791.7  416.03  4800.5  414.66  4805.7  414.92
  4812.7  413.68  4838.2  412.57  4851.4  410.90  4940.9  403.99  4947.1  401.92
  4950.6  401.92  4958.9  398.00  4967.0  397.78  4967.2  397.28  4970.7  397.28
  4971.0  397.78  5069.2  399.43  5079.2  398.76  5099.2  399.49  5169.4  399.99
  5210.6  402.22  5294.1  410.66  5339.7  413.12  5359.4  413.11  5366.5  412.51
#Mann=6,-1,0
  4683.6     0.1       0  4707.8    0.12       0  4851.4     0.1       0
  4967.0    0.07       0  4971.0     0.1       0  5294.1    0.12       0
Bank Sta=4967,4971
Exp/Cntr=0.3,0.1

Type RM Length L Ch R = 1,4541,378,378,378
BEGIN DESCRIPTION:
Walnut96 11.0
END DESCRIPTION:
XS GIS Cut Line= 3
      2764707.48      6762818.65      2764264.15      6762800.06
      2764076.92      6762987.29
#Sta/Elev= 30
  4768.0  414.91  4809.5  412.36  4850.2  408.65  4869.6  407.48  4909.6  403.11
  4929.6  401.76  4977.7  395.44  4977.9  394.94  4981.4  394.94  4981.7  395.44
  5029.7  396.88  5067.3  396.90  5089.8  396.28  5099.8  397.11  5139.8  396.83
  5179.8  397.88  5212.9  397.35  5239.4  398.63  5310.1  403.55  5338.4  406.39
  5366.6  408.22  5402.0  408.68  5409.1  409.31  5416.1  408.75  5423.2  409.39
  5451.5  409.76  5458.6  409.11  5465.6  409.66  5472.7  409.24  5476.5  409.83
#Mann=5,-1,0
  4768.0    0.12       0  4850.2     0.1       0  4977.7    0.07       0
  4981.7     0.1       0  5212.9    0.12       0
Bank Sta=4977.7,4981.7
Exp/Cntr=0.3,0.1

Type RM Length L Ch R = 1,4163,322,322,322
BEGIN DESCRIPTION:
Walnut96 10.0
END DESCRIPTION:
XS GIS Cut Line= 3
      2764731.40      6762770.84      2764590.70      6762582.36
      2764075.99      6762260.99
#Sta/Elev= 30
  4593.4  414.30  4611.3  414.50  4625.9  413.74  4763.6  404.43  4769.7  403.74
  4782.3  403.02  4828.3  397.97  4898.1  393.29  4934.7  393.56  4955.9  392.92
  4971.2  393.42  4982.3  392.83  5020.8  391.66  5021.0  391.16  5024.5  391.16
  5024.8  391.66  5082.5  392.25  5138.7  392.50  5152.4  393.96  5181.2  395.66
  5202.4  396.01  5211.4  397.83  5223.7  399.09  5305.7  403.70  5354.6  406.99
  5369.9  408.71  5385.3  408.41  5400.0  409.77  5406.5  409.74  5435.4  412.50
#Mann=7,-1,0
  4593.4    0.12       0  4763.6     0.1       0  4769.7    0.12       0
  4982.3     0.1       0  5020.8    0.07       0  5024.8     0.1       0
  5082.5    0.05       0
Bank Sta=5020.8,5024.8
Exp/Cntr=0.3,0.1

Type RM Length L Ch R = 1,3841,169,169,169
BEGIN DESCRIPTION:
Walnut96 9.0
END DESCRIPTION:
XS GIS Cut Line= 3
      2765392.78      6762445.70      2765008.40      6762325.34
      2764053.35      6762084.64
#Sta/Elev= 30
  4151.3  413.21  4184.2  412.11  4200.3  408.55  4216.6  406.99  4384.1  397.58
  4481.5  393.77  4633.6  390.68  4710.6  392.21  4833.8  389.72  4938.1  389.52
  4957.1  387.14  4979.4  387.65  5003.3  386.46  5008.3  384.79  5008.6  384.29
  5012.3  384.79  5044.4  386.49  5061.9  388.98  5144.4  390.41  5162.5  393.79
  5203.6  395.76  5208.8  395.01  5244.7  398.28  5278.4  399.49  5309.4  402.93
  5373.1  404.31  5450.1  409.41  5496.3  410.15  5505.3  411.83  5539.0  413.41
#Mann=3,-1,0
  4151.3    0.05       0  5008.3    0.05       0  5012.3    0.05       0
Bank Sta=5008.3,5012.3
Exp/Cntr=0.3,0.1

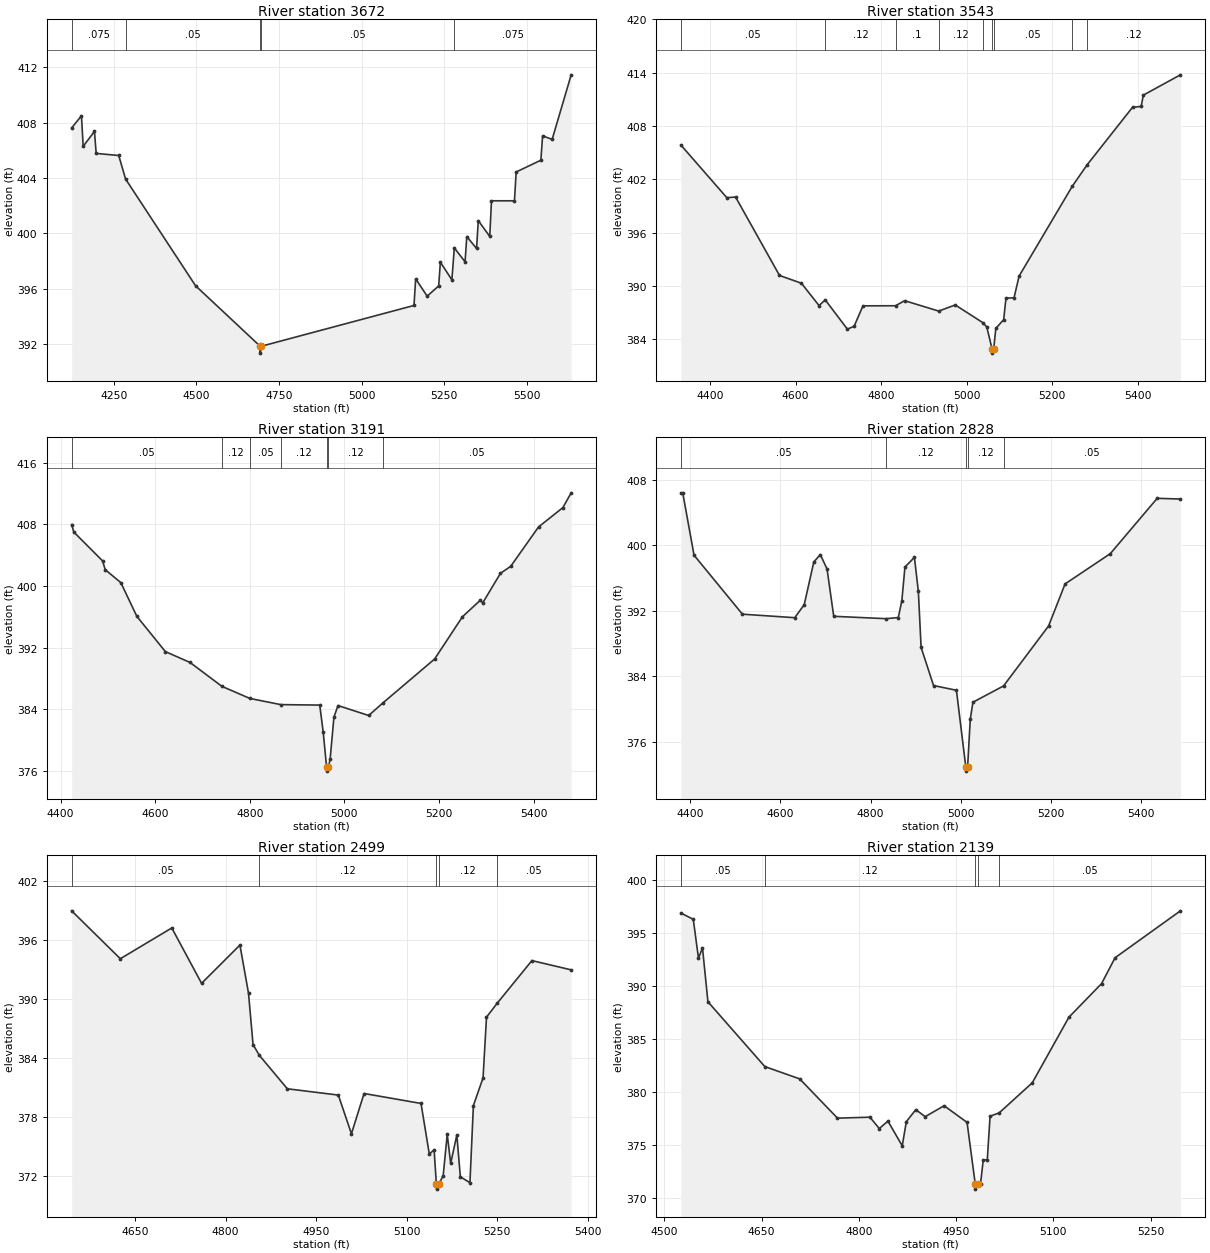
Type RM Length L Ch R = 1,3672,129,129,129
BEGIN DESCRIPTION:
Walnut96 8.5
END DESCRIPTION:
XS GIS Cut Line= 3
      2765516.97      6762344.74      2764641.15      6762099.17
      2764060.35      6761942.70
#Sta/Elev= 30
  4122.6  407.61  4152.3  408.48  4157.5  406.28  4191.6  407.36  4196.8  405.77
  4265.0  405.62  4285.8  403.92  4497.5  396.22  4692.8  391.86  4693.1  391.36
  4696.8  391.86  5158.2  394.80  5163.3  396.72  5198.1  395.47  5232.9  396.21
  5238.0  397.92  5272.8  396.65  5280.2  398.95  5312.7  397.95  5317.9  399.77
  5347.5  398.91  5352.7  400.92  5387.4  399.78  5392.6  402.35  5462.1  402.35
  5467.3  404.43  5542.0  405.28  5547.2  407.04  5576.1  406.78  5633.7  411.44
#Mann=5,-1,0
  4122.6   0.075       0  4285.8    0.05       0  4692.8    0.05       0
  4696.8    0.05       0  5280.2   0.075       0
Bank Sta=4692.8,4696.8
Exp/Cntr=0.3,0.1

Type RM Length L Ch R = 1,3543,352,352,352
BEGIN DESCRIPTION:
Walnut96 8.0
END DESCRIPTION:
XS GIS Cut Line= 4
      2765330.61      6762142.86      2764721.09      6762003.10
      2764663.33      6762020.24      2764210.40      6761856.21
#Sta/Elev= 30
  4332.2  405.86  4439.5  399.94  4460.0  400.01  4562.6  391.19  4613.9  390.31
  4655.0  387.80  4669.5  388.44  4721.2  385.15  4737.0  385.47  4757.6  387.77
  4833.7  387.78  4855.0  388.35  4934.6  387.18  4973.3  387.87  5038.0  385.87
  5046.9  385.40  5059.2  382.95  5059.4  382.45  5063.2  382.95  5068.1  385.23
  5086.5  386.22  5091.8  388.63  5110.7  388.68  5122.5  391.12  5246.7  401.22
  5281.5  403.64  5387.6  410.11  5407.6  410.20  5412.9  411.48  5499.5  413.76
#Mann=9,-1,0
  4332.2    0.05       0  4669.5    0.12       0  4833.7     0.1       0
  4934.6    0.12       0  5038.0    0.05       0  5059.2    0.07       0
  5063.2    0.05       0  5246.7   0.075       0  5281.5    0.12       0
Bank Sta=5059.2,5063.2
Exp/Cntr=0.3,0.1

Type RM Length L Ch R = 1,3191,363,363,363
BEGIN DESCRIPTION:
Walnut96 7.0
END DESCRIPTION:
XS GIS Cut Line= 3
      2765338.43      6762026.40      2764826.00      6761761.00
      2764410.75      6761521.81
#Sta/Elev= 30
  4423.2  407.96  4427.8  407.00  4488.6  403.26  4494.2  402.12  4527.2  400.44
  4561.1  396.07  4621.4  391.50  4673.7  390.09  4740.9  387.00  4800.1  385.43
  4865.5  384.63  4947.8  384.57  4955.2  381.05  4962.3  376.51  4962.5  376.01
  4966.3  376.51  4969.9  377.64  4977.8  383.00  4986.4  384.51  5051.3  383.22
  5081.0  384.83  5190.7  390.54  5249.6  396.02  5286.9  398.13  5292.7  397.84
  5330.0  401.65  5351.6  402.55  5410.5  407.66  5461.9  410.16  5479.5  412.08
#Mann=7,-1,0
  4423.2    0.05       0  4740.9    0.12       0  4800.1    0.05       0
  4865.5    0.12       0  4962.3    0.07       0  4966.3    0.12       0
  5081.0    0.05       0
Bank Sta=4962.3,4966.3
Exp/Cntr=0.3,0.1

Type RM Length L Ch R = 1,2828,329,329,329
BEGIN DESCRIPTION:
Walnut96 6.0
END DESCRIPTION:
XS GIS Cut Line= 3
      2765427.74      6761820.64      2764965.69      6761498.37
      2764503.67      6761211.06
#Sta/Elev= 30
  4379.4  406.40  4383.5  406.40  4408.5  398.78  4515.8  391.57  4631.8  391.14
  4652.8  392.73  4674.1  397.96  4688.5  398.85  4703.4  397.09  4718.2  391.31
  4834.3  391.02  4861.3  391.16  4869.2  393.20  4876.1  397.34  4897.1  398.51
  4905.8  394.35  4911.9  387.50  4939.5  382.85  4990.2  382.27  5011.0  372.89
  5011.3  372.39  5015.0  372.89  5020.9  378.74  5026.8  380.81  5094.6  382.80
  5194.5  390.13  5231.1  395.27  5331.4  398.97  5435.3  405.73  5486.8  405.64
#Mann=5,-1,0
  4379.4    0.05       0  4834.3    0.12       0  5011.0    0.07       0
  5015.0    0.12       0  5094.6    0.05       0
Bank Sta=5011,5015
Exp/Cntr=0.3,0.1

Type RM Length L Ch R = 1,2499,360,360,360
BEGIN DESCRIPTION:
Walnut96 5.0
END DESCRIPTION:
XS GIS Cut Line= 3
      2765404.42      6761626.50      2765039.46      6761222.71
      2764900.86      6760976.31
#Sta/Elev= 30
  4545.2  398.96  4625.8  394.09  4711.0  397.22  4760.3  391.59  4823.8  395.48
  4838.0  390.59  4845.5  385.37  4855.7  384.29  4902.3  380.87  4986.7  380.23
  5008.4  376.30  5029.3  380.39  5123.6  379.38  5137.3  374.24  5145.3  374.66
  5149.0  371.17  5149.3  370.67  5153.0  371.17  5160.3  372.04  5167.0  376.24
  5172.7  373.29  5182.9  376.17  5188.7  371.92  5204.6  371.33  5210.3  379.16
  5226.3  381.98  5232.0  388.15  5249.6  389.56  5307.2  393.90  5372.2  392.96
#Mann=5,-1,0
  4545.2    0.05       0  4855.7    0.12       0  5149.0    0.07       0
  5153.0    0.12       0  5249.6    0.05       0
Bank Sta=5149,5153
Exp/Cntr=0.3,0.1

Type RM Length L Ch R = 1,2139,430,430,430
BEGIN DESCRIPTION:
Walnut96 4.0
END DESCRIPTION:
XS GIS Cut Line= 3
      2765408.32      6761436.28      2765126.00      6761061.00
      2764950.89      6760816.07
#Sta/Elev= 30
  4525.4  396.86  4544.5  396.27  4552.5  392.61  4558.7  393.58  4567.1  388.50
  4654.9  382.39  4708.7  381.23  4767.0  377.53  4817.0  377.62  4831.5  376.55
  4844.8  377.25  4866.9  374.92  4873.2  377.20  4887.8  378.33  4902.3  377.67
  4931.5  378.70  4966.9  377.13  4979.5  371.34  4979.7  370.84  4983.5  371.34
  4987.7  371.35  4991.9  373.60  4998.1  373.60  5002.4  377.71  5016.5  378.03
  5067.5  380.86  5124.0  387.04  5174.4  390.21  5195.3  392.65  5296.1  397.07
#Mann=5,-1,0
  4525.4    0.05       0  4654.9    0.12       0  4979.5    0.07       0
  4983.5    0.12       0  5016.5    0.05       0
Bank Sta=4979.5,4983.5
Exp/Cntr=0.3,0.1

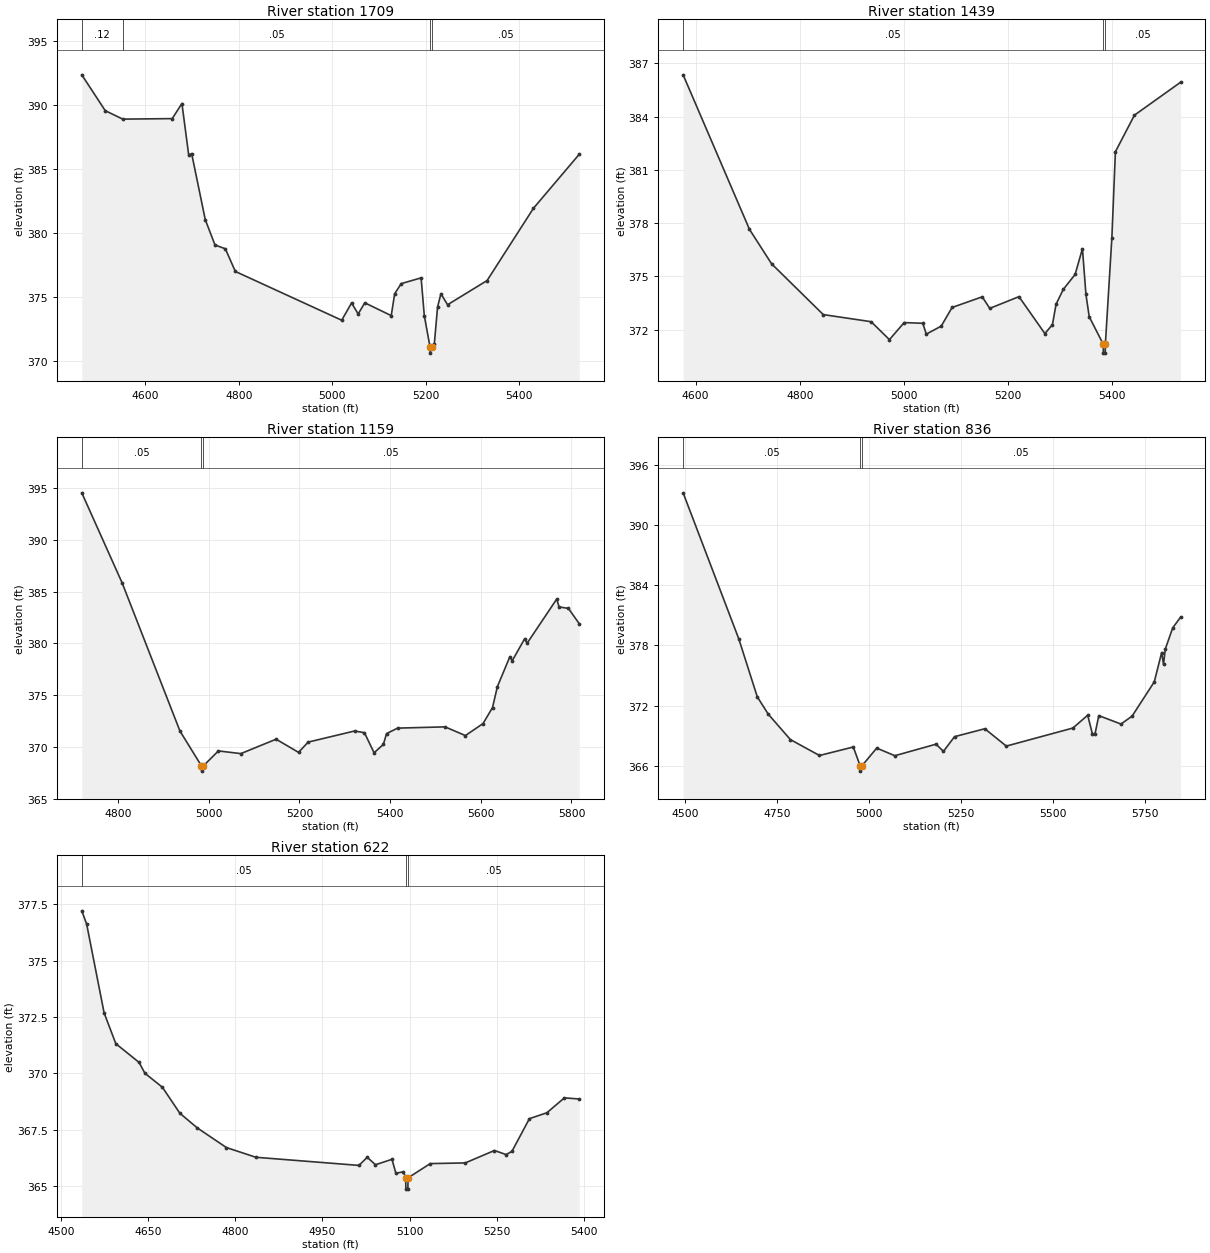
Type RM Length L Ch R = 1,1709,270,270,270
BEGIN DESCRIPTION:
Walnut96 3.0
END DESCRIPTION:
XS GIS Cut Line= 3
      2765812.06      6761475.05      2765497.59      6761063.53
      2765121.00      6760667.52
#Sta/Elev= 30
  4464.1  392.34  4514.3  389.54  4551.7  388.88  4657.6  388.92  4678.4  390.10
  4692.9  386.07  4699.2  386.19  4728.3  381.03  4749.1  379.05  4771.3  378.75
  4792.7  376.98  5020.3  373.17  5041.4  374.52  5055.5  373.66  5069.7  374.53
  5126.3  373.53  5133.6  375.24  5147.7  376.03  5190.2  376.48  5197.1  373.51
  5209.2  371.10  5209.5  370.60  5213.2  371.10  5218.5  371.33  5225.4  374.20
  5232.6  375.24  5246.8  374.38  5331.4  376.27  5430.5  381.91  5528.5  386.13
#Mann=4,-1,0
  4464.1    0.12       0  4551.7    0.05       0  5209.2    0.04       0
  5213.2    0.05       0
Bank Sta=5209.2,5213.2
Exp/Cntr=0.3,0.1

Type RM Length L Ch R = 1,1439,280,280,280
BEGIN DESCRIPTION:
Walnut96 2.0
END DESCRIPTION:
XS GIS Cut Line= 3
      2766026.04      6761211.03      2765676.19      6760888.82
      2765297.14      6760594.86
#Sta/Elev= 30
  4575.9  386.35  4703.3  377.65  4745.8  375.71  4845.0  372.85  4936.9  372.45
  4972.1  371.44  5000.4  372.40  5036.2  372.36  5042.9  371.75  5071.6  372.20
  5092.4  373.25  5150.3  373.85  5164.8  373.20  5220.9  373.86  5270.7  371.78
  5285.2  372.29  5292.2  373.44  5306.0  374.27  5328.7  375.11  5342.8  376.56
  5349.5  373.99  5355.8  372.73  5382.8  371.18  5383.0  370.68  5386.5  370.68
  5386.8  371.18  5399.3  377.17  5406.1  382.02  5442.7  384.08  5531.2  385.93
#Mann=3,-1,0
  4575.9    0.05       0  5382.8    0.04       0  5386.8    0.05       0
Bank Sta=5382.8,5386.8
Exp/Cntr=0.3,0.1

Type RM Length L Ch R = 1,1159,323,323,323
BEGIN DESCRIPTION:
Walnut96 1.0
END DESCRIPTION:
XS GIS Cut Line= 3
      2766159.95      6761023.21      2765784.94      6760648.21
      2765243.25      6760481.53
#Sta/Elev= 30
  4720.0  394.53  4809.2  385.82  4936.5  371.55  4984.0  368.18  4984.2  367.68
  4988.0  368.18  5021.3  369.63  5070.8  369.37  5148.6  370.76  5198.1  369.49
  5219.3  370.48  5321.5  371.55  5343.4  371.39  5364.7  369.45  5385.2  370.26
  5392.2  371.30  5416.6  371.83  5521.3  371.95  5566.1  371.11  5605.0  372.27
  5625.9  373.81  5636.7  375.84  5664.2  378.72  5669.4  378.33  5696.9  380.46
  5702.1  380.01  5767.5  384.28  5772.7  383.52  5793.3  383.38  5817.1  381.91
#Mann=3,-1,0
  4720.0    0.05       0  4984.0    0.04       0  4988.0    0.05       0
Bank Sta=4984,4988
Exp/Cntr=0.3,0.1

Type RM Length L Ch R = 1,836,214,214,214
BEGIN DESCRIPTION:
Walnut96 0.5
END DESCRIPTION:
XS GIS Cut Line= 4
      2766201.61      6761002.39      2766211.20      6760672.16
      2766028.00      6760467.65      2765284.95      6760391.26
#Sta/Elev= 30
  4495.4  393.23  4646.9  378.63  4696.9  372.87  4726.9  371.13  4786.9  368.60
  4866.0  367.01  4957.9  367.86  4976.8  365.95  4977.1  365.45  4980.8  365.95
  5021.5  367.75  5070.8  366.99  5182.8  368.14  5202.9  367.42  5233.0  368.89
  5315.3  369.68  5373.8  367.95  5554.7  369.75  5594.9  371.03  5607.7  369.17
  5615.0  369.20  5625.1  370.99  5685.4  370.15  5715.6  370.94  5775.9  374.36
  5796.0  377.29  5801.0  376.12  5806.0  377.65  5826.1  379.76  5847.3  380.81
#Mann=3,-1,0
  4495.4    0.05       0  4976.8    0.04       0  4980.8    0.05       0
Bank Sta=4976.8,4980.8
Exp/Cntr=0.3,0.1

Type RM Length L Ch R = 1,622,0,0,0
BEGIN DESCRIPTION:
Walnut96 0.3
END DESCRIPTION:
XS GIS Cut Line= 4
      2766368.59      6760819.40      2766355.31      6760541.29
      2766172.10      6760336.78      2765870.58      6760315.05
#Sta/Elev= 30
  4536.1  377.20  4544.5  376.61  4574.5  372.68  4594.6  371.32  4634.6  370.49
  4644.6  370.01  4674.7  369.39  4704.7  368.24  4734.7  367.59  4784.8  366.72
  4835.5  366.29  5012.7  365.93  5026.9  366.29  5041.1  365.96  5069.5  366.20
  5076.2  365.58  5089.1  365.65  5093.1  365.38  5093.3  364.88  5096.8  364.88
  5097.1  365.38  5135.3  366.01  5195.5  366.04  5245.6  366.59  5265.7  366.41
  5275.7  366.55  5305.8  368.00  5335.8  368.26  5365.9  368.92  5391.4  368.87
#Mann=3,-1,0
  4536.1    0.05       0  5093.1    0.04       0  5097.1    0.05       0
Bank Sta=5093.1,5097.1
Exp/Cntr=0.3,0.1

Chan Stop Cuts=-1