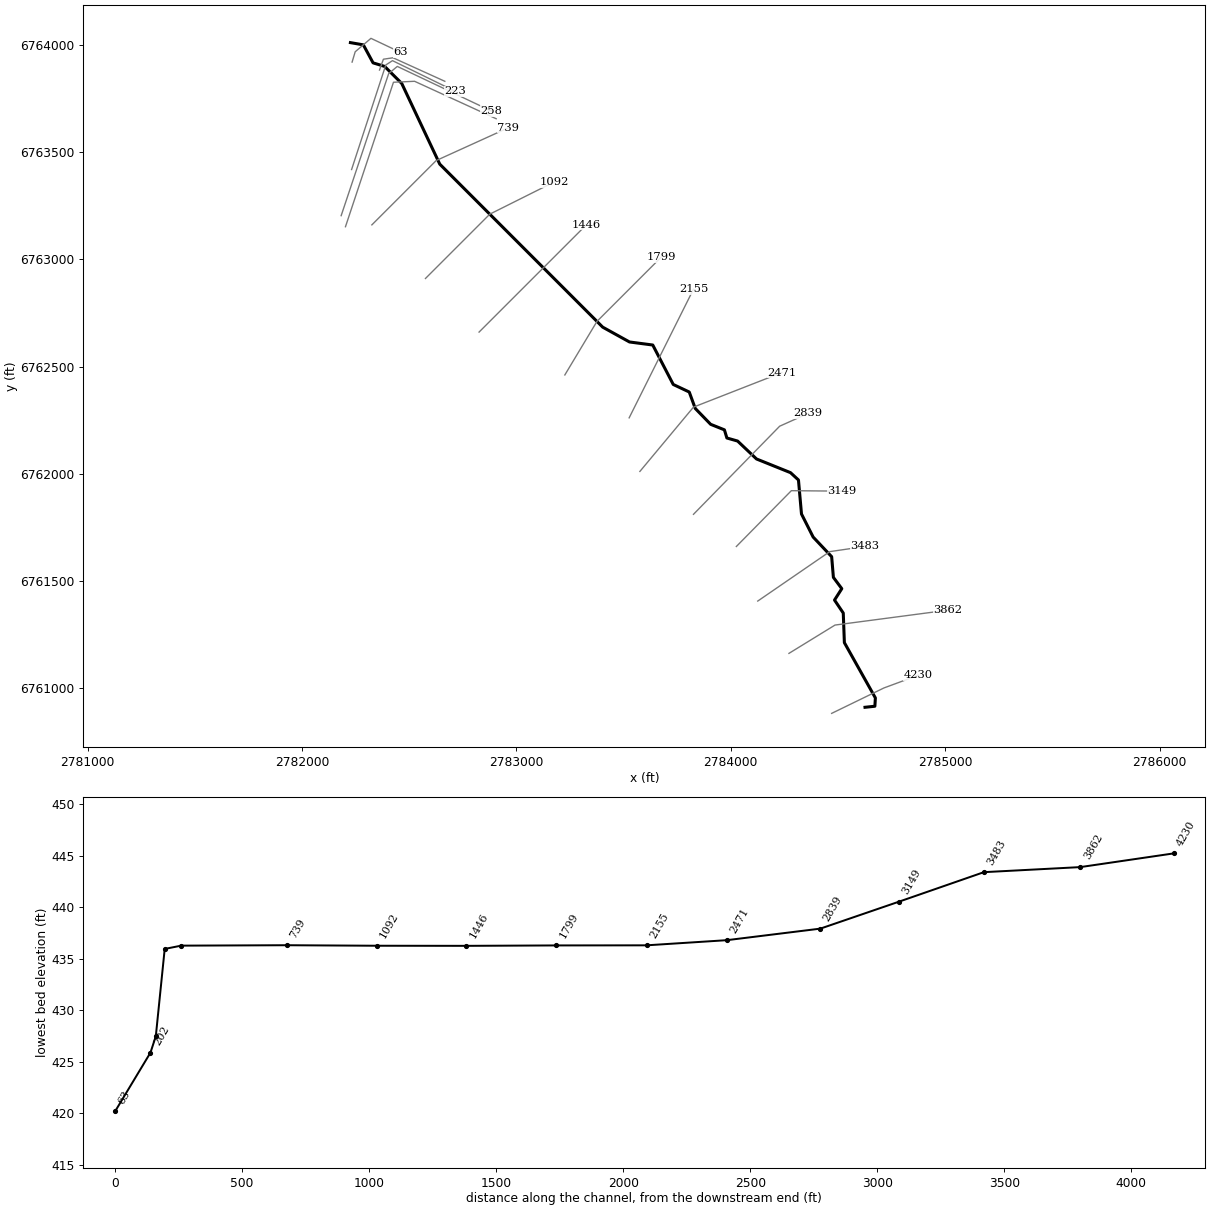
--- Walnut98.prj (project) ---

Proj Title=Walnut98 Base Level Engineering
Current Plan=p01
Default Exp/Contr=0.3,0.1
English Units
Geom File=g01
Flow File=f01
Plan File=p01
Y Axis Title=Elevation
X Axis Title(PF)=Main Channel Distance
X Axis Title(XS)=Station
BEGIN DESCRIPTION:
Walnut98
END DESCRIPTION:
DSS Export Rating Curves= 0
DSS Export Rating Curve Sorted= 0
DSS Export Volume Flow Curves= 0
DXF OffsetX= 0
DXF OffsetY= 0
DXF ScaleX= 1
DXF ScaleY= 10

--- Walnut98.p01 (plan) ---

Plan Title=Multiple Run
Program Version=4.10
Short Identifier=Multiple
Geom File=g01
Flow File=f01
Subcritical Flow
K Sum by GR= 0
Std Step Tol= 0.01
Critical Tol= 0.01
Num of Std Step Trials= 20
Max Error Tol= 0.3
Flow Tol Ratio= 0.001
Split Flow NTrial= 30
Split Flow Tol= 0.02
Split Flow Ratio= 0.02
Log Output Level= 0
Friction Slope Method= 1
Unsteady Friction Slope Method= 2
Unsteady Bridges Friction Slope Method= 1
Parabolic Critical Depth
Global Vel Dist= 1 , 1 , 1
Global Log Level= 0
CheckData=True
Encroach Param=-1 ,0,0, 0
BEGIN DESCRIPTION:
Multiple Run
END DESCRIPTION:
Computation Interval=1HOUR
Output Interval=1HOUR
Run HTab= 0
Run UNet= 0
Run PostProcess= 0
Run WQNet= 0
UNET Theta= 1
UNET Theta Warmup= 1
UNET ZTol= 0.02
UNET ZSATol= 0.05
UNET MxIter= 20
UNET MaxInSteps= 0
UNET DtIC= 0
UNET DtMin= 0
UNET MaxCRTS= 20
UNET WFStab= 2
UNET SFStab= 1
UNET WFX= 1
UNET SFX= 1
UNET DSS MLevel= 4
UNET DZMax Abort= 100
UNET Convert EG Bridges= 0
UNET Use Existing IB Tables=-1
UNET Froude Reduction=False
UNET Froude Limit= 1
UNET Froude Power= 10
UNET Time Slicing=0,0, 5
UNET Junction Losses=0
Instantaneous Interval=1HOUR
Write IC File= 0
Write IC File at Sim End=0
Echo Input=False
Echo Parameters=False
Echo Output=False
Write Detailed= 0
WQ AD Non Conservative
WQ ULTIMATE=-1
WQ Max Comp Step=1HOUR
WQ Output Interval=15MIN
WQ Output Selected Increments= 0
WQ Output face flow=0
WQ Output face velocity=0
WQ Output face area=0
WQ Output face dispersion=0
WQ Output cell volume=0
WQ Output cell surface area=0
WQ Output cell continuity=0
WQ Output cumulative cell continuity=0
WQ Output face conc=0
WQ Output face dconc_dx=0
WQ Output face courant=0
WQ Output face peclet=0
WQ Output face adv mass=0
WQ Output face disp mass=0
WQ Output cell mass=0
WQ Output cell source sink temp=0
WQ Output cell source sink nsm=0
WQ Output MaxMinRange=-1
WQ Daily Max Min Mean=-1
WQ Daily Range=0
WQ Daily Time=0
WQ Create Restart=0
WQ Fixed Restart=0
WQ System Summary=0
WQ Use Fixed Temperature=0
Sorting and Armoring Iterations= 10
XS Update Threshold= 0.02
Hydraulics Update Threshold= 0.02
Energy Slope Method= 1
Volume Change Method= 0
XS Weighting Method= 0
Number of US Weighted Cross Sections= 1
Number of DS Weighted Cross Sections= 1
Upstream XS Weight=0.25
Main XS Weight=0.5
Downstream XS Weight=0.25
Number of DS XS's Weighted with US Boundary= 1
Upstream Boundary Weight= 1
Weight of XSs Associated with US Boundary= 0
Number of US XS's Weighted with DS Boundary= 1
Downstream Boundary Weight= 0.5
Weight of XSs Associated with DS Boundary= 0.5
Sediment Output Level= 4
Mass or Volume Output= 0
Output Increment Type= 1
Profile and TS Output Increment= 10
XS Output Flag= 0
XS Output Increment= 10
Disregard all LS=0
Disregard all Conn=0
Disregard all Breaches=0
Disregard all Pumps=0

--- Walnut98.f01 (steady flow) ---

Flow Title=Multiple
Program Version=4.10
Number of Profiles= 7
Profile Names=10-year,25-year,50-year,1pct_min,100-year,1pct_plu,500-year
River Rch & RM=Walnut98,Reach-1         ,4230
     521     700     846     509    1015    2026    1464
River Rch & RM=Walnut98,Reach-1         ,63
     872    1194    1461     886    1769    3529    2599
Boundary for River Rch & Prof#=Walnut98,Reach-1         , 1
Up Type= 0
Dn Type= 3
Dn Slope=0.04
Boundary for River Rch & Prof#=Walnut98,Reach-1         , 2
Up Type= 0
Dn Type= 3
Dn Slope=0.04
Boundary for River Rch & Prof#=Walnut98,Reach-1         , 3
Up Type= 0
Dn Type= 3
Dn Slope=0.04
Boundary for River Rch & Prof#=Walnut98,Reach-1         , 4
Up Type= 0
Dn Type= 3
Dn Slope=0.04
Boundary for River Rch & Prof#=Walnut98,Reach-1         , 5
Up Type= 0
Dn Type= 3
Dn Slope=0.04
Boundary for River Rch & Prof#=Walnut98,Reach-1         , 6
Up Type= 0
Dn Type= 3
Dn Slope=0.04
Boundary for River Rch & Prof#=Walnut98,Reach-1         , 7
Up Type= 0
Dn Type= 3
Dn Slope=0.04
DSS Import GetInterval= 0
DSS Import GetPeak= 0
DSS Import FillOption= 0

--- Walnut98.g01 (geometry) ---

Geom Title=Existing Conditions

River Reach=Walnut98,Reach-1
Reach XY= 30
      2784626.00      6760911.00      2784672.03      6760915.90
      2784674.36      6760954.70      2784529.76      6761212.56
      2784524.61      6761350.56      2784483.79      6761411.10
      2784517.72      6761464.22      2784478.55      6761516.89
      2784470.47      6761613.42      2784384.16      6761704.95
      2784329.76      6761812.56      2784315.65      6761971.12
      2784278.58      6762005.29      2784119.95      6762069.16
      2784031.76      6762152.75      2783981.77      6762166.98
      2783970.23      6762205.02      2783906.03      6762230.82
      2783834.16      6762304.95      2783806.27      6762381.43
      2783731.62      6762416.62      2783636.11      6762600.62
      2783527.59      6762614.83      2783402.53      6762684.01
      2782642.64      6763444.32      2782465.24      6763820.70
      2782385.44      6763900.12      2782331.60      6763916.62
      2782286.22      6764000.60      2782226.00      6764011.00

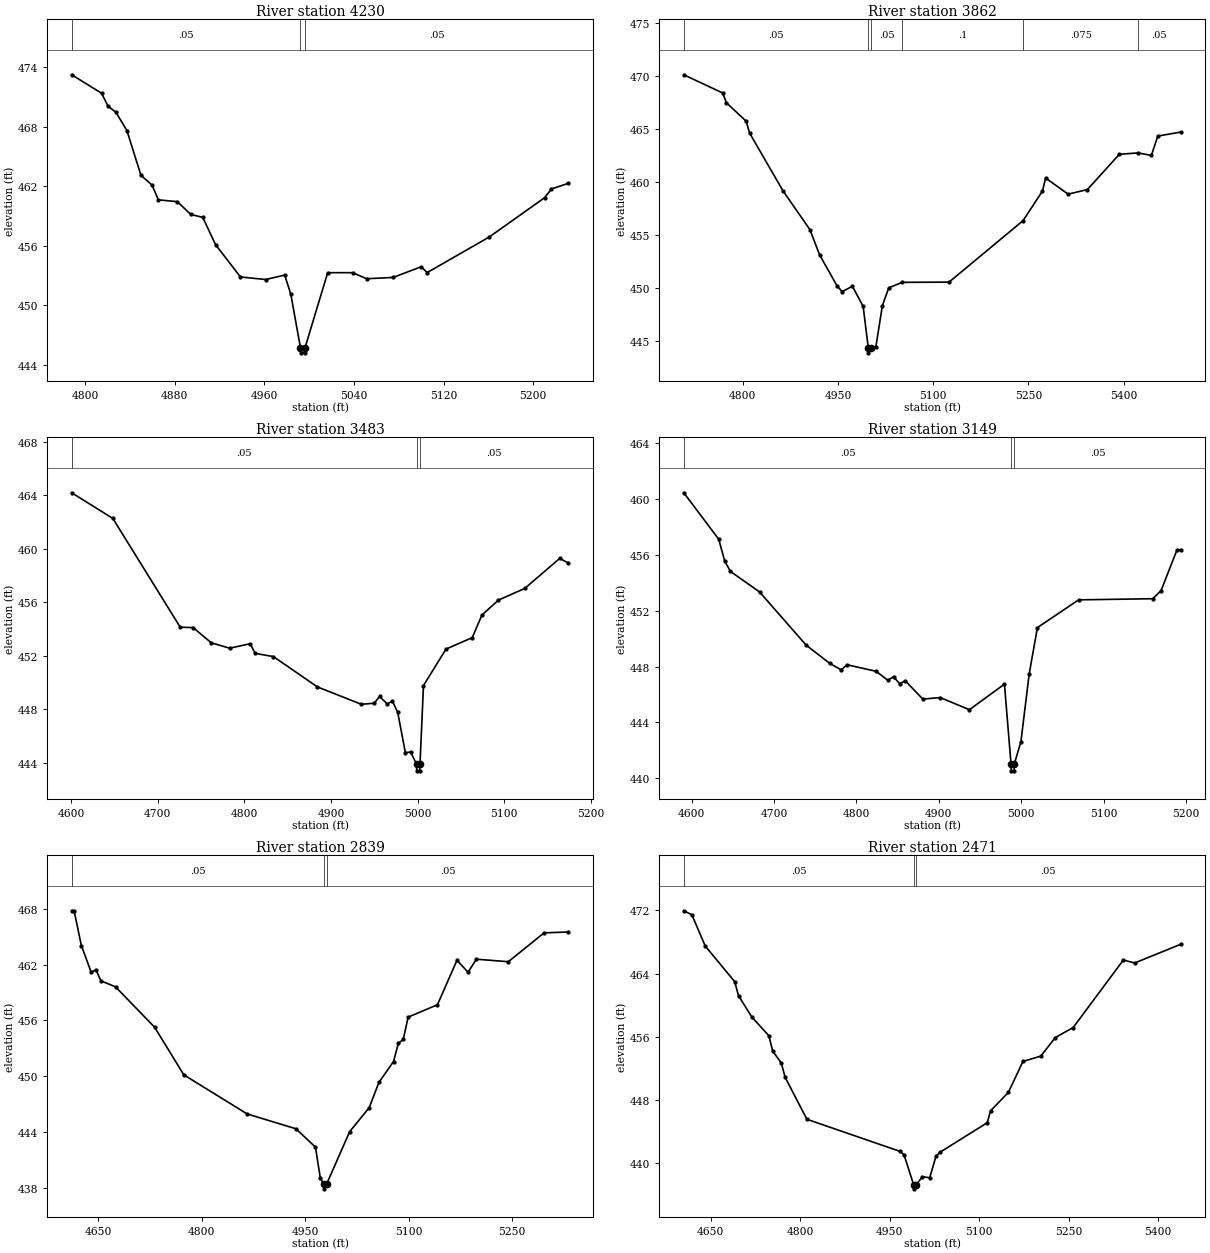
Type RM Length L Ch R = 1,4230,368,368,368
BEGIN DESCRIPTION:
Walnut98 12.0
END DESCRIPTION:
XS GIS Cut Line= 3
      2784470.45      6760882.61      2784714.45      6761001.26
      2784876.03      6761061.01
#Sta/Elev= 30
  4787.9  473.24  4814.6  471.38  4820.2  470.10  4827.4  469.45  4837.2  467.62
  4849.7  463.12  4859.7  462.11  4865.3  460.63  4882.3  460.45  4894.2  459.16
  4904.9  458.87  4916.4  456.11  4938.6  452.86  4961.1  452.60  4978.1  453.05
  4983.6  451.10  4992.2  445.71  4992.5  445.21  4996.0  445.21  4996.2  445.71
  5016.5  453.29  5038.7  453.29  5051.3  452.68  5074.9  452.81  5100.0  453.89
  5105.3  453.30  5160.8  456.89  5210.1  460.84  5216.3  461.73  5231.5  462.30
#Mann=3,-1,0
  4787.9    0.05       0  4992.2    0.03       0  4996.2    0.05       0
Bank Sta=4992.2,4996.2
Exp/Cntr=0.3,0.1

Type RM Length L Ch R = 1,3862,379,379,379
BEGIN DESCRIPTION:
Walnut98 11.0
END DESCRIPTION:
XS GIS Cut Line= 3
      2784271.25      6761162.43      2784486.13      6761294.49
      2785011.56      6761363.81
#Sta/Elev= 30
  4707.4  470.11  4768.7  468.39  4774.5  467.47  4805.4  465.74  4811.2  464.59
  4863.4  459.18  4905.9  455.51  4921.3  453.11  4948.5  450.22  4956.6  449.65
  4972.9  450.16  4989.8  448.26  4997.8  444.38  4998.1  443.88  5001.8  444.38
  5009.9  444.47  5020.0  448.32  5030.1  450.01  5051.1  450.53  5125.0  450.55
  5241.6  456.35  5272.1  459.14  5277.1  460.37  5312.5  458.85  5342.8  459.28
  5393.2  462.61  5422.7  462.74  5443.6  462.50  5453.7  464.33  5489.6  464.70
#Mann=6,-1,0
  4707.4    0.05       0  4997.8    0.03       0  5001.8    0.05       0
  5051.1     0.1       0  5241.6   0.075       0  5422.7    0.05       0
Bank Sta=4997.8,5001.8
Exp/Cntr=0.3,0.1

Type RM Length L Ch R = 1,3483,334,334,334
BEGIN DESCRIPTION:
Walnut98 10.0
END DESCRIPTION:
XS GIS Cut Line= 3
      2784125.73      6761406.42      2784461.50      6761636.98
      2784625.95      6761660.99
#Sta/Elev= 30
  4600.6  464.20  4648.1  462.28  4725.9  454.14  4740.8  454.11  4761.8  452.97
  4782.9  452.57  4806.5  452.90  4812.5  452.18  4833.5  451.94  4884.3  449.67
  4935.0  448.37  4949.9  448.45  4956.0  448.96  4964.8  448.40  4970.9  448.60
  4977.0  447.76  4985.8  444.75  4991.8  444.80  4998.7  443.89  4998.9  443.39
  5002.4  443.39  5002.7  443.89  5006.7  449.77  5032.7  452.50  5063.0  453.36
  5074.2  455.05  5093.3  456.17  5123.6  457.04  5164.0  459.29  5174.1  458.94
#Mann=3,-1,0
  4600.6    0.05       0  4998.7    0.05       0  5002.7    0.05       0
Bank Sta=4998.7,5002.7
Exp/Cntr=0.3,0.1

Type RM Length L Ch R = 1,3149,310,310,310
BEGIN DESCRIPTION:
Walnut98 9.0
END DESCRIPTION:
XS GIS Cut Line= 3
      2784025.99      6761660.98      2784282.43      6761921.26
      2784519.73      6761919.02
#Sta/Elev= 30
  4590.6  460.45  4633.0  457.12  4640.1  455.58  4647.1  454.82  4682.6  453.34
  4739.1  449.53  4767.4  448.24  4781.6  447.76  4788.6  448.13  4824.0  447.66
  4838.1  447.02  4845.1  447.27  4852.3  446.78  4859.3  446.98  4880.6  445.67
  4901.7  445.78  4937.1  444.91  4979.6  446.74  4987.6  441.03  4987.8  440.53
  4991.3  440.53  4991.6  441.03  4999.6  442.62  5009.6  447.46  5019.6  450.79
  5069.6  452.78  5159.6  452.86  5169.6  453.44  5188.9  456.35  5193.3  456.35
#Mann=3,-1,0
  4590.6    0.05       0  4987.6    0.03       0  4991.6    0.05       0
Bank Sta=4987.6,4991.6
Exp/Cntr=0.3,0.1

Type RM Length L Ch R = 1,2839,368,368,368
BEGIN DESCRIPTION:
Walnut98 8.0
END DESCRIPTION:
XS GIS Cut Line= 3
      2783826.03      6761811.03      2784227.95      6762221.95
      2784360.75      6762281.65
#Sta/Elev= 30
  4611.4  467.77  4614.9  467.77  4625.4  464.04  4639.6  461.18  4646.7  461.42
  4653.7  460.25  4675.0  459.60  4731.6  455.27  4774.0  450.15  4865.9  445.95
  4936.6  444.36  4964.9  442.39  4972.0  439.04  4977.0  438.41  4977.3  437.91
  4981.0  438.41  5014.5  444.05  5042.8  446.62  5056.9  449.34  5078.1  451.58
  5085.2  453.55  5092.2  453.95  5099.3  456.35  5141.8  457.68  5170.1  462.46
  5186.2  461.17  5198.3  462.57  5244.6  462.30  5296.4  465.40  5331.8  465.49
#Mann=3,-1,0
  4611.4    0.05       0  4977.0    0.03       0  4981.0    0.05       0
Bank Sta=4977,4981
Exp/Cntr=0.3,0.1

Type RM Length L Ch R = 1,2471,316,316,316
BEGIN DESCRIPTION:
Walnut98 7.0
END DESCRIPTION:
XS GIS Cut Line= 3
      2783576.02      6762011.03      2783826.00      6762311.00
      2784237.68      6762471.93
#Sta/Elev= 30
  4605.2  471.93  4618.8  471.42  4641.0  467.49  4690.4  462.98  4696.9  461.20
  4719.1  458.51  4747.7  456.14  4754.2  454.19  4768.5  452.71  4775.0  450.89
  4811.5  445.58  4967.7  441.52  4974.2  441.11  4990.4  437.29  4990.7  436.79
  4994.4  437.29  5005.2  438.33  5017.2  438.19  5027.9  440.92  5035.1  441.44
  5113.8  445.15  5119.2  446.65  5149.1  448.97  5173.5  452.89  5203.4  453.56
  5227.8  455.91  5257.7  457.17  5341.8  465.71  5360.7  465.33  5437.7  467.69
#Mann=3,-1,0
  4605.2    0.05       0  4990.4    0.03       0  4994.4    0.05       0
Bank Sta=4990.4,4994.4
Exp/Cntr=0.3,0.1

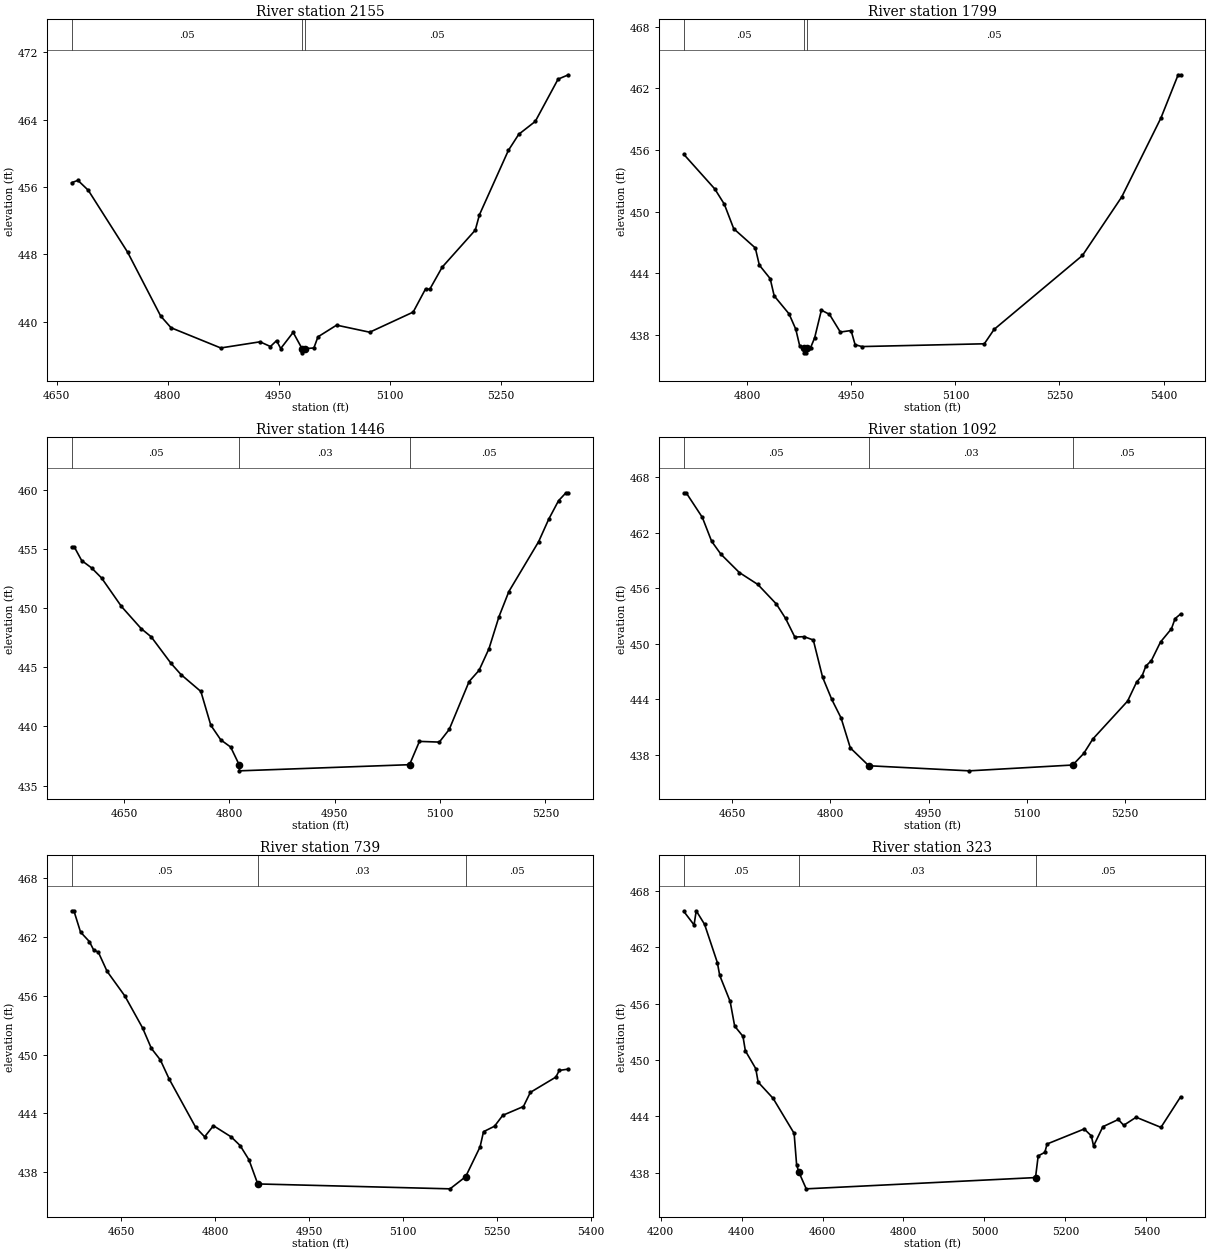
Type RM Length L Ch R = 1,2155,356,356,356
BEGIN DESCRIPTION:
Walnut98 6.0
END DESCRIPTION:
XS GIS Cut Line= 3
      2783525.99      6762260.97      2783676.00      6762561.00
      2783826.02      6762861.04
#Sta/Elev= 30
  4670.4  456.50  4678.8  456.78  4692.8  455.60  4745.9  448.25  4790.6  440.66
  4804.6  439.27  4871.7  436.87  4924.8  437.60  4938.8  437.04  4947.1  437.74
  4952.7  436.80  4969.5  438.72  4981.5  436.79  4981.7  436.29  4985.5  436.79
  4997.5  436.87  5003.0  438.19  5028.2  439.58  5072.9  438.74  5131.6  441.13
  5148.4  443.90  5154.0  443.84  5170.8  446.47  5215.5  450.87  5221.1  452.69
  5260.2  460.34  5274.2  462.25  5296.5  463.78  5327.3  468.80  5341.3  469.32
#Mann=3,-1,0
  4670.4    0.05       0  4981.5    0.03       0  4985.5    0.05       0
Bank Sta=4981.5,4985.5
Exp/Cntr=0.3,0.1

Type RM Length L Ch R = 1,1799,353,353,353
BEGIN DESCRIPTION:
Walnut98 5.0
END DESCRIPTION:
XS GIS Cut Line= 3
      2783226.00      6762461.01      2783376.00      6762711.00
      2783676.00      6763011.00
#Sta/Elev= 30
  4708.7  455.58  4753.4  452.21  4767.0  450.74  4780.6  448.35  4811.7  446.48
  4817.5  444.81  4833.1  443.50  4838.9  441.82  4860.3  440.07  4870.0  438.58
  4875.8  436.92  4881.6  436.78  4881.9  436.28  4885.4  436.28  4885.6  436.78
  4891.4  436.79  4897.2  437.74  4906.9  440.43  4918.6  440.02  4934.2  438.30
  4949.7  438.45  4955.5  437.07  4965.3  436.89  5141.7  437.16  5155.8  438.56
  5283.1  445.75  5339.7  451.44  5396.2  459.12  5421.0  463.32  5424.5  463.32
#Mann=3,-1,0
  4708.7    0.05       0  4881.6    0.04       0  4885.6    0.05       0
Bank Sta=4881.6,4885.6
Exp/Cntr=0.3,0.1

Type RM Length L Ch R = 1,1446,354,354,354
BEGIN DESCRIPTION:
Walnut98 4.0
END DESCRIPTION:
XS GIS Cut Line= 3
      2782825.97      6762660.97      2783126.00      6762961.00
      2783325.97      6763160.97
#Sta/Elev= 30
  4575.7  455.18  4579.3  455.18  4589.9  454.02  4604.0  453.40  4618.2  452.55
  4646.5  450.14  4674.7  448.26  4688.9  447.57  4717.2  445.32  4731.3  444.38
  4759.6  442.95  4773.7  440.10  4787.9  438.86  4802.0  438.25  4814.2  436.74
  4814.4  436.24  5056.6  436.76  5070.7  438.73  5099.0  438.67  5113.1  439.74
  5141.4  443.79  5155.6  444.74  5169.7  446.57  5183.9  449.27  5198.0  451.40
  5240.4  455.62  5254.6  457.50  5268.7  459.08  5279.3  459.75  5282.8  459.75
#Mann=3,-1,0
  4575.7    0.05       0  4814.2    0.03       0  5056.6    0.05       0
Bank Sta=4814.2,5056.6
Exp/Cntr=0.3,0.1

Type RM Length L Ch R = 1,1092,353,353,353
BEGIN DESCRIPTION:
Walnut98 3.0
END DESCRIPTION:
XS GIS Cut Line= 3
      2782575.97      6762910.97      2782876.00      6763211.00
      2783175.99      6763360.99
#Sta/Elev= 30
  4575.7  466.30  4579.3  466.30  4604.0  463.64  4618.2  461.06  4632.3  459.67
  4660.6  457.68  4688.9  456.39  4717.2  454.28  4731.3  452.72  4745.4  450.71
  4759.6  450.75  4773.7  450.39  4787.9  446.37  4802.0  443.96  4816.2  441.96
  4830.3  438.73  4858.6  436.80  5012.2  436.25  5170.5  436.88  5187.3  438.13
  5201.2  439.69  5254.4  443.79  5268.3  445.86  5276.7  446.54  5282.3  447.57
  5290.7  448.16  5304.7  450.17  5321.4  451.60  5327.0  452.70  5335.4  453.20
#Mann=3,-1,0
  4575.7    0.05       0  4858.6    0.03       0  5170.5    0.05       0
Bank Sta=4858.6,5170.5
Exp/Cntr=0.3,0.1

Type RM Length L Ch R = 1,739,416,416,416
BEGIN DESCRIPTION:
Walnut98 2.0
END DESCRIPTION:
XS GIS Cut Line= 3
      2782326.03      6763161.03      2782626.00      6763461.00
      2782961.39      6763613.38
#Sta/Elev= 30
  4571.5  464.67  4575.0  464.67  4585.6  462.50  4599.7  461.53  4606.8  460.64
  4613.9  460.46  4628.0  458.49  4656.3  455.98  4684.6  452.72  4698.7  450.62
  4712.9  449.46  4727.0  447.51  4769.4  442.57  4783.6  441.61  4797.7  442.74
  4826.0  441.60  4840.2  440.72  4854.3  439.27  4868.4  436.80  5175.2  436.30
  5200.1  437.54  5223.1  440.58  5228.6  442.13  5246.2  442.69  5259.3  443.80
  5292.3  444.70  5303.3  446.14  5344.0  447.70  5349.5  448.38  5364.1  448.52
#Mann=3,-1,0
  4571.5    0.05       0  4868.4    0.03       0  5200.1    0.05       0
Bank Sta=4868.4,5200.1
Exp/Cntr=0.3,0.1

Type RM Length L Ch R = 1,323,65,65,65
BEGIN DESCRIPTION:
Walnut98 1.0
END DESCRIPTION:
XS GIS Cut Line= 4
      2782202.89      6763152.39      2782426.74      6763826.19
      2782525.24      6763830.67      2782905.79      6763656.06
#Sta/Elev= 30
  4257.3  465.82  4282.6  464.38  4287.9  465.89  4308.5  464.45  4340.1  460.37
  4345.9  459.01  4371.7  456.23  4382.9  453.60  4403.4  452.51  4409.3  450.97
  4435.0  449.07  4440.9  447.63  4477.9  445.90  4529.8  442.17  4535.9  438.85
  4541.2  438.07  4559.7  436.26  5126.2  437.46  5132.8  439.77  5149.2  440.15
  5154.8  441.04  5246.6  442.64  5264.1  441.90  5269.6  440.83  5292.6  442.88
  5330.8  443.65  5344.1  443.03  5374.8  443.89  5436.1  442.81  5484.6  446.06
#Mann=3,-1,0
  4257.3    0.05       0  4541.2    0.03       0  5126.2    0.05       0
Bank Sta=4541.2,5126.2
Exp/Cntr=0.3,0.1

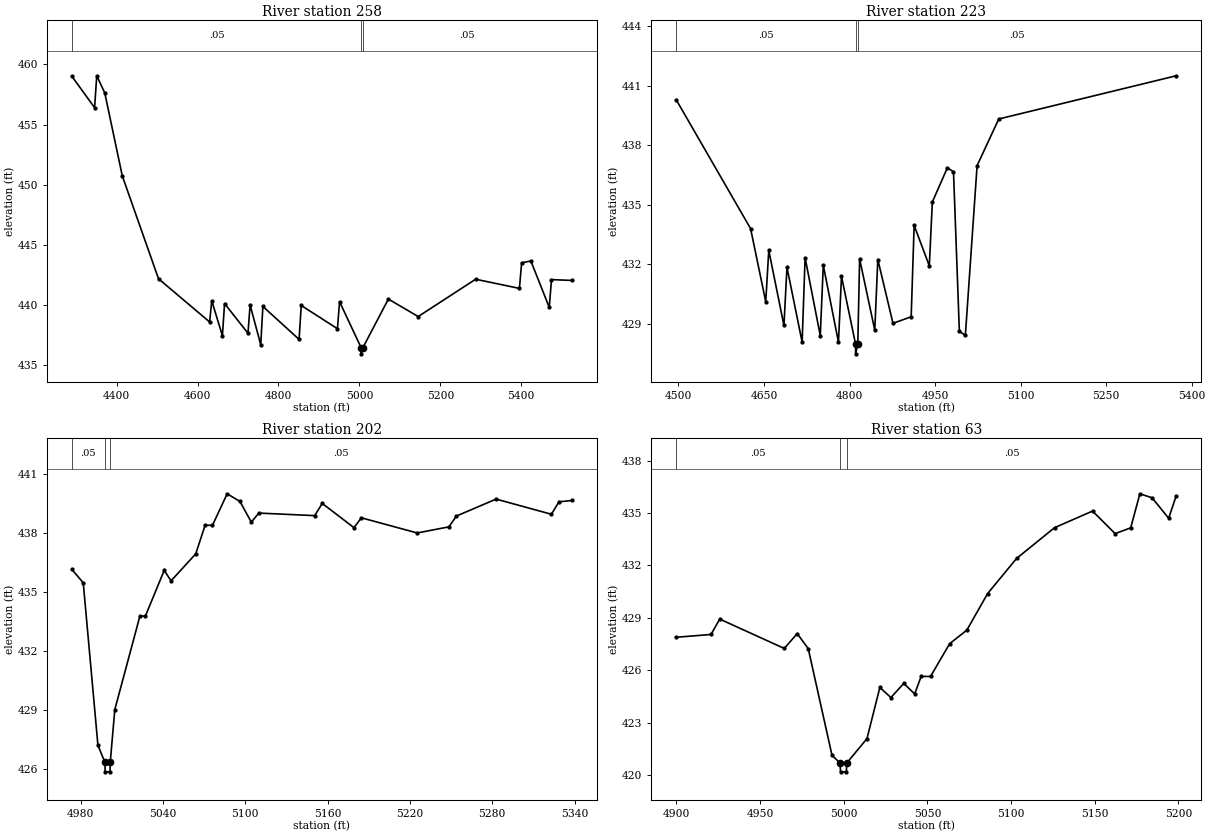
Type RM Length L Ch R = 1,258,35,35,35
BEGIN DESCRIPTION:
Walnut98 0.9
END DESCRIPTION:
XS GIS Cut Line= 4
      2782182.76      6763203.93      2782404.36      6763866.48
      2782444.65      6763900.06      2782882.21      6763692.44
#Sta/Elev= 30
  4289.5  459.01  4345.7  456.40  4351.0  459.05  4370.8  457.63  4414.1  450.73
  4503.6  442.18  4629.9  438.59  4635.2  440.35  4661.5  437.44  4666.8  440.12
  4724.7  437.65  4729.9  440.00  4756.2  436.70  4761.5  439.88  4851.0  437.14
  4856.3  439.96  4945.7  438.03  4951.0  440.27  5004.4  436.44  5004.6  435.94
  5008.4  436.44  5071.6  440.49  5145.3  439.04  5287.2  442.14  5395.3  441.38
  5400.9  443.50  5423.6  443.66  5469.1  439.80  5474.6  442.11  5524.9  442.04
#Mann=3,-1,0
  4289.5    0.05       0  5004.4    0.05       0  5008.4    0.05       0
Bank Sta=5004.4,5008.4
Exp/Cntr=0.3,0.1

Type RM Length L Ch R = 1,223,21,21,21
BEGIN DESCRIPTION:
Walnut98 0.8
END DESCRIPTION:
XS GIS Cut Line= 4
      2782231.40      6763419.11      2782390.93      6763906.78
      2782422.27      6763926.92      2782715.49      6763783.67
#Sta/Elev= 30
  4496.1  440.29  4626.5  433.79  4653.1  430.10  4658.4  432.69  4685.0  428.90
  4690.3  431.84  4716.9  428.06  4722.1  432.32  4748.7  428.39  4754.0  431.94
  4780.6  428.06  4785.9  431.38  4810.5  427.97  4810.7  427.47  4814.5  427.97
  4817.7  432.26  4844.3  428.66  4849.6  432.23  4876.2  429.01  4908.1  429.34
  4913.3  433.95  4939.9  431.91  4945.2  435.13  4971.6  436.86  4982.3  436.66
  4992.6  428.61  5003.1  428.40  5023.7  436.97  5061.7  439.32  5372.8  441.50
#Mann=3,-1,0
  4496.1    0.05       0  4810.5    0.03       0  4814.5    0.05       0
Bank Sta=4810.5,4814.5
Exp/Cntr=0.3,0.1

Type RM Length L Ch R = 1,202,139,139,139
BEGIN DESCRIPTION:
Walnut98 0.7
END DESCRIPTION:
XS GIS Cut Line= 4
      2782361.63      6763883.16      2782379.74      6763933.64
      2782424.51      6763940.35      2782666.28      6763830.66
#Sta/Elev= 30
  4973.6  436.16  4981.9  435.48  4992.6  427.23  4997.6  426.38  4997.9  425.88
  5001.4  425.88  5001.6  426.38  5004.9  429.04  5023.2  433.79  5027.2  433.79
  5040.9  436.11  5045.9  435.58  5063.9  436.95  5070.7  438.40  5076.1  438.40
  5086.8  440.00  5096.1  439.61  5104.4  438.56  5109.9  439.02  5150.6  438.89
  5156.1  439.51  5179.2  438.28  5184.6  438.78  5225.3  438.01  5248.4  438.32
  5253.9  438.87  5282.8  439.73  5323.1  438.96  5328.6  439.59  5338.0  439.66
#Mann=3,-1,0
  4973.6    0.05       0  4997.6    0.03       0  5001.6    0.05       0
Bank Sta=4997.6,5001.6
Exp/Cntr=0.3,0.1

Type RM Length L Ch R = 1,63,0,0,0
BEGIN DESCRIPTION:
Walnut98 0.5
END DESCRIPTION:
XS GIS Cut Line= 4
      2782233.79      6763920.17      2782248.25      6763968.37
      2782321.73      6764031.01      2782459.03      6763965.98
#Sta/Elev= 30
  4899.9  427.89  4920.7  428.05  4925.9  428.93  4964.5  427.25  4972.2  428.10
  4978.8  427.24  4993.0  421.14  4997.8  420.69  4998.1  420.19  5001.6  420.19
  5001.8  420.69  5013.9  422.09  5021.6  425.02  5028.2  424.44  5035.9  425.25
  5042.4  424.65  5046.3  425.65  5051.9  425.65  5063.3  427.52  5073.6  428.30
  5086.0  430.39  5103.3  432.40  5126.0  434.16  5148.7  435.11  5162.2  433.82
  5171.5  434.15  5177.0  436.10  5184.3  435.87  5194.2  434.70  5198.7  435.98
#Mann=3,-1,0
  4899.9    0.05       0  4997.8    0.03       0  5001.8    0.05       0
Bank Sta=4997.8,5001.8
Exp/Cntr=0.3,0.1

Chan Stop Cuts=-1