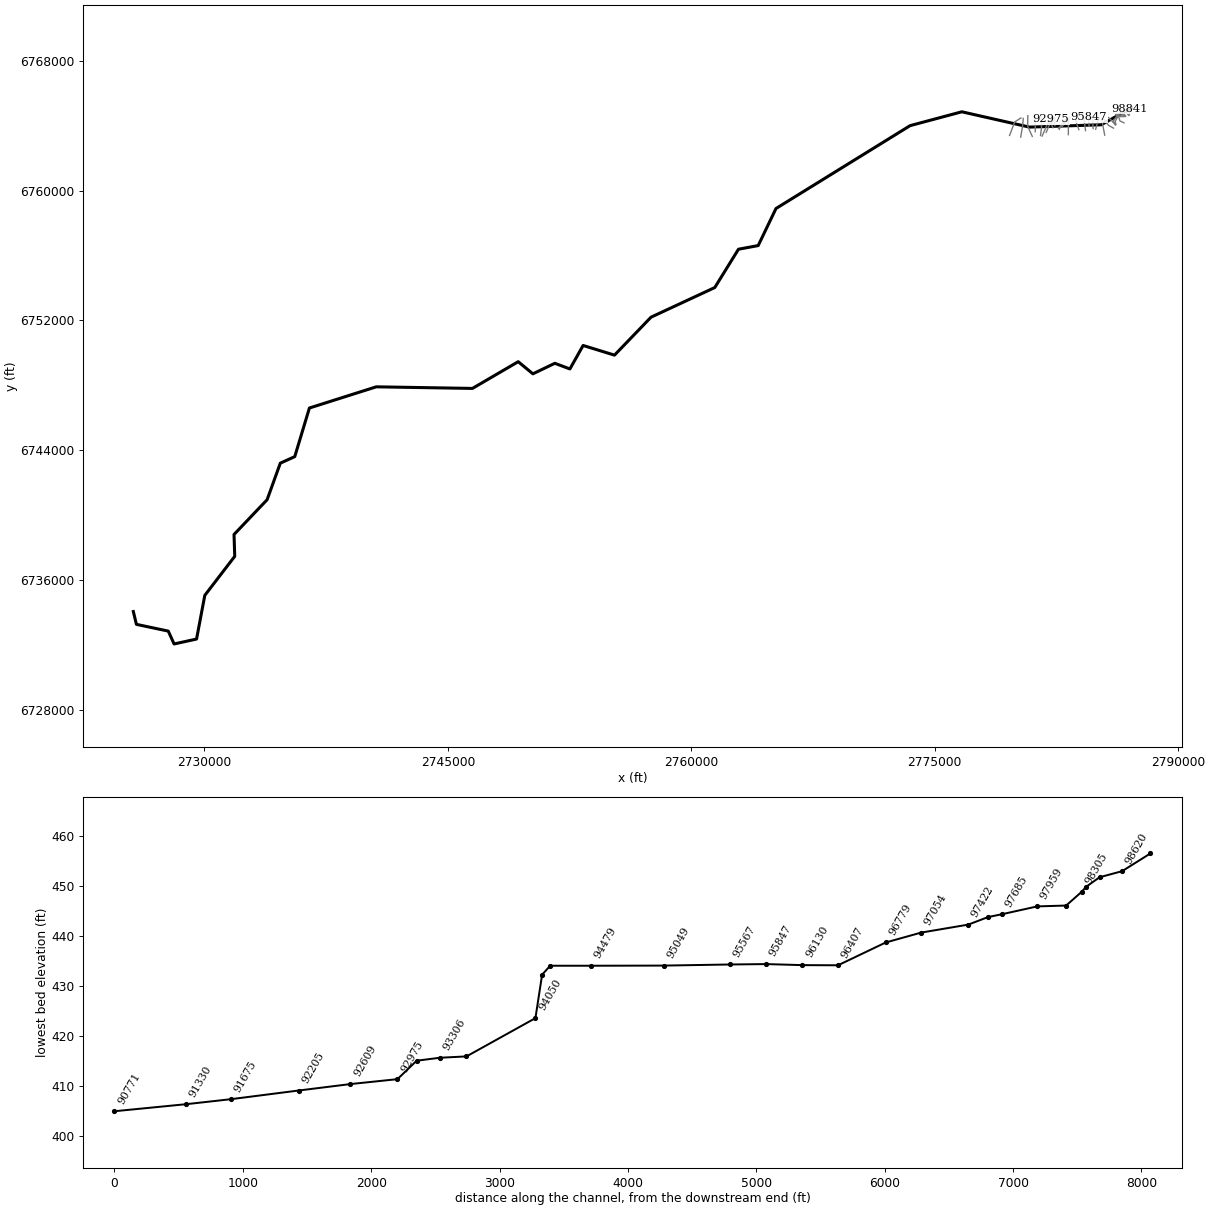
--- Walnut Creek.prj (project) ---

Proj Title=Walnut Creek Base Level Engineering
Current Plan=p01
Default Exp/Contr=0.3,0.1
English Units
Geom File=g01
Flow File=f01
Plan File=p01
Y Axis Title=Elevation
X Axis Title(PF)=Main Channel Distance
X Axis Title(XS)=Station
BEGIN DESCRIPTION:
Walnut Creek
END DESCRIPTION:
DSS Export Rating Curves= 0
DSS Export Rating Curve Sorted= 0
DSS Export Volume Flow Curves= 0
DXF OffsetX= 0
DXF OffsetY= 0
DXF ScaleX= 1
DXF ScaleY= 10

--- Walnut Creek.p01 (plan) ---

Plan Title=Multiple Run
Program Version=4.10
Short Identifier=Multiple
Geom File=g01
Flow File=f01
Subcritical Flow
K Sum by GR= 0
Std Step Tol= 0.01
Critical Tol= 0.01
Num of Std Step Trials= 20
Max Error Tol= 0.3
Flow Tol Ratio= 0.001
Split Flow NTrial= 30
Split Flow Tol= 0.02
Split Flow Ratio= 0.02
Log Output Level= 0
Friction Slope Method= 1
Unsteady Friction Slope Method= 2
Unsteady Bridges Friction Slope Method= 1
Parabolic Critical Depth
Global Vel Dist= 1 , 1 , 1
Global Log Level= 0
CheckData=True
Encroach Param=-1 ,0,0, 0
BEGIN DESCRIPTION:
Multiple Run
END DESCRIPTION:
Computation Interval=1HOUR
Output Interval=1HOUR
Run HTab= 0
Run UNet= 0
Run PostProcess= 0
Run WQNet= 0
UNET Theta= 1
UNET Theta Warmup= 1
UNET ZTol= 0.02
UNET ZSATol= 0.05
UNET MxIter= 20
UNET MaxInSteps= 0
UNET DtIC= 0
UNET DtMin= 0
UNET MaxCRTS= 20
UNET WFStab= 2
UNET SFStab= 1
UNET WFX= 1
UNET SFX= 1
UNET DSS MLevel= 4
UNET DZMax Abort= 100
UNET Convert EG Bridges= 0
UNET Use Existing IB Tables=-1
UNET Froude Reduction=False
UNET Froude Limit= 1
UNET Froude Power= 10
UNET Time Slicing=0,0, 5
UNET Junction Losses=0
Instantaneous Interval=1HOUR
Write IC File= 0
Write IC File at Sim End=0
Echo Input=False
Echo Parameters=False
Echo Output=False
Write Detailed= 0
WQ AD Non Conservative
WQ ULTIMATE=-1
WQ Max Comp Step=1HOUR
WQ Output Interval=15MIN
WQ Output Selected Increments= 0
WQ Output face flow=0
WQ Output face velocity=0
WQ Output face area=0
WQ Output face dispersion=0
WQ Output cell volume=0
WQ Output cell surface area=0
WQ Output cell continuity=0
WQ Output cumulative cell continuity=0
WQ Output face conc=0
WQ Output face dconc_dx=0
WQ Output face courant=0
WQ Output face peclet=0
WQ Output face adv mass=0
WQ Output face disp mass=0
WQ Output cell mass=0
WQ Output cell source sink temp=0
WQ Output cell source sink nsm=0
WQ Output MaxMinRange=-1
WQ Daily Max Min Mean=-1
WQ Daily Range=0
WQ Daily Time=0
WQ Create Restart=0
WQ Fixed Restart=0
WQ System Summary=0
WQ Use Fixed Temperature=0
Sorting and Armoring Iterations= 10
XS Update Threshold= 0.02
Hydraulics Update Threshold= 0.02
Energy Slope Method= 1
Volume Change Method= 0
XS Weighting Method= 0
Number of US Weighted Cross Sections= 1
Number of DS Weighted Cross Sections= 1
Upstream XS Weight=0.25
Main XS Weight=0.5
Downstream XS Weight=0.25
Number of DS XS's Weighted with US Boundary= 1
Upstream Boundary Weight= 1
Weight of XSs Associated with US Boundary= 0
Number of US XS's Weighted with DS Boundary= 1
Downstream Boundary Weight= 0.5
Weight of XSs Associated with DS Boundary= 0.5
Sediment Output Level= 4
Mass or Volume Output= 0
Output Increment Type= 1
Profile and TS Output Increment= 10
XS Output Flag= 0
XS Output Increment= 10
Disregard all LS=0
Disregard all Conn=0
Disregard all Breaches=0
Disregard all Pumps=0

--- Walnut Creek.f01 (steady flow) ---

Flow Title=Multiple
Number of Profiles=7
Profile Names=10-year,25-year,50-year,1pct_min,100-year,1pct_plu,500-year
River Rch & RM= Walnut Creek,Reach-1,98841
     356     466     553     327     653    1302     910
River Rch & RM= Walnut Creek,Reach-1,97685
     522     700     845     508    1013    2021    1456
River Rch & RM= Walnut Creek,Reach-1,97054
     686     934    1138     689    1375    2744    2013
River Rch & RM= Walnut Creek,Reach-1,93306
     872    1194    1461     886    1769    3529    2599
River Rch & RM= Walnut Creek,Reach-1,92609
     819    1100    1327     793    1581    3155    2253
River Rch & RM= Walnut Creek,Reach-1,91330
    1085    1478    1799    1084    2164    4317    3138
River Rch & RM= Walnut Creek,Reach-1,87651
    1534    2130    2628    1603    3199    6384    4757
River Rch & RM= Walnut Creek,Reach-1,83604
    1538    2120    2602    1578    3149    6283    4627
River Rch & RM= Walnut Creek,Reach-1,80899
    1717    2378    2928    1781    3554    7091    5254
River Rch & RM= Walnut Creek,Reach-1,79089
    1988    2779    3444    2109    4208    8396    6301
River Rch & RM= Walnut Creek,Reach-1,75611
    2351    3309    4120    2533    5055   10086    7633
River Rch & RM= Walnut Creek,Reach-1,70611
    2831    4037    5073    3148    6282   12534    9662
River Rch & RM= Walnut Creek,Reach-1,66315
    2907    4150    5218    3241    6467   12902    9959
River Rch & RM= Walnut Creek,Reach-1,65059
    2407    3337    4111    2499    4986    9948    7355
River Rch & RM= Walnut Creek,Reach-1,58047
    2998    4197    5205    3184    6354   12677    9492
River Rch & RM= Walnut Creek,Reach-1,51315
    3000    4204    5216    3192    6369   12707    9522
River Rch & RM= Walnut Creek,Reach-1,46297
    3457    4868    6060    3719    7420   14805   11160
River Rch & RM= Walnut Creek,Reach-1,35644
    3554    4995    6211    3807    7595   15155   11391
River Rch & RM= Walnut Creek,Reach-1,31121
    3472    4819    5940    3607    7198   14361   10596
River Rch & RM= Walnut Creek,Reach-1,14603
    3578    4972    6132    3725    7433   14831   10953
River Rch & RM= Walnut Creek,Reach-1,9408
     426     470     493     253     506    1009     533
Boundary for River Rch & Prof#=Walnut Creek,Reach-1,1
Up Type=0
Dn Type=3
Dn Slope=0.003
Boundary for River Rch & Prof#=Walnut Creek,Reach-1,2
Up Type=0
Dn Type=3
Dn Slope=0.003
Boundary for River Rch & Prof#=Walnut Creek,Reach-1,3
Up Type=0
Dn Type=3
Dn Slope=0.003
Boundary for River Rch & Prof#=Walnut Creek,Reach-1,4
Up Type=0
Dn Type=3
Dn Slope=0.003
Boundary for River Rch & Prof#=Walnut Creek,Reach-1,5
Up Type=0
Dn Type=3
Dn Slope=0.003
Boundary for River Rch & Prof#=Walnut Creek,Reach-1,6
Up Type=0
Dn Type=3
Dn Slope=0.003
Boundary for River Rch & Prof#=Walnut Creek,Reach-1,7
Up Type=0
Dn Type=3
Dn Slope=0.003

--- Walnut Creek.g01 (geometry) ---

Geom Title=Existing Conditions

River Reach=Walnut Creek,Reach-1
Reach XY= 30
      2787126.00      6765111.00      2785255.97      6764061.07
      2780825.92      6763918.30      2776665.81      6764861.45
      2773477.52      6764007.26      2765216.32      6758900.22
      2764120.74      6756616.47      2762905.68      6756391.32
      2761446.04      6754030.19      2757519.30      6752203.53
      2755267.55      6749863.59      2753335.25      6750459.81
      2752519.96      6749012.57      2751591.39      6749360.92
      2750239.92      6748711.41      2749336.48      6749460.07
      2746516.35      6747812.36      2740591.33      6747911.05
      2736473.61      6746605.32      2735570.20      6743608.70
      2734680.59      6743205.83      2733868.00      6740954.61
      2731829.12      6738809.37      2731872.45      6737462.47
      2730029.54      6735059.54      2729520.71      6732366.48
      2728137.12      6732062.84      2727778.45      6732855.54
      2725816.21      6733271.52      2725626.00      6734061.00

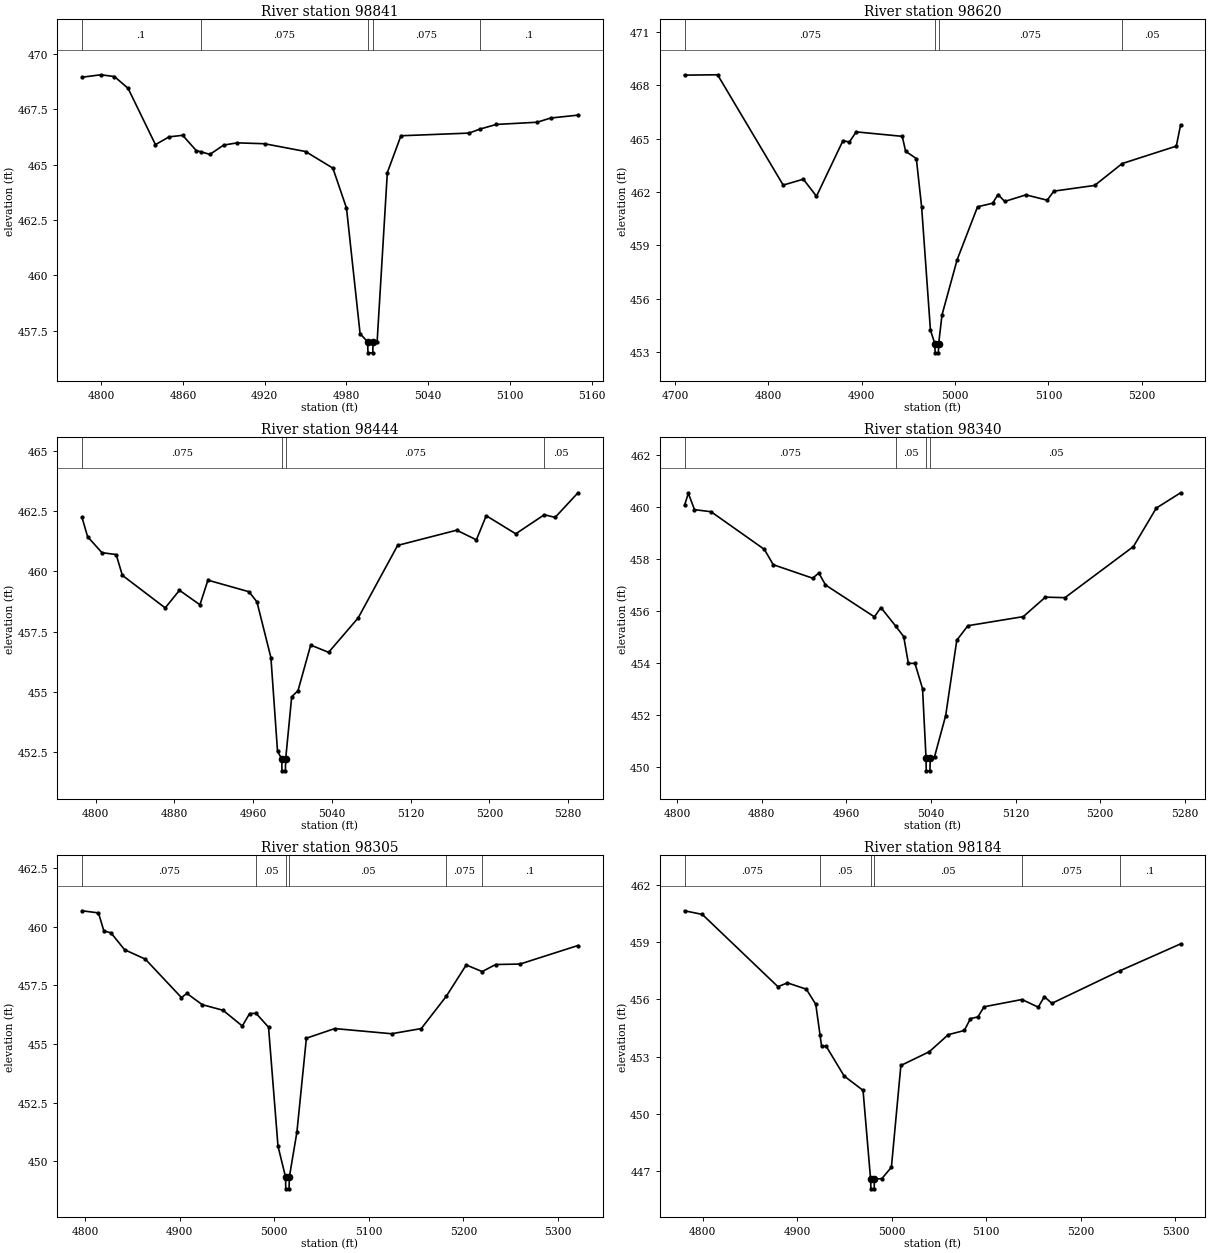
Type RM Length L Ch R = 1,98841,221,221,221
BEGIN DESCRIPTION:
Walnut Creek 154.0
END DESCRIPTION:
XS GIS Cut Line= 3
      2786990.32      6764697.16      2786976.00      6764911.00
      2786976.00      6765060.98
#Sta/Elev= 30
  4785.7  468.94  4799.6  469.05  4809.6  468.97  4819.6  468.44  4839.7  465.90
  4849.7  466.25  4859.7  466.32  4869.7  465.63  4872.9  465.58  4879.7  465.46
  4889.8  465.88  4899.8  465.98  4919.8  465.94  4949.9  465.59  4970.0  464.84
  4980.0  463.04  4990.0  457.37  4995.5  457.01  4995.8  456.51  4999.3  456.51
  4999.5  457.01  5002.5  457.01  5010.0  464.64  5020.0  466.30  5070.0  466.42
  5078.0  466.60  5090.0  466.81  5120.0  466.91  5130.0  467.10  5150.0  467.23
#Mann=5,-1,0
  4785.7     0.1       0  4872.9   0.075       0  4995.5    0.07       0
  4999.5   0.075       0  5078.0     0.1       0
Bank Sta=4995.5,4999.5
Exp/Cntr=0.3,0.1

Type RM Length L Ch R = 1,98620,176,176,176
BEGIN DESCRIPTION:
Walnut Creek 153.0
END DESCRIPTION:
XS GIS Cut Line= 3
      2786958.79      6764634.06      2786796.05      6764810.08
      2786656.98      6765066.69
#Sta/Elev= 30
  4710.1  468.57  4745.5  468.59  4815.8  462.39  4837.4  462.72  4851.5  461.76
  4879.9  464.89  4886.7  464.81  4894.1  465.38  4943.4  465.13  4947.0  464.29
  4958.5  463.88  4964.2  461.14  4973.6  454.24  4978.4  453.46  4978.6  452.96
  4982.1  452.96  4982.4  453.46  4986.0  455.09  5002.2  458.19  5024.1  461.17
  5040.3  461.37  5046.0  461.86  5053.2  461.47  5076.0  461.84  5098.7  461.54
  5105.9  462.05  5149.6  462.37  5179.1  463.60  5237.1  464.58  5241.7  465.78
#Mann=4,-1,0
  4710.1   0.075       0  4978.4    0.07       0  4982.4   0.075       0
  5179.1    0.05       0
Bank Sta=4978.4,4982.4
Exp/Cntr=0.3,0.1

Type RM Length L Ch R = 1,98444,104,104,104
BEGIN DESCRIPTION:
Walnut Creek 152.7
END DESCRIPTION:
XS GIS Cut Line= 3
      2786762.86      6764589.21      2786620.04      6764773.55
      2786613.40      6765044.18
#Sta/Elev= 30
  4786.0  462.25  4791.8  461.44  4806.3  460.78  4820.8  460.70  4827.1  459.84
  4870.6  458.49  4885.1  459.22  4905.9  458.62  4914.0  459.64  4955.7  459.16
  4963.8  458.74  4978.0  456.43  4984.7  452.55  4989.0  452.24  4989.2  451.74
  4992.7  451.74  4993.0  452.24  4999.1  454.81  5005.5  455.06  5018.4  456.95
  5036.6  456.65  5066.7  458.08  5106.7  461.08  5166.7  461.71  5186.7  461.31
  5196.7  462.31  5226.7  461.56  5255.7  462.35  5266.7  462.24  5289.9  463.26
#Mann=4,-1,0
  4786.0   0.075       0  4989.0    0.07       0  4993.0   0.075       0
  5255.7    0.05       0
Bank Sta=4989,4993
Exp/Cntr=0.3,0.1

Type RM Length L Ch R = 1,98340,35,35,35
BEGIN DESCRIPTION:
Walnut Creek 152.5
END DESCRIPTION:
XS GIS Cut Line= 3
      2786721.31      6764592.57      2786535.35      6764700.49
      2786458.96      6764942.94
#Sta/Elev= 30
  4806.9  460.07  4810.5  460.53  4816.3  459.90  4832.0  459.82  4882.4  458.37
  4890.8  457.78  4928.1  457.26  4933.9  457.46  4940.2  457.00  4986.5  455.77
  4992.6  456.13  5006.7  455.41  5014.2  455.01  5018.6  453.98  5024.8  453.98
  5032.0  453.01  5035.3  450.34  5035.5  449.84  5039.0  449.84  5039.3  450.34
  5043.4  450.39  5053.9  451.97  5064.4  454.87  5074.9  455.43  5127.3  455.78
  5148.2  456.53  5166.7  456.51  5231.5  458.48  5253.1  459.96  5276.1  460.55
#Mann=4,-1,0
  4806.9   0.075       0  5006.7    0.05       0  5035.3    0.07       0
  5039.3    0.05       0
Bank Sta=5035.3,5039.3
Exp/Cntr=0.3,0.1

Type RM Length L Ch R = 1,98305,121,121,121
BEGIN DESCRIPTION:
Walnut Creek 152.3
END DESCRIPTION:
XS GIS Cut Line= 4
      2786713.03      6764585.92      2786563.61      6764666.04
      2786399.19      6764662.30      2786219.60      6764724.91
#Sta/Elev= 30
  4796.8  460.68  4814.3  460.59  4820.0  459.82  4827.5  459.74  4841.9  459.02
  4863.8  458.62  4902.0  456.98  4907.7  457.16  4923.9  456.68  4945.9  456.44
  4966.3  455.77  4974.0  456.30  4980.8  456.31  4994.0  455.72  5004.0  450.65
  5012.0  449.33  5012.2  448.83  5015.7  448.83  5016.0  449.33  5024.0  451.25
  5034.0  455.25  5064.0  455.66  5124.0  455.44  5155.4  455.66  5181.9  457.04
  5202.9  458.37  5219.8  458.09  5234.0  458.39  5259.8  458.41  5321.0  459.20
#Mann=6,-1,0
  4796.8   0.075       0  4980.8    0.05       0  5012.0    0.05       0
  5016.0    0.05       0  5181.9   0.075       0  5219.8     0.1       0
Bank Sta=5012,5016
Exp/Cntr=0.3,0.1

Type RM Length L Ch R = 1,98184,225,225,225
BEGIN DESCRIPTION:
Walnut Creek 152.0
END DESCRIPTION:
XS GIS Cut Line= 3
      2786694.79      6764569.32      2786402.51      6764562.67
      2786223.20      6764710.44
#Sta/Elev= 30
  4780.8  460.63  4799.6  460.44  4879.6  456.66  4889.6  456.86  4909.6  456.53
  4919.6  455.74  4924.1  454.14  4925.7  453.57  4930.7  453.54  4949.6  451.99
  4969.6  451.24  4977.6  446.59  4977.9  446.09  4981.4  446.09  4981.6  446.59
  4989.6  446.63  4999.6  447.22  5009.6  452.54  5039.7  453.26  5059.7  454.15
  5076.7  454.37  5083.2  454.99  5091.1  455.08  5097.6  455.61  5137.7  455.99
  5154.9  455.59  5161.4  456.14  5169.3  455.79  5241.2  457.49  5305.5  458.90
#Mann=6,-1,0
  4780.8   0.075       0  4924.1    0.05       0  4977.6    0.05       0
  4981.6    0.05       0  5137.7   0.075       0  5241.2     0.1       0
Bank Sta=4977.6,4981.6
Exp/Cntr=0.3,0.1

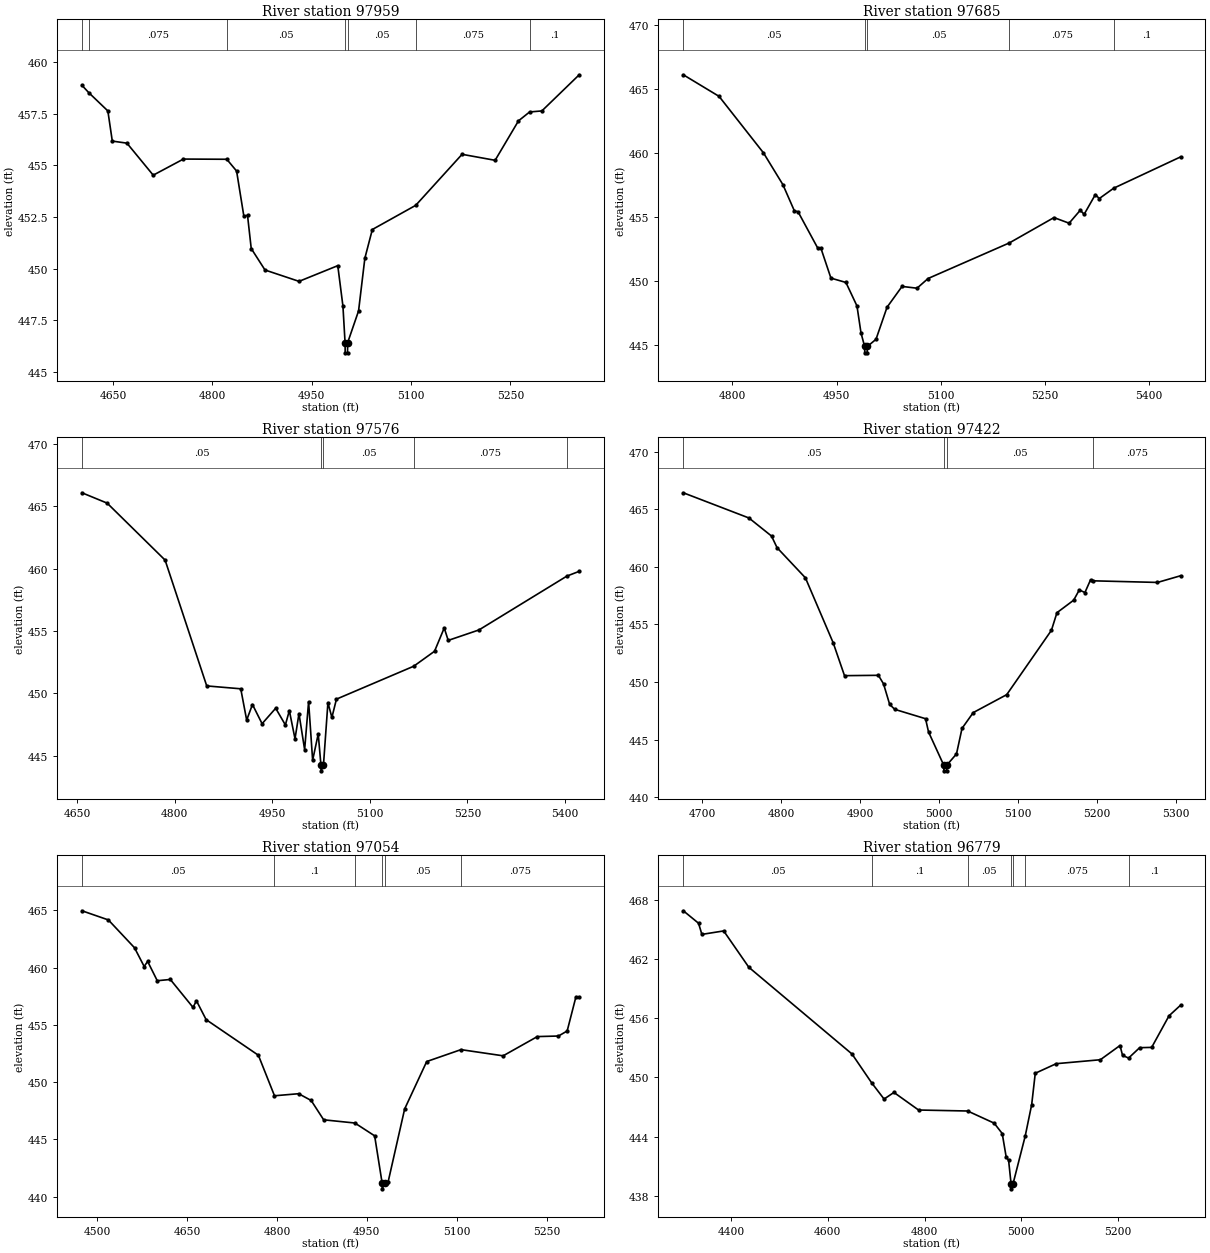
Type RM Length L Ch R = 1,97959,274,274,274
BEGIN DESCRIPTION:
Walnut Creek 151.0
END DESCRIPTION:
XS GIS Cut Line= 4
      2786657.44      6764179.86      2786404.49      6764298.51
      2786328.38      6764553.69      2786203.47      6764716.51
#Sta/Elev= 30
  4603.1  458.87  4613.2  458.52  4642.2  457.63  4648.9  456.17  4671.0  456.07
  4710.7  454.52  4756.3  455.30  4821.8  455.29  4836.6  454.72  4847.6  452.53
  4853.1  452.58  4858.7  450.97  4879.5  449.93  4930.9  449.38  4989.4  450.14
  4997.2  448.18  5000.4  446.42  5000.6  445.92  5004.1  445.92  5004.4  446.42
  5020.8  447.95  5030.3  450.50  5041.6  451.89  5107.1  453.06  5177.1  455.53
  5227.0  455.24  5262.3  457.15  5279.1  457.58  5297.6  457.63  5354.0  459.38
#Mann=7,-1,0
  4603.1    0.05       0  4613.2   0.075       0  4821.8    0.05       0
  5000.4    0.03       0  5004.4    0.05       0  5107.1   0.075       0
  5279.1     0.1       0
Bank Sta=5000.4,5004.4
Exp/Cntr=0.3,0.1

Type RM Length L Ch R = 1,97685,109,109,109
BEGIN DESCRIPTION:
Walnut Creek 150.0
END DESCRIPTION:
XS GIS Cut Line= 4
      2786154.38      6764080.66      2786113.34      6764274.70
      2786270.03      6764550.78      2786173.06      6764726.06
#Sta/Elev= 30
  4729.3  466.13  4780.8  464.44  4844.7  460.02  4872.7  457.53  4889.3  455.47
  4894.5  455.41  4923.2  452.53  4927.6  452.53  4941.9  450.21  4963.5  449.87
  4979.4  448.03  4985.2  445.92  4990.4  444.86  4990.6  444.36  4994.1  444.36
  4994.4  444.86  5006.8  445.42  5022.7  447.93  5044.3  449.56  5065.9  449.42
  5081.8  450.18  5199.0  452.97  5263.1  454.95  5284.9  454.51  5300.9  455.52
  5306.6  455.21  5322.7  456.75  5328.4  456.44  5349.1  457.25  5445.4  459.70
#Mann=5,-1,0
  4729.3    0.05       0  4990.4    0.05       0  4994.4    0.05       0
  5199.0   0.075       0  5349.1     0.1       0
Bank Sta=4990.4,4994.4
Exp/Cntr=0.3,0.1

Type RM Length L Ch R = 1,97576,154,154,154
BEGIN DESCRIPTION:
Walnut Creek 149.8
END DESCRIPTION:
XS GIS Cut Line= 4
      2786130.12      6764071.38      2785997.68      6764289.62
      2786201.01      6764580.62      2786145.06      6764724.23
#Sta/Elev= 30
  4657.4  466.09  4696.1  465.26  4785.2  460.69  4849.2  450.60  4901.5  450.37
  4910.6  447.86  4919.5  449.11  4934.3  447.57  4955.2  448.81  4970.1  447.47
  4976.2  448.62  4984.9  446.36  4991.0  448.38  4999.7  445.49  5005.8  449.34
  5012.0  444.64  5020.6  446.75  5024.7  444.29  5025.0  443.79  5028.7  444.29
  5035.5  449.26  5041.6  448.07  5048.6  449.54  5167.4  452.18  5199.4  453.38
  5214.3  455.25  5220.4  454.25  5267.7  455.09  5402.9  459.41  5421.8  459.79
#Mann=5,-1,0
  4657.4    0.05       0  5024.7    0.05       0  5028.7    0.05       0
  5167.4   0.075       0  5402.9     0.1       0
Bank Sta=5024.7,5028.7
Exp/Cntr=0.3,0.1

Type RM Length L Ch R = 1,97422,368,368,368
BEGIN DESCRIPTION:
Walnut Creek 149.0
END DESCRIPTION:
XS GIS Cut Line= 3
      2786122.46      6764050.02      2785925.46      6764285.08
      2785697.13      6764513.40
#Sta/Elev= 30
  4676.1  466.44  4759.2  464.25  4787.8  462.68  4794.8  461.67  4830.7  459.05
  4865.9  453.40  4880.2  450.55  4923.1  450.58  4929.6  449.84  4937.4  448.05
  4943.9  447.62  4982.8  446.81  4986.6  445.66  5005.8  442.78  5006.1  442.28
  5009.6  442.28  5009.8  442.78  5022.0  443.75  5029.0  445.97  5043.2  447.34
  5085.6  448.90  5142.2  454.49  5149.2  456.02  5170.4  457.11  5177.5  458.00
  5184.6  457.77  5191.7  458.87  5195.1  458.79  5276.5  458.65  5305.7  459.23
#Mann=4,-1,0
  4676.1    0.05       0  5005.8    0.05       0  5009.8    0.05       0
  5195.1   0.075       0
Bank Sta=5005.8,5009.8
Exp/Cntr=0.3,0.1

Type RM Length L Ch R = 1,97054,275,275,275
BEGIN DESCRIPTION:
Walnut Creek 148.0
END DESCRIPTION:
XS GIS Cut Line= 3
      2786010.52      6763855.29      2785699.37      6764025.41
      2785408.39      6764401.45
#Sta/Elev= 30
  4474.4  464.97  4518.5  464.17  4562.1  461.74  4578.3  460.10  4584.0  460.55
  4600.1  458.86  4621.9  458.97  4659.8  456.53  4665.5  457.11  4681.7  455.46
  4768.9  452.35  4795.8  448.81  4836.1  448.99  4857.0  448.40  4877.9  446.71
  4930.0  446.43  4963.0  445.31  4975.5  441.18  4975.7  440.68  4979.5  441.18
  4985.6  441.31  5013.1  447.66  5049.9  451.80  5107.1  452.84  5177.5  452.30
  5234.6  453.98  5269.9  454.03  5284.4  454.47  5298.9  457.43  5304.5  457.43
#Mann=6,-1,0
  4474.4    0.05       0  4795.8     0.1       0  4930.0    0.05       0
  4975.5    0.05       0  4979.5    0.05       0  5107.1   0.075       0
Bank Sta=4975.5,4979.5
Exp/Cntr=0.3,0.1

Type RM Length L Ch R = 1,96779,372,372,372
BEGIN DESCRIPTION:
Walnut Creek 147.0
END DESCRIPTION:
XS GIS Cut Line= 3
      2785466.57      6763423.29      2785345.69      6764054.51
      2785280.88      6764434.44
#Sta/Elev= 30
  4301.3  466.86  4332.8  465.60  4339.7  464.47  4384.8  464.82  4436.8  461.14
  4650.1  452.36  4690.6  449.45  4716.4  447.80  4736.8  448.47  4787.7  446.69
  4889.2  446.59  4944.0  445.36  4960.7  444.31  4968.8  441.95  4973.9  441.59
  4979.0  439.21  4979.3  438.71  4983.0  439.21  5008.2  444.05  5021.6  447.24
  5029.0  450.41  5072.3  451.38  5163.6  451.78  5204.2  453.22  5209.5  452.22
  5222.0  451.95  5244.8  453.00  5269.7  453.03  5305.6  456.23  5329.4  457.30
#Mann=7,-1,0
  4301.3    0.05       0  4690.6     0.1       0  4889.2    0.05       0
  4979.0    0.05       0  4983.0    0.05       0  5008.2   0.075       0
  5222.0     0.1       0
Bank Sta=4979,4983
Exp/Cntr=0.3,0.1

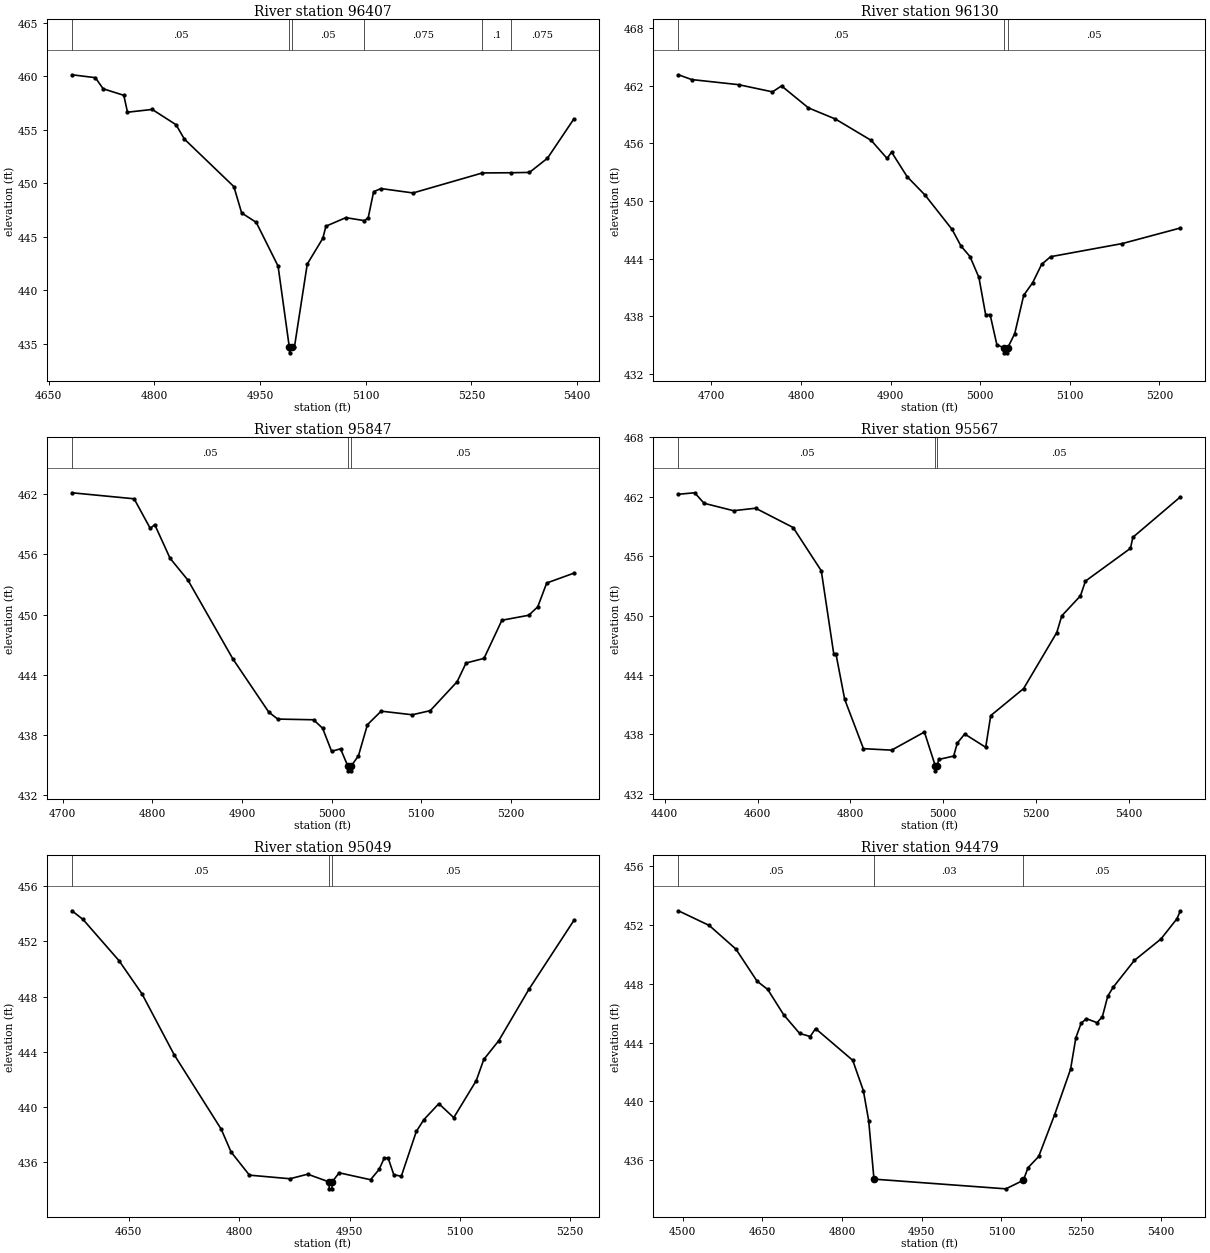
Type RM Length L Ch R = 1,96407,277,277,277
BEGIN DESCRIPTION:
Walnut Creek 146.0
END DESCRIPTION:
XS GIS Cut Line= 3
      2784911.43      6763788.11      2785003.21      6764137.34
      2785112.90      6764470.88
#Sta/Elev= 30
  4683.1  460.15  4716.3  459.88  4727.4  458.84  4756.7  458.23  4761.9  456.65
  4797.0  456.91  4830.8  455.48  4842.6  454.14  4912.9  449.69  4923.9  447.23
  4944.6  446.35  4975.6  442.26  4991.6  434.65  4991.9  434.15  4995.6  434.65
  4998.8  434.69  5017.0  442.45  5039.1  444.86  5043.5  445.99  5071.7  446.79
  5098.2  446.51  5103.5  446.79  5111.2  449.22  5121.7  449.51  5167.1  449.10
  5265.5  450.97  5306.0  450.99  5332.3  451.02  5357.9  452.35  5395.3  456.02
#Mann=6,-1,0
  4683.1    0.05       0  4991.6    0.05       0  4995.6    0.05       0
  5098.2   0.075       0  5265.5     0.1       0  5306.0   0.075       0
Bank Sta=4991.6,4995.6
Exp/Cntr=0.3,0.1

Type RM Length L Ch R = 1,96130,283,283,283
BEGIN DESCRIPTION:
Walnut Creek 145.3
END DESCRIPTION:
XS GIS Cut Line= 3
      2784754.74      6763826.14      2784734.60      6764170.91
      2784734.60      6764385.76
#Sta/Elev= 30
  4663.1  463.16  4678.0  462.66  4730.2  462.13  4768.1  461.38  4778.2  462.00
  4808.2  459.71  4838.3  458.55  4878.3  456.32  4896.0  454.44  4901.0  455.10
  4918.4  452.54  4938.4  450.62  4968.5  447.05  4978.5  445.31  4988.5  444.22
  4998.5  442.04  5006.0  438.16  5011.0  438.16  5018.5  435.04  5026.5  434.68
  5026.8  434.18  5030.3  434.18  5030.5  434.68  5038.5  436.19  5048.5  440.18
  5058.5  441.49  5068.5  443.40  5078.5  444.20  5158.5  445.57  5223.3  447.19
#Mann=3,-1,0
  4663.1    0.05       0  5026.5    0.03       0  5030.5    0.05       0
Bank Sta=5026.5,5030.5
Exp/Cntr=0.3,0.1

Type RM Length L Ch R = 1,95847,280,280,280
BEGIN DESCRIPTION:
Walnut Creek 145.0
END DESCRIPTION:
XS GIS Cut Line= 3
      2784506.27      6763971.72      2784486.13      6764316.41
      2784486.13      6764531.34
#Sta/Elev= 30
  4710.2  462.16  4779.6  461.56  4797.6  458.60  4802.6  458.98  4819.7  455.62
  4839.7  453.43  4889.8  445.57  4929.9  440.25  4939.9  439.56  4979.9  439.49
  4990.0  438.64  5000.0  436.34  5010.0  436.59  5018.0  434.89  5018.3  434.39
  5021.8  434.39  5022.1  434.89  5030.0  435.90  5040.0  439.00  5055.3  440.35
  5090.1  439.99  5110.1  440.40  5140.1  443.29  5150.1  445.16  5170.1  445.62
  5190.1  449.43  5220.1  449.93  5230.1  450.77  5240.1  453.15  5270.4  454.13
#Mann=3,-1,0
  4710.2    0.05       0  5018.0    0.03       0  5022.1    0.05       0
Bank Sta=5018,5022.1
Exp/Cntr=0.3,0.1

Type RM Length L Ch R = 1,95567,518,518,518
BEGIN DESCRIPTION:
Walnut Creek 144.0
END DESCRIPTION:
XS GIS Cut Line= 3
      2784286.91      6763696.32      2784206.32      6764280.60
      2784110.07      6764761.86
#Sta/Elev= 30
  4429.6  462.25  4464.6  462.40  4484.8  461.34  4548.2  460.59  4595.8  460.84
  4676.6  458.89  4737.2  454.52  4764.0  446.14  4769.0  446.07  4787.6  441.53
  4828.0  436.55  4888.6  436.40  4959.2  438.23  4982.7  434.81  4983.0  434.31
  4986.9  434.81  4989.9  435.46  5022.2  435.80  5030.0  437.11  5045.9  438.03
  5091.2  436.69  5102.0  439.89  5172.8  442.62  5244.2  448.28  5255.0  449.97
  5295.2  451.99  5306.0  453.48  5402.9  456.79  5408.0  457.90  5510.2  461.98
#Mann=3,-1,0
  4429.6    0.05       0  4982.7    0.03       0  4986.9    0.05       0
Bank Sta=4982.7,4986.9
Exp/Cntr=0.3,0.1

Type RM Length L Ch R = 1,95049,570,570,570
BEGIN DESCRIPTION:
Walnut Creek 143.0
END DESCRIPTION:
XS GIS Cut Line= 3
      2783875.99      6763761.03      2783726.00      6764161.00
      2783676.00      6764410.99
#Sta/Elev= 30
  4572.8  454.20  4587.9  453.57  4636.8  450.59  4668.0  448.19  4711.6  443.80
  4775.7  438.40  4789.0  436.76  4814.0  435.08  4869.1  434.82  4893.2  435.15
  4922.2  434.59  4922.5  434.09  4926.1  434.09  4926.4  434.59  4935.9  435.25
  4978.6  434.75  4990.2  435.49  4997.3  436.32  5002.5  436.32  5010.2  435.11
  5020.4  435.00  5040.8  438.24  5051.0  439.09  5071.4  440.25  5091.7  439.24
  5122.3  441.92  5132.5  443.45  5152.9  444.81  5193.7  448.51  5254.9  453.50
#Mann=3,-1,0
  4572.8    0.05       0  4922.2    0.03       0  4926.4    0.05       0
Bank Sta=4922.2,4926.4
Exp/Cntr=0.3,0.1

Type RM Length L Ch R = 1,94479,314,314,314
BEGIN DESCRIPTION:
Walnut Creek 142.0
END DESCRIPTION:
XS GIS Cut Line= 3
      2783226.86      6763452.91      2783226.86      6764098.13
      2783233.52      6764397.54
#Sta/Elev= 30
  4492.0  452.97  4550.1  451.97  4600.1  450.37  4640.1  448.18  4660.1  447.62
  4690.1  445.90  4720.1  444.63  4740.1  444.42  4750.1  444.96  4820.1  442.80
  4840.1  440.74  4850.1  438.70  4860.1  434.72  5108.3  434.06  5141.2  434.64
  5150.1  435.50  5170.1  436.26  5200.1  439.10  5230.1  442.19  5240.1  444.34
  5250.1  445.33  5260.1  445.63  5280.1  445.36  5290.1  445.78  5300.1  447.16
  5310.1  447.76  5350.1  449.59  5400.2  451.05  5430.2  452.42  5436.7  452.96
#Mann=3,-1,0
  4492.0    0.05       0  4860.1    0.03       0  5141.2    0.05       0
Bank Sta=4860.1,5141.2
Exp/Cntr=0.3,0.1

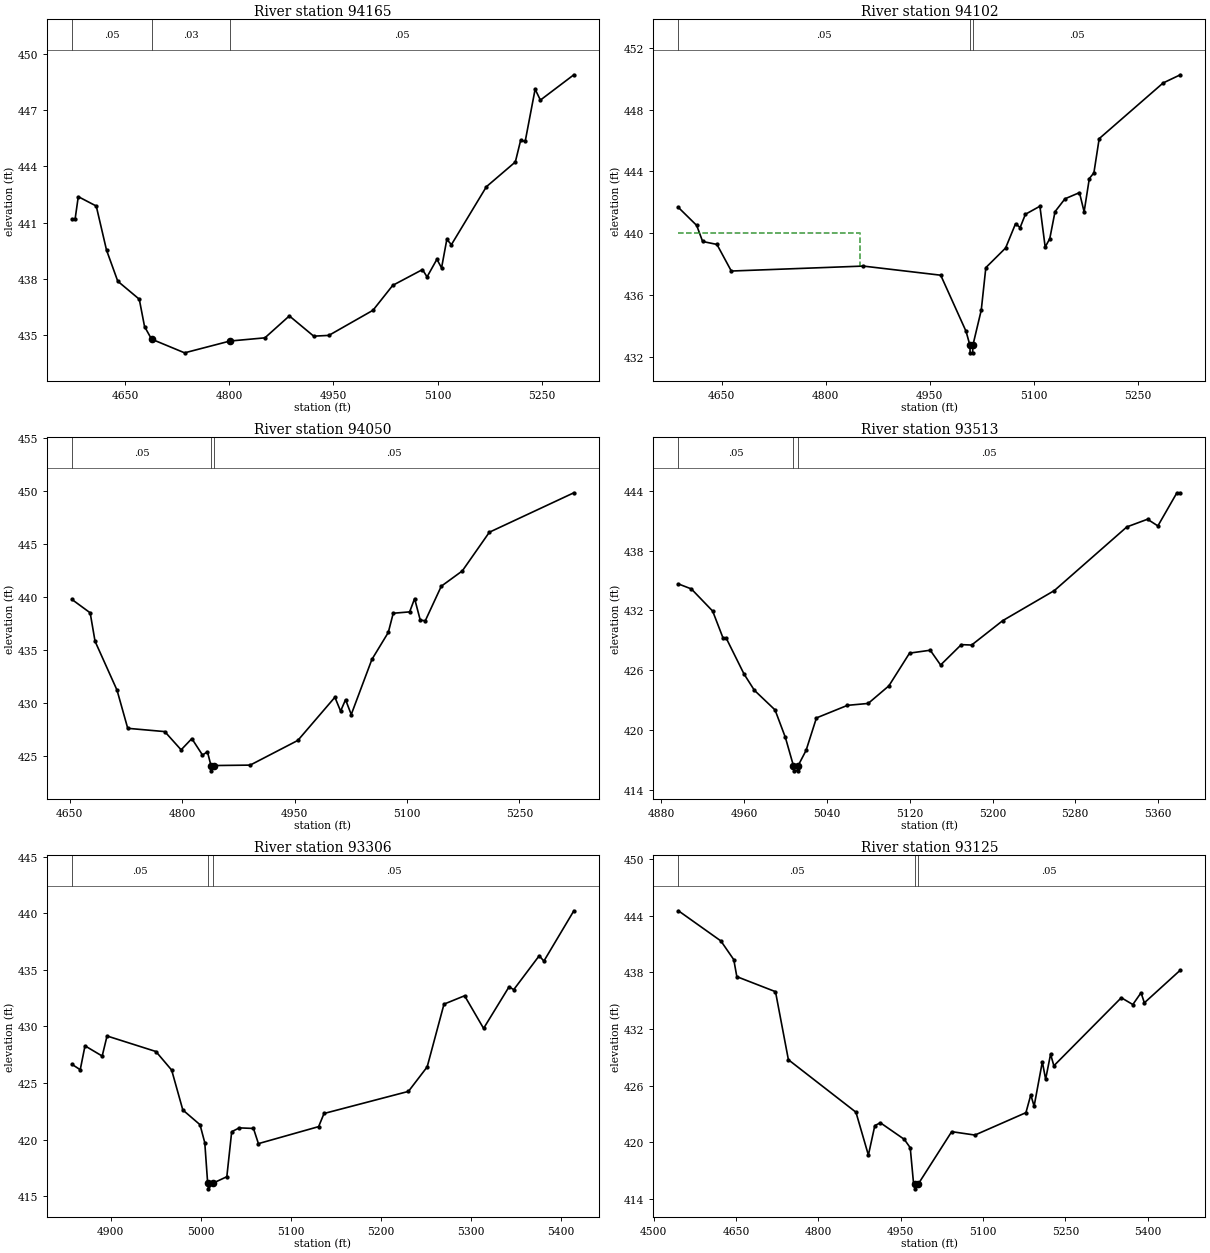
Type RM Length L Ch R = 1,94165,63,63,63
BEGIN DESCRIPTION:
Walnut Creek 141.4
END DESCRIPTION:
XS GIS Cut Line= 2
      2782847.88      6763958.38      2783322.66      6764503.78
#Sta/Elev= 30
  4573.2  441.18  4577.7  441.18  4582.3  442.39  4608.2  441.89  4623.0  439.54
  4639.2  437.88  4670.2  436.92  4677.8  435.46  4687.9  434.79  4735.5  434.06
  4800.9  434.69  4851.2  434.86  4886.4  436.03  4921.5  434.95  4943.3  434.99
  5006.9  436.33  5035.4  437.66  5078.2  438.50  5084.8  438.11  5099.0  439.05
  5105.7  438.59  5113.3  440.11  5119.9  439.83  5170.3  442.92  5212.0  444.24
  5219.6  445.39  5226.2  445.34  5240.5  448.12  5248.1  447.54  5296.3  448.89
#Mann=3,-1,0
  4573.2    0.05       0  4687.9    0.03       0  4800.9    0.05       0
Bank Sta=4687.9,4800.9
Exp/Cntr=0.3,0.1

Type RM Length L Ch R = 1,94102,52,52,52
BEGIN DESCRIPTION:
Walnut Creek 141.2
END DESCRIPTION:
XS GIS Cut Line= 3
      2782675.27      6763777.22      2782702.00      6763880.84
      2783106.52      6764345.53
#Sta/Elev= 30
  4587.9  441.67  4614.2  440.51  4622.8  439.47  4643.4  439.28  4664.1  437.56
  4854.2  437.88  4965.8  437.29  5002.3  433.66  5007.8  432.77  5008.2  432.27
  5011.8  432.27  5012.2  432.77  5024.2  435.03  5030.8  437.78  5059.3  439.05
  5073.6  440.62  5080.2  440.37  5087.8  441.23  5108.7  441.75  5116.3  439.11
  5122.9  439.65  5130.5  441.40  5144.8  442.23  5165.7  442.63  5172.4  441.39
  5179.9  443.54  5186.5  443.91  5194.1  446.12  5286.2  449.72  5311.0  450.25
#Mann=3,-1,0
  4587.9    0.05       0  5007.8    0.03       0  5012.2    0.05       0
#XS Ineff=2,0
    0.00 4850.00  440.00               0
Permanent Ineff=
       F       F
Bank Sta=5007.8,5012.2
Exp/Cntr=0.3,0.1

Type RM Length L Ch R = 1,94050,537,537,537
BEGIN DESCRIPTION:
Walnut Creek 141.0
END DESCRIPTION:
XS GIS Cut Line= 3
      2782627.52      6763845.60      2782658.54      6763890.86
      2783062.03      6764354.37
#Sta/Elev= 30
  4653.1  439.75  4677.4  438.49  4683.9  435.81  4713.2  431.20  4727.5  427.60
  4776.9  427.29  4798.7  425.57  4813.0  426.63  4827.2  425.08  4833.8  425.39
  4838.5  424.09  4838.9  423.59  4842.9  424.09  4890.8  424.13  4954.4  426.46
  5003.8  430.53  5011.4  429.22  5018.0  430.30  5025.6  428.90  5053.1  434.09
  5075.0  436.64  5081.6  438.45  5103.5  438.58  5110.1  439.83  5117.7  437.79
  5124.4  437.75  5145.7  441.00  5173.7  442.44  5209.8  446.09  5322.5  449.81
#Mann=3,-1,0
  4653.1    0.05       0  4838.5    0.05       0  4842.9    0.05       0
Bank Sta=4838.5,4842.9
Exp/Cntr=0.3,0.1

Type RM Length L Ch R = 1,93513,207,207,207
BEGIN DESCRIPTION:
Walnut Creek 140.0
END DESCRIPTION:
XS GIS Cut Line= 3
      2782401.56      6764008.93      2782390.68      6764051.34
      2782387.76      6764492.65
#Sta/Elev= 30
  4896.4  434.66  4908.9  434.16  4929.5  431.94  4939.5  429.25  4942.5  429.25
  4959.8  425.64  4969.8  424.01  4989.8  422.04  4999.8  419.28  5007.6  416.44
  5008.0  415.94  5011.6  415.94  5012.0  416.44  5019.8  417.99  5029.8  421.24
  5059.8  422.50  5079.8  422.69  5099.8  424.45  5119.8  427.73  5139.8  428.02
  5149.8  426.54  5169.8  428.58  5179.8  428.54  5209.8  430.98  5259.8  434.00
  5329.8  440.37  5349.8  441.14  5359.8  440.47  5378.2  443.79  5381.5  443.79
#Mann=3,-1,0
  4896.4    0.05       0  5007.6    0.05       0  5012.0    0.05       0
Bank Sta=5007.6,5012
Exp/Cntr=0.3,0.1

Type RM Length L Ch R = 1,93306,181,181,181
BEGIN DESCRIPTION:
Walnut Creek 139.0
END DESCRIPTION:
XS GIS Cut Line= 3
      2782274.46      6763877.81      2782201.05      6764065.67
      2782300.40      6764407.53
#Sta/Elev= 30
  4857.0  426.66  4866.2  426.18  4871.5  428.29  4890.6  427.39  4896.0  429.16
  4950.3  427.79  4967.8  426.15  4980.2  422.63  4999.3  421.33  5004.6  419.74
  5007.8  416.17  5008.7  415.67  5013.7  416.17  5029.1  416.74  5034.5  420.71
  5042.9  421.05  5058.7  421.00  5064.2  419.66  5131.1  421.16  5137.1  422.32
  5230.9  424.27  5251.7  426.43  5270.4  431.97  5293.3  432.71  5314.4  429.83
  5342.7  433.50  5347.9  433.25  5376.2  436.24  5381.4  435.77  5414.7  440.21
#Mann=3,-1,0
  4857.0    0.05       0  5007.8    0.05       0  5013.7    0.05       0
Bank Sta=5007.8,5013.7
Exp/Cntr=0.3,0.1

Type RM Length L Ch R = 1,93125,150,150,150
BEGIN DESCRIPTION:
Walnut Creek 138.7
END DESCRIPTION:
XS GIS Cut Line= 3
      2781861.16      6763593.31      2782060.14      6764054.67
      2782290.79      6764395.64
#Sta/Elev= 30
  4545.1  444.50  4622.4  441.31  4645.9  439.33  4651.5  437.53  4721.9  435.94
  4745.4  428.74  4868.4  423.19  4891.1  418.65  4902.8  421.77  4912.9  422.07
  4956.4  420.32  4967.3  419.43  4973.4  415.61  4975.8  415.58  4976.8  415.08
  4981.8  415.58  5042.8  421.13  5085.1  420.77  5178.0  423.14  5186.9  425.03
  5192.9  423.82  5207.9  428.52  5213.9  426.67  5222.9  429.33  5228.9  428.10
  5351.7  435.30  5372.7  434.58  5387.7  435.83  5393.7  434.76  5459.2  438.22
#Mann=3,-1,0
  4545.1    0.05       0  4975.8    0.05       0  4981.8    0.05       0
Bank Sta=4975.8,4981.8
Exp/Cntr=0.3,0.1

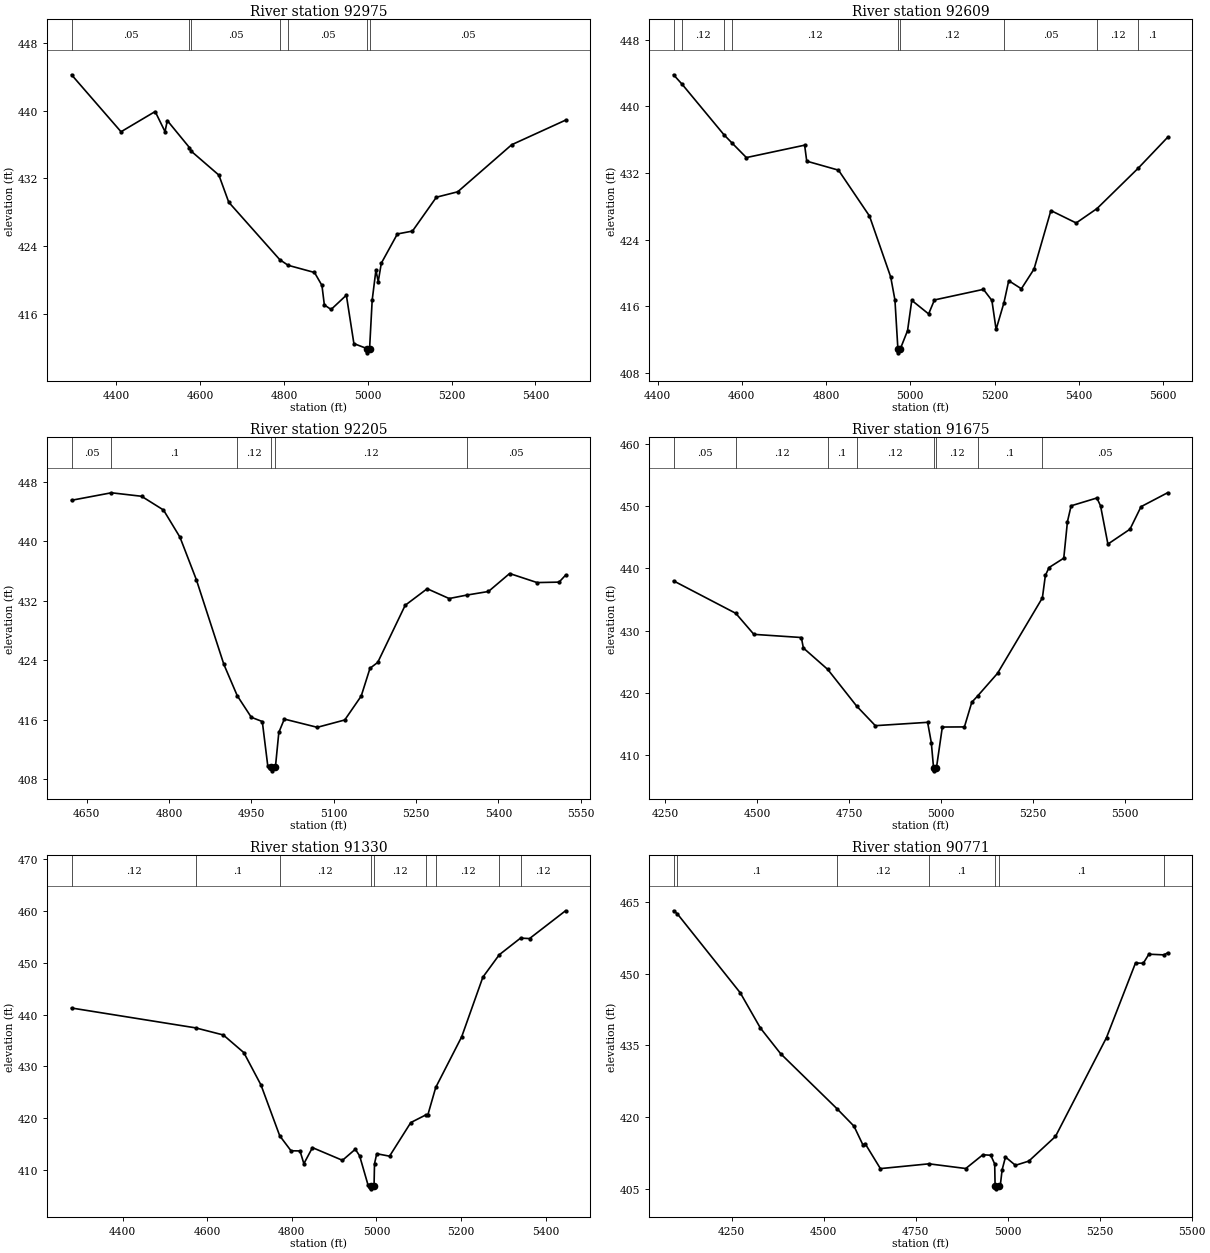
Type RM Length L Ch R = 1,92975,366,366,366
BEGIN DESCRIPTION:
Walnut Creek 138.5
END DESCRIPTION:
XS GIS Cut Line= 3
      2781612.15      6763362.63      2781916.39      6764068.05
      2782146.04      6764407.54
#Sta/Elev= 30
  4293.6  444.23  4411.6  437.50  4493.0  439.89  4516.5  437.52  4522.0  438.82
  4574.8  435.63  4578.7  435.22  4645.0  432.38  4668.5  429.18  4790.3  422.39
  4810.1  421.73  4873.0  420.88  4890.8  419.35  4896.5  417.05  4912.6  416.51
  4949.0  418.20  4967.0  412.48  4998.4  411.89  4999.4  411.39  5004.4  411.89
  5010.6  417.61  5019.5  421.15  5025.0  419.80  5032.4  421.98  5070.7  425.43
  5106.7  425.77  5163.7  429.77  5214.6  430.41  5343.4  435.97  5471.7  438.87
#Mann=7,-1,0
  4293.6    0.05       0  4574.8    0.12       0  4578.7    0.05       0
  4790.3    0.12       0  4810.1    0.05       0  4998.4    0.03       0
  5004.4    0.05       0
Bank Sta=4998.4,5004.4
Exp/Cntr=0.3,0.1

Type RM Length L Ch R = 1,92609,404,404,404
BEGIN DESCRIPTION:
Walnut Creek 138.0
END DESCRIPTION:
XS GIS Cut Line= 3
      2781511.88      6763399.43      2781575.39      6763904.24
      2781548.72      6764567.71
#Sta/Elev= 30
  4437.8  443.79  4458.5  442.63  4557.5  436.59  4576.6  435.60  4610.7  433.85
  4749.0  435.34  4754.0  433.42  4829.4  432.34  4903.0  426.83  4953.4  419.51
  4963.4  416.76  4970.4  410.91  4971.4  410.41  4976.4  410.91  4993.4  413.08
  5003.4  416.71  5043.4  415.08  5057.2  416.76  5173.5  418.03  5193.6  416.70
  5203.6  413.22  5222.3  416.44  5233.6  419.07  5263.6  418.10  5293.6  420.46
  5333.7  427.49  5393.7  426.00  5443.2  427.73  5541.1  432.58  5610.6  436.27
#Mann=9,-1,0
  4437.8    0.05       0  4458.5    0.12       0  4557.5     0.1       0
  4576.6    0.12       0  4970.4    0.07       0  4976.4    0.12       0
  5222.3    0.05       0  5443.2    0.12       0  5541.1     0.1       0
Bank Sta=4970.4,4976.4
Exp/Cntr=0.3,0.1

Type RM Length L Ch R = 1,92205,530,530,530
BEGIN DESCRIPTION:
Walnut Creek 137.0
END DESCRIPTION:
XS GIS Cut Line= 3
      2781187.60      6763633.48      2781190.94      6763967.76
      2781164.20      6764532.73
#Sta/Elev= 30
  4622.4  445.55  4695.0  446.56  4749.9  446.09  4789.9  444.24  4819.9  440.58
  4849.9  434.83  4899.9  423.45  4924.3  419.23  4949.9  416.33  4969.9  415.76
  4980.0  409.71  4986.1  409.62  4987.3  409.12  4993.8  409.62  5000.0  414.29
  5010.0  416.09  5070.1  414.98  5120.1  415.97  5150.1  419.19  5166.1  422.93
  5180.2  423.72  5230.2  431.41  5270.3  433.64  5310.3  432.32  5342.0  432.78
  5381.9  433.27  5420.5  435.69  5470.5  434.47  5510.6  434.53  5522.3  435.46
#Mann=6,-1,0
  4622.4    0.05       0  4695.0     0.1       0  4924.3    0.12       0
  4986.1    0.07       0  4993.8    0.12       0  5342.0    0.05       0
Bank Sta=4986.1,4993.8
Exp/Cntr=0.3,0.1

Type RM Length L Ch R = 1,91675,345,345,345
BEGIN DESCRIPTION:
Walnut Creek 136.0
END DESCRIPTION:
XS GIS Cut Line= 3
      2781007.06      6763342.64      2780722.91      6763961.07
      2780729.60      6764622.95
#Sta/Elev= 30
  4272.3  438.00  4441.4  432.77  4490.6  429.38  4619.6  428.87  4625.1  427.18
  4691.3  423.73  4769.9  417.82  4820.7  414.66  4962.8  415.20  4972.8  411.94
  4978.9  407.88  4980.1  407.38  4986.8  407.88  5002.8  414.44  5062.8  414.46
  5082.8  418.43  5098.6  419.44  5152.8  423.10  5274.7  435.26  5282.8  438.87
  5292.8  440.15  5332.8  441.66  5342.8  447.55  5352.8  450.10  5422.8  451.36
  5432.8  450.09  5452.8  443.93  5512.8  446.33  5542.8  449.96  5614.8  452.20
#Mann=8,-1,0
  4272.3    0.05       0  4441.4    0.12       0  4691.3     0.1       0
  4769.9    0.12       0  4978.9    0.07       0  4986.8    0.12       0
  5098.6     0.1       0  5274.7    0.05       0
Bank Sta=4978.9,4986.8
Exp/Cntr=0.3,0.1

Type RM Length L Ch R = 1,91330,559,559,559
BEGIN DESCRIPTION:
Walnut Creek 135.0
END DESCRIPTION:
XS GIS Cut Line= 3
      2780291.66      6763299.16      2780415.35      6764031.27
      2780448.79      6764455.87
#Sta/Elev= 30
  4278.9  441.26  4572.4  437.43  4637.9  436.06  4686.4  432.66  4727.0  426.41
  4771.3  416.62  4798.0  413.73  4819.3  413.70  4828.4  411.24  4848.7  414.34
  4919.7  411.89  4950.1  414.03  4960.3  412.75  4980.5  407.04  4986.5  406.89
  4987.7  406.39  4994.4  406.89  4995.5  411.24  5000.8  413.16  5031.1  412.69
  5081.3  419.17  5117.0  420.65  5121.4  420.57  5140.3  425.94  5201.7  435.71
  5251.8  447.21  5290.6  451.53  5340.9  454.74  5362.2  454.65  5447.3  460.01
#Mann=9,-1,0
  4278.9    0.12       0  4572.4     0.1       0  4771.3    0.12       0
  4986.5    0.07       0  4994.4    0.12       0  5117.0     0.1       0
  5140.3    0.12       0  5290.6     0.1       0  5340.9    0.12       0
Bank Sta=4986.5,4994.4
Exp/Cntr=0.3,0.1

Type RM Length L Ch R = 1,90771,361,361,361
BEGIN DESCRIPTION:
Walnut Creek 134.0
END DESCRIPTION:
XS GIS Cut Line= 3
      2779606.34      6763406.15      2779923.92      6764235.20
      2780305.06      6764482.61
#Sta/Elev= 30
  4092.2  463.12  4102.2  462.51  4273.5  445.96  4328.2  438.60  4383.0  433.25
  4536.2  421.74  4582.5  418.08  4607.2  414.09  4612.6  414.45  4654.2  409.21
  4786.2  410.21  4886.2  409.23  4932.7  412.11  4954.1  412.00  4964.8  410.18
  4965.9  405.48  4967.3  404.98  4976.0  405.48  4980.0  405.67  4985.0  408.97
  4994.1  411.63  5021.2  409.90  5057.5  410.78  5130.0  415.94  5268.6  436.61
  5347.4  452.20  5368.6  452.15  5383.7  454.04  5424.7  453.90  5434.4  454.31
#Mann=7,-1,0
  4092.2    0.12       0  4102.2     0.1       0  4536.2    0.12       0
  4786.2     0.1       0  4965.9    0.07       0  4976.0     0.1       0
  5424.7    0.12       0
Bank Sta=4965.9,4976
Exp/Cntr=0.3,0.1