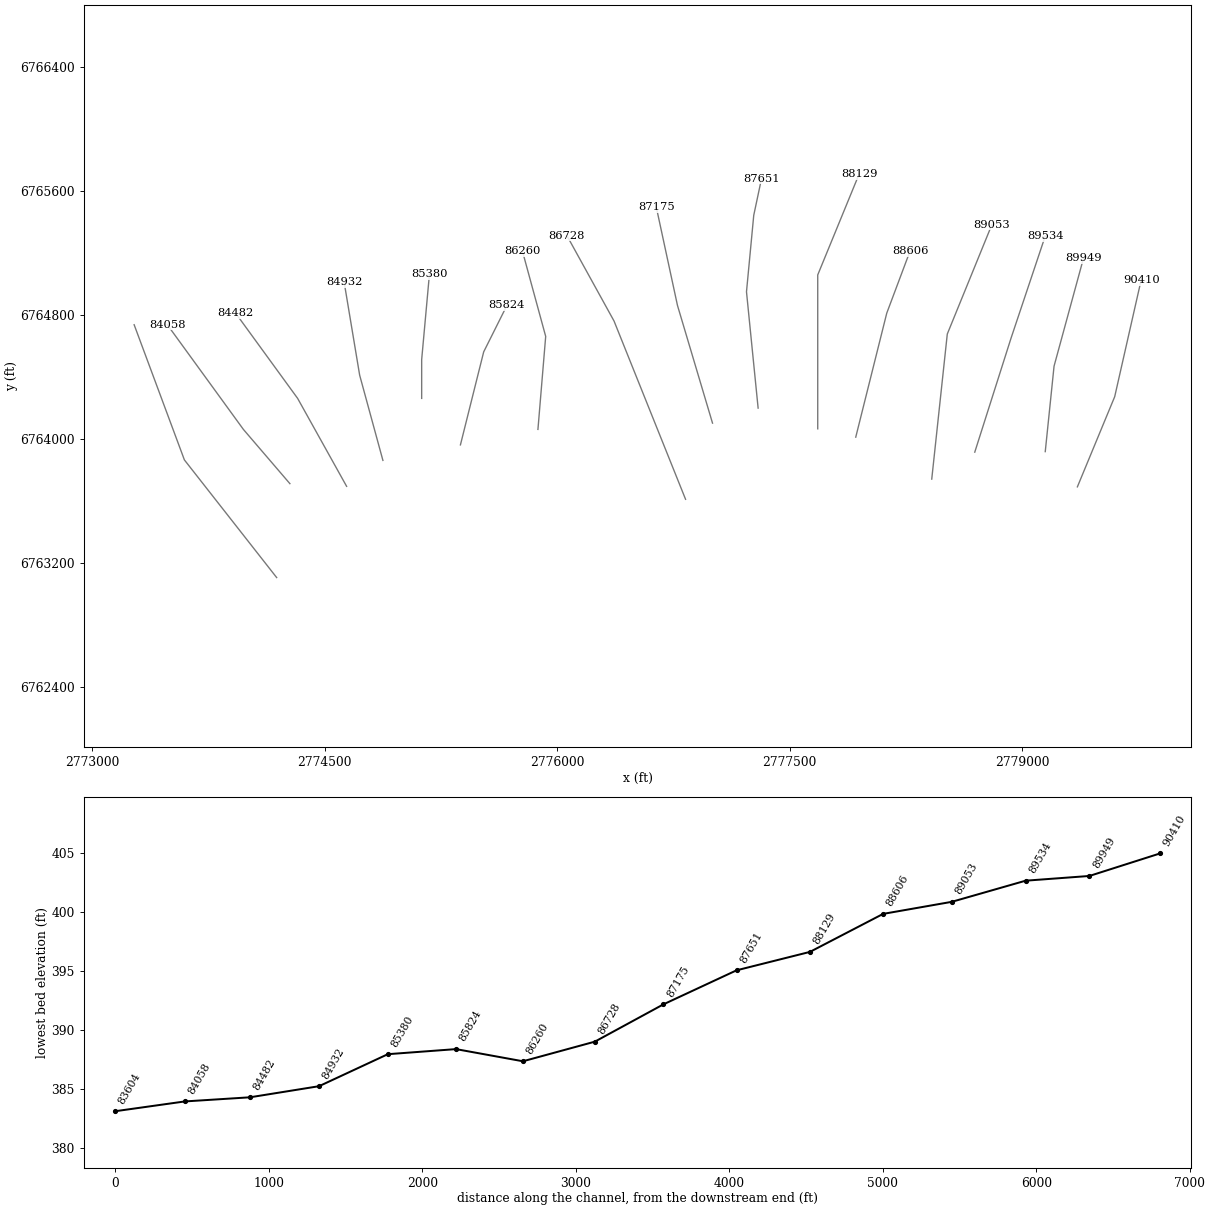
HEC-RAS study Walnut Creek.prj: Walnut Creek Base Level Engineering

--- Walnut Creek.g01 (geometry) --- (continued)

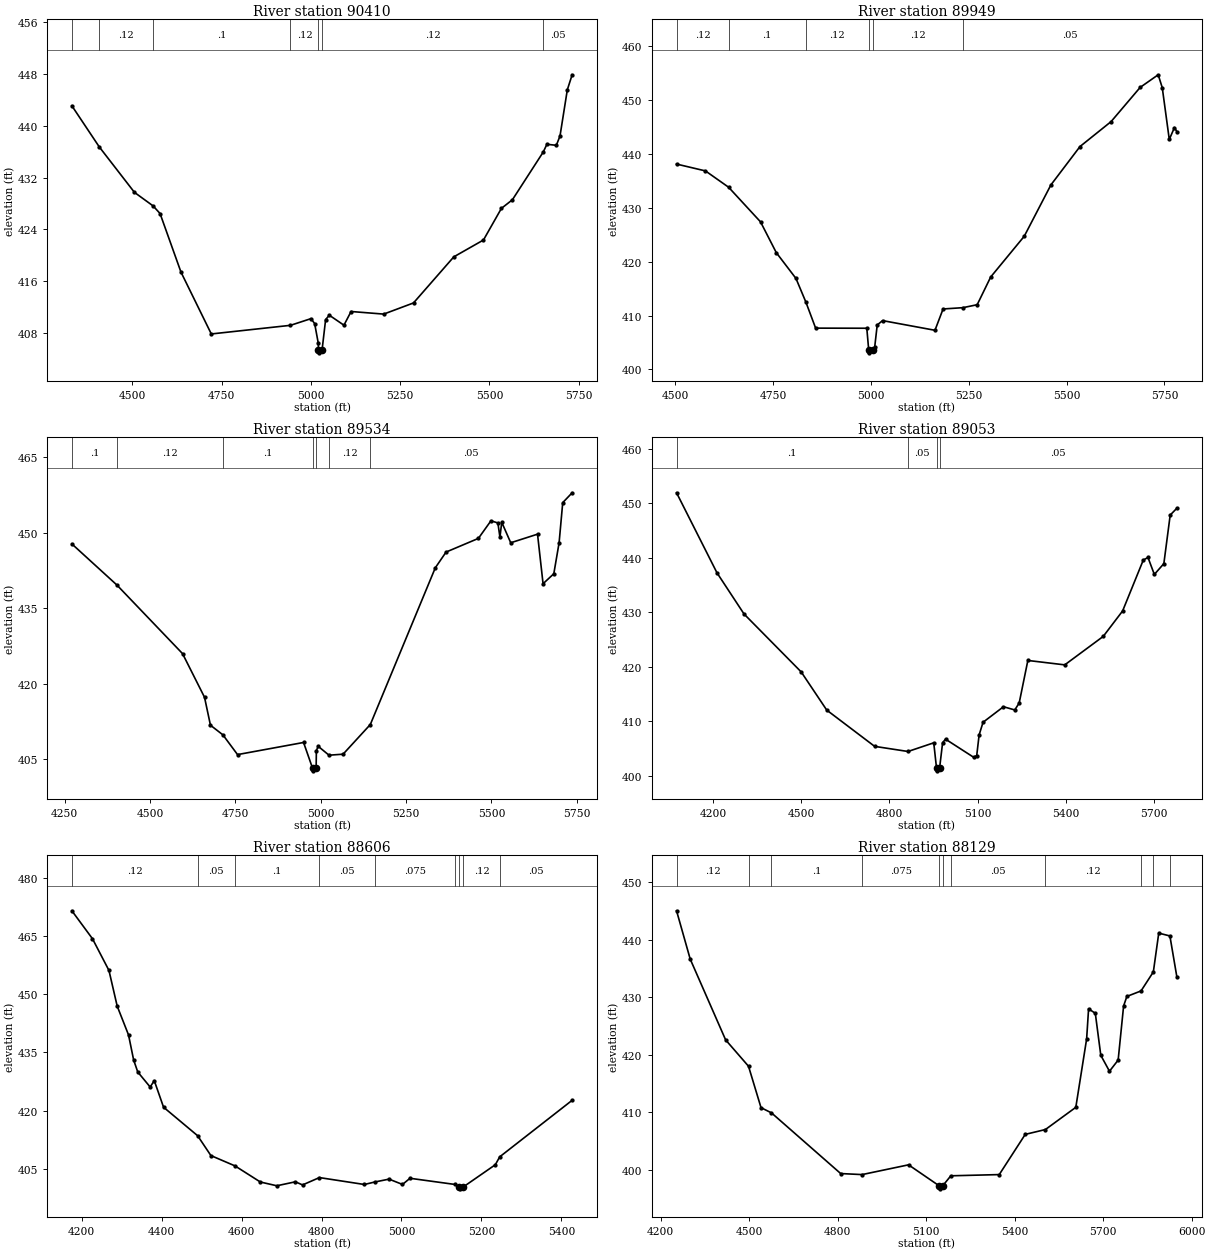
Type RM Length L Ch R = 1,90410,461,461,461
BEGIN DESCRIPTION:
Walnut Creek 133.0
END DESCRIPTION:
XS GIS Cut Line= 3
      2779355.61      6763690.30      2779596.30      6764271.97
      2779766.80      6765024.19
#Sta/Elev= 30
  4330.7  443.05  4407.5  436.71  4505.9  429.71  4558.2  427.62  4577.6  426.45
  4636.2  417.42  4721.1  407.89  4942.8  409.22  5000.2  410.25  5010.5  409.49
  5020.7  406.45  5021.2  405.48  5022.6  404.98  5031.4  405.48  5041.2  410.10
  5051.5  410.78  5092.5  409.24  5112.5  411.35  5203.9  410.95  5287.3  412.67
  5400.1  419.77  5483.2  422.37  5533.4  427.24  5564.2  428.57  5650.7  435.94
  5660.8  437.12  5687.2  436.96  5697.5  438.40  5718.0  445.52  5731.5  447.83
#Mann=7,-1,0
  4330.7     0.1       0  4407.5    0.12       0  4558.2     0.1       0
  4942.8    0.12       0  5021.2    0.07       0  5031.4    0.12       0
  5650.7    0.05       0
Bank Sta=5021.2,5031.4
Exp/Cntr=0.3,0.1

Type RM Length L Ch R = 1,89949,415,415,415
BEGIN DESCRIPTION:
Walnut Creek 132.0
END DESCRIPTION:
XS GIS Cut Line= 3
      2779148.34      6763917.63      2779205.17      6764469.21
      2779395.45      6765166.93
#Sta/Elev= 30
  4503.8  438.14  4577.6  436.87  4636.7  433.84  4718.3  427.40  4758.5  421.69
  4808.8  416.89  4834.2  412.48  4859.0  407.66  4989.7  407.64  4994.6  403.57
  4996.0  403.07  5004.9  403.57  5009.8  404.10  5016.3  408.24  5029.9  409.06
  5163.8  407.26  5184.5  411.22  5235.0  411.46  5271.6  412.01  5306.1  417.16
  5391.8  424.73  5459.9  434.27  5534.2  441.40  5613.6  446.03  5687.9  452.39
  5733.9  454.73  5744.3  452.33  5762.2  442.72  5775.4  444.93  5781.5  444.17
#Mann=6,-1,0
  4503.8    0.12       0  4636.7     0.1       0  4834.2    0.12       0
  4994.6    0.07       0  5004.9    0.12       0  5235.0    0.05       0
Bank Sta=4994.6,5004.9
Exp/Cntr=0.3,0.1

Type RM Length L Ch R = 1,89534,481,481,481
BEGIN DESCRIPTION:
Walnut Creek 131.0
END DESCRIPTION:
XS GIS Cut Line= 3
      2778693.67      6763914.24      2778927.69      6764649.74
      2779147.95      6765307.19
#Sta/Elev= 30
  4271.1  447.79  4402.8  439.63  4595.2  425.98  4659.6  417.30  4677.0  411.74
  4713.5  409.82  4756.3  405.90  4949.7  408.31  4976.1  403.17  4977.5  402.67
  4986.5  403.17  4987.2  406.68  4992.5  407.55  5024.2  405.78  5065.4  405.98
  5145.2  411.88  5335.5  443.04  5367.0  446.17  5461.7  448.89  5498.5  452.39
  5518.8  451.96  5524.8  449.12  5530.1  452.10  5556.4  448.02  5634.9  449.73
  5651.1  439.88  5682.6  441.86  5698.1  448.03  5708.7  456.00  5736.3  457.96
#Mann=7,-1,0
  4271.1     0.1       0  4402.8    0.12       0  4713.5     0.1       0
  4976.1    0.07       0  4986.5     0.1       0  5024.2    0.12       0
  5145.2    0.05       0
Bank Sta=4976.1,4986.5
Exp/Cntr=0.3,0.1

Type RM Length L Ch R = 1,89053,447,447,447
BEGIN DESCRIPTION:
Walnut Creek 130.0
END DESCRIPTION:
XS GIS Cut Line= 3
      2778416.20      6763740.40      2778516.50      6764676.48
      2778804.01      6765381.90
#Sta/Elev= 30
  4075.4  451.89  4213.0  437.21  4305.2  429.65  4499.7  419.03  4586.8  412.02
  4749.8  405.37  4863.4  404.43  4951.0  406.02  4960.5  401.38  4961.9  400.88
  4970.9  401.38  4981.2  406.05  4991.2  406.69  5086.8  403.37  5097.3  403.67
  5105.5  407.47  5118.9  409.79  5188.4  412.64  5226.9  412.05  5241.9  413.33
  5271.4  421.13  5397.0  420.32  5528.0  425.54  5594.0  430.21  5664.4  439.55
  5680.4  440.02  5702.0  436.91  5734.4  438.89  5756.0  447.80  5778.6  449.05
#Mann=4,-1,0
  4075.4     0.1       0  4863.4    0.05       0  4960.5    0.03       0
  4970.9    0.05       0
Bank Sta=4960.5,4970.9
Exp/Cntr=0.3,0.1

Type RM Length L Ch R = 1,88606,477,477,477
BEGIN DESCRIPTION:
Walnut Creek 129.0
END DESCRIPTION:
XS GIS Cut Line= 3
      2777925.99      6764010.98      2778126.00      6764811.00
      2778275.98      6765210.96
#Sta/Elev= 30
  4175.3  471.49  4226.9  464.28  4268.1  456.12  4288.7  446.93  4317.1  439.50
  4329.9  433.03  4340.2  429.96  4371.2  426.09  4381.5  427.73  4404.7  420.89
  4490.0  413.54  4523.2  408.43  4583.5  405.77  4646.9  401.62  4688.1  400.65
  4734.5  401.67  4752.6  400.87  4794.7  402.76  4907.2  400.98  4933.5  401.63
  4969.0  402.36  5002.6  400.99  5021.3  402.58  5134.0  400.99  5144.1  400.36
  5145.6  399.86  5154.8  400.36  5234.9  406.07  5245.8  408.10  5427.1  422.67
#Mann=9,-1,0
  4175.3    0.12       0  4490.0    0.05       0  4583.5     0.1       0
  4794.7    0.05       0  4933.5   0.075       0  5134.0    0.12       0
  5144.1    0.07       0  5154.8    0.12       0  5245.8    0.05       0
Bank Sta=5144.1,5154.8
Exp/Cntr=0.3,0.1

Type RM Length L Ch R = 1,88129,478,478,478
BEGIN DESCRIPTION:
Walnut Creek 128.0
END DESCRIPTION:
XS GIS Cut Line= 3
      2777680.73      6764064.73      2777680.73      6765057.59
      2777947.46      6765707.74
#Sta/Elev= 30
  4254.2  445.04  4300.5  436.63  4420.5  422.57  4498.1  417.98  4540.5  410.77
  4576.0  409.86  4810.5  399.30  4883.0  399.12  5040.5  400.82  5145.1  397.14
  5146.6  396.64  5155.9  397.14  5183.8  398.91  5347.9  399.12  5436.0  406.12
  5504.3  406.96  5607.4  410.83  5644.1  422.74  5650.7  427.98  5673.5  427.19
  5692.1  419.88  5721.5  417.11  5750.9  419.05  5769.4  428.47  5780.4  430.13
  5828.5  431.09  5870.2  434.40  5888.5  441.15  5926.3  440.66  5949.8  433.56
#Mann=11,-1,0
  4254.2    0.12       0  4498.1    0.05       0  4576.0     0.1       0
  4883.0   0.075       0  5145.1    0.07       0  5155.9   0.075       0
  5183.8    0.05       0  5504.3    0.12       0  5828.5   0.075       0
  5870.2    0.05       0  5926.3   0.075       0
Bank Sta=5145.1,5155.9
Exp/Cntr=0.3,0.1

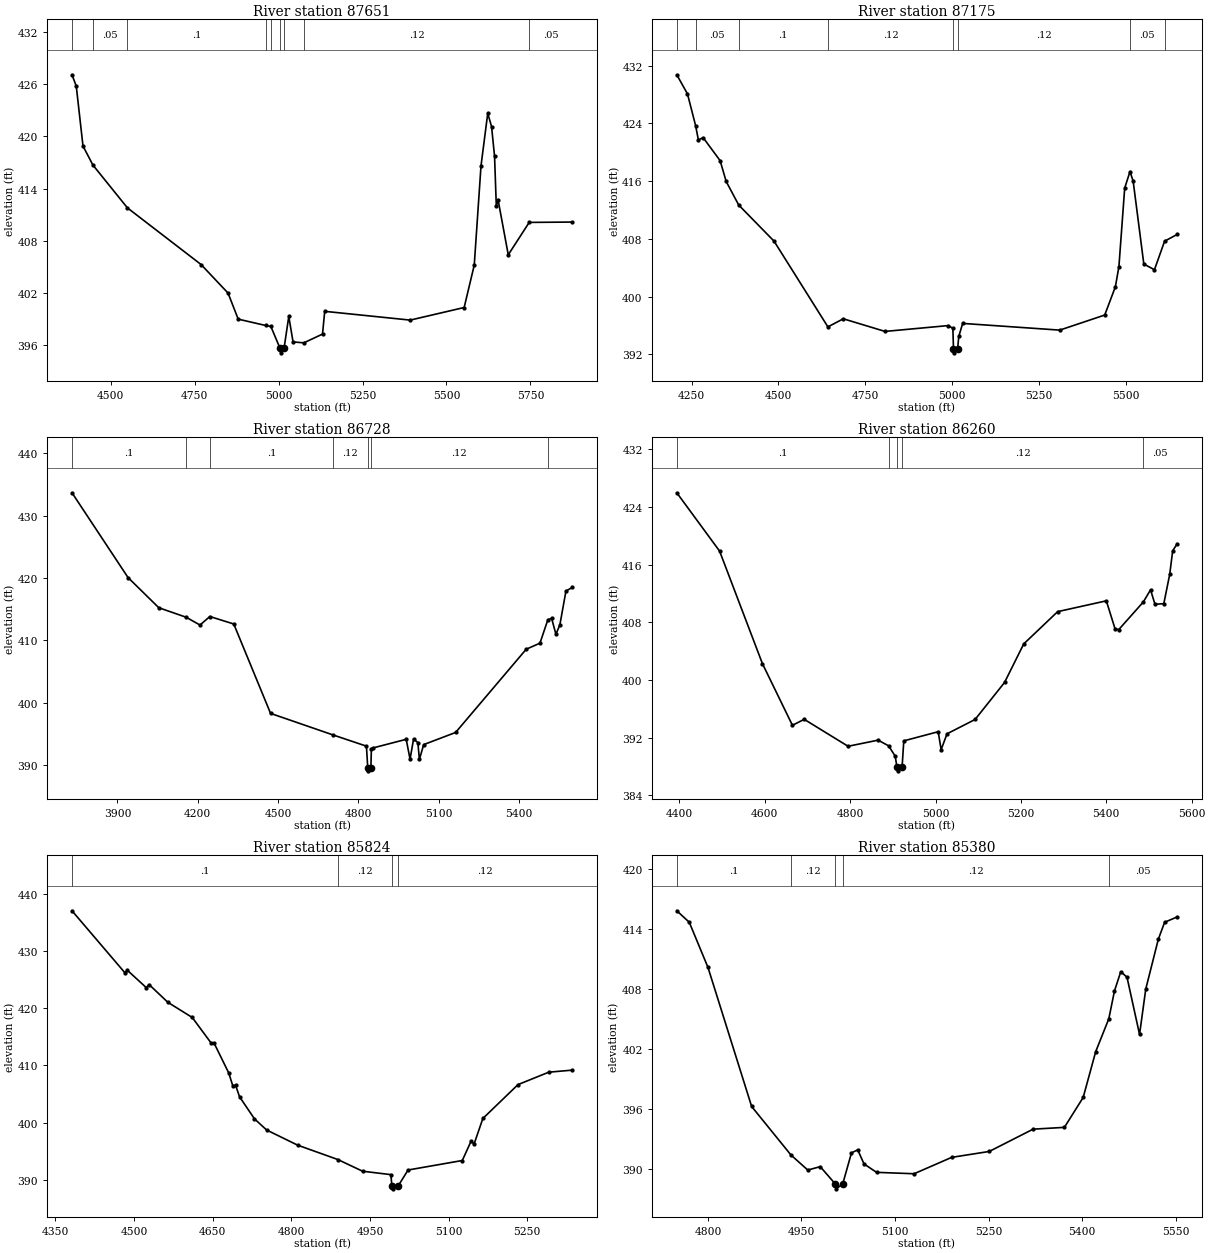
Type RM Length L Ch R = 1,87651,476,476,476
BEGIN DESCRIPTION:
Walnut Creek 127.0
END DESCRIPTION:
XS GIS Cut Line= 4
      2777296.28      6764198.40      2777221.23      6764948.93
      2777268.03      6765442.32      2777317.86      6765677.52
#Sta/Elev= 30
  4384.4  427.10  4397.1  425.80  4417.2  418.89  4446.8  416.70  4549.6  411.77
  4768.9  405.25  4849.3  401.96  4879.5  398.96  4961.3  398.23  4976.8  398.12
  5004.3  395.58  5005.9  395.08  5016.0  395.58  5030.2  399.27  5042.9  396.34
  5075.0  396.23  5130.7  397.24  5137.2  399.86  5391.9  398.85  5552.6  400.30
  5582.7  405.18  5602.8  416.61  5622.9  422.67  5634.3  421.12  5643.2  417.69
  5648.4  411.98  5653.5  412.73  5684.0  406.37  5746.4  410.10  5874.7  410.14
#Mann=9,-1,0
  4384.4     0.1       0  4446.8    0.05       0  4549.6     0.1       0
  4961.3    0.12       0  4976.8    0.05       0  5004.3    0.05       0
  5016.0    0.05       0  5075.0    0.12       0  5746.4    0.05       0
Bank Sta=5004.3,5016
Exp/Cntr=0.3,0.1

Type RM Length L Ch R = 1,87175,447,447,447
BEGIN DESCRIPTION:
Walnut Creek 126.0
END DESCRIPTION:
XS GIS Cut Line= 3
      2777002.09      6764101.47      2776776.00      6764861.00
      2776639.48      6765494.69
#Sta/Elev= 30
  4207.5  430.75  4238.3  428.09  4261.9  423.65  4269.6  421.72  4283.3  422.04
  4332.2  418.85  4349.7  415.96  4385.8  412.69  4487.6  407.68  4642.6  395.80
  4687.0  396.92  4807.1  395.17  4989.5  395.98  5002.5  395.59  5004.3  392.70
  5005.9  392.20  5016.0  392.70  5019.5  394.47  5030.7  396.28  5310.3  395.35
  5439.8  397.44  5470.5  401.36  5480.7  404.17  5497.3  415.04  5512.6  417.34
  5521.7  416.00  5552.4  404.51  5583.0  403.72  5612.2  407.68  5648.2  408.61
#Mann=8,-1,0
  4207.5     0.1       0  4261.9    0.05       0  4385.8     0.1       0
  4642.6    0.12       0  5004.3    0.07       0  5016.0    0.12       0
  5512.6    0.05       0  5612.2   0.075       0
Bank Sta=5004.3,5016
Exp/Cntr=0.3,0.1

Type RM Length L Ch R = 1,86728,468,468,468
BEGIN DESCRIPTION:
Walnut Creek 125.0
END DESCRIPTION:
XS GIS Cut Line= 3
      2776828.26      6763610.02      2776366.91      6764760.06
      2776062.67      6765311.69
#Sta/Elev= 30
  3730.1  433.67  3939.4  420.07  4054.4  415.22  4156.8  413.69  4208.4  412.44
  4245.1  413.81  4334.5  412.61  4472.0  398.26  4705.5  394.80  4830.2  393.00
  4835.0  389.54  4836.7  389.04  4846.8  389.54  4848.6  392.54  4854.0  392.71
  4978.7  394.10  4993.1  390.92  5006.2  394.13  5022.3  393.58  5028.0  390.88
  5044.1  393.25  5163.3  395.20  5427.1  408.56  5478.5  409.53  5507.9  413.29
  5522.0  413.51  5538.1  410.97  5552.7  412.44  5575.6  417.91  5599.2  418.47
#Mann=7,-1,0
  3730.1     0.1       0  4156.8    0.05       0  4245.1     0.1       0
  4705.5    0.12       0  4835.0    0.07       0  4846.8    0.12       0
  5507.9    0.05       0
Bank Sta=4835,4846.8
Exp/Cntr=0.3,0.1

Type RM Length L Ch R = 1,86260,436,436,436
BEGIN DESCRIPTION:
Walnut Creek 124.0
END DESCRIPTION:
XS GIS Cut Line= 3
      2775876.00      6764061.04      2775926.00      6764661.00
      2775776.01      6765210.98
#Sta/Elev= 30
  4393.8  425.98  4494.1  417.88  4594.4  402.26  4664.7  393.70  4692.3  394.53
  4795.1  390.79  4865.4  391.64  4890.1  390.85  4905.5  389.41  4909.6  387.88
  4911.2  387.38  4921.6  387.88  4925.6  391.54  5006.2  392.81  5013.1  390.32
  5026.9  392.52  5092.6  394.51  5161.7  399.65  5206.6  405.00  5286.1  409.48
  5400.1  410.98  5420.8  407.05  5429.4  407.00  5486.8  410.82  5503.7  412.51
  5514.1  410.50  5534.8  410.59  5548.6  414.65  5555.6  417.92  5565.9  418.89
#Mann=5,-1,0
  4393.8     0.1       0  4890.1    0.12       0  4909.6    0.07       0
  4921.6    0.12       0  5486.8    0.05       0
Bank Sta=4909.6,4921.6
Exp/Cntr=0.3,0.1

Type RM Length L Ch R = 1,85824,444,444,444
BEGIN DESCRIPTION:
Walnut Creek 123.0
END DESCRIPTION:
XS GIS Cut Line= 3
      2775376.00      6763961.01      2775526.00      6764561.00
      2775676.02      6764861.03
#Sta/Elev= 30
  4382.0  436.99  4482.5  426.20  4487.6  426.59  4523.7  423.56  4528.9  424.11
  4564.9  420.99  4611.3  418.35  4647.4  413.87  4652.6  413.93  4680.9  408.65
  4688.6  406.41  4693.8  406.53  4701.5  404.49  4729.9  400.64  4753.1  398.69
  4812.3  396.04  4888.9  393.53  4936.0  391.49  4990.1  390.89  4991.9  388.91
  4993.5  388.41  5003.9  388.91  5022.8  391.70  5126.2  393.36  5143.0  396.75
  5148.6  396.22  5165.4  400.70  5232.4  406.62  5291.1  408.79  5335.9  409.15
#Mann=4,-1,0
  4382.0     0.1       0  4888.9    0.12       0  4991.9    0.07       0
  5003.9    0.12       0
Bank Sta=4991.9,5003.9
Exp/Cntr=0.3,0.1

Type RM Length L Ch R = 1,85380,448,448,448
BEGIN DESCRIPTION:
Walnut Creek 122.0
END DESCRIPTION:
XS GIS Cut Line= 3
      2775126.00      6764261.03      2775126.00      6764511.00
      2775176.00      6765060.96
#Sta/Elev= 30
  4750.1  415.80  4770.1  414.65  4800.1  410.13  4870.1  396.22  4933.1  391.37
  4960.1  389.86  4980.1  390.20  5004.1  388.48  5005.8  387.98  5016.2  388.48
  5030.2  391.58  5040.2  391.88  5050.3  390.47  5070.4  389.63  5130.6  389.49
  5190.9  391.13  5251.1  391.72  5321.4  393.95  5371.6  394.13  5401.7  397.12
  5421.8  401.71  5442.8  404.99  5451.9  407.78  5462.0  409.71  5472.0  409.15
  5492.1  403.43  5502.1  407.98  5522.2  412.95  5532.3  414.65  5552.3  415.18
#Mann=5,-1,0
  4750.1     0.1       0  4933.1    0.12       0  5004.1    0.07       0
  5016.2    0.12       0  5442.8    0.05       0
Bank Sta=5004.1,5016.2
Exp/Cntr=0.3,0.1

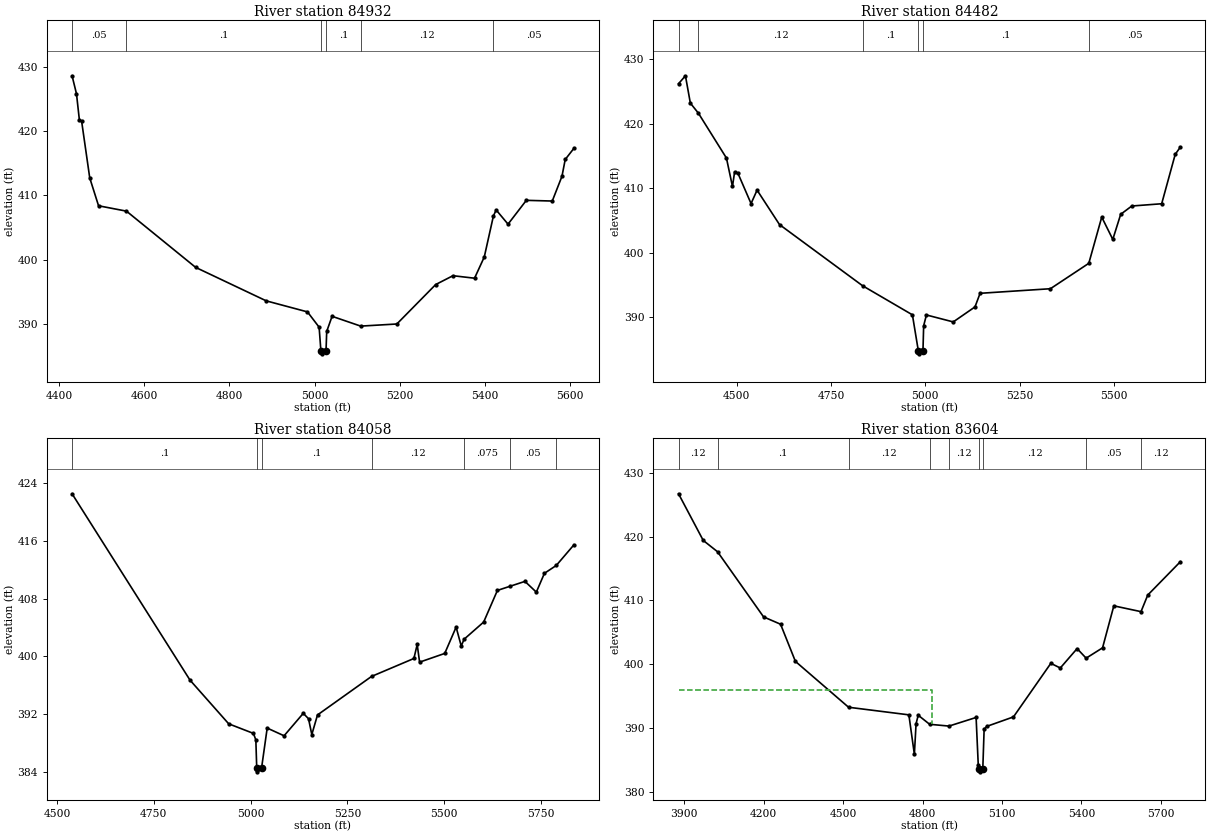
Type RM Length L Ch R = 1,84932,450,450,450
BEGIN DESCRIPTION:
Walnut Creek 121.0
END DESCRIPTION:
XS GIS Cut Line= 3
      2774876.00      6763861.01      2774726.00      6764411.00
      2774625.99      6765011.04
#Sta/Elev= 30
  4430.3  428.69  4440.7  425.87  4447.6  421.71  4452.8  421.57  4471.8  412.74
  4492.5  408.39  4558.1  407.55  4720.5  398.77  4886.4  393.54  4983.1  391.82
  5010.5  389.43  5014.6  385.77  5016.3  385.27  5026.7  385.77  5028.3  388.77
  5040.9  391.13  5108.1  389.60  5193.0  389.93  5284.2  396.09  5324.8  397.47
  5375.5  397.08  5398.3  400.39  5419.8  406.80  5426.2  407.74  5454.1  405.52
  5497.1  409.24  5558.0  409.13  5580.8  413.00  5588.4  415.62  5608.7  417.35
#Mann=6,-1,0
  4430.3    0.05       0  4558.1     0.1       0  5014.6    0.07       0
  5026.7     0.1       0  5108.1    0.12       0  5419.8    0.05       0
Bank Sta=5014.6,5026.7
Exp/Cntr=0.3,0.1

Type RM Length L Ch R = 1,84482,424,424,424
BEGIN DESCRIPTION:
Walnut Creek 120.0
END DESCRIPTION:
XS GIS Cut Line= 3
      2774641.88      6763693.64      2774326.00      6764261.00
      2773926.03      6764810.96
#Sta/Elev= 30
  4346.3  426.23  4364.6  427.46  4377.6  423.22  4398.9  421.66  4473.2  414.70
  4489.2  410.29  4494.9  412.57  4503.5  412.36  4538.4  407.64  4554.4  409.72
  4613.8  404.38  4833.7  394.90  4965.9  390.38  4981.5  384.83  4983.2  384.33
  4993.9  384.83  4995.7  388.68  5003.0  390.36  5074.1  389.28  5131.7  391.61
  5145.2  393.72  5331.5  394.43  5433.2  398.37  5467.5  405.54  5496.8  402.08
  5517.7  405.97  5547.1  407.26  5626.3  407.61  5662.2  415.28  5675.7  416.39
#Mann=6,-1,0
  4346.3    0.05       0  4398.9    0.12       0  4833.7     0.1       0
  4981.5    0.07       0  4993.9     0.1       0  5433.2    0.05       0
Bank Sta=4981.5,4993.9
Exp/Cntr=0.3,0.1

Type RM Length L Ch R = 1,84058,454,454,454
BEGIN DESCRIPTION:
Walnut Creek 119.0
END DESCRIPTION:
XS GIS Cut Line= 3
      2774275.97      6763711.04      2773976.00      6764061.00
      2773485.45      6764736.30
#Sta/Elev= 30
  4539.1  422.54  4843.6  396.70  4943.5  390.64  5007.4  389.31  5013.6  388.41
  5015.9  384.48  5017.6  383.98  5028.3  384.48  5042.9  390.05  5086.5  388.98
  5136.0  392.09  5149.6  391.35  5158.1  389.15  5172.8  391.87  5312.3  397.21
  5421.7  399.70  5430.2  401.64  5436.4  399.19  5501.3  400.40  5530.7  404.05
  5543.9  401.43  5551.3  402.37  5601.8  404.75  5637.3  409.14  5670.3  409.72
  5708.4  410.39  5737.8  408.90  5758.7  411.51  5789.3  412.60  5834.7  415.45
#Mann=7,-1,0
  4539.1     0.1       0  5015.9    0.07       0  5028.3     0.1       0
  5312.3    0.12       0  5551.3   0.075       0  5670.3    0.05       0
  5789.3    0.12       0
Bank Sta=5015.9,5028.3
Exp/Cntr=0.3,0.1

Type RM Length L Ch R = 1,83604,495,495,495
BEGIN DESCRIPTION:
Walnut Creek 118.0
END DESCRIPTION:
XS GIS Cut Line= 3
      2774190.60      6763105.22      2773595.51      6763864.12
      2773271.36      6764736.34
#Sta/Elev= 30
  3878.6  426.72  3971.9  419.41  4025.8  417.64  4199.7  407.43  4263.9  406.28
  4319.9  400.46  4520.7  393.27  4748.4  392.08  4769.2  385.90  4775.6  390.69
  4783.7  392.02  4826.8  390.60  4899.9  390.32  5002.3  391.67  5010.4  384.26
  5014.5  383.65  5016.3  383.15  5027.6  383.65  5032.6  389.82  5042.4  390.27
  5143.4  391.76  5284.5  400.15  5320.2  399.42  5383.7  402.46  5417.8  400.96
  5479.8  402.58  5522.4  409.16  5625.0  408.25  5650.5  410.85  5773.5  416.07
#Mann=9,-1,0
  3878.6    0.12       0  4025.8     0.1       0  4520.7    0.12       0
  4826.8    0.05       0  4899.9    0.12       0  5014.5    0.07       0
  5027.6    0.12       0  5417.8    0.05       0  5625.0    0.12       0
#XS Ineff=2,0
    0.00 4835.00  396.00               0
Permanent Ineff=
       F       F
Bank Sta=5014.5,5027.6
Exp/Cntr=0.3,0.1