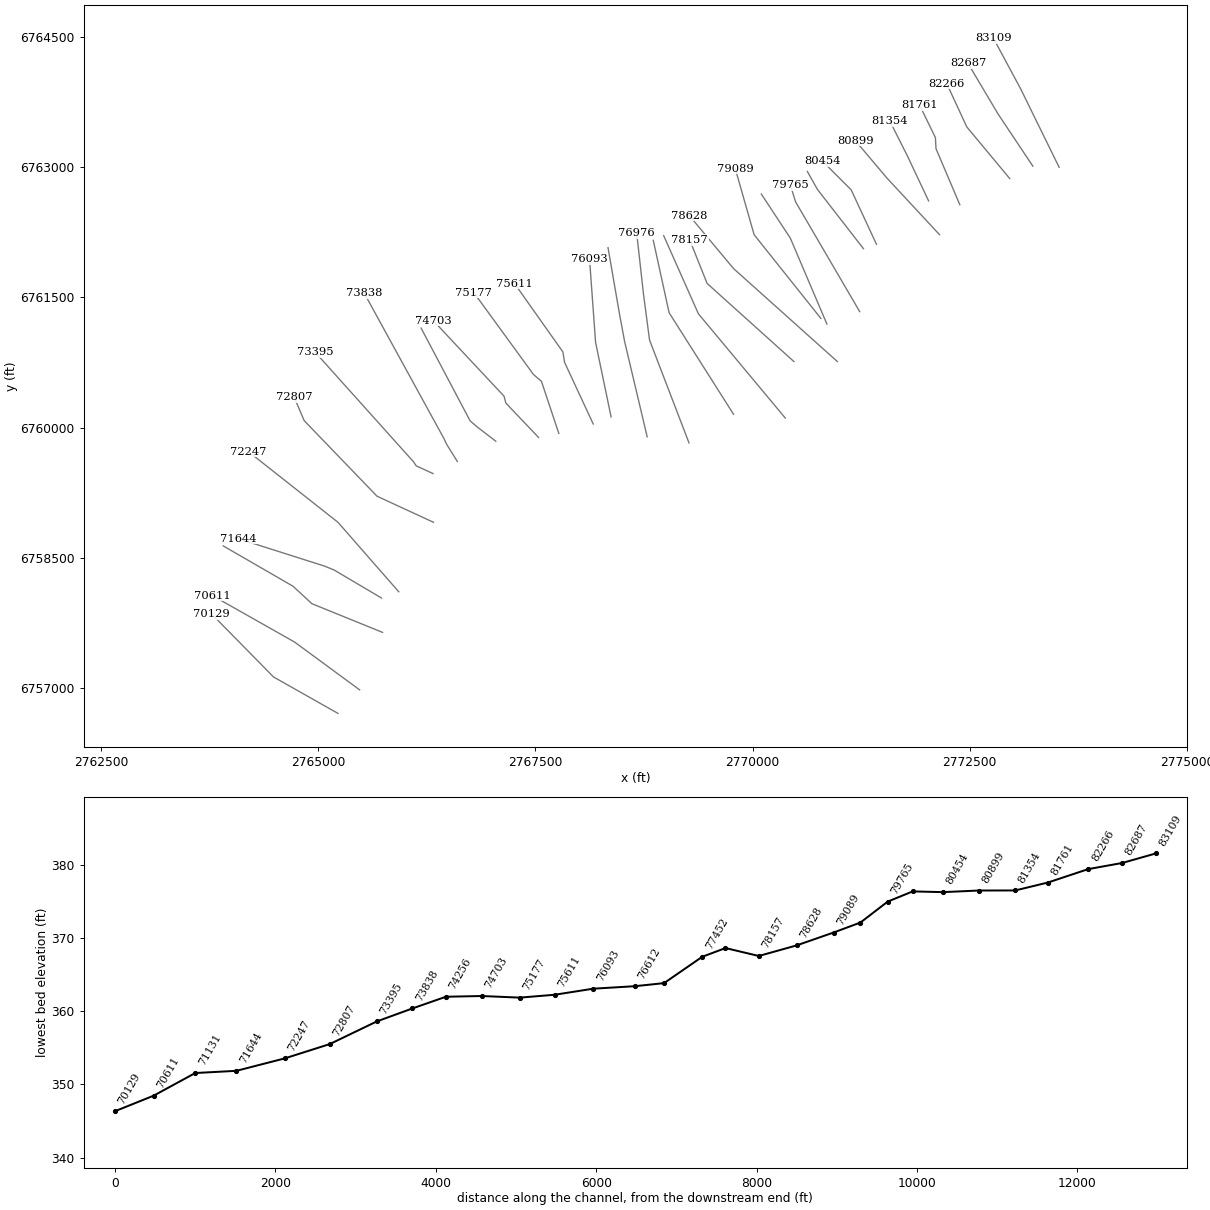
HEC-RAS study Walnut Creek.prj: Walnut Creek Base Level Engineering

--- Walnut Creek.g01 (geometry) --- (continued)

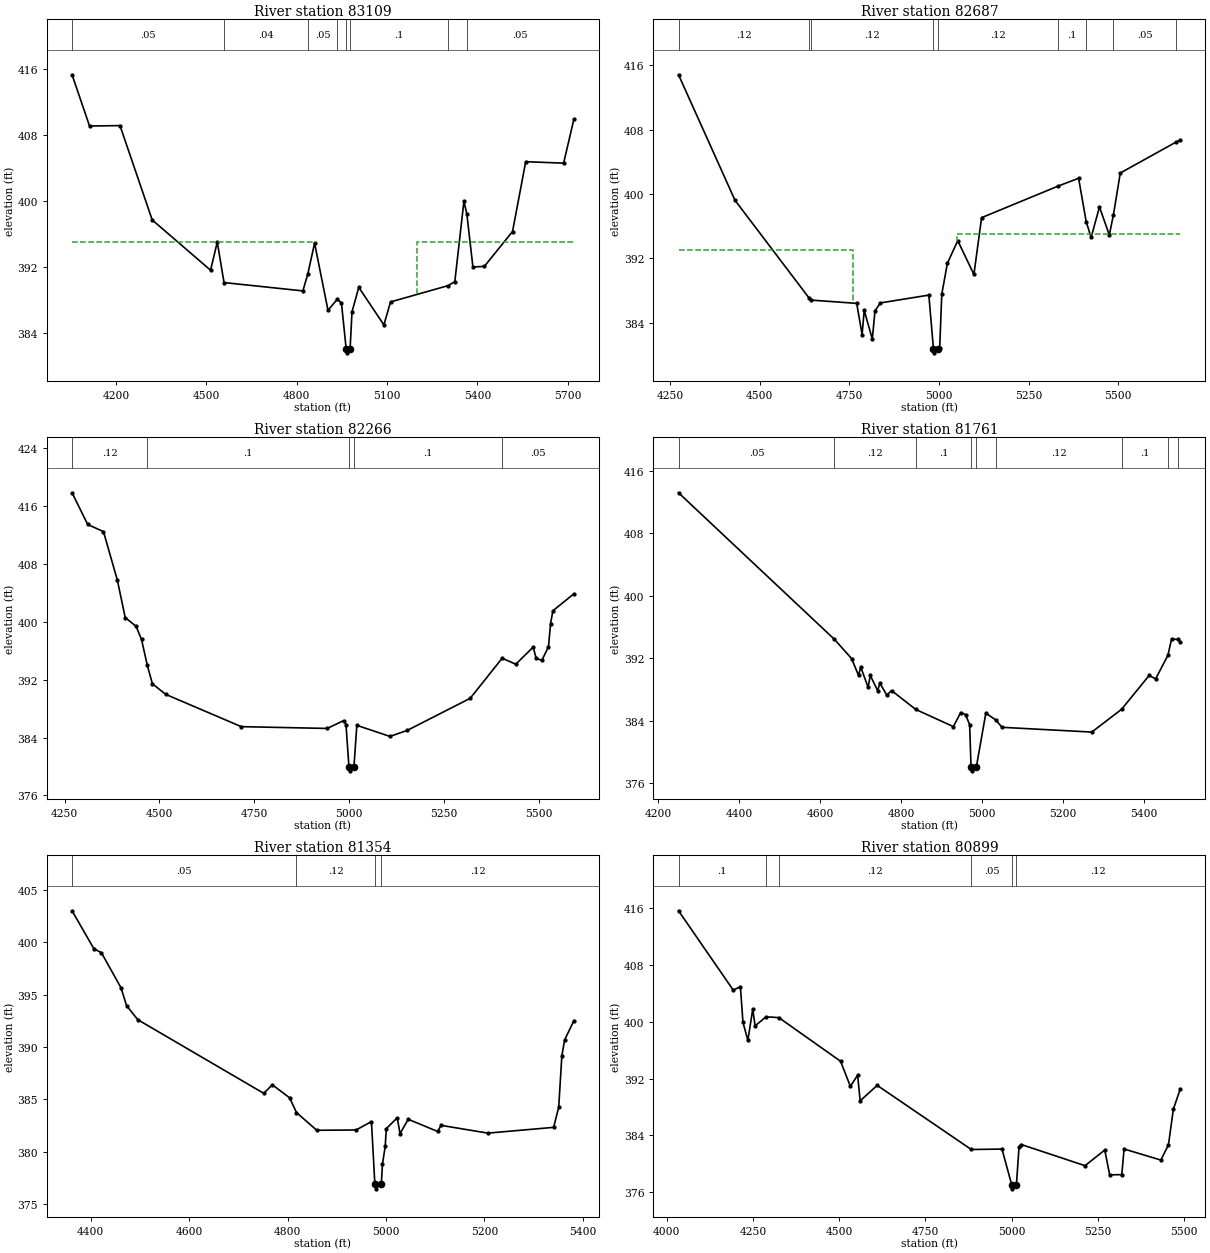
Type RM Length L Ch R = 1,83109,422,422,422
BEGIN DESCRIPTION:
Walnut Creek 117.0
END DESCRIPTION:
XS GIS Cut Line= 3
      2773528.66      6762998.25      2773087.37      6763897.55
      2772773.13      6764482.56
#Sta/Elev= 30
  4054.5  415.30  4112.5  409.08  4213.6  409.13  4320.5  397.68  4514.3  391.57
  4536.5  394.99  4559.0  390.07  4820.8  389.06  4837.0  391.11  4859.6  394.86
  4904.1  386.70  4934.7  388.04  4948.7  387.62  4964.4  382.04  4966.3  381.54
  4977.5  382.04  4983.8  386.52  5006.3  389.49  5089.7  384.93  5111.6  387.72
  5302.7  389.70  5325.1  390.18  5355.3  399.93  5365.0  398.40  5385.2  391.96
  5423.3  392.04  5516.7  396.27  5560.5  404.75  5686.3  404.57  5720.3  409.89
#Mann=8,-1,0
  4054.5    0.05       0  4559.0    0.04       0  4837.0    0.05       0
  4934.7     0.1       0  4964.4    0.07       0  4977.5     0.1       0
  5302.7    0.12       0  5365.0    0.05       0
#XS Ineff=2,0
    0.00 4859.60  395.00 5200.00    0.00  395.00
Permanent Ineff=
       F       F
Bank Sta=4964.4,4977.5
Exp/Cntr=0.3,0.1

Type RM Length L Ch R = 1,82687,421,421,421
BEGIN DESCRIPTION:
Walnut Creek 116.0
END DESCRIPTION:
XS GIS Cut Line= 3
      2773225.99      6763011.01      2772826.00      6763611.00
      2772478.94      6764195.07
#Sta/Elev= 30
  4273.0  414.81  4430.7  399.19  4638.0  387.01  4643.5  386.79  4770.3  386.38
  4785.3  382.50  4791.3  385.51  4813.8  381.94  4821.3  385.45  4836.4  386.44
  4971.6  387.41  4984.5  380.73  4986.4  380.23  4997.6  380.73  5001.9  380.82
  5007.7  387.51  5023.3  391.36  5052.3  394.18  5097.4  389.98  5118.8  397.04
  5333.1  400.98  5389.6  401.94  5410.7  396.56  5424.5  394.58  5447.8  398.37
  5475.3  394.89  5486.8  397.40  5505.9  402.59  5662.3  406.46  5673.5  406.67
#Mann=9,-1,0
  4273.0    0.12       0  4638.0     0.1       0  4643.5    0.12       0
  4984.5    0.07       0  4997.6    0.12       0  5333.1     0.1       0
  5410.7    0.12       0  5486.8    0.05       0  5662.3   0.075       0
#XS Ineff=2,0
    0.00 4760.00  393.00 5050.00    0.00  395.00
Permanent Ineff=
       F       F
Bank Sta=4984.5,4997.6
Exp/Cntr=0.3,0.1

Type RM Length L Ch R = 1,82266,505,505,505
BEGIN DESCRIPTION:
Walnut Creek 115.0
END DESCRIPTION:
XS GIS Cut Line= 3
      2772960.31      6762867.92      2772465.56      6763462.95
      2772234.88      6763961.08
#Sta/Elev= 30
  4269.9  417.84  4311.1  413.46  4352.7  412.47  4389.2  405.78  4410.0  400.59
  4438.7  399.37  4453.0  397.56  4468.1  394.01  4481.6  391.44  4516.8  389.97
  4716.0  385.51  4942.5  385.26  4985.5  386.34  4992.0  385.80  4999.8  379.90
  5001.6  379.40  5012.9  379.90  5020.6  385.69  5107.7  384.16  5153.5  384.99
  5319.5  389.43  5403.7  394.97  5439.6  394.14  5485.4  396.50  5493.4  394.95
  5508.4  394.67  5525.8  396.56  5531.3  399.76  5537.5  401.53  5592.7  403.87
#Mann=5,-1,0
  4269.9    0.12       0  4468.1     0.1       0  4999.8    0.07       0
  5012.9     0.1       0  5403.7    0.05       0
Bank Sta=4999.8,5012.9
Exp/Cntr=0.3,0.1

Type RM Length L Ch R = 1,81761,407,407,407
BEGIN DESCRIPTION:
Walnut Creek 114.0
END DESCRIPTION:
XS GIS Cut Line= 4
      2772385.34      6762566.98      2772111.20      6763212.22
      2772104.51      6763339.26      2771924.00      6763710.31
#Sta/Elev= 30
  4249.9  413.21  4635.0  394.44  4678.0  391.95  4695.0  389.79  4700.5  390.86
  4718.7  388.27  4724.1  389.79  4742.3  387.84  4747.8  388.80  4764.9  387.27
  4776.8  387.85  4836.5  385.43  4929.6  383.23  4947.6  385.03  4959.8  384.76
  4969.8  383.47  4973.2  378.06  4975.1  377.56  4986.4  378.06  5009.8  384.95
  5033.8  384.11  5049.9  383.14  5271.9  382.53  5345.5  385.45  5413.7  389.79
  5429.7  389.35  5460.1  392.37  5469.3  394.48  5484.5  394.40  5490.8  394.10
#Mann=9,-1,0
  4249.9    0.05       0  4635.0    0.12       0  4836.5     0.1       0
  4973.2    0.07       0  4986.4     0.1       0  5033.8    0.12       0
  5345.5     0.1       0  5460.1    0.12       0  5484.5     0.1       0
Bank Sta=4973.2,4986.4
Exp/Cntr=0.3,0.1

Type RM Length L Ch R = 1,81354,455,455,455
BEGIN DESCRIPTION:
Walnut Creek 113.0
END DESCRIPTION:
XS GIS Cut Line= 3
      2772026.01      6762610.98      2771783.58      6763125.30
      2771580.33      6763528.47
#Sta/Elev= 30
  4361.9  402.98  4406.1  399.37  4421.6  398.98  4461.4  395.64  4472.7  393.94
  4495.5  392.60  4751.6  385.58  4768.9  386.40  4804.1  385.16  4818.1  383.75
  4859.4  382.06  4939.3  382.09  4970.5  382.89  4977.4  376.98  4979.3  376.48
  4990.6  376.98  4992.9  378.83  4998.5  380.53  5000.7  382.22  5023.0  383.25
  5028.6  381.74  5045.3  383.11  5104.9  381.95  5112.2  382.53  5207.0  381.79
  5340.9  382.34  5351.2  384.27  5357.6  389.16  5363.2  390.67  5382.0  392.50
#Mann=4,-1,0
  4361.9    0.05       0  4818.1    0.12       0  4977.4    0.07       0
  4990.6    0.12       0
Bank Sta=4977.4,4990.6
Exp/Cntr=0.3,0.1

Type RM Length L Ch R = 1,80899,445,445,445
BEGIN DESCRIPTION:
Walnut Creek 112.0
END DESCRIPTION:
XS GIS Cut Line= 3
      2772151.30      6762222.70      2771542.88      6762877.92
      2771181.84      6763305.81
#Sta/Elev= 30
  4034.5  415.62  4192.9  404.46  4213.8  404.91  4221.2  399.91  4235.4  397.38
  4249.5  401.76  4256.4  399.41  4287.9  400.69  4325.1  400.58  4504.1  394.43
  4532.4  390.90  4553.4  392.47  4560.8  388.86  4610.1  391.04  4882.8  382.01
  4971.7  382.07  5000.3  376.97  5002.1  376.47  5013.5  376.97  5021.2  382.43
  5027.7  382.71  5212.3  379.73  5269.5  381.93  5283.8  378.44  5318.9  378.47
  5325.5  382.08  5432.1  380.52  5454.1  382.67  5468.4  387.70  5488.5  390.55
#Mann=6,-1,0
  4034.5     0.1       0  4287.9    0.05       0  4325.1    0.12       0
  4882.8    0.05       0  5000.3    0.05       0  5013.5    0.12       0
Bank Sta=5000.3,5013.5
Exp/Cntr=0.3,0.1

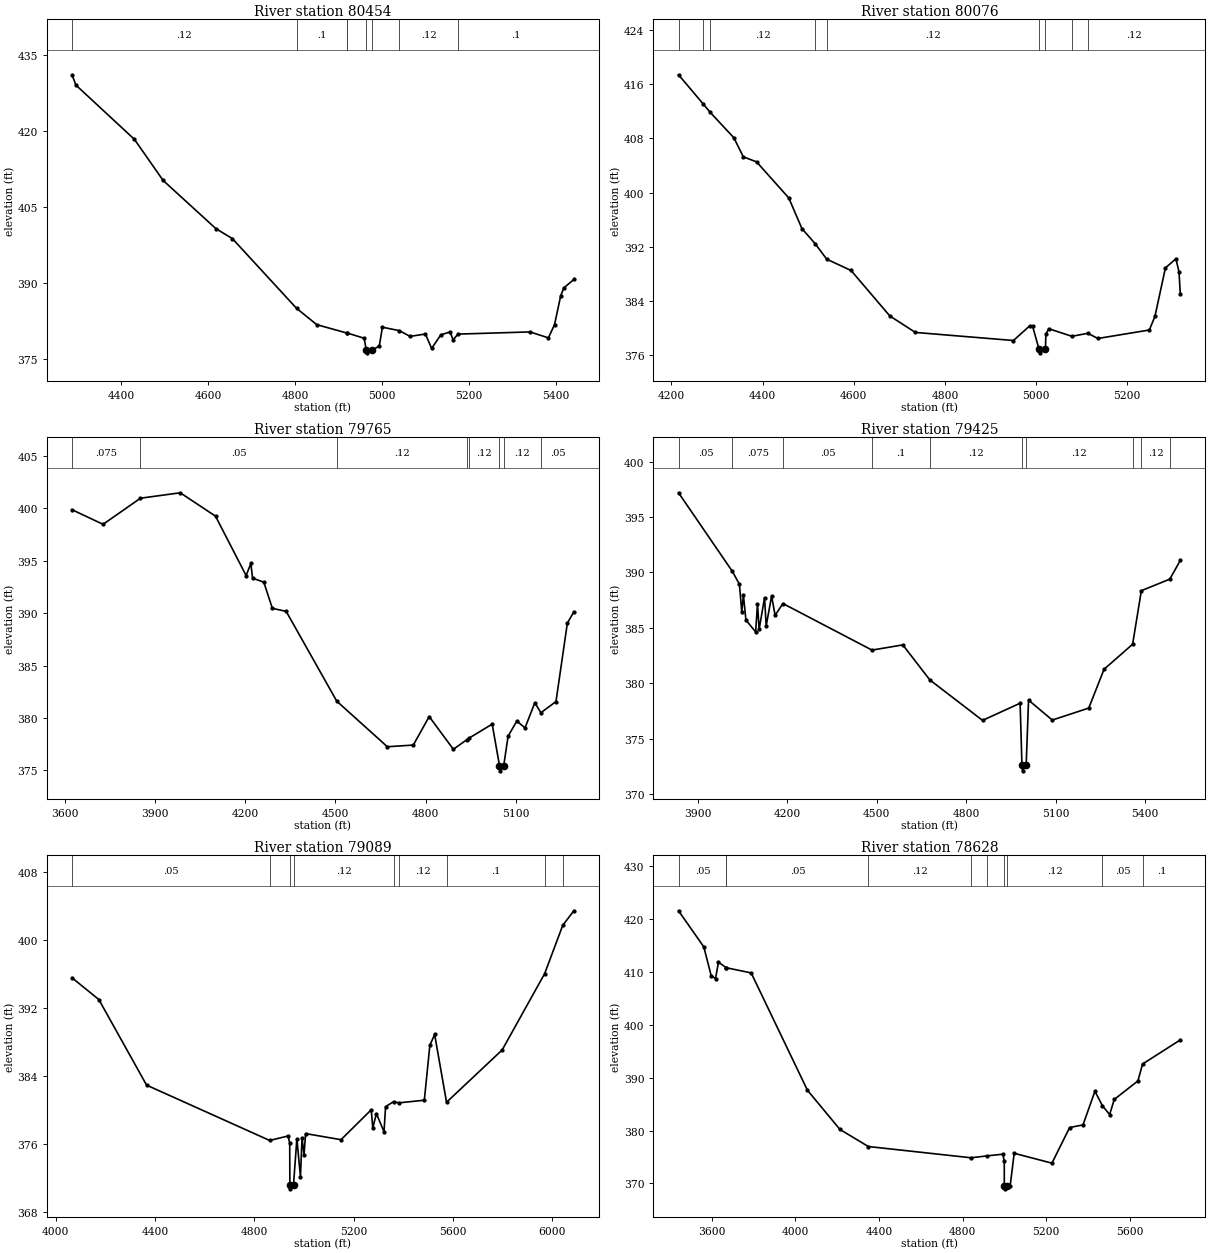
Type RM Length L Ch R = 1,80454,378,378,378
BEGIN DESCRIPTION:
Walnut Creek 111.0
END DESCRIPTION:
XS GIS Cut Line= 3
      2771426.02      6762110.96      2771135.02      6762737.51
      2770807.37      6763065.16
#Sta/Elev= 30
  4286.8  431.03  4295.5  429.01  4430.2  418.31  4496.3  410.21  4617.6  400.72
  4655.5  398.76  4803.1  385.02  4849.7  381.80  4919.4  380.14  4920.0  380.15
  4958.7  379.12  4963.5  376.75  4965.5  376.25  4977.5  376.75  4993.6  377.64
  5000.6  381.30  5039.3  380.63  5064.3  379.49  5099.6  379.96  5113.8  377.12
  5135.0  379.79  5156.2  380.37  5163.3  378.82  5174.6  379.94  5340.0  380.37
  5382.5  379.20  5396.6  381.83  5410.7  387.47  5417.8  389.04  5441.0  390.70
#Mann=8,-1,0
  4286.8    0.12       0  4803.1     0.1       0  4919.4    0.12       0
  4920.0     0.1       0  4963.5    0.07       0  4977.5     0.1       0
  5039.3    0.12       0  5174.6     0.1       0
Bank Sta=4963.5,4977.5
Exp/Cntr=0.3,0.1

Type RM Length L Ch R = 1,80076,311,311,311
BEGIN DESCRIPTION:
Walnut Creek 110.0
END DESCRIPTION:
XS GIS Cut Line= 3
      2771276.03      6762060.96      2770746.49      6762742.62
      2770630.14      6762949.47
#Sta/Elev= 30
  4215.8  417.38  4269.7  413.09  4285.3  411.83  4337.1  408.09  4357.9  405.27
  4386.9  404.53  4457.5  399.21  4486.4  394.69  4515.5  392.45  4540.8  390.17
  4594.2  388.50  4679.2  381.79  4735.3  379.36  4950.3  378.17  4986.0  380.33
  4992.4  380.24  5006.6  376.85  5008.6  376.35  5020.6  376.85  5021.3  379.07
  5027.7  379.91  5078.5  378.79  5113.3  379.23  5135.6  378.47  5248.4  379.72
  5260.7  381.75  5283.6  388.88  5306.6  390.23  5313.4  388.29  5316.3  385.01
#Mann=9,-1,0
  4215.8    0.12       0  4269.7    0.05       0  4285.3    0.12       0
  4515.5    0.05       0  4540.8    0.12       0  5006.6    0.07       0
  5020.6    0.12       0  5078.5     0.1       0  5113.3    0.12       0
Bank Sta=5006.6,5020.6
Exp/Cntr=0.3,0.1

Type RM Length L Ch R = 1,79765,340,340,340
BEGIN DESCRIPTION:
Walnut Creek 109.5
END DESCRIPTION:
XS GIS Cut Line= 3
      2771232.58      6761336.41      2770494.76      6762599.39
      2770433.98      6762794.75
#Sta/Elev= 30
  3624.7  399.88  3727.7  398.49  3851.9  400.98  3984.0  401.50  4101.3  399.27
  4203.0  393.60  4218.7  394.75  4224.5  393.35  4261.7  392.97  4290.2  390.47
  4336.1  390.18  4504.2  381.61  4672.3  377.26  4758.5  377.42  4811.3  380.14
  4891.6  377.02  4936.9  377.94  4943.1  378.07  5020.6  379.42  5044.9  375.46
  5046.9  374.96  5059.0  375.46  5073.5  378.27  5102.4  379.71  5129.7  379.06
  5162.3  381.46  5182.5  380.51  5232.6  381.57  5270.4  389.06  5292.0  390.13
#Mann=8,-1,0
  3624.7   0.075       0  3851.9    0.05       0  4504.2    0.12       0
  4936.9   0.075       0  4943.1    0.12       0  5044.9    0.07       0
  5059.0    0.12       0  5182.5    0.05       0
Bank Sta=5044.9,5059
Exp/Cntr=0.3,0.1

Type RM Length L Ch R = 1,79425,336,336,336
BEGIN DESCRIPTION:
Walnut Creek 109.0
END DESCRIPTION:
XS GIS Cut Line= 3
      2770854.98      6761193.18      2770433.99      6762182.72
      2770100.39      6762689.62
#Sta/Elev= 30
  3835.4  397.18  4016.1  390.08  4039.5  388.93  4047.4  386.42  4052.9  387.96
  4061.3  385.70  4093.9  384.63  4100.1  387.15  4105.6  384.86  4123.8  387.72
  4129.2  385.17  4147.4  387.87  4159.1  386.13  4185.4  387.19  4483.9  382.99
  4587.3  383.46  4677.9  380.30  4854.6  376.65  4980.5  378.20  4986.7  372.60
  4988.7  372.10  5000.8  372.60  5008.8  378.48  5088.3  376.68  5210.6  377.76
  5261.9  381.26  5357.7  383.52  5386.9  388.35  5482.3  389.39  5517.6  391.08
#Mann=10,-1,0
  3835.4    0.05       0  4016.1   0.075       0  4185.4    0.05       0
  4483.9     0.1       0  4677.9    0.12       0  4986.7    0.07       0
  5000.8    0.12       0  5357.7   0.075       0  5386.9    0.12       0
  5482.3     0.1       0
Bank Sta=4986.7,5000.8
Exp/Cntr=0.3,0.1

Type RM Length L Ch R = 1,79089,461,461,461
BEGIN DESCRIPTION:
Walnut Creek 108.0
END DESCRIPTION:
XS GIS Cut Line= 3
      2770785.55      6761258.25      2770017.32      6762221.79
      2769800.65      6762980.13
#Sta/Elev= 30
  4066.2  395.59  4174.1  393.03  4366.3  382.95  4862.0  376.43  4936.4  376.96
  4942.8  376.10  4943.4  371.23  4945.4  370.73  4958.1  371.23  4971.6  376.63
  4986.0  372.15  4992.4  376.73  5000.4  374.75  5006.8  377.24  5149.3  376.52
  5271.1  380.04  5277.4  377.90  5291.9  379.59  5322.6  377.46  5328.9  380.42
  5361.3  381.00  5382.3  380.86  5484.9  381.17  5507.2  387.64  5526.5  388.92
  5574.4  380.93  5798.4  387.09  5969.7  396.09  6042.5  401.78  6087.2  403.49
#Mann=9,-1,0
  4066.2    0.05       0  4862.0    0.12       0  4943.4    0.07       0
  4958.1    0.12       0  5361.3    0.05       0  5382.3    0.12       0
  5574.4     0.1       0  5969.7    0.12       0  6042.5     0.1       0
Bank Sta=4943.4,4958.1
Exp/Cntr=0.3,0.1

Type RM Length L Ch R = 1,78628,471,471,471
BEGIN DESCRIPTION:
Walnut Creek 107.0
END DESCRIPTION:
XS GIS Cut Line= 3
      2770976.01      6760760.99      2769780.00      6761832.26
      2769271.40      6762441.81
#Sta/Elev= 30
  3441.6  421.60  3562.4  414.77  3597.5  409.34  3618.4  408.76  3632.6  411.87
  3669.8  410.82  3670.6  410.81  3788.9  409.84  4058.0  387.63  4213.5  380.21
  4349.2  376.98  4840.4  374.85  4917.3  375.21  4992.5  375.53  4999.2  374.20
  4999.4  369.47  5001.4  368.97  5014.1  369.47  5027.7  369.60  5046.6  375.70
  5227.2  373.83  5311.8  380.58  5375.6  381.07  5432.8  387.44  5468.7  384.69
  5503.1  383.03  5525.2  385.90  5638.5  389.40  5660.3  392.59  5841.1  397.16
#Mann=10,-1,0
  3441.6    0.05       0  3669.8   0.075       0  3670.6    0.05       0
  4349.2    0.12       0  4840.4     0.1       0  4917.3    0.12       0
  4999.4    0.07       0  5014.1    0.12       0  5468.7    0.05       0
  5660.3     0.1       0
Bank Sta=4999.4,5014.1
Exp/Cntr=0.3,0.1

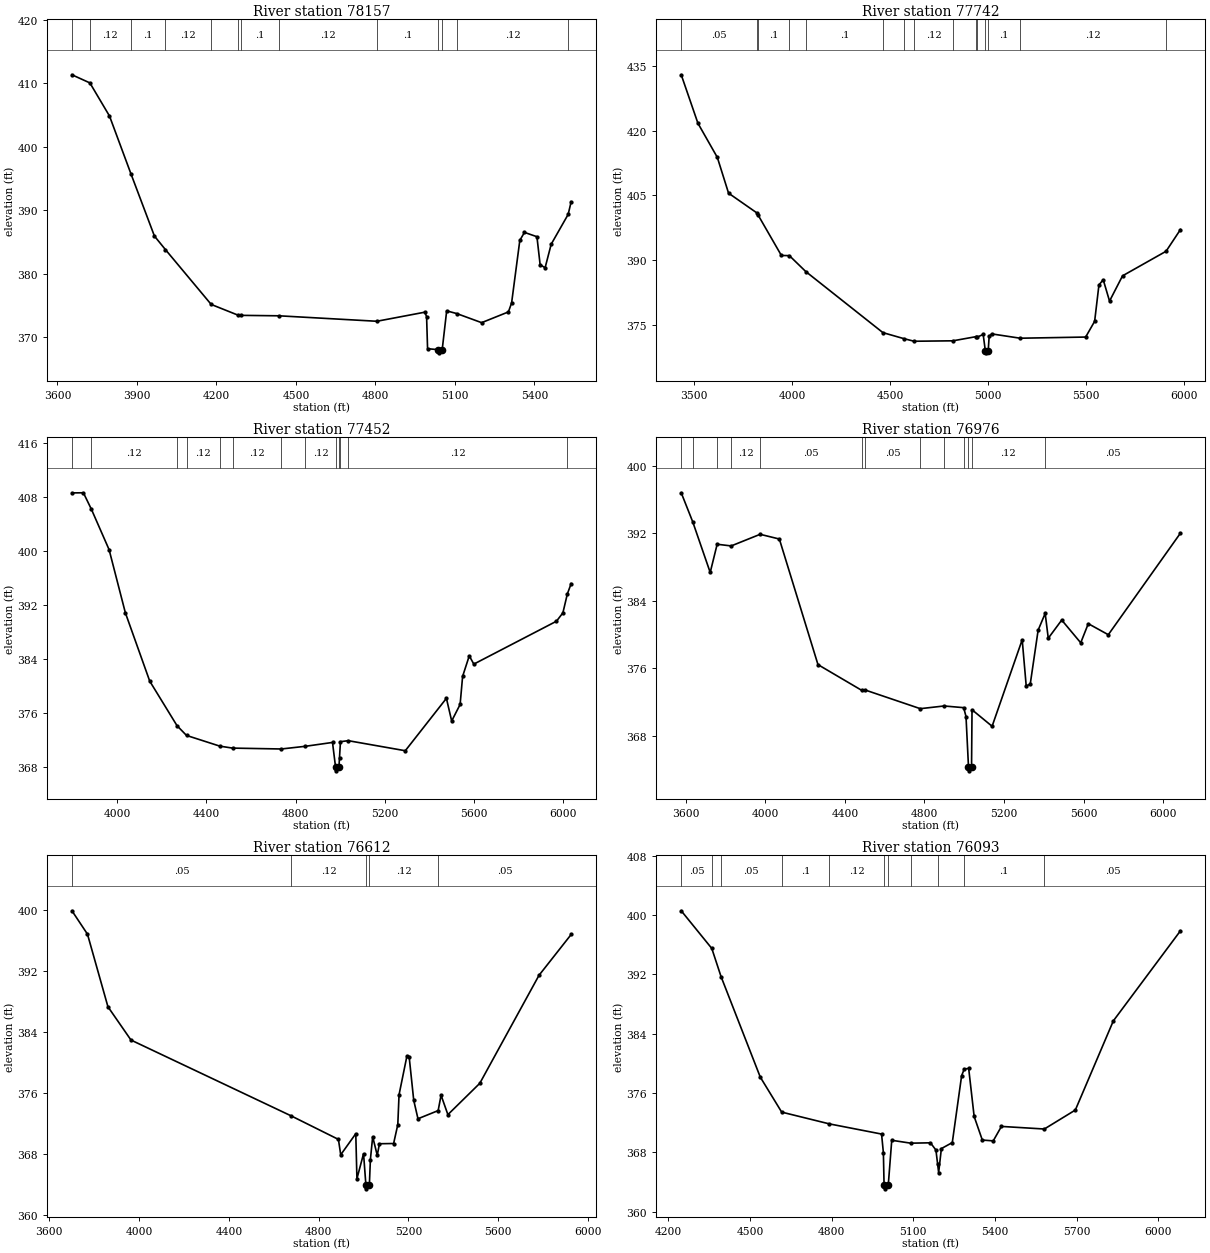
Type RM Length L Ch R = 1,78157,415,415,415
BEGIN DESCRIPTION:
Walnut Creek 106.0
END DESCRIPTION:
XS GIS Cut Line= 3
      2770476.03      6760760.97      2769476.00      6761661.00
      2769276.01      6762160.98
#Sta/Elev= 30
  3654.5  411.30  3722.2  410.02  3796.2  404.81  3876.8  395.75  3965.8  385.91
  4007.5  383.77  4180.0  375.15  4282.0  373.45  4292.9  373.43  4435.5  373.36
  4805.2  372.50  4986.1  373.93  4992.8  373.24  4996.5  368.18  5037.0  368.03
  5039.0  367.53  5051.7  368.03  5068.6  374.14  5106.8  373.71  5200.5  372.28
  5301.5  373.97  5313.6  375.38  5344.6  385.23  5362.1  386.49  5409.2  385.81
  5421.3  381.39  5440.1  380.93  5463.0  384.63  5527.0  389.32  5538.4  391.32
#Mann=13,-1,0
  3654.5    0.05       0  3722.2    0.12       0  3876.8     0.1       0
  4007.5    0.12       0  4180.0     0.1       0  4282.0    0.12       0
  4292.9     0.1       0  4435.5    0.12       0  4805.2     0.1       0
  5037.0    0.07       0  5051.7     0.1       0  5106.8    0.12       0
  5527.0    0.05       0
Bank Sta=5037,5051.7
Exp/Cntr=0.3,0.1

Type RM Length L Ch R = 1,77742,290,290,290
BEGIN DESCRIPTION:
Walnut Creek 105.0
END DESCRIPTION:
XS GIS Cut Line= 3
      2770376.02      6760110.97      2769376.00      6761311.00
      2768975.99      6762211.02
#Sta/Elev= 30
  3433.8  432.89  3519.1  421.67  3618.0  413.79  3675.3  405.52  3821.6  400.90
  3826.4  400.43  3944.8  391.12  3985.5  391.08  4069.8  387.38  4462.8  373.28
  4569.9  371.89  4621.9  371.29  4820.0  371.39  4940.1  372.37  4945.0  372.28
  4974.4  372.85  4985.2  369.11  4987.2  368.61  5000.0  369.11  5004.8  372.40
  5017.8  372.99  5163.0  371.99  5497.2  372.26  5543.0  375.90  5564.9  384.30
  5586.8  385.51  5619.0  380.57  5685.3  386.41  5907.4  392.09  5980.8  397.11
#Mann=15,-1,0
  3433.8    0.05       0  3821.6    0.12       0  3826.4     0.1       0
  3985.5    0.05       0  4069.8     0.1       0  4462.8    0.12       0
  4569.9     0.1       0  4621.9    0.12       0  4820.0     0.1       0
  4940.1    0.05       0  4945.0     0.1       0  4985.2    0.07       0
  5000.0     0.1       0  5163.0    0.12       0  5907.4    0.05       0
Bank Sta=4985.2,5000
Exp/Cntr=0.3,0.1

Type RM Length L Ch R = 1,77452,476,476,476
BEGIN DESCRIPTION:
Walnut Creek 104.0
END DESCRIPTION:
XS GIS Cut Line= 3
      2769780.00      6760155.01      2769038.44      6761323.66
      2768856.22      6762157.20
#Sta/Elev= 30
  3797.2  408.62  3848.5  408.64  3884.5  406.19  3963.7  400.21  4036.6  390.85
  4145.9  380.71  4268.2  374.11  4310.6  372.67  4460.1  371.08  4516.8  370.79
  4735.5  370.66  4843.8  371.06  4964.9  371.63  4978.8  367.92  4980.8  367.42
  4993.7  367.92  4996.3  369.38  5000.5  371.74  5035.6  371.89  5291.1  370.40
  5475.4  378.17  5499.0  374.81  5536.8  377.26  5548.0  381.42  5577.8  384.47
  5598.2  383.24  5968.6  389.60  5997.4  390.84  6017.4  393.65  6034.5  395.18
#Mann=13,-1,0
  3797.2    0.05       0  3884.5    0.12       0  4268.2     0.1       0
  4310.6    0.12       0  4460.1     0.1       0  4516.8    0.12       0
  4735.5    0.05       0  4843.8    0.12       0  4978.8    0.07       0
  4993.7    0.12       0  4996.3     0.1       0  5035.6    0.12       0
  6017.4    0.05       0
Bank Sta=4978.8,4993.7
Exp/Cntr=0.3,0.1

Type RM Length L Ch R = 1,76976,364,364,364
BEGIN DESCRIPTION:
Walnut Creek 103.0
END DESCRIPTION:
XS GIS Cut Line= 4
      2769267.51      6759825.00      2768813.25      6761009.17
      2768743.89      6761534.88      2768665.22      6762241.44
#Sta/Elev= 30
  3577.4  396.83  3635.4  393.37  3723.1  387.37  3758.0  390.72  3828.6  390.52
  3974.1  391.90  4070.7  391.34  4264.8  376.43  4485.8  373.36  4501.5  373.42
  4779.1  371.20  4898.7  371.52  4997.2  371.32  5008.9  370.27  5021.4  364.32
  5023.4  363.82  5036.8  364.32  5039.2  371.07  5140.1  369.11  5291.4  379.38
  5311.5  373.91  5331.7  374.10  5371.5  380.52  5406.9  382.51  5422.4  379.56
  5490.1  381.72  5585.6  379.02  5623.6  381.29  5724.2  379.98  6086.9  392.04
#Mann=13,-1,0
  3577.4    0.05       0  3635.4    0.12       0  3758.0    0.05       0
  3828.6    0.12       0  3974.1    0.05       0  4485.8     0.1       0
  4501.5    0.05       0  4779.1    0.12       0  4898.7     0.1       0
  4997.2    0.12       0  5021.4    0.07       0  5036.8    0.12       0
  5406.9    0.05       0
Bank Sta=5021.4,5036.8
Exp/Cntr=0.3,0.1

Type RM Length L Ch R = 1,76612,519,519,519
BEGIN DESCRIPTION:
Walnut Creek 102.0
END DESCRIPTION:
XS GIS Cut Line= 4
      2768786.07      6759894.94      2768525.95      6760993.64
      2768465.89      6761317.04      2768335.35      6762072.24
#Sta/Elev= 30
  3700.6  399.90  3769.8  396.83  3861.0  387.30  3963.7  382.93  4677.2  372.98
  4888.0  369.89  4898.2  367.87  4965.3  370.64  4970.4  364.73  4999.9  368.01
  5010.4  363.90  5012.4  363.40  5025.8  363.90  5030.4  367.24  5040.6  370.24
  5060.9  367.81  5070.9  369.32  5133.9  369.35  5152.5  371.83  5158.1  375.76
  5193.1  380.82  5203.2  380.71  5223.5  375.02  5242.4  372.60  5332.3  373.67
  5345.3  375.69  5375.7  373.14  5517.8  377.25  5781.7  391.43  5925.0  396.79
#Mann=5,-1,0
  3700.6    0.05       0  4677.2    0.12       0  5010.4    0.07       0
  5025.8    0.12       0  5332.3    0.05       0
Bank Sta=5010.4,5025.8
Exp/Cntr=0.3,0.1

Type RM Length L Ch R = 1,76093,482,482,482
BEGIN DESCRIPTION:
Walnut Creek 101.0
END DESCRIPTION:
XS GIS Cut Line= 3
      2768370.65      6760123.96      2768192.05      6760982.00
      2768122.73      6761936.86
#Sta/Elev= 30
  4247.7  400.57  4360.0  395.49  4393.9  391.70  4538.1  378.13  4616.7  373.41
  4792.1  371.82  4983.6  370.45  4990.3  367.93  4992.8  363.56  4994.8  363.06
  5008.2  363.56  5021.0  369.61  5090.8  369.22  5163.2  369.27  5183.3  368.29
  5189.3  366.47  5193.3  365.25  5203.3  368.49  5243.4  369.30  5277.7  378.33
  5287.4  379.22  5303.6  379.30  5323.7  372.82  5353.7  369.64  5393.8  369.53
  5423.9  371.48  5581.5  371.13  5695.4  373.69  5835.0  385.72  6081.5  397.87
#Mann=11,-1,0
  4247.7    0.05       0  4360.0    0.12       0  4393.9    0.05       0
  4616.7     0.1       0  4792.1    0.12       0  4992.8    0.07       0
  5008.2    0.12       0  5090.8     0.1       0  5189.3    0.12       0
  5287.4     0.1       0  5581.5    0.05       0
Bank Sta=4992.8,5008.2
Exp/Cntr=0.3,0.1

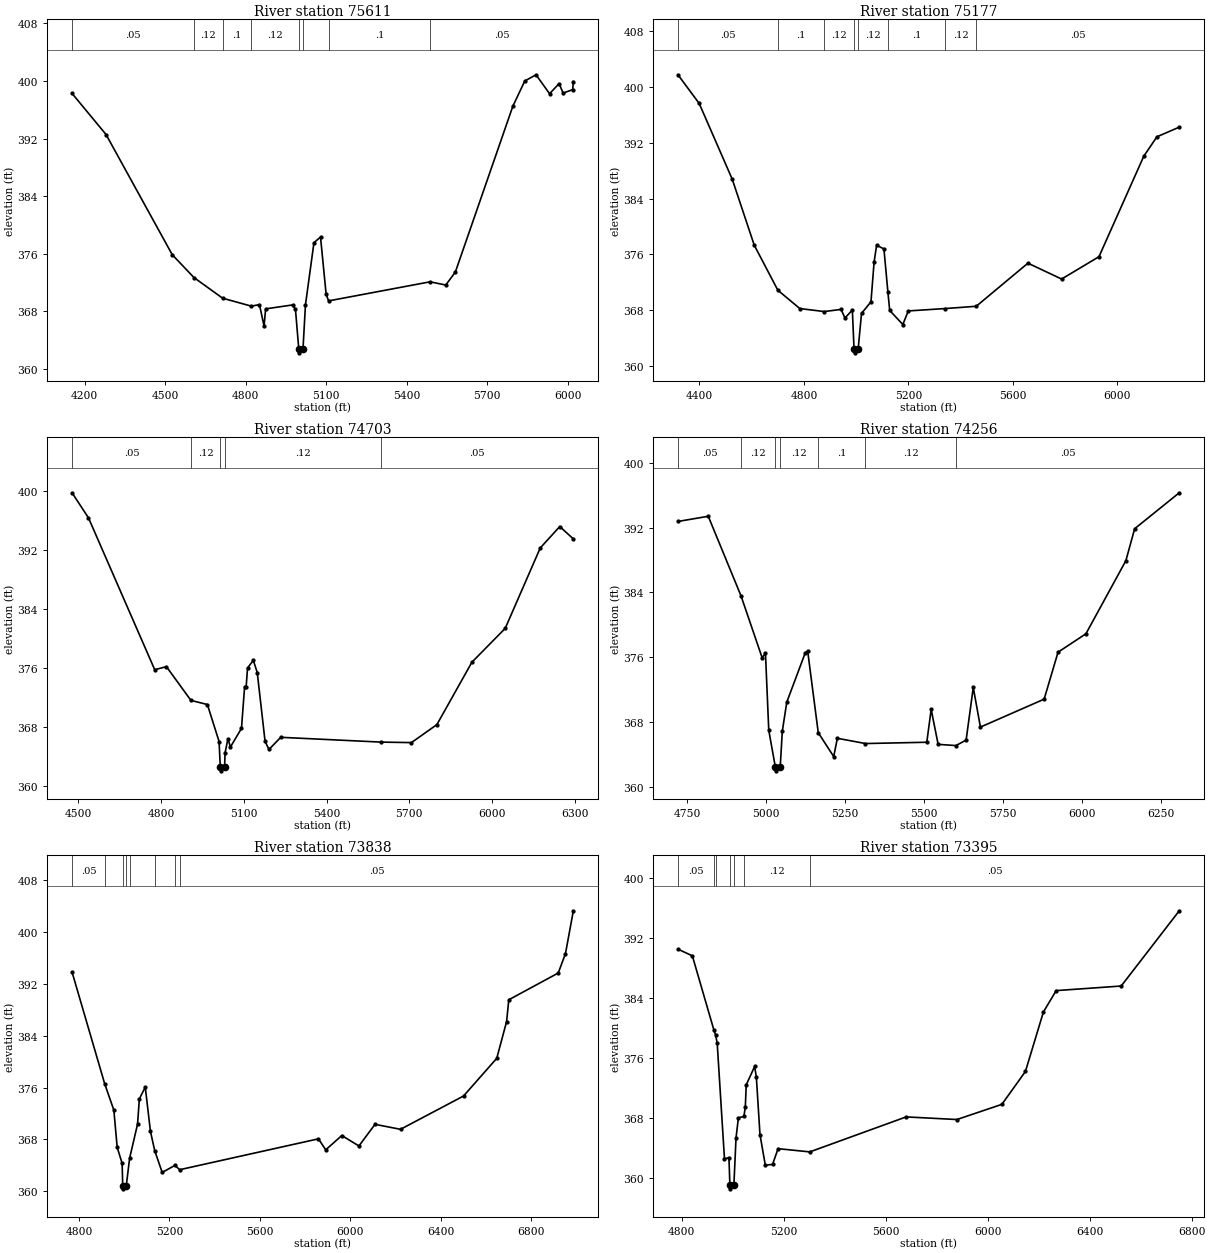
Type RM Length L Ch R = 1,75611,434,434,434
BEGIN DESCRIPTION:
Walnut Creek 100.0
END DESCRIPTION:
XS GIS Cut Line= 4
      2768164.88      6760042.43      2767834.86      6760752.93
      2767815.82      6760871.87      2767259.99      6761658.43
#Sta/Elev= 30
  4153.2  398.28  4279.8  392.57  4526.5  375.86  4607.3  372.69  4714.1  369.82
  4820.9  368.72  4851.3  368.93  4868.3  365.94  4874.2  368.34  4975.2  368.89
  4985.3  368.27  4997.7  362.73  4999.7  362.23  5013.3  362.73  5022.5  368.89
  5054.1  377.53  5078.6  378.33  5099.5  370.36  5108.7  369.45  5486.7  372.10
  5545.1  371.65  5580.8  373.46  5795.0  396.51  5839.4  400.01  5881.2  400.87
  5931.7  398.24  5967.3  399.65  5982.1  398.32  6017.8  398.81  6020.2  399.93
#Mann=8,-1,0
  4153.2    0.05       0  4607.3    0.12       0  4714.1     0.1       0
  4820.9    0.12       0  4997.7    0.07       0  5013.3    0.12       0
  5108.7     0.1       0  5486.7    0.05       0
Bank Sta=4997.7,5013.3
Exp/Cntr=0.3,0.1

Type RM Length L Ch R = 1,75177,474,474,474
BEGIN DESCRIPTION:
Walnut Creek 99.0
END DESCRIPTION:
XS GIS Cut Line= 4
      2767768.70      6759933.84      2767568.71      6760533.82
      2767476.60      6760612.87      2766790.59      6761555.20
#Sta/Elev= 30
  4317.7  401.78  4399.0  397.66  4525.5  386.78  4609.8  377.30  4700.2  370.83
  4784.3  368.20  4877.9  367.77  4942.4  368.08  4956.9  366.84  4985.4  367.99
  4991.9  362.34  4993.9  361.84  5007.5  362.34  5020.5  367.50  5056.7  369.17
  5068.6  374.85  5078.2  377.29  5106.3  376.77  5121.4  370.61  5128.4  367.93
  5178.7  365.91  5199.5  367.86  5340.7  368.20  5459.8  368.53  5657.7  374.72
  5786.6  372.44  5929.7  375.65  6101.2  390.08  6151.5  392.87  6237.1  394.26
#Mann=8,-1,0
  4317.7    0.05       0  4700.2     0.1       0  4877.9    0.12       0
  4991.9    0.07       0  5007.5    0.12       0  5121.4     0.1       0
  5340.7    0.12       0  5459.8    0.05       0
Bank Sta=4991.9,5007.5
Exp/Cntr=0.3,0.1

Type RM Length L Ch R = 1,74703,447,447,447
BEGIN DESCRIPTION:
Walnut Creek 98.0
END DESCRIPTION:
XS GIS Cut Line= 4
      2767535.89      6759887.15      2767159.31      6760283.14
      2767137.80      6760363.03      2766325.79      6761230.21
#Sta/Elev= 30
  4477.6  399.79  4537.0  396.40  4777.3  375.78  4819.7  376.20  4908.5  371.62
  4968.2  371.06  5010.6  366.04  5015.0  362.56  5017.0  362.06  5030.6  362.56
  5032.2  364.49  5042.6  366.38  5051.9  365.30  5091.8  367.82  5103.2  373.50
  5108.8  373.50  5113.8  376.02  5134.8  377.05  5149.0  375.39  5177.3  366.06
  5191.5  364.96  5234.0  366.61  5597.4  365.96  5707.8  365.89  5800.1  368.33
  5927.1  376.80  6047.8  381.39  6174.8  392.30  6245.6  395.21  6294.8  393.53
#Mann=5,-1,0
  4477.6    0.05       0  4908.5    0.12       0  5015.0    0.07       0
  5030.6    0.12       0  5597.4    0.05       0
Bank Sta=5015,5030.6
Exp/Cntr=0.3,0.1

Type RM Length L Ch R = 1,74256,418,418,418
BEGIN DESCRIPTION:
Walnut Creek 97.0
END DESCRIPTION:
XS GIS Cut Line= 4
      2767042.79      6759844.45      2766826.00      6760011.00
      2766747.35      6760079.00      2766183.01      6761146.90
#Sta/Elev= 30
  4721.6  392.75  4817.4  393.39  4920.8  383.58  4987.7  375.93  4998.3  376.46
  5008.7  366.97  5029.4  362.46  5031.4  361.96  5045.0  362.46  5051.5  366.84
  5065.7  370.44  5123.8  376.50  5131.7  376.77  5165.2  366.67  5214.1  363.72
  5225.6  365.98  5314.6  365.33  5508.4  365.49  5522.3  369.54  5544.3  365.23
  5600.7  365.08  5632.8  365.76  5655.4  372.25  5678.0  367.36  5879.5  370.81
  5923.5  376.61  6011.6  378.88  6138.0  387.91  6165.7  391.85  6306.8  396.29
#Mann=7,-1,0
  4721.6    0.05       0  4920.8    0.12       0  5029.4    0.07       0
  5045.0    0.12       0  5165.2     0.1       0  5314.6    0.12       0
  5600.7    0.05       0
Bank Sta=5029.4,5045
Exp/Cntr=0.3,0.1

Type RM Length L Ch R = 1,73838,443,443,443
BEGIN DESCRIPTION:
Walnut Creek 96.0
END DESCRIPTION:
XS GIS Cut Line= 4
      2766600.21      6759611.49      2766476.00      6759811.00
      2766448.88      6759870.06      2765527.18      6761551.39
#Sta/Elev= 30
  4769.4  393.83  4913.9  376.57  4954.3  372.51  4969.1  366.76  4990.9  364.31
  4993.6  360.86  4995.6  360.36  5009.3  360.86  5024.1  365.09  5059.1  370.34
  5067.2  374.25  5093.3  376.07  5116.1  369.25  5135.0  366.26  5168.2  362.89
  5224.9  363.99  5245.2  363.31  5859.3  368.08  5891.5  366.38  5962.6  368.59
  6038.4  366.98  6109.5  370.32  6222.3  369.55  6501.0  374.69  6648.0  380.51
  6691.6  386.19  6701.3  389.55  6920.0  393.68  6952.1  396.69  6986.8  403.29
#Mann=8,-1,0
  4769.4    0.05       0  4913.9    0.12       0  4993.6    0.07       0
  5009.3    0.12       0  5024.1    0.12       0  5135.0     0.1       0
  5224.9    0.12       0  5245.2    0.05       0
Bank Sta=4993.6,5009.3
Exp/Cntr=0.3,0.1

Type RM Length L Ch R = 1,73395,588,588,588
BEGIN DESCRIPTION:
Walnut Creek 95.0
END DESCRIPTION:
XS GIS Cut Line= 4
      2766320.66      6759471.71      2766126.00      6759561.00
      2766097.12      6759606.23      2764962.92      6760869.99
#Sta/Elev= 30
  4785.6  390.51  4842.0  389.62  4926.4  379.75  4933.1  379.09  4939.5  377.97
  4968.0  362.58  4985.5  362.75  4989.2  359.09  4991.2  358.59  5004.9  359.09
  5013.3  365.37  5022.6  368.05  5044.0  368.23  5049.7  369.46  5053.3  372.44
  5086.3  374.89  5093.0  373.47  5107.2  365.82  5128.1  361.74  5156.5  361.84
  5178.2  363.94  5302.6  363.51  5680.5  368.17  5879.4  367.82  6055.8  369.84
  6148.2  374.22  6218.8  382.15  6268.9  384.99  6523.8  385.60  6751.5  395.62
#Mann=7,-1,0
  4785.6    0.05       0  4926.4    0.12       0  4933.1    0.05       0
  4989.2    0.05       0  5004.9    0.05       0  5044.0    0.12       0
  5302.6    0.05       0
Bank Sta=4989.2,5004.9
Exp/Cntr=0.3,0.1

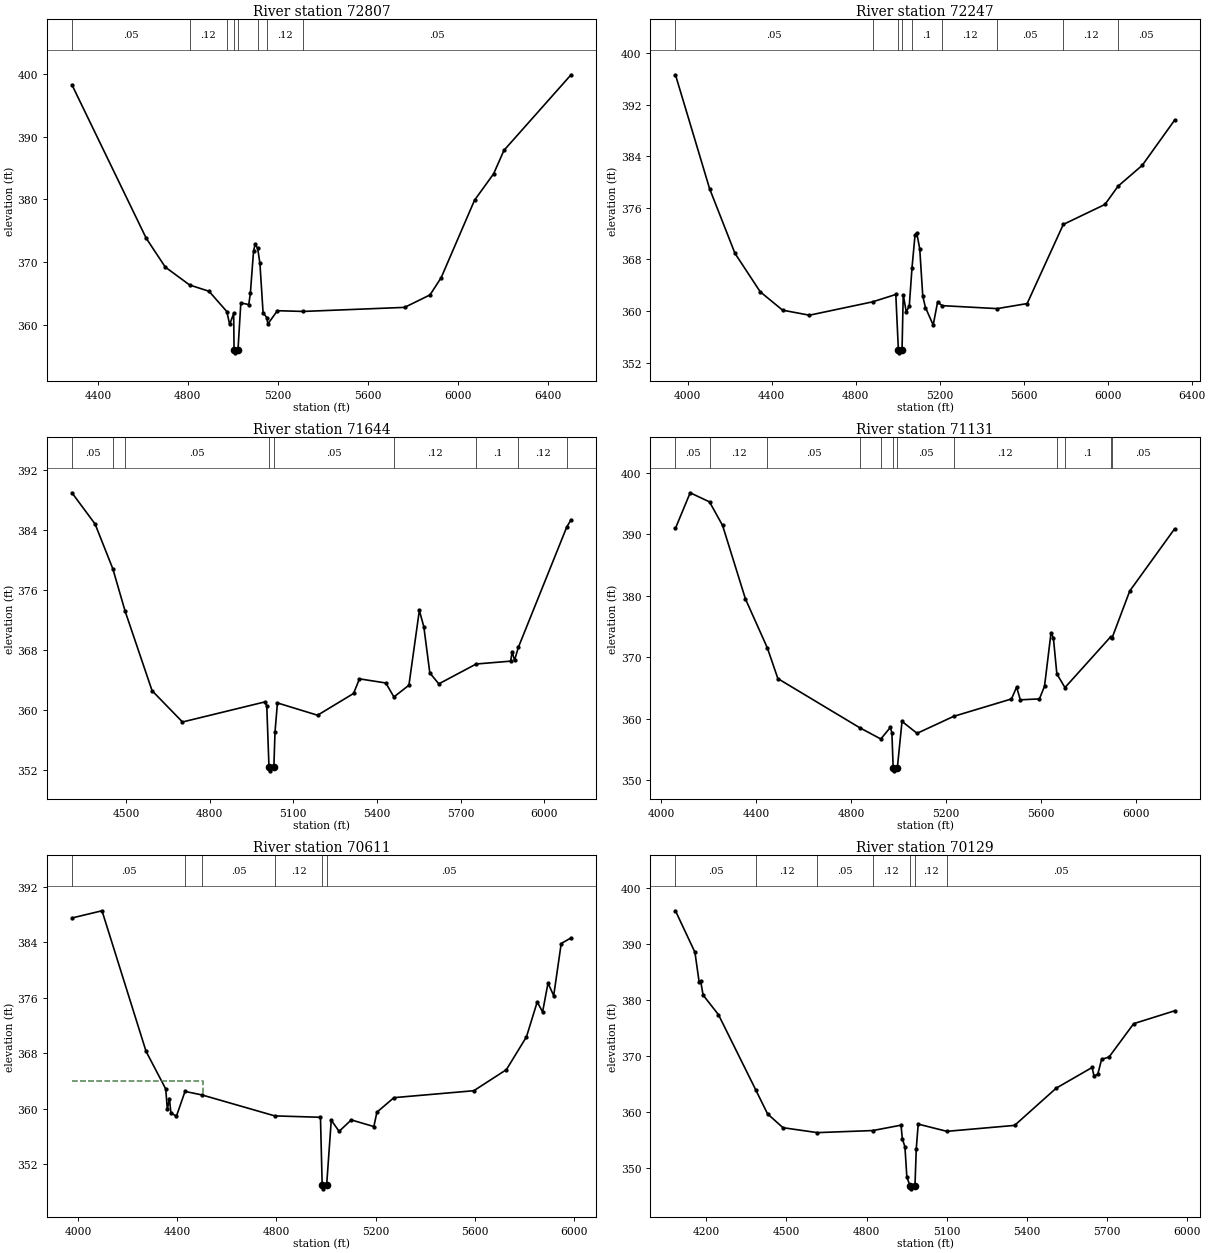
Type RM Length L Ch R = 1,72807,560,560,560
BEGIN DESCRIPTION:
Walnut Creek 94.0
END DESCRIPTION:
XS GIS Cut Line= 4
      2766326.03      6758910.98      2765676.00      6759211.00
      2764837.23      6760081.07      2764721.09      6760353.04
#Sta/Elev= 30
  4284.3  398.29  4614.7  373.79  4699.6  369.18  4808.1  366.32  4894.2  365.32
  4973.1  362.09  4986.0  360.02  5003.7  361.78  5005.5  355.99  5007.5  355.49
  5023.0  355.99  5035.6  363.46  5070.8  363.20  5078.0  365.00  5092.2  371.75
  5099.1  372.81  5110.5  372.17  5120.5  369.79  5134.6  361.87  5151.3  361.12
  5155.7  360.09  5198.2  362.22  5312.9  362.10  5764.2  362.75  5877.1  364.74
  5926.7  367.49  6075.2  379.86  6160.1  384.08  6206.0  387.82  6504.5  399.89
#Mann=8,-1,0
  4284.3    0.05       0  4808.1    0.12       0  4973.1     0.1       0
  5005.5    0.07       0  5023.0     0.1       0  5110.5     0.1       0
  5151.3    0.12       0  5312.9    0.05       0
Bank Sta=5005.5,5023
Exp/Cntr=0.3,0.1

Type RM Length L Ch R = 1,72247,603,603,603
BEGIN DESCRIPTION:
Walnut Creek 93.0
END DESCRIPTION:
XS GIS Cut Line= 3
      2765926.03      6758110.96      2765226.00      6758911.00
      2764194.65      6759724.61
#Sta/Elev= 30
  3941.6  396.61  4104.4  378.95  4225.0  368.95  4345.5  362.99  4451.8  360.15
  4579.5  359.37  4880.5  361.44  4990.9  362.58  5003.1  354.04  5005.1  353.54
  5020.6  354.04  5026.3  362.54  5040.8  359.85  5055.2  360.83  5068.1  366.74
  5082.4  371.77  5090.5  372.13  5104.9  369.65  5119.3  362.32  5132.1  360.56
  5169.0  357.85  5189.8  361.39  5211.8  360.85  5473.4  360.39  5616.3  361.17
  5788.5  373.43  5986.6  376.52  6049.5  379.36  6164.6  382.59  6318.3  389.57
#Mann=9,-1,0
  3941.6    0.05       0  4880.5    0.12       0  5003.1    0.07       0
  5020.6    0.12       0  5068.1     0.1       0  5211.8    0.12       0
  5473.4    0.05       0  5788.5    0.12       0  6049.5    0.05       0
Bank Sta=5003.1,5020.6
Exp/Cntr=0.3,0.1

Type RM Length L Ch R = 1,71644,513,513,513
BEGIN DESCRIPTION:
Walnut Creek 92.0
END DESCRIPTION:
XS GIS Cut Line= 4
      2765727.44      6758039.12      2765181.97      6758361.45
      2765070.40      6758406.90      2764082.70      6758720.98
#Sta/Elev= 30
  4306.0  388.90  4389.0  384.74  4452.8  378.76  4496.6  373.14  4593.5  362.52
  4702.6  358.35  4999.6  361.04  5005.0  360.43  5012.9  352.34  5014.9  351.84
  5030.4  352.34  5034.5  357.02  5043.2  360.89  5187.2  359.25  5316.2  362.15
  5337.5  364.10  5431.9  363.55  5461.1  361.69  5514.9  363.25  5552.3  373.22
  5568.4  371.04  5589.8  364.90  5622.1  363.43  5756.3  366.08  5880.0  366.46
  5885.2  367.73  5893.7  366.57  5907.7  368.32  6081.3  384.35  6096.5  385.30
#Mann=9,-1,0
  4306.0    0.05       0  4452.8    0.12       0  4496.6    0.05       0
  5012.9    0.04       0  5030.4    0.05       0  5461.1    0.12       0
  5756.3     0.1       0  5907.7    0.12       0  6081.3    0.05       0
Bank Sta=5012.9,5030.4
Exp/Cntr=0.3,0.1

Type RM Length L Ch R = 1,71131,520,520,520
BEGIN DESCRIPTION:
Walnut Creek 91.0
END DESCRIPTION:
XS GIS Cut Line= 4
      2765739.83      6757643.23      2764925.76      6757973.81
      2764709.16      6758174.46      2763905.05      6758639.13
#Sta/Elev= 30
  4059.8  390.98  4121.8  396.76  4203.3  395.28  4258.4  391.44  4354.7  379.49
  4447.0  371.53  4491.3  366.54  4836.1  358.55  4925.0  356.72  4964.8  358.59
  4971.6  357.75  4977.0  352.04  4979.0  351.54  4994.6  352.04  5014.2  359.58
  5077.7  357.64  5231.8  360.40  5475.4  363.23  5496.9  365.15  5512.7  363.09
  5593.1  363.24  5614.6  365.29  5641.9  373.97  5651.9  373.18  5666.5  367.31
  5700.7  365.08  5893.2  373.34  5899.2  373.16  5973.5  380.78  6162.4  390.89
#Mann=12,-1,0
  4059.8    0.05       0  4203.3    0.12       0  4447.0    0.05       0
  4836.1    0.12       0  4925.0    0.05       0  4977.0    0.03       0
  4994.6    0.05       0  5231.8    0.12       0  5666.5    0.05       0
  5700.7     0.1       0  5893.2    0.12       0  5899.2    0.05       0
Bank Sta=4977,4994.6
Exp/Cntr=0.3,0.1

Type RM Length L Ch R = 1,70611,482,482,482
BEGIN DESCRIPTION:
Walnut Creek 90.0
END DESCRIPTION:
XS GIS Cut Line= 3
      2765475.42      6756981.98      2764727.39      6757531.63
      2763785.20      6758064.71
#Sta/Elev= 30
  3975.9  387.50  4097.0  388.54  4274.5  368.27  4353.9  362.83  4360.2  359.91
  4368.6  361.46  4374.8  359.34  4397.1  358.94  4431.5  362.49  4499.9  361.98
  4793.1  358.96  4977.2  358.76  4984.1  348.94  4986.1  348.44  5002.0  348.94
  5020.7  358.34  5052.3  356.73  5101.3  358.38  5192.3  357.42  5204.5  359.49
  5273.1  361.59  5595.1  362.59  5726.3  365.63  5807.1  370.36  5850.4  375.39
  5872.1  373.96  5893.9  378.11  5916.8  376.30  5947.1  383.82  5986.7  384.63
#Mann=6,-1,0
  3975.9    0.05       0  4431.5     0.1       0  4499.9    0.05       0
  4793.1    0.12       0  4984.1    0.04       0  5002.0    0.05       0
#XS Ineff=2,0
    0.00 4504.40  364.00               0
Permanent Ineff=
       F       F
Bank Sta=4984.1,5002
Exp/Cntr=0.3,0.1

Type RM Length L Ch R = 1,70129,544,544,544
BEGIN DESCRIPTION:
Walnut Creek 89.0
END DESCRIPTION:
XS GIS Cut Line= 3
      2765226.00      6756711.00      2764483.57      6757130.77
      2763772.78      6757853.96
#Sta/Elev= 30
  4085.0  395.93  4157.9  388.53  4173.8  383.14  4179.5  383.34  4188.4  380.89
  4245.8  377.40  4385.4  363.97  4429.6  359.69  4487.1  357.23  4615.7  356.35
  4823.1  356.72  4928.8  357.68  4933.6  355.27  4943.4  353.81  4950.5  348.46
  4962.4  346.82  4964.4  346.32  4980.9  346.82  4985.8  353.49  4993.0  357.87
  5100.1  356.58  5353.6  357.64  5509.1  364.28  5643.4  367.97  5650.6  366.46
  5664.7  366.76  5678.9  369.41  5707.1  369.85  5799.0  375.79  5951.9  378.08
#Mann=7,-1,0
  4085.0    0.05       0  4385.4    0.12       0  4615.7    0.05       0
  4823.1    0.12       0  4962.4    0.04       0  4980.9    0.12       0
  5100.1    0.05       0
Bank Sta=4962.4,4980.9
Exp/Cntr=0.3,0.1