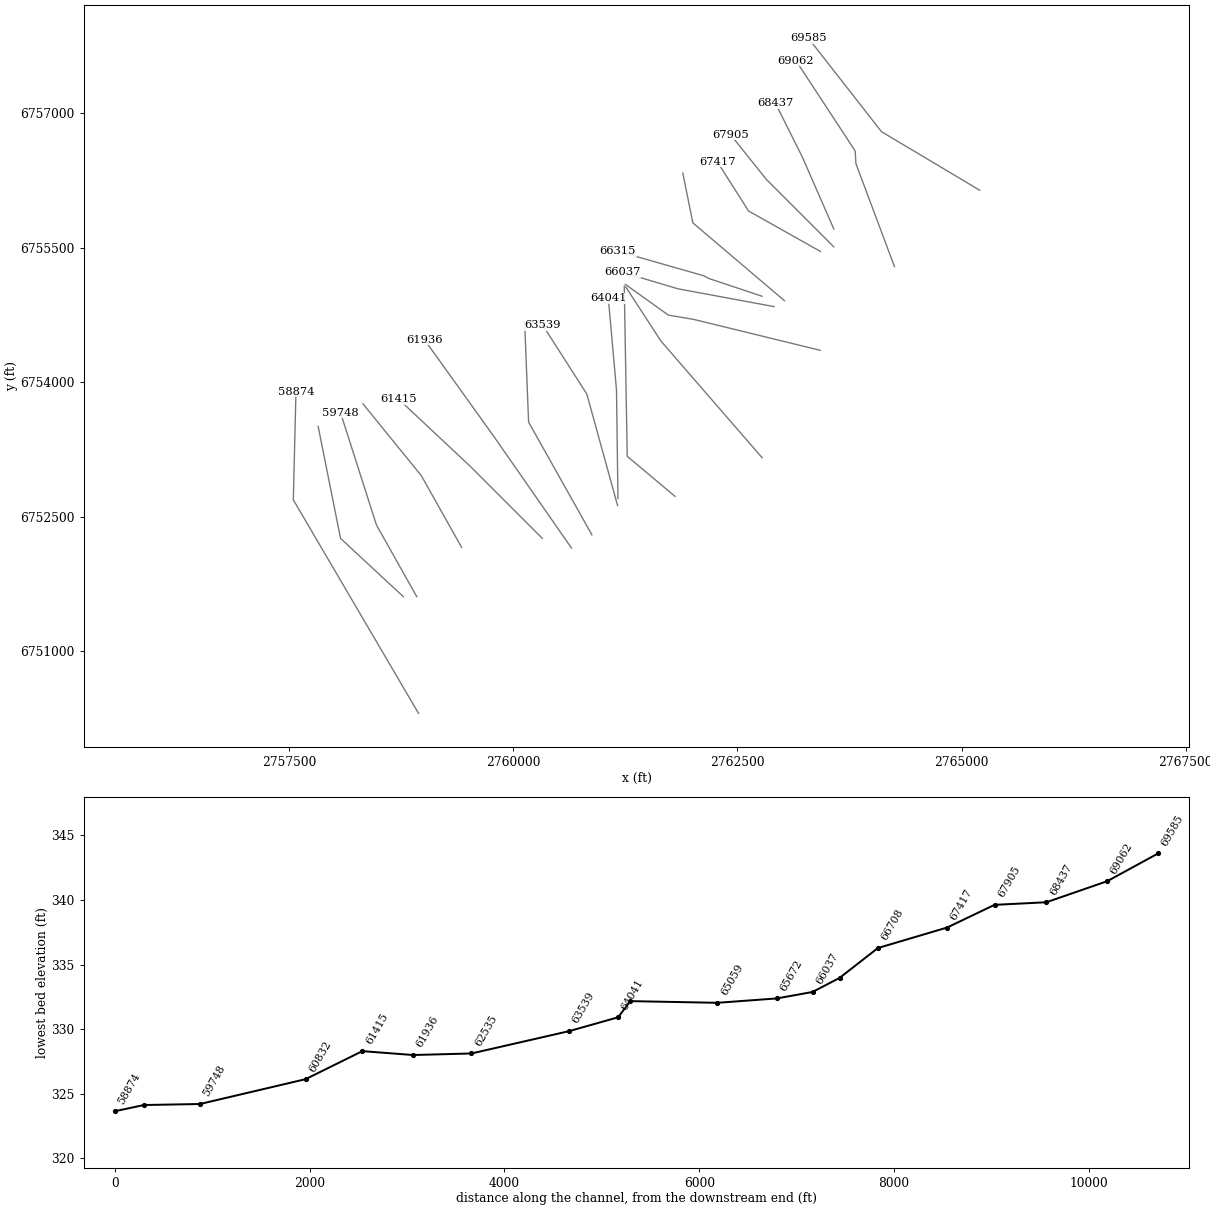
HEC-RAS study Walnut Creek.prj: Walnut Creek Base Level Engineering

--- Walnut Creek.g01 (geometry) --- (continued)

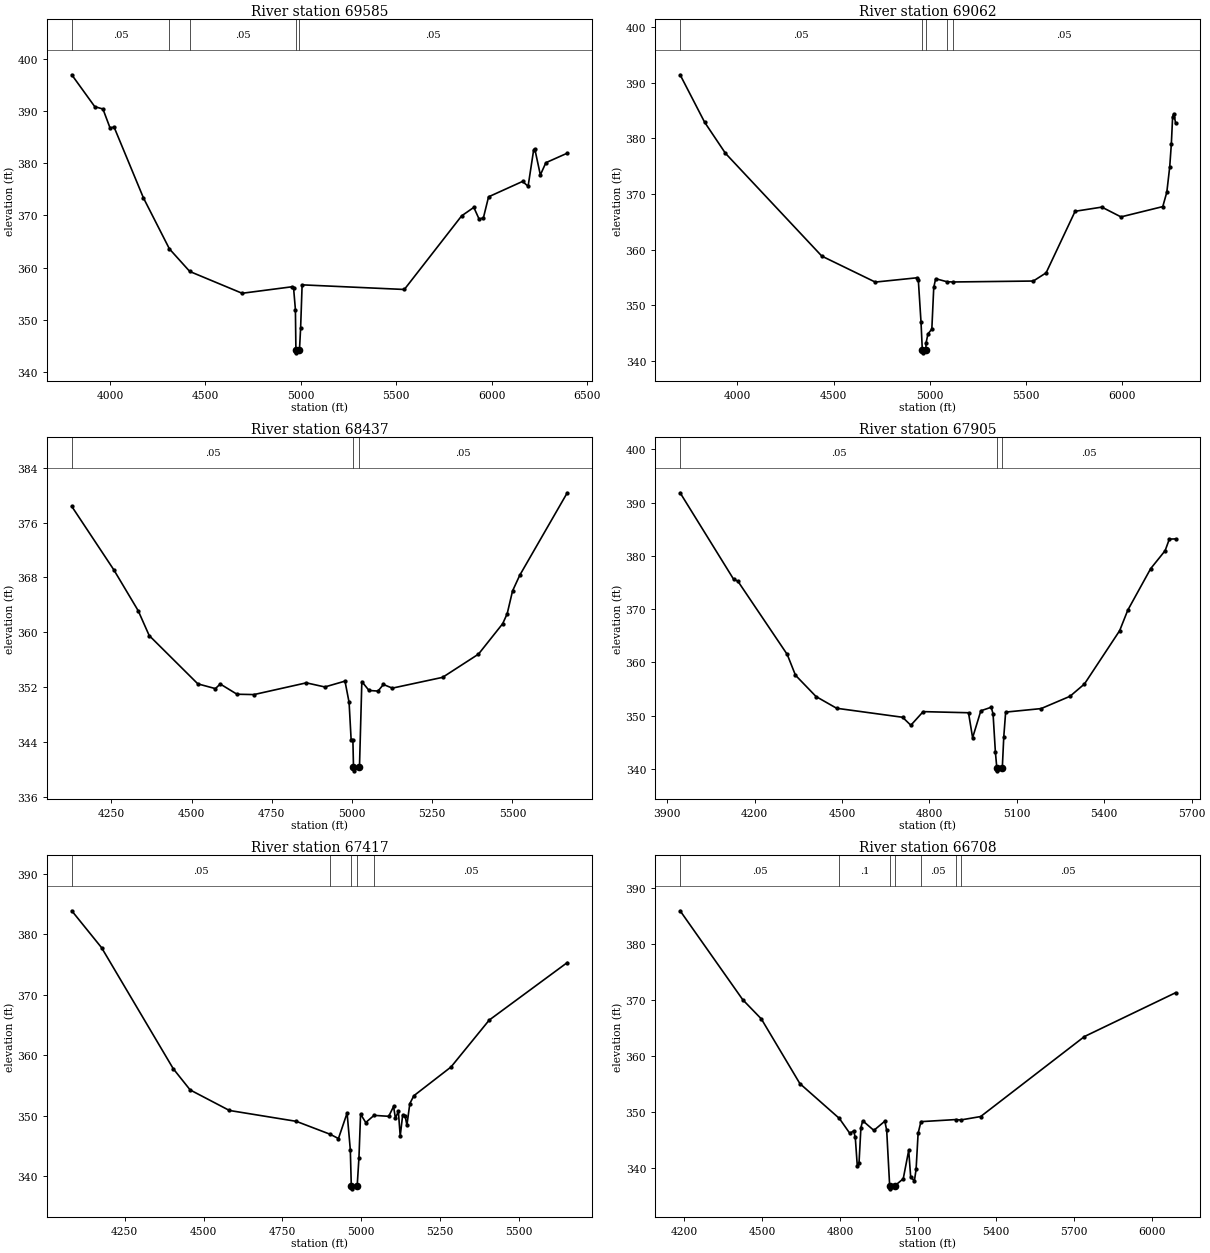
Type RM Length L Ch R = 1,69585,523,523,523
BEGIN DESCRIPTION:
Walnut Creek 88.0
END DESCRIPTION:
XS GIS Cut Line= 3
      2765202.64      6756143.09      2764107.51      6756796.03
      2763293.93      6757836.75
#Sta/Elev= 30
  3800.2  397.05  3920.8  390.92  3963.6  390.47  4000.6  386.85  4022.0  386.99
  4175.8  373.38  4311.9  363.58  4418.5  359.24  4692.8  355.05  4956.4  356.31
  4962.2  356.13  4971.9  351.93  4974.6  344.10  4976.6  343.60  4993.1  344.10
  4999.2  348.33  5007.1  356.67  5542.6  355.78  5842.8  369.93  5906.6  371.56
  5934.2  369.32  5956.8  369.54  5983.9  373.59  6162.1  376.55  6191.0  375.61
  6219.9  382.55  6226.3  382.76  6255.2  377.80  6284.2  380.15  6396.2  381.98
#Mann=5,-1,0
  3800.2    0.05       0  4311.9    0.12       0  4418.5    0.05       0
  4974.6    0.06       0  4993.1    0.05       0
Bank Sta=4974.6,4993.1
Exp/Cntr=0.3,0.1

Type RM Length L Ch R = 1,69062,625,625,625
BEGIN DESCRIPTION:
Walnut Creek 87.0
END DESCRIPTION:
XS GIS Cut Line= 4
      2764252.16      6755291.75      2763822.36      6756440.63
      2763814.10      6756581.14      2763152.89      6757589.49
#Sta/Elev= 30
  3703.3  391.44  3830.6  382.91  3938.8  377.32  4439.2  358.84  4716.8  354.17
  4932.6  354.94  4940.3  354.57  4954.3  346.98  4961.1  341.95  4963.1  341.45
  4979.6  341.95  4980.4  343.20  4990.4  344.85  5010.5  345.72  5020.5  353.22
  5030.5  354.78  5088.2  354.24  5119.2  354.19  5537.6  354.36  5603.9  355.83
  5754.6  366.90  5893.3  367.65  5992.7  365.89  6209.8  367.74  6230.8  370.34
  6245.9  374.89  6254.4  379.07  6261.0  383.93  6267.0  384.45  6276.5  382.75
#Mann=5,-1,0
  3703.3    0.05       0  4961.1    0.06       0  4979.6    0.05       0
  5088.2    0.12       0  5119.2    0.05       0
Bank Sta=4961.1,4979.6
Exp/Cntr=0.3,0.1

Type RM Length L Ch R = 1,68437,532,532,532
BEGIN DESCRIPTION:
Walnut Creek 86.0
END DESCRIPTION:
XS GIS Cut Line= 3
      2763576.00      6755711.01      2763226.00      6756511.00
      2762926.01      6757110.98
#Sta/Elev= 30
  4126.7  378.35  4257.7  369.11  4333.7  363.15  4368.0  359.53  4519.6  352.49
  4574.2  351.80  4589.4  352.47  4641.6  350.98  4694.3  350.93  4857.6  352.64
  4915.3  352.04  4978.1  352.89  4990.9  349.78  4997.2  344.38  5002.7  344.38
  5004.6  340.32  5006.6  339.82  5023.2  340.32  5030.6  352.82  5053.0  351.53
  5081.0  351.44  5097.7  352.40  5125.7  351.87  5282.2  353.44  5394.0  356.82
  5469.5  361.26  5483.5  362.71  5500.2  366.03  5522.6  368.31  5670.7  380.33
#Mann=3,-1,0
  4126.7    0.05       0  5004.6    0.04       0  5023.2    0.05       0
Bank Sta=5004.6,5023.2
Exp/Cntr=0.3,0.1

Type RM Length L Ch R = 1,67905,488,488,488
BEGIN DESCRIPTION:
Walnut Creek 85.0
END DESCRIPTION:
XS GIS Cut Line= 3
      2763576.00      6755511.00      2762826.00      6756261.00
      2762425.99      6756761.02
#Sta/Elev= 30
  3944.0  391.84  4127.9  375.58  4142.0  375.26  4311.7  361.48  4340.0  357.58
  4410.7  353.57  4481.4  351.37  4707.7  349.68  4736.0  348.18  4778.4  350.74
  4934.0  350.53  4948.1  345.84  4976.4  350.90  5011.9  351.56  5018.3  350.33
  5026.3  343.13  5031.3  340.12  5033.3  339.62  5050.0  340.12  5055.1  346.01
  5061.5  350.65  5183.2  351.31  5282.4  353.62  5332.0  355.93  5452.9  365.95
  5480.9  369.81  5559.3  377.59  5609.0  380.97  5623.4  383.14  5645.0  383.18
#Mann=3,-1,0
  3944.0    0.05       0  5031.3    0.04       0  5050.0    0.05       0
Bank Sta=5031.3,5050
Exp/Cntr=0.3,0.1

Type RM Length L Ch R = 1,67417,709,709,709
BEGIN DESCRIPTION:
Walnut Creek 84.0
END DESCRIPTION:
XS GIS Cut Line= 3
      2763425.99      6755461.01      2762626.00      6755911.00
      2762275.99      6756461.01
#Sta/Elev= 30
  4082.6  383.91  4177.2  377.79  4404.2  357.75  4457.7  354.24  4582.0  350.84
  4793.9  349.04  4901.5  346.89  4927.5  346.19  4954.9  350.41  4965.1  344.34
  4968.2  338.36  4970.2  337.86  4986.9  338.36  4992.5  343.05  4997.6  350.23
  5014.0  348.84  5040.3  350.03  5086.8  349.87  5102.1  351.50  5108.0  349.55
  5117.3  350.71  5123.2  346.60  5130.8  350.02  5138.5  349.98  5144.4  348.41
  5153.7  351.99  5166.4  353.28  5284.1  358.04  5405.2  365.81  5652.4  375.33
#Mann=5,-1,0
  4082.6    0.05       0  4901.5    0.12       0  4968.2    0.07       0
  4986.9    0.12       0  5040.3    0.05       0
Bank Sta=4968.2,4986.9
Exp/Cntr=0.3,0.1

Type RM Length L Ch R = 1,66708,393,393,393
BEGIN DESCRIPTION:
Walnut Creek 83.0
END DESCRIPTION:
XS GIS Cut Line= 3
      2763026.02      6754910.99      2762004.04      6755779.42
      2761892.46      6756333.17
#Sta/Elev= 30
  4185.1  385.90  4426.2  370.02  4497.6  366.60  4645.8  355.06  4797.5  348.85
  4838.1  346.17  4852.4  346.62  4858.9  345.47  4866.6  340.38  4873.2  340.81
  4880.6  347.22  4887.5  348.43  4930.3  346.71  4972.5  348.35  4979.7  346.73
  4991.2  336.78  4993.2  336.28  5010.0  336.78  5043.4  338.08  5064.4  343.15
  5072.0  338.40  5086.3  337.69  5092.8  339.76  5100.6  346.20  5111.5  348.27
  5244.8  348.64  5264.5  348.57  5341.1  349.18  5740.5  363.46  6091.1  371.28
#Mann=7,-1,0
  4185.1    0.05       0  4797.5     0.1       0  4991.2    0.07       0
  5010.0     0.1       0  5111.5    0.05       0  5244.8    0.12       0
  5264.5    0.05       0
Bank Sta=4991.2,5010
Exp/Cntr=0.3,0.1

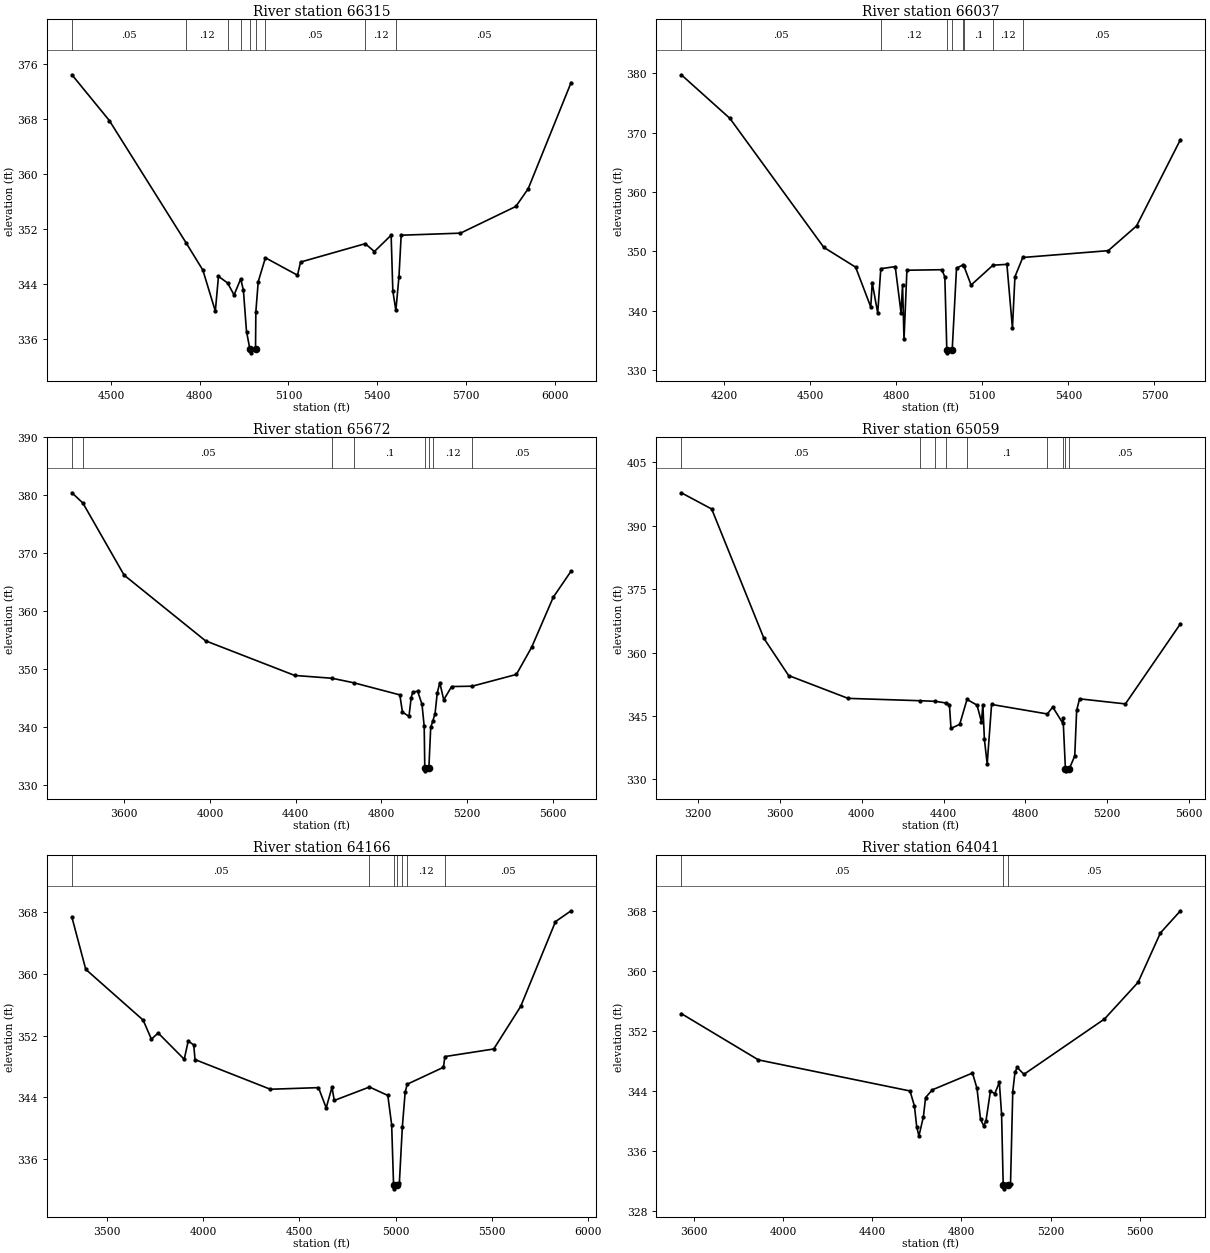
Type RM Length L Ch R = 1,66315,278,278,278
BEGIN DESCRIPTION:
Walnut Creek 82.0
END DESCRIPTION:
XS GIS Cut Line= 4
      2762776.03      6754960.99      2762176.00      6755161.00
      2762127.25      6755188.89      2761166.36      6755463.11
#Sta/Elev= 30
  4367.8  374.37  4494.3  367.72  4754.0  349.94  4810.5  345.99  4852.7  340.03
  4863.3  345.08  4894.2  344.12  4916.0  342.38  4938.5  344.71  4947.6  343.07
  4958.1  337.07  4969.8  334.47  4971.8  333.97  4988.6  334.47  4989.7  339.93
  4997.7  344.31  5022.1  347.78  5130.5  345.25  5140.9  347.16  5359.6  349.83
  5390.5  348.69  5447.2  351.06  5452.9  342.95  5463.2  340.14  5473.7  345.06
  5481.1  351.06  5681.7  351.36  5868.9  355.24  5910.5  357.80  6055.7  373.24
#Mann=9,-1,0
  4367.8    0.05       0  4754.0    0.12       0  4894.2     0.1       0
  4938.5    0.12       0  4969.8    0.07       0  4988.6    0.12       0
  5022.1    0.05       0  5359.6    0.12       0  5463.2    0.05       0
Bank Sta=4969.8,4988.6
Exp/Cntr=0.3,0.1

Type RM Length L Ch R = 1,66037,365,365,365
BEGIN DESCRIPTION:
Walnut Creek 81.0
END DESCRIPTION:
XS GIS Cut Line= 3
      2762909.11      6754845.46      2761838.74      6755043.83
      2761214.75      6755229.78
#Sta/Elev= 30
  4051.0  379.77  4220.3  372.42  4547.6  350.67  4658.5  347.33  4711.3  340.62
  4716.4  344.68  4735.6  339.60  4746.3  347.07  4796.6  347.42  4816.9  339.62
  4822.1  344.40  4827.2  335.13  4837.3  346.81  4959.3  346.90  4969.5  345.67
  4976.4  333.38  4978.4  332.88  4995.2  333.38  5010.2  347.16  5032.0  347.69
  5036.1  347.50  5061.0  344.31  5137.2  347.66  5185.8  347.80  5205.1  337.05
  5213.8  345.71  5241.1  348.96  5539.0  350.11  5637.7  354.28  5790.7  368.84
#Mann=8,-1,0
  4051.0    0.05       0  4746.3    0.12       0  4976.4    0.07       0
  4995.2    0.12       0  5032.0    0.05       0  5036.1     0.1       0
  5137.2    0.12       0  5241.1    0.05       0
Bank Sta=4976.4,4995.2
Exp/Cntr=0.3,0.1

Type RM Length L Ch R = 1,65672,613,613,613
BEGIN DESCRIPTION:
Walnut Creek 80.0
END DESCRIPTION:
XS GIS Cut Line= 4
      2763425.68      6754357.82      2762013.34      6754702.85
      2761731.29      6754750.42      2761251.88      6755093.45
#Sta/Elev= 30
  3356.2  380.41  3407.2  378.64  3599.6  366.19  3979.6  354.84  4395.6  348.86
  4570.2  348.37  4672.6  347.58  4886.3  345.50  4898.6  342.53  4929.1  341.79
  4939.2  344.98  4946.8  345.98  4969.6  346.13  4989.9  343.85  5000.1  340.04
  5002.8  332.88  5004.8  332.38  5021.9  332.88  5030.5  339.87  5040.8  341.06
  5050.8  342.27  5060.9  345.82  5072.8  347.62  5091.2  344.65  5128.1  346.94
  5223.9  347.00  5430.3  349.03  5501.6  353.73  5602.3  362.36  5685.6  366.88
#Mann=8,-1,0
  3356.2    0.12       0  3407.2    0.05       0  4570.2    0.12       0
  4672.6     0.1       0  5002.8    0.07       0  5021.9     0.1       0
  5040.8    0.12       0  5223.9    0.05       0
Bank Sta=5002.8,5021.9
Exp/Cntr=0.3,0.1

Type RM Length L Ch R = 1,65059,893,893,893
BEGIN DESCRIPTION:
Walnut Creek 79.0
END DESCRIPTION:
XS GIS Cut Line= 3
      2762775.97      6753161.04      2761648.64      6754461.14
      2761256.06      6755064.47
#Sta/Elev= 30
  3117.7  397.80  3266.3  393.96  3521.8  363.36  3642.4  354.58  3933.0  349.18
  4285.9  348.62  4359.4  348.48  4412.9  348.08  4428.7  347.67  4436.3  342.06
  4479.1  343.05  4514.7  348.93  4563.6  347.58  4585.4  343.63  4592.1  347.71
  4599.7  339.48  4613.3  333.66  4634.8  347.74  4907.5  345.49  4933.8  347.13
  4982.0  343.39  4984.2  344.56  4995.8  332.54  4997.8  332.04  5014.9  332.54
  5041.5  335.58  5050.7  346.32  5065.0  349.07  5289.1  347.87  5558.3  366.82
#Mann=9,-1,0
  3117.7    0.05       0  4285.9     0.1       0  4359.4    0.05       0
  4412.9    0.12       0  4514.7     0.1       0  4907.5    0.12       0
  4982.0    0.05       0  4995.8    0.04       0  5014.9    0.05       0
Bank Sta=4995.8,5014.9
Exp/Cntr=0.3,0.1

Type RM Length L Ch R = 1,64166,125,125,125
BEGIN DESCRIPTION:
Walnut Creek 78.0
END DESCRIPTION:
XS GIS Cut Line= 3
      2761805.70      6752729.58      2761272.58      6753175.91
      2761239.52      6755072.73
#Sta/Elev= 30
  3319.4  367.31  3391.2  360.58  3689.2  354.01  3732.1  351.54  3767.3  352.34
  3902.6  348.94  3923.4  351.31  3952.0  350.79  3958.6  348.90  4349.8  345.06
  4599.9  345.27  4639.9  342.65  4669.9  345.32  4681.9  343.61  4864.7  345.35
  4959.9  344.26  4979.9  340.47  4989.8  332.67  4991.8  332.17  5010.0  332.67
  5019.9  332.92  5035.3  340.16  5049.9  344.65  5060.5  345.71  5248.9  347.90
  5256.4  349.29  5510.0  350.27  5650.0  355.78  5830.8  366.76  5911.8  368.16
#Mann=7,-1,0
  3319.4    0.05       0  4864.7    0.12       0  4989.8    0.07       0
  5010.0    0.12       0  5035.3    0.05       0  5060.5    0.12       0
  5256.4    0.05       0
Bank Sta=4989.8,5010
Exp/Cntr=0.3,0.1

Type RM Length L Ch R = 1,64041,502,502,502
BEGIN DESCRIPTION:
Walnut Creek 77.8
END DESCRIPTION:
XS GIS Cut Line= 3
      2761169.26      6752704.80      2761152.73      6753915.64
      2761061.81      6754940.56
#Sta/Elev= 30
  3542.7  354.27  3888.9  348.10  4569.0  343.96  4589.0  341.94  4599.0  339.20
  4609.0  337.96  4629.0  340.52  4639.0  343.09  4669.0  344.11  4849.4  346.35
  4869.5  344.31  4885.5  340.16  4899.6  339.34  4909.6  339.91  4929.7  343.92
  4949.8  343.61  4969.9  345.13  4979.9  340.88  4987.2  331.42  4989.2  330.92
  5007.4  331.42  5020.1  331.62  5030.1  343.87  5040.1  346.47  5050.2  347.09
  5080.3  346.18  5441.7  353.55  5592.3  358.43  5692.7  365.02  5782.6  367.97
#Mann=3,-1,0
  3542.7    0.05       0  4987.2    0.03       0  5007.4    0.05       0
Bank Sta=4987.2,5007.4
Exp/Cntr=0.3,0.1

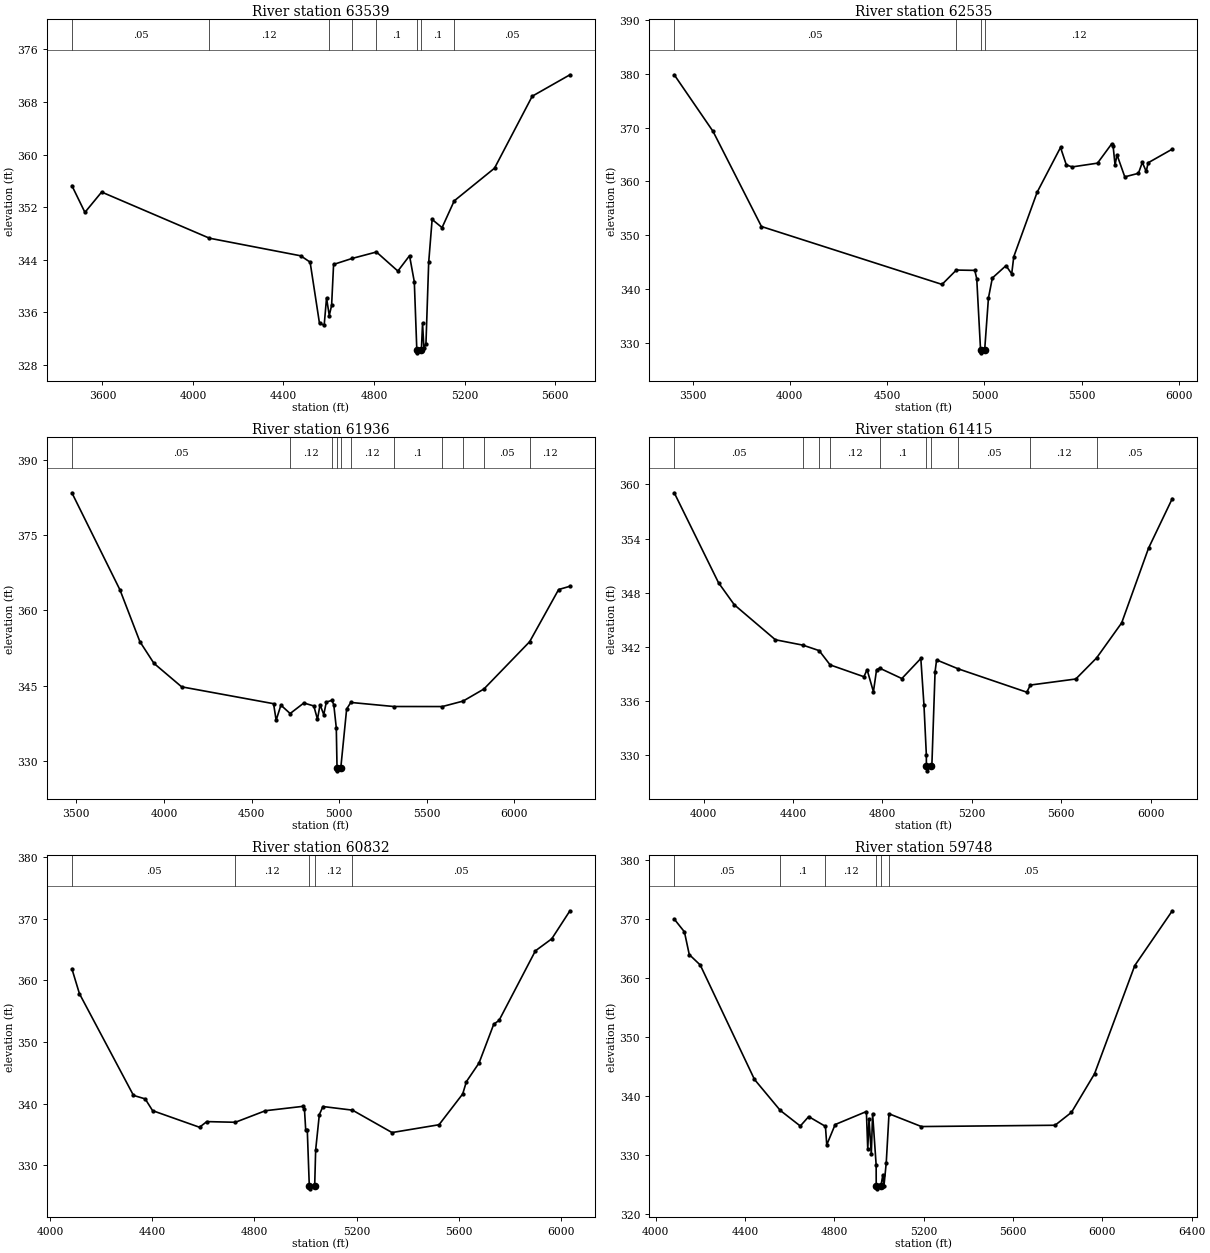
Type RM Length L Ch R = 1,63539,1004,1004,1004
BEGIN DESCRIPTION:
Walnut Creek 77.0
END DESCRIPTION:
XS GIS Cut Line= 3
      2761165.13      6752626.27      2760822.13      6753870.18
      2760331.56      6754636.94
#Sta/Elev= 30
  3465.2  355.29  3522.8  351.22  3596.7  354.31  4073.0  347.29  4476.3  344.61
  4517.8  343.65  4559.3  334.32  4580.0  334.07  4590.4  338.21  4602.4  335.53
  4612.8  337.07  4621.5  343.30  4703.3  344.21  4810.8  345.19  4905.5  342.29
  4957.1  344.63  4978.2  340.65  4989.2  330.35  4991.3  329.85  5009.5  330.35
  5014.6  334.37  5020.5  330.59  5029.6  331.20  5041.7  343.60  5056.9  350.14
  5100.8  348.90  5154.5  352.97  5332.6  357.94  5499.2  368.89  5665.8  372.15
#Mann=8,-1,0
  3465.2    0.05       0  4073.0    0.12       0  4602.4    0.05       0
  4703.3    0.12       0  4810.8     0.1       0  4989.2    0.07       0
  5009.5     0.1       0  5154.5    0.05       0
Bank Sta=4989.2,5009.5
Exp/Cntr=0.3,0.1

Type RM Length L Ch R = 1,62535,599,599,599
BEGIN DESCRIPTION:
Walnut Creek 76.0
END DESCRIPTION:
XS GIS Cut Line= 3
      2760878.20      6752301.24      2760172.72      6753557.88
      2760128.63      6754674.88
#Sta/Elev= 30
  3406.0  379.85  3605.5  369.31  3854.2  351.62  4781.9  340.85  4855.4  343.52
  4950.3  343.46  4960.3  341.89  4979.9  328.62  4982.0  328.12  5000.9  328.62
  5020.4  338.32  5040.4  342.04  5110.5  344.34  5139.9  342.82  5150.5  346.01
  5270.6  358.00  5390.7  366.33  5420.7  363.07  5450.7  362.71  5580.8  363.41
  5653.6  367.00  5660.9  366.60  5670.9  363.06  5680.9  364.96  5720.9  360.86
  5791.0  361.52  5811.0  363.55  5831.0  361.87  5841.0  363.48  5965.0  366.02
#Mann=4,-1,0
  3406.0    0.05       0  4855.4    0.12       0  4979.9    0.07       0
  5000.9    0.12       0
Bank Sta=4979.9,5000.9
Exp/Cntr=0.3,0.1

Type RM Length L Ch R = 1,61936,521,521,521
BEGIN DESCRIPTION:
Walnut Creek 75.0
END DESCRIPTION:
XS GIS Cut Line= 3
      2760650.36      6752154.33      2759776.00      6753411.00
      2759011.82      6754476.21
#Sta/Elev= 30
  3474.8  383.41  3749.3  364.05  3862.8  353.75  3943.1  349.42  4101.1  344.74
  4625.6  341.38  4640.3  338.09  4667.5  341.09  4720.2  339.42  4798.4  341.52
  4855.2  340.93  4876.1  338.28  4891.0  341.18  4911.9  339.20  4926.7  341.70
  4958.7  342.05  4969.2  341.17  4983.5  336.57  4987.8  328.50  4989.9  328.00
  5008.9  328.50  5042.6  340.32  5066.4  341.63  5310.8  340.82  5588.5  340.81
  5707.1  341.90  5825.6  344.30  6086.8  353.73  6252.2  364.13  6316.7  364.78
#Mann=11,-1,0
  3474.8    0.05       0  4720.2    0.12       0  4958.7     0.1       0
  4987.8    0.07       0  5008.9     0.1       0  5066.4    0.12       0
  5310.8     0.1       0  5588.5    0.12       0  5707.1     0.1       0
  5825.6    0.05       0  6086.8    0.12       0
Bank Sta=4987.8,5008.9
Exp/Cntr=0.3,0.1

Type RM Length L Ch R = 1,61415,583,583,583
BEGIN DESCRIPTION:
Walnut Creek 74.0
END DESCRIPTION:
XS GIS Cut Line= 3
      2760326.00      6752261.00      2759526.00      6753061.00
      2758725.97      6753811.03
#Sta/Elev= 30
  3868.9  359.06  4066.9  349.11  4137.6  346.67  4321.4  342.80  4445.2  342.20
  4517.1  341.60  4566.2  340.02  4717.4  338.71  4731.6  339.49  4759.9  337.05
  4774.0  339.48  4787.7  339.66  4887.1  338.51  4972.0  340.73  4986.1  335.54
  4996.7  330.06  4996.8  328.80  4999.0  328.30  5017.9  328.80  5021.5  328.99
  5035.7  339.26  5042.5  340.57  5139.6  339.58  5446.0  337.00  5461.9  337.79
  5665.3  338.46  5758.3  340.79  5870.5  344.67  5990.6  352.93  6096.9  358.42
#Mann=10,-1,0
  3868.9    0.05       0  4445.2    0.12       0  4517.1    0.05       0
  4566.2    0.12       0  4787.7     0.1       0  4996.8    0.07       0
  5017.9     0.1       0  5139.6    0.05       0  5461.9    0.12       0
  5758.3    0.05       0
Bank Sta=4996.8,5017.9
Exp/Cntr=0.3,0.1

Type RM Length L Ch R = 1,60832,1084,1084,1084
BEGIN DESCRIPTION:
Walnut Creek 73.0
END DESCRIPTION:
XS GIS Cut Line= 3
      2759426.00      6752160.99      2758976.00      6752961.00
      2758325.98      6753761.03
#Sta/Elev= 30
  4086.0  361.91  4115.6  357.85  4327.0  341.32  4372.8  340.75  4401.8  338.84
  4585.4  336.14  4613.8  337.06  4725.6  336.95  4843.3  338.83  4990.2  339.54
  4995.9  339.14  5001.0  335.62  5007.1  335.62  5014.9  326.63  5017.0  326.13
  5036.0  326.63  5039.8  332.45  5054.2  338.20  5068.3  339.51  5183.9  338.92
  5338.6  335.28  5522.5  336.55  5615.2  341.56  5629.5  343.55  5679.1  346.59
  5736.6  352.89  5757.4  353.51  5899.6  364.82  5963.5  366.77  6034.7  371.33
#Mann=5,-1,0
  4086.0    0.05       0  4725.6    0.12       0  5014.9    0.07       0
  5036.0    0.12       0  5183.9    0.05       0
Bank Sta=5014.9,5036
Exp/Cntr=0.3,0.1

Type RM Length L Ch R = 1,59748,576,576,576
BEGIN DESCRIPTION:
Walnut Creek 72.0
END DESCRIPTION:
XS GIS Cut Line= 3
      2758926.02      6751610.97      2758476.00      6752411.00
      2758075.98      6753661.05
#Sta/Elev= 30
  4082.6  370.03  4128.2  367.86  4149.9  364.00  4199.0  362.23  4441.8  342.80
  4557.4  337.53  4647.1  334.88  4684.7  336.48  4759.7  334.82  4765.6  331.68
  4803.2  335.13  4943.1  337.34  4949.2  330.95  4954.9  336.03  4965.1  330.07
  4970.9  336.98  4986.8  328.26  4987.1  324.71  4989.2  324.21  5008.2  324.71
  5016.6  326.53  5021.8  324.72  5032.0  328.63  5044.4  336.96  5189.5  334.79
  5788.0  335.01  5861.5  337.20  5964.8  343.75  6145.0  362.14  6313.0  371.44
#Mann=6,-1,0
  4082.6    0.05       0  4557.4     0.1       0  4759.7    0.12       0
  4987.1    0.07       0  5008.2    0.12       0  5044.4    0.05       0
Bank Sta=4987.1,5008.2
Exp/Cntr=0.3,0.1

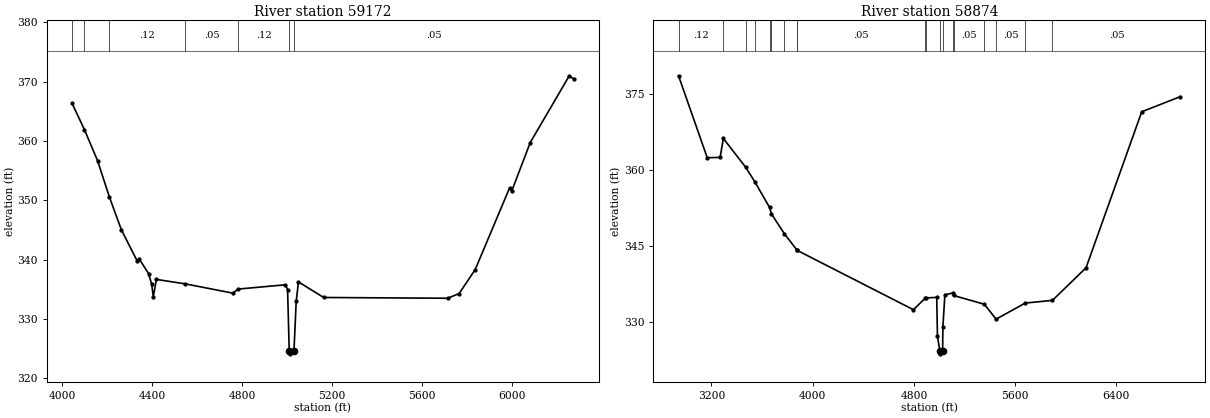
Type RM Length L Ch R = 1,59172,298,298,298
BEGIN DESCRIPTION:
Walnut Creek 71.0
END DESCRIPTION:
XS GIS Cut Line= 3
      2758775.99      6751611.01      2758076.00      6752261.00
      2757826.00      6753511.00
#Sta/Elev= 30
  4044.6  366.34  4099.7  361.91  4157.7  356.71  4210.3  350.59  4263.7  345.04
  4334.6  339.73  4341.9  340.20  4384.4  337.65  4398.6  335.85  4405.4  333.75
  4419.6  336.67  4545.5  335.94  4759.2  334.36  4783.1  335.05  4992.8  335.77
  5002.4  334.96  5009.6  324.63  5011.7  324.13  5030.8  324.63  5040.6  332.96
  5050.8  336.25  5163.0  333.63  5713.7  333.50  5764.7  334.29  5836.1  338.33
  5989.1  352.11  5999.2  351.64  6080.8  359.75  6254.2  371.00  6274.6  370.44
#Mann=7,-1,0
  4044.6    0.05       0  4099.7     0.1       0  4210.3    0.12       0
  4545.5    0.05       0  4783.1    0.12       0  5009.6    0.07       0
  5030.8    0.05       0
Bank Sta=5009.6,5030.8
Exp/Cntr=0.3,0.1

Type RM Length L Ch R = 1,58874,827,827,827
BEGIN DESCRIPTION:
Walnut Creek 70.0
END DESCRIPTION:
XS GIS Cut Line= 3
      2758945.53      6750309.78      2757549.29      6752690.75
      2757578.68      6753895.92
#Sta/Elev= 30
  2939.7  378.52  3166.6  362.35  3268.2  362.41  3293.8  366.15  3470.0  360.48
  3541.6  357.64  3659.3  352.53  3673.8  351.27  3775.8  347.36  3877.6  344.07
  3877.7  344.06  4795.9  332.36  4887.1  334.59  4891.6  334.68  4980.2  334.79
  4986.0  327.09  5005.6  324.15  5007.7  323.65  5026.8  324.15  5029.0  329.01
  5044.7  335.30  5105.0  335.64  5112.9  335.17  5357.0  333.43  5449.4  330.49
  5679.8  333.67  5894.6  334.20  6160.3  340.63  6600.4  371.42  6905.4  374.40
#Mann=19,-1,0
  2939.7    0.12       0  3293.8     0.1       0  3470.0    0.12       0
  3541.6     0.1       0  3659.3    0.12       0  3673.8    0.05       0
  3775.8     0.1       0  3877.6    0.12       0  3877.7    0.05       0
  4887.1    0.12       0  4891.6     0.1       0  5005.6    0.07       0
  5026.8     0.1       0  5105.0    0.12       0  5112.9    0.05       0
  5357.0    0.12       0  5449.4    0.05       0  5679.8     0.1       0
  5894.6    0.05       0
Bank Sta=5005.6,5026.8
Exp/Cntr=0.3,0.1