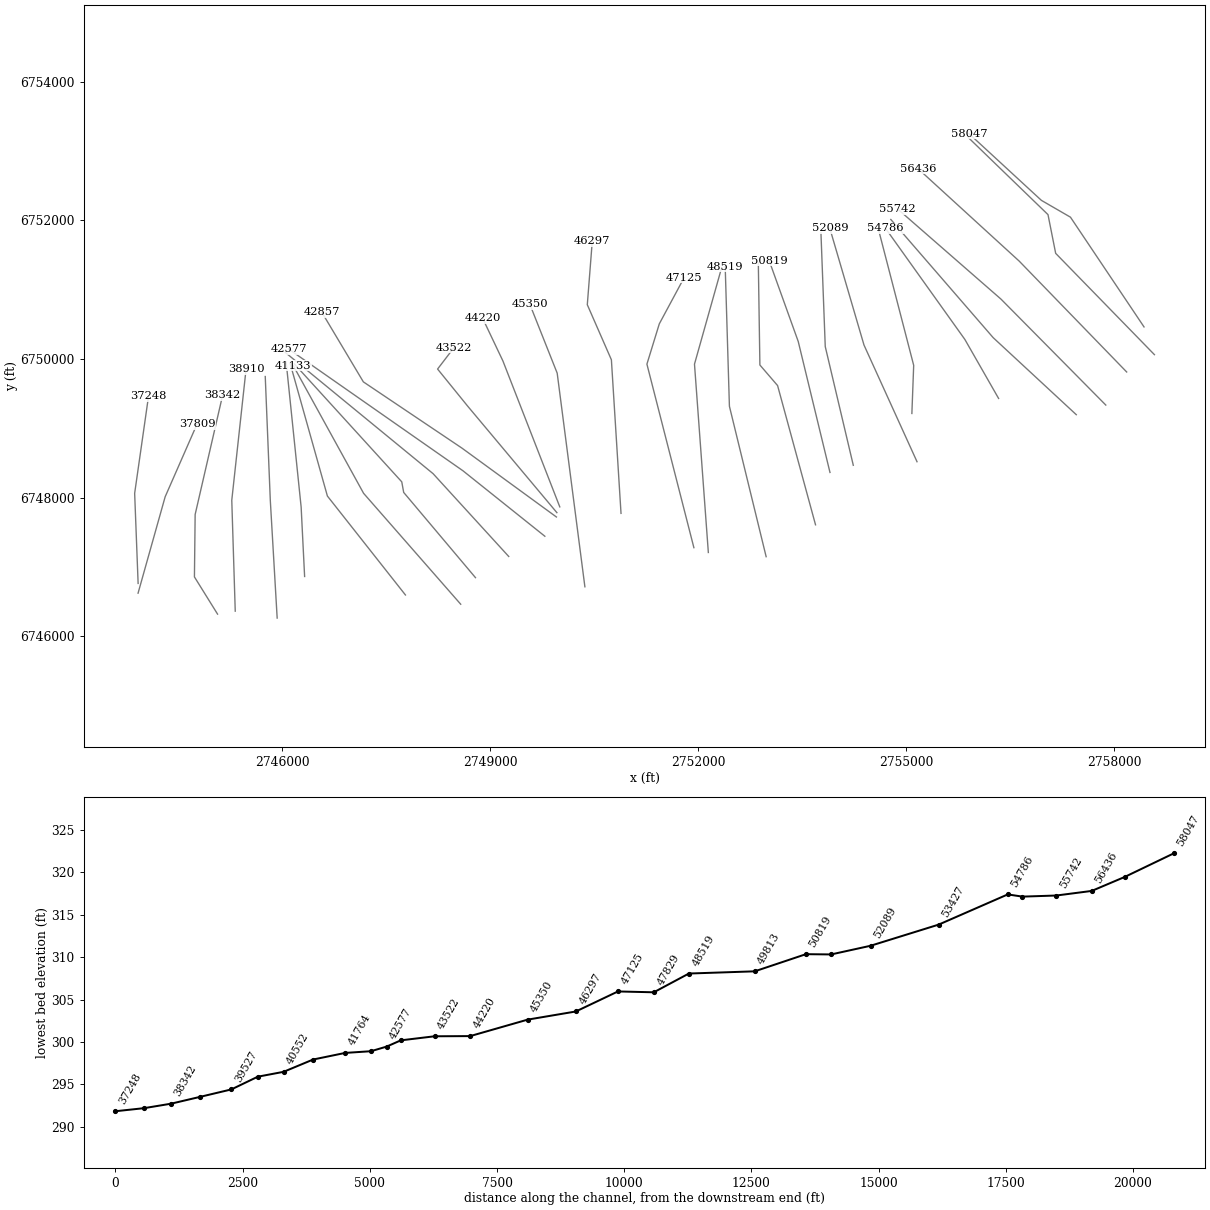
HEC-RAS study Walnut Creek.prj: Walnut Creek Base Level Engineering

--- Walnut Creek.g01 (geometry) --- (continued)

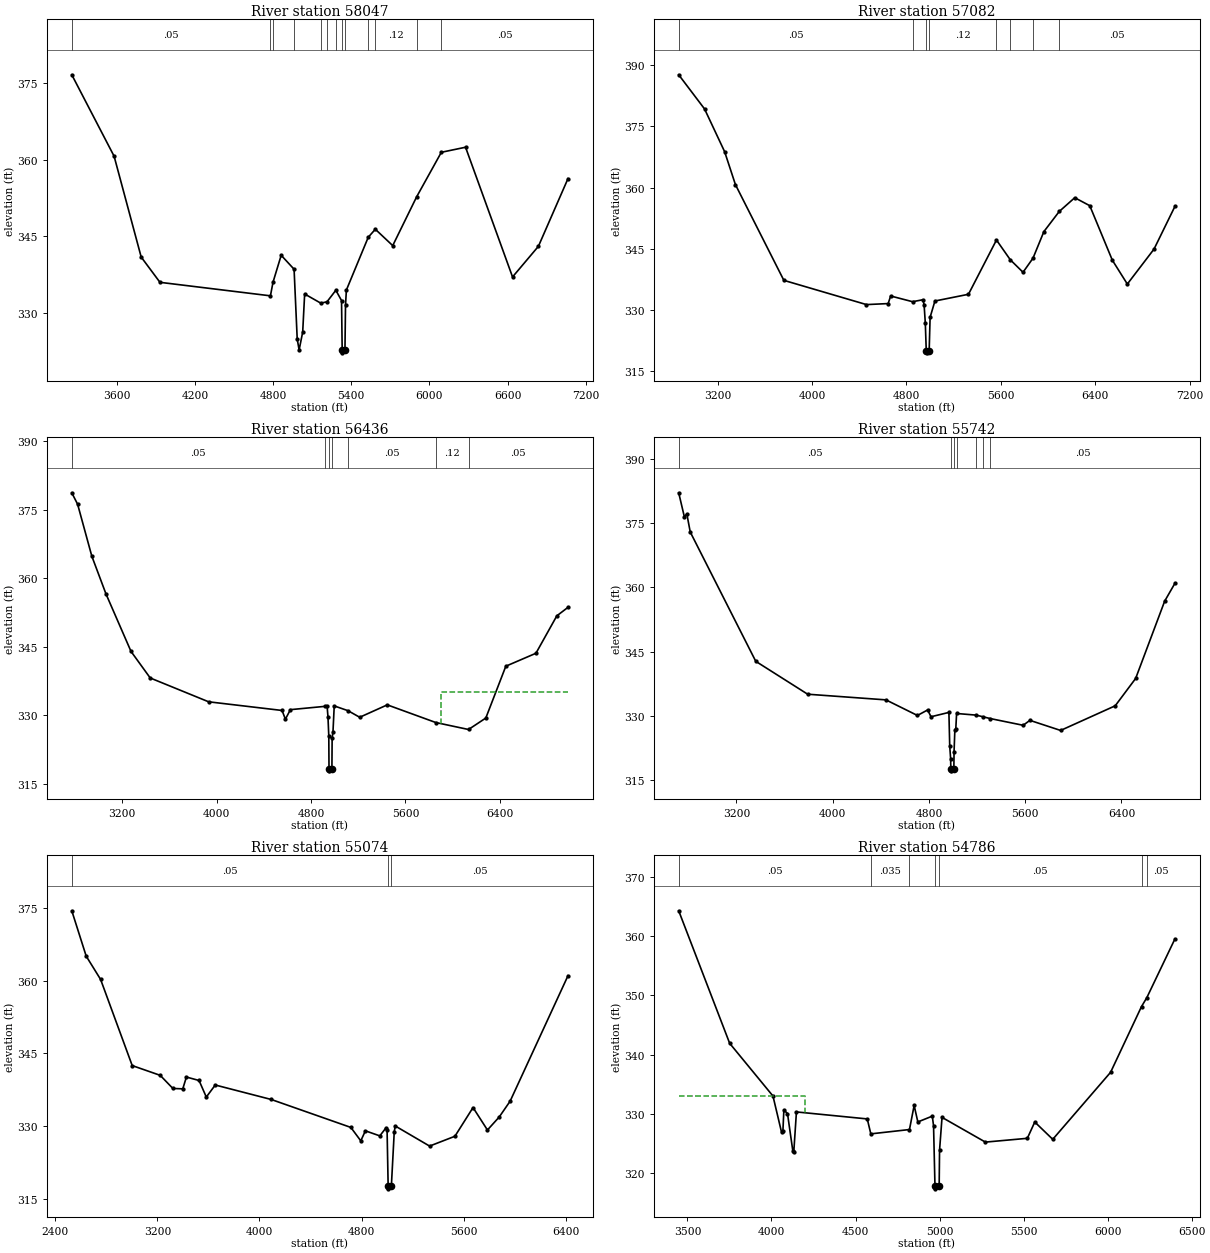
Type RM Length L Ch R = 1,58047,965,965,965
BEGIN DESCRIPTION:
Walnut Creek 69.0
END DESCRIPTION:
XS GIS Cut Line= 4
      2758425.98      6750461.03      2757365.57      6752044.07
      2756946.70      6752286.58      2755903.21      6753249.24
#Sta/Elev= 30
  3255.0  376.59  3579.9  360.66  3787.8  340.94  3931.9  336.00  4779.9  333.36
  4799.9  336.04  4862.5  341.29  4961.5  338.56  4985.5  324.92  5000.2  322.77
  5027.6  326.28  5042.6  333.72  5166.2  331.93  5214.2  332.19  5282.1  334.45
  5325.7  332.44  5330.8  322.71  5332.9  322.21  5352.0  322.71  5356.3  331.53
  5363.0  334.49  5530.9  344.82  5585.2  346.38  5718.7  343.18  5902.5  352.73
  6091.9  361.43  6277.8  362.42  6638.5  337.05  6837.0  343.04  7064.1  356.28
#Mann=13,-1,0
  3255.0    0.05       0  4779.9     0.1       0  4799.9    0.05       0
  4961.5    0.12       0  5166.2     0.1       0  5214.2    0.05       0
  5282.1    0.12       0  5330.8    0.07       0  5352.0    0.12       0
  5530.9    0.05       0  5585.2    0.12       0  5902.5     0.1       0
  6091.9    0.05       0
Bank Sta=5330.8,5352
Exp/Cntr=0.3,0.1

Type RM Length L Ch R = 1,57082,646,646,646
BEGIN DESCRIPTION:
Walnut Creek 68.0
END DESCRIPTION:
XS GIS Cut Line= 4
      2758575.97      6750061.03      2757152.46      6751522.33
      2757041.89      6752080.75      2755895.83      6753190.48
#Sta/Elev= 30
  2869.9  387.67  3089.1  379.28  3258.9  368.81  3350.7  360.71  3761.0  337.22
  4461.1  331.27  4644.8  331.52  4666.1  333.38  4851.3  331.98  4939.2  332.46
  4949.4  331.25  4959.6  326.75  4967.7  319.93  4970.1  319.43  4992.3  319.93
  5000.3  328.15  5041.1  332.15  5325.4  333.80  5562.6  347.12  5679.7  342.27
  5787.7  339.20  5872.2  342.66  5964.4  349.18  6094.7  354.13  6226.0  357.50
  6353.3  355.54  6544.4  342.17  6671.5  336.31  6897.9  344.90  7074.5  355.35
#Mann=8,-1,0
  2869.9    0.05       0  4851.3    0.12       0  4967.7    0.07       0
  4992.3    0.12       0  5562.6    0.05       0  5679.7    0.12       0
  5872.2     0.1       0  6094.7    0.05       0
Bank Sta=4967.7,4992.3
Exp/Cntr=0.3,0.1

Type RM Length L Ch R = 1,56436,694,694,694
BEGIN DESCRIPTION:
Walnut Creek 67.0
END DESCRIPTION:
XS GIS Cut Line= 3
      2758176.02      6749810.98      2756626.00      6751411.00
      2755166.49      6752745.44
#Sta/Elev= 30
  2772.3  378.73  2821.8  376.21  2942.0  364.84  3062.4  356.54  3274.3  343.96
  3437.1  338.14  3932.1  332.92  4554.5  331.02  4582.6  329.11  4625.1  331.20
  4917.3  331.92  4936.3  331.94  4943.5  329.61  4950.5  325.39  4952.3  318.29
  4954.8  317.79  4976.9  318.29  4978.8  324.97  4986.0  326.38  4996.5  332.02
  5113.6  330.97  5212.4  329.53  5446.2  332.25  5857.2  328.38  6134.7  326.85
  6281.2  329.36  6450.8  340.72  6706.1  343.56  6883.1  351.76  6977.6  353.62
#Mann=7,-1,0
  2772.3    0.05       0  4917.3    0.12       0  4952.3    0.07       0
  4976.9    0.12       0  5113.6    0.05       0  5857.2    0.12       0
  6134.7    0.05       0
#XS Ineff=2,0
       0                 5900.00    0.00  335.00
Permanent Ineff=
       F       F
Bank Sta=4952.3,4976.9
Exp/Cntr=0.3,0.1

Type RM Length L Ch R = 1,55742,668,668,668
BEGIN DESCRIPTION:
Walnut Creek 66.0
END DESCRIPTION:
XS GIS Cut Line= 3
      2757874.84      6749333.97      2756364.39      6750861.78
      2754875.99      6752161.01
#Sta/Elev= 30
  2719.9  382.02  2766.5  376.47  2787.7  377.06  2815.9  372.88  3360.5  342.76
  3791.8  335.10  4442.4  333.78  4704.0  330.15  4788.8  331.43  4817.1  329.85
  4965.8  330.86  4972.5  323.04  4980.1  320.06  4981.8  317.75  4984.3  317.25
  5006.8  317.75  5008.6  321.74  5015.2  326.69  5022.8  326.92  5029.7  330.61
  5191.8  330.23  5251.0  329.83  5309.1  329.43  5582.9  327.86  5638.9  329.01
  5894.2  326.66  6348.0  332.40  6517.9  338.77  6759.0  356.77  6844.0  360.92
#Mann=7,-1,0
  2719.9    0.05       0  4981.8    0.04       0  5006.8    0.05       0
  5029.7    0.12       0  5191.8    0.05       0  5251.0    0.12       0
  5309.1    0.05       0
Bank Sta=4981.8,5006.8
Exp/Cntr=0.3,0.1

Type RM Length L Ch R = 1,55074,288,288,288
BEGIN DESCRIPTION:
Walnut Creek 65.0
END DESCRIPTION:
XS GIS Cut Line= 3
      2757449.44      6749195.13      2756251.54      6750306.22
      2754776.01      6752010.99
#Sta/Elev= 30
  2529.0  374.35  2642.0  365.01  2754.8  360.22  3002.5  342.49  3221.9  340.48
  3321.2  337.78  3398.8  337.70  3427.2  340.13  3526.4  339.42  3583.1  336.01
  3653.4  338.49  4092.2  335.51  4715.9  329.76  4793.8  327.00  4829.9  329.06
  4942.9  328.02  4992.3  329.71  4999.9  329.15  5008.3  317.62  5010.8  317.12
  5033.3  317.62  5055.9  328.80  5063.6  330.06  5333.0  325.92  5531.4  327.94
  5673.4  333.85  5786.3  329.23  5878.5  331.90  5964.0  335.16  6417.5  360.98
#Mann=3,-1,0
  2529.0    0.05       0  5008.3    0.04       0  5033.3    0.05       0
Bank Sta=5008.3,5033.3
Exp/Cntr=0.3,0.1

Type RM Length L Ch R = 1,54786,1359,1359,1359
BEGIN DESCRIPTION:
Walnut Creek 64.0
END DESCRIPTION:
XS GIS Cut Line= 3
      2756329.65      6749429.51      2755843.56      6750280.18
      2754697.75      6751886.05
#Sta/Elev= 30
  3447.8  364.27  3751.1  341.92  4008.8  333.03  4059.9  326.91  4067.8  327.07
  4073.6  330.67  4095.2  330.08  4126.8  323.79  4132.6  323.61  4148.4  330.35
  4569.8  329.17  4591.0  326.65  4821.0  327.38  4848.8  331.44  4870.8  328.66
  4956.8  329.64  4964.3  328.01  4972.7  317.88  4975.2  317.38  4997.7  317.88
  5000.0  323.89  5014.7  329.43  5272.8  325.26  5522.3  325.90  5566.6  328.65
  5673.5  325.73  6017.7  337.03  6201.7  348.12  6233.0  349.60  6400.3  359.51
#Mann=7,-1,0
  3447.8    0.05       0  4591.0   0.035       0  4821.0    0.05       0
  4972.7    0.04       0  4997.7    0.05       0  6201.7    0.12       0
  6233.0    0.05       0
#XS Ineff=2,0
    0.00 4200.00  333.00               0
Permanent Ineff=
       F       F
Bank Sta=4972.7,4997.7
Exp/Cntr=0.3,0.1

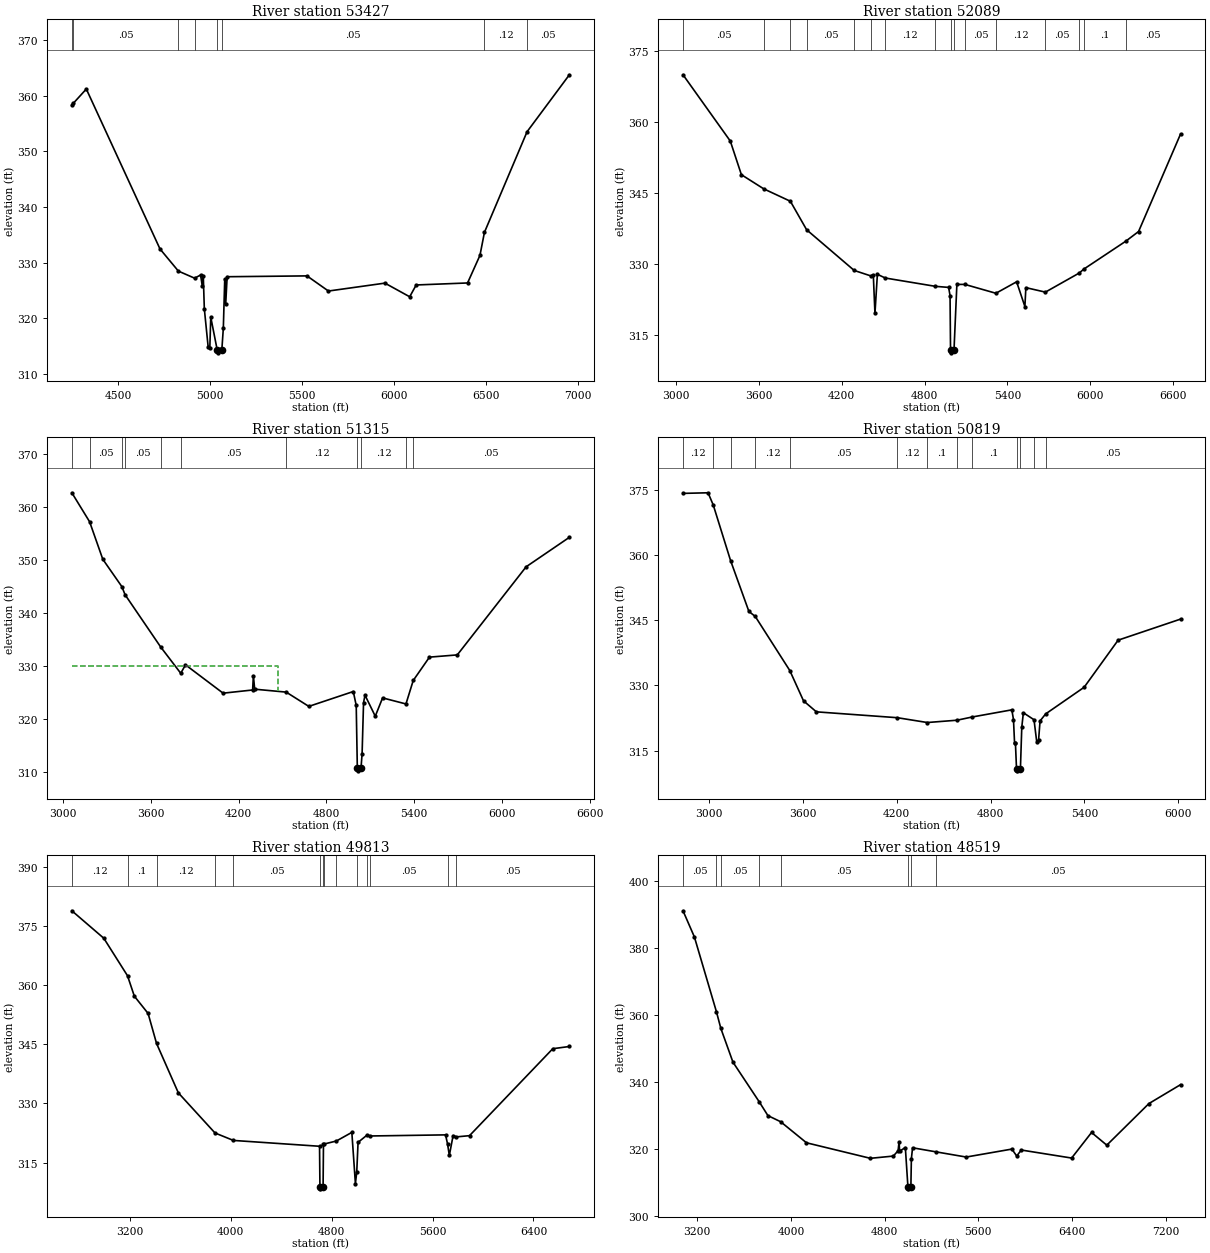
Type RM Length L Ch R = 1,53427,1338,1338,1338
BEGIN DESCRIPTION:
Walnut Creek 63.0
END DESCRIPTION:
XS GIS Cut Line= 3
      2755079.67      6749212.47      2755105.71      6749906.92
      2754602.24      6751851.36
#Sta/Elev= 30
  4248.0  358.31  4255.4  358.62  4326.6  361.20  4726.9  332.48  4826.9  328.50
  4915.0  327.23  4947.6  327.80  4957.0  325.76  4962.2  327.60  4967.8  321.75
  4988.5  314.92  4997.6  314.63  5002.8  320.23  5037.9  314.32  5040.4  313.82
  5062.9  314.32  5071.1  318.26  5078.8  327.12  5084.0  322.61  5091.8  327.49
  5525.6  327.64  5642.2  324.92  5949.1  326.34  6083.7  323.89  6119.1  326.01
  6398.2  326.37  6465.6  331.33  6489.9  335.46  6721.5  353.53  6951.5  363.76
#Mann=8,-1,0
  4248.0     0.1       0  4255.4    0.05       0  4826.9    0.12       0
  4915.0    0.05       0  5037.9    0.04       0  5062.9    0.05       0
  6489.9    0.12       0  6721.5    0.05       0
Bank Sta=5037.9,5062.9
Exp/Cntr=0.3,0.1

Type RM Length L Ch R = 1,52089,774,774,774
BEGIN DESCRIPTION:
Walnut Creek 62.0
END DESCRIPTION:
XS GIS Cut Line= 3
      2755153.68      6748516.73      2754389.41      6750199.59
      2753897.07      6751882.37
#Sta/Elev= 30
  3051.4  370.05  3393.8  356.05  3474.0  348.95  3635.9  345.96  3828.6  343.34
  3946.3  337.32  4290.6  328.73  4409.4  327.59  4429.0  327.76  4440.9  319.65
  4458.5  327.91  4515.9  327.13  4879.1  325.37  4974.1  325.15  4984.5  323.43
  4988.0  311.83  4990.5  311.33  5013.0  311.83  5033.9  325.78  5091.8  325.78
  5316.5  323.91  5466.4  326.33  5526.3  321.11  5533.3  325.10  5674.6  324.15
  5919.5  328.18  5953.2  329.02  6255.9  334.89  6349.2  336.95  6653.0  357.53
#Mann=16,-1,0
  3051.4    0.05       0  3635.9     0.1       0  3828.6    0.12       0
  3946.3    0.05       0  4290.6    0.12       0  4409.4     0.1       0
  4515.9    0.12       0  4879.1     0.1       0  4988.0    0.07       0
  5013.0     0.1       0  5091.8    0.05       0  5316.5    0.12       0
  5674.6    0.05       0  5919.5    0.12       0  5953.2     0.1       0
  6255.9    0.05       0
Bank Sta=4988,5013
Exp/Cntr=0.3,0.1

Type RM Length L Ch R = 1,51315,496,496,496
BEGIN DESCRIPTION:
Walnut Creek 61.0
END DESCRIPTION:
XS GIS Cut Line= 3
      2754235.08      6748465.35      2753830.92      6750177.54
      2753768.92      6751816.32
#Sta/Elev= 30
  3060.8  362.69  3182.1  357.23  3272.1  350.17  3402.2  345.02  3424.5  343.48
  3667.4  333.65  3804.7  328.69  3837.2  330.28  4094.1  324.94  4295.9  325.54
  4301.0  328.25  4309.9  325.69  4525.1  325.14  4679.8  322.45  4983.6  325.25
  5003.6  322.63  5011.2  310.81  5013.7  310.31  5036.2  310.81  5043.7  313.49
  5053.7  323.16  5063.7  324.56  5133.7  320.60  5183.8  324.05  5343.5  322.91
  5393.1  327.33  5504.0  331.73  5694.1  332.15  6164.5  348.75  6460.0  354.30
#Mann=11,-1,0
  3060.8     0.1       0  3182.1    0.05       0  3402.2     0.1       0
  3424.5    0.05       0  3667.4    0.12       0  3804.7    0.05       0
  4525.1    0.12       0  5011.2    0.07       0  5036.2    0.12       0
  5343.5     0.1       0  5393.1    0.05       0
#XS Ineff=2,0
    0.00 4470.00  330.00               0
Permanent Ineff=
       F       F
Bank Sta=5011.2,5036.2
Exp/Cntr=0.3,0.1

Type RM Length L Ch R = 1,50819,1006,1006,1006
BEGIN DESCRIPTION:
Walnut Creek 60.0
END DESCRIPTION:
XS GIS Cut Line= 3
      2753899.12      6748361.75      2753441.44      6750251.03
      2753022.62      6751416.65
#Sta/Elev= 30
  2832.4  374.25  2992.7  374.39  3026.2  371.54  3136.7  358.77  3253.9  347.06
  3294.6  345.90  3515.4  333.45  3603.3  326.46  3685.6  323.93  4203.3  322.58
  4395.2  321.47  4584.8  322.00  4680.3  322.73  4935.7  324.39  4946.3  322.16
  4953.3  316.68  4958.7  316.77  4965.7  310.84  4968.2  310.34  4990.7  310.84
  4999.4  320.39  5009.5  323.72  5077.6  322.11  5095.1  317.00  5107.0  317.50
  5116.3  321.83  5151.9  323.45  5398.3  329.59  5615.7  340.44  6014.9  345.29
#Mann=13,-1,0
  2832.4    0.12       0  3026.2     0.1       0  3136.7    0.05       0
  3294.6    0.12       0  3515.4    0.05       0  4203.3    0.12       0
  4395.2     0.1       0  4584.8    0.12       0  4680.3     0.1       0
  4965.7    0.07       0  4990.7     0.1       0  5077.6    0.12       0
  5151.9    0.05       0
Bank Sta=4965.7,4990.7
Exp/Cntr=0.3,0.1

Type RM Length L Ch R = 1,49813,1294,1294,1294
BEGIN DESCRIPTION:
Walnut Creek 59.0
END DESCRIPTION:
XS GIS Cut Line= 4
      2753690.77      6747606.59      2753143.96      6749614.92
      2752888.75      6749911.80      2752866.13      6751382.59
#Sta/Elev= 30
  2740.8  378.86  2994.1  371.89  3181.9  362.38  3236.2  357.19  3345.1  352.82
  3412.0  345.22  3584.9  332.67  3875.6  322.49  4021.4  320.60  4704.2  319.12
  4707.3  308.82  4709.8  308.32  4732.3  308.82  4735.3  319.61  4740.6  319.69
  4837.4  320.45  4960.2  322.64  4988.5  309.66  4999.0  312.54  5009.6  320.11
  5083.1  322.02  5103.6  321.73  5703.0  322.01  5718.5  319.77  5733.0  316.81
  5763.0  321.84  5788.8  321.50  5893.0  321.81  6553.1  343.87  6684.7  344.43
#Mann=14,-1,0
  2740.8    0.12       0  3181.9     0.1       0  3412.0    0.12       0
  3875.6     0.1       0  4021.4    0.05       0  4707.3    0.07       0
  4732.3    0.05       0  4740.6     0.1       0  4837.4    0.12       0
  4999.0     0.1       0  5083.1    0.12       0  5103.6    0.05       0
  5718.5    0.12       0  5788.8    0.05       0
Bank Sta=4707.3,4732.3
Exp/Cntr=0.3,0.1

Type RM Length L Ch R = 1,48519,690,690,690
BEGIN DESCRIPTION:
Walnut Creek 58.0
END DESCRIPTION:
XS GIS Cut Line= 3
      2752978.97      6747146.53      2752449.46      6749316.64
      2752388.69      6751330.54
#Sta/Elev= 30
  3078.0  391.15  3175.2  383.33  3362.9  361.05  3401.0  356.01  3504.6  345.91
  3727.5  334.14  3803.1  329.94  3911.5  328.12  4132.5  321.82  4678.1  317.18
  4873.7  317.85  4914.8  319.44  4922.8  322.10  4927.9  319.31  4976.6  320.41
  4998.8  308.56  5001.3  308.06  5023.8  308.56  5028.1  317.05  5038.3  320.33
  5237.1  319.12  5496.2  317.56  5886.4  319.94  5927.6  317.86  5966.4  319.66
  6396.6  317.26  6566.7  324.90  6696.8  321.11  7056.9  333.55  7326.6  339.19
#Mann=8,-1,0
  3078.0    0.05       0  3362.9     0.1       0  3401.0    0.05       0
  3727.5     0.1       0  3911.5    0.05       0  4998.8    0.04       0
  5023.8    0.05       0  5237.1    0.05       0
Bank Sta=4998.8,5023.8
Exp/Cntr=0.3,0.1

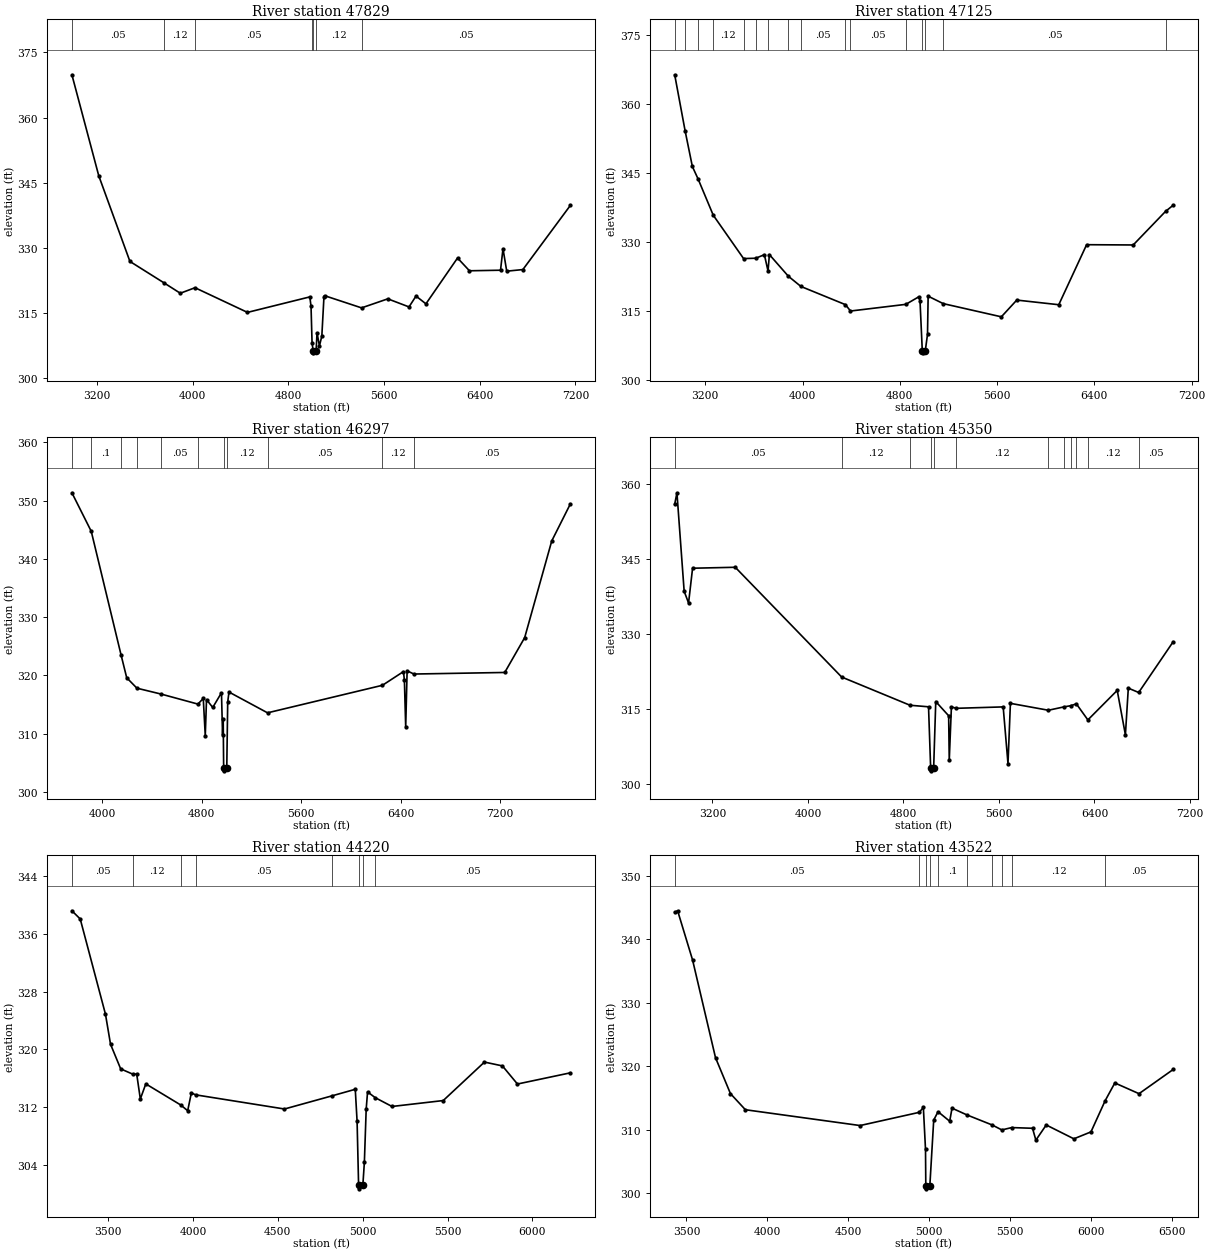
Type RM Length L Ch R = 1,47829,704,704,704
BEGIN DESCRIPTION:
Walnut Creek 57.0
END DESCRIPTION:
XS GIS Cut Line= 3
      2752145.64      6747207.25      2751945.99      6749924.28
      2752336.60      6751313.14
#Sta/Elev= 30
  2991.5  369.86  3215.9  346.62  3476.6  326.89  3760.3  321.98  3897.7  319.57
  4020.7  320.84  4459.2  315.16  4980.6  318.73  4990.6  316.57  4999.2  308.15
  5008.2  306.35  5010.7  305.85  5033.2  306.35  5040.8  310.46  5060.8  307.44
  5080.9  309.71  5098.8  318.80  5103.8  319.01  5413.0  316.20  5632.4  318.28
  5809.7  316.42  5868.3  318.92  5951.1  317.13  6215.4  327.68  6315.0  324.74
  6574.7  324.87  6595.4  329.82  6626.6  324.65  6761.6  325.02  7158.6  339.79
#Mann=7,-1,0
  2991.5    0.05       0  3760.3    0.12       0  4020.7    0.05       0
  4999.2    0.12       0  5008.2    0.07       0  5033.2    0.12       0
  5413.0    0.05       0
Bank Sta=5008.2,5033.2
Exp/Cntr=0.3,0.1

Type RM Length L Ch R = 1,47125,828,828,828
BEGIN DESCRIPTION:
Walnut Creek 56.0
END DESCRIPTION:
XS GIS Cut Line= 4
      2751937.31      6747276.70      2751260.22      6749924.28
      2751438.75      6750505.43      2751797.58      6751173.41
#Sta/Elev= 30
  2948.4  366.40  3034.3  354.17  3093.6  346.46  3141.2  343.72  3265.4  335.87
  3514.9  326.44  3615.4  326.52  3685.7  327.29  3715.9  323.74  3727.0  327.31
  3883.1  322.60  3986.4  320.38  4352.9  316.42  4394.0  315.04  4848.9  316.49
  4956.0  318.14  4965.6  317.29  4984.3  306.45  4986.8  305.95  5009.3  306.45
  5027.3  309.96  5032.5  318.27  5156.5  316.65  5634.5  313.78  5761.4  317.42
  6106.7  316.41  6335.7  329.46  6718.8  329.40  6985.4  336.72  7047.4  338.04
#Mann=16,-1,0
  2948.4     0.1       0  3034.3    0.12       0  3141.2     0.1       0
  3265.4    0.12       0  3514.9    0.05       0  3615.4    0.12       0
  3715.9    0.05       0  3883.1    0.12       0  3986.4    0.05       0
  4352.9    0.12       0  4394.0    0.05       0  4848.9    0.12       0
  4984.3    0.07       0  5009.3    0.12       0  5156.5    0.05       0
  6985.4    0.12       0
Bank Sta=4984.3,5009.3
Exp/Cntr=0.3,0.1

Type RM Length L Ch R = 1,46297,947,947,947
BEGIN DESCRIPTION:
Walnut Creek 55.5
END DESCRIPTION:
XS GIS Cut Line= 4
      2750886.96      6747771.51      2750748.12      6749987.14
      2750400.84      6750781.47      2750472.54      6751696.97
#Sta/Elev= 30
  3758.1  351.33  3913.6  344.71  4152.9  323.51  4198.5  319.57  4280.6  317.78
  4476.6  316.76  4770.6  315.05  4813.7  316.02  4829.7  309.63  4839.7  315.82
  4889.8  314.47  4959.9  316.99  4968.8  309.74  4973.8  312.54  4977.5  304.09
  4980.0  303.59  5002.5  304.09  5010.0  315.38  5020.1  317.12  5330.1  313.55
  6253.5  318.28  6422.3  320.63  6429.8  319.12  6440.2  311.11  6451.6  320.76
  6506.1  320.21  7236.0  320.48  7396.2  326.46  7613.7  343.06  7763.3  349.42
#Mann=11,-1,0
  3758.1    0.12       0  3913.6     0.1       0  4152.9    0.05       0
  4280.6    0.12       0  4476.6    0.05       0  4770.6    0.12       0
  4977.5    0.07       0  5002.5    0.12       0  5330.1    0.05       0
  6253.5    0.12       0  6506.1    0.05       0
Bank Sta=4977.5,5002.5
Exp/Cntr=0.3,0.1

Type RM Length L Ch R = 1,45350,1130,1130,1130
BEGIN DESCRIPTION:
Walnut Creek 55.0
END DESCRIPTION:
XS GIS Cut Line= 3
      2750366.12      6746712.50      2749966.82      6749794.07
      2749572.91      6750786.52
#Sta/Elev= 30
  2883.8  355.93  2902.5  358.21  2963.0  338.52  2999.9  336.18  3033.5  343.13
  3391.0  343.32  4282.2  321.38  4854.8  315.74  5009.9  315.43  5027.7  303.13
  5030.2  302.63  5052.7  303.13  5070.4  316.48  5178.4  313.64  5183.4  304.74
  5201.5  315.40  5243.5  315.13  5635.1  315.41  5675.4  304.07  5695.6  316.12
  6013.8  314.74  6143.6  315.41  6201.2  315.65  6248.0  316.02  6344.5  312.81
  6590.3  318.71  6658.9  309.83  6683.2  319.16  6770.1  318.29  7058.9  328.43
#Mann=12,-1,0
  2883.8    0.05       0  4282.2    0.12       0  4854.8     0.1       0
  5027.7    0.07       0  5052.7     0.1       0  5243.5    0.12       0
  6013.8     0.1       0  6143.6    0.05       0  6201.2    0.12       0
  6248.0    0.05       0  6344.5    0.12       0  6770.1    0.05       0
Bank Sta=5027.7,5052.7
Exp/Cntr=0.3,0.1

Type RM Length L Ch R = 1,44220,698,698,698
BEGIN DESCRIPTION:
Walnut Creek 54.0
END DESCRIPTION:
XS GIS Cut Line= 3
      2750004.14      6747865.26      2749184.70      6749969.42
      2748893.68      6750582.68
#Sta/Elev= 30
  3286.6  339.21  3335.7  338.07  3484.4  324.88  3514.2  320.72  3574.0  317.31
  3646.8  316.56  3668.4  316.59  3689.8  313.14  3722.0  315.23  3928.2  312.30
  3968.8  311.51  3990.3  313.97  4016.0  313.71  4539.1  311.75  4820.3  313.58
  4956.2  314.48  4966.9  310.04  4975.8  301.19  4978.3  300.69  5000.8  301.19
  5009.8  304.35  5020.5  311.72  5028.6  314.12  5073.7  313.32  5172.6  312.10
  5474.4  312.92  5717.3  318.25  5823.2  317.72  5911.7  315.21  6223.5  316.76
#Mann=8,-1,0
  3286.6    0.05       0  3646.8    0.12       0  3928.2     0.1       0
  4016.0    0.05       0  4820.3    0.12       0  4975.8    0.07       0
  5000.8    0.12       0  5073.7    0.05       0
Bank Sta=4975.8,5000.8
Exp/Cntr=0.3,0.1

Type RM Length L Ch R = 1,43522,665,665,665
BEGIN DESCRIPTION:
Walnut Creek 53.0
END DESCRIPTION:
XS GIS Cut Line= 4
      2749962.46      6747781.93      2748677.76      6749316.64
      2748242.77      6749853.38      2748479.63      6750163.18
#Sta/Elev= 30
  3427.8  344.23  3445.9  344.47  3538.3  336.72  3680.1  321.33  3772.5  315.67
  3864.9  313.13  4574.2  310.64  4940.0  312.72  4965.4  313.50  4978.7  306.88
  4980.5  301.17  4983.0  300.67  5005.5  301.17  5029.4  311.50  5056.2  312.82
  5128.3  311.32  5142.6  313.38  5233.3  312.33  5390.9  310.73  5450.6  309.95
  5511.8  310.32  5640.4  310.21  5661.2  308.34  5725.2  310.73  5896.2  308.55
  6001.8  309.64  6089.7  314.56  6149.4  317.35  6299.0  315.66  6510.1  319.47
#Mann=10,-1,0
  3427.8    0.05       0  4940.0    0.12       0  4980.5    0.07       0
  5005.5    0.12       0  5056.2     0.1       0  5233.3    0.05       0
  5390.9    0.12       0  5450.6    0.05       0  5511.8    0.12       0
  6089.7    0.05       0
Bank Sta=4980.5,5005.5
Exp/Cntr=0.3,0.1

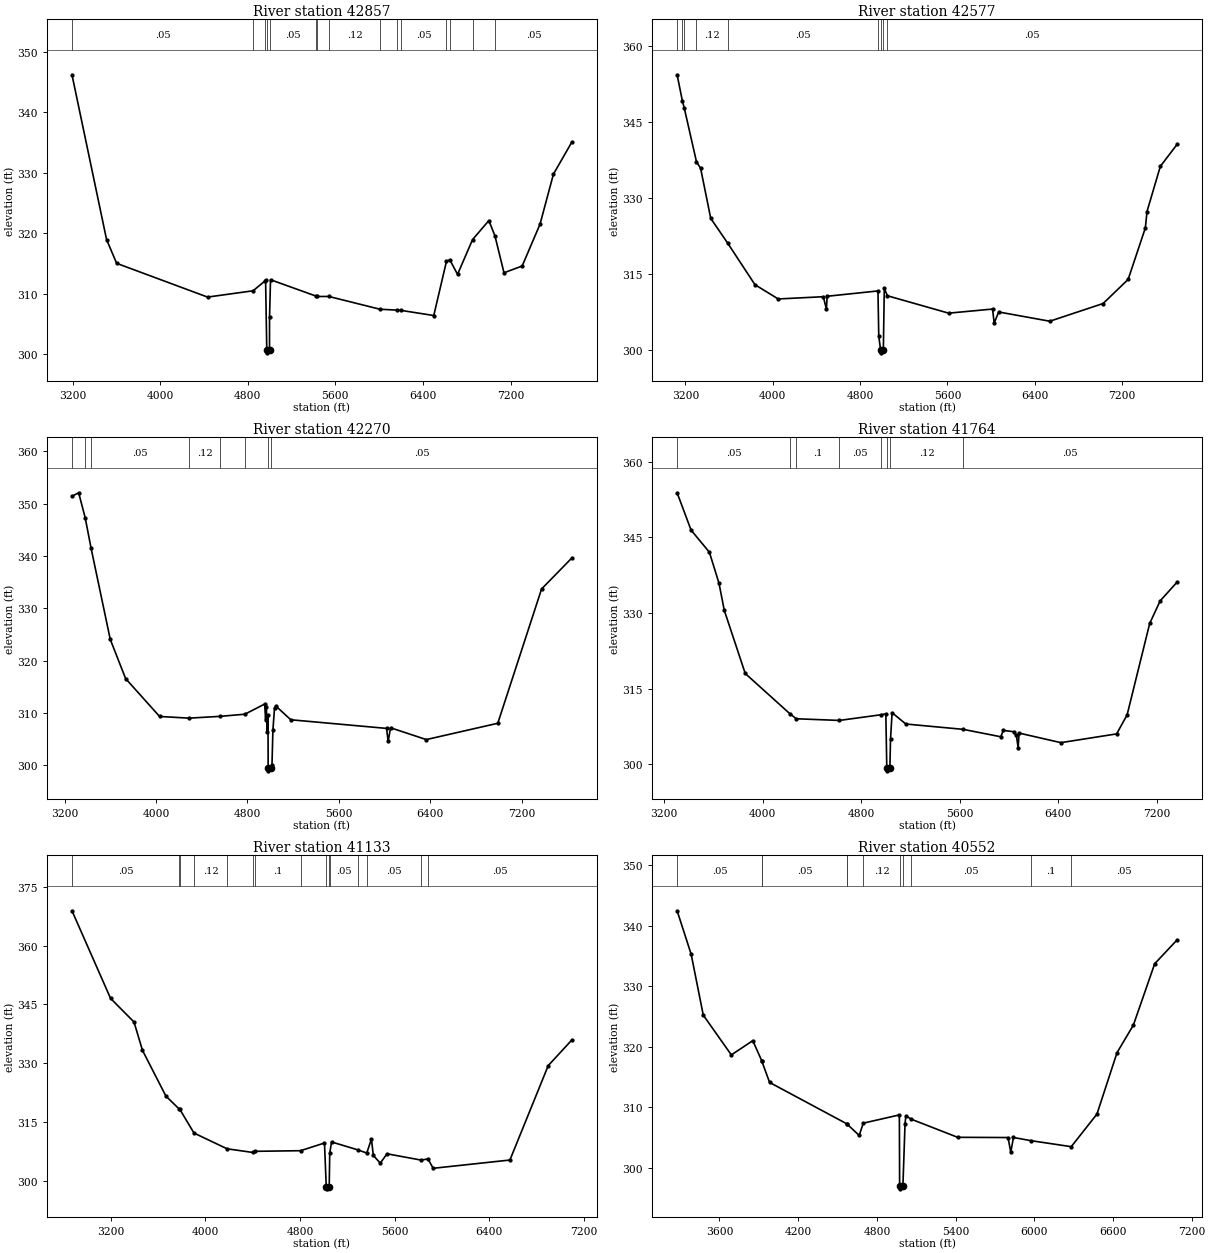
Type RM Length L Ch R = 1,42857,280,280,280
BEGIN DESCRIPTION:
Walnut Creek 52.0
END DESCRIPTION:
XS GIS Cut Line= 4
      2749955.53      6747719.42      2748594.42      6748712.47
      2747172.63      6749668.44      2746574.94      6750671.05
#Sta/Elev= 30
  3195.1  346.17  3510.9  318.93  3603.0  314.99  4433.2  309.41  4848.9  310.45
  4953.5  312.01  4963.2  312.23  4974.0  300.69  4976.5  300.19  4999.0  300.69
  4999.2  306.08  5008.2  312.28  5421.4  309.59  5433.3  309.51  5541.4  309.51
  6007.8  307.40  6167.7  307.25  6203.7  307.20  6499.0  306.36  6615.1  315.33
  6645.6  315.58  6716.0  313.16  6853.7  318.93  7002.2  322.06  7057.8  319.52
  7140.4  313.43  7306.4  314.55  7469.4  321.47  7592.0  329.75  7760.5  335.06
#Mann=15,-1,0
  3195.1    0.05       0  4848.9    0.12       0  4953.5    0.05       0
  4974.0    0.04       0  4999.0    0.05       0  5421.4    0.12       0
  5433.3    0.05       0  5541.4    0.12       0  6007.8    0.05       0
  6167.7    0.12       0  6203.7    0.05       0  6615.1    0.12       0
  6645.6    0.05       0  6853.7    0.12       0  7057.8    0.05       0
Bank Sta=4974,4999
Exp/Cntr=0.3,0.1

Type RM Length L Ch R = 1,42577,307,307,307
BEGIN DESCRIPTION:
Walnut Creek 51.8
END DESCRIPTION:
XS GIS Cut Line= 3
      2749788.88      6747441.63      2748608.31      6748386.08
      2746094.40      6750143.05
#Sta/Elev= 30
  3124.3  354.25  3172.5  349.09  3190.1  347.66  3301.6  337.10  3339.3  335.83
  3432.2  325.95  3585.8  321.12  3837.2  312.88  4050.1  310.07  4463.1  310.51
  4491.9  308.05  4498.3  310.60  4963.8  311.65  4971.1  302.79  4988.2  299.95
  4990.7  299.45  5013.2  299.95  5021.7  312.15  5050.3  310.70  5611.2  307.27
  6013.3  308.08  6028.1  305.34  6070.0  307.50  6537.4  305.68  7025.8  309.17
  7255.2  313.92  7413.1  324.09  7427.9  327.30  7550.0  336.20  7703.2  340.53
#Mann=9,-1,0
  3124.3    0.05       0  3172.5    0.12       0  3190.1    0.05       0
  3301.6    0.12       0  3585.8    0.05       0  4963.8     0.1       0
  4988.2    0.07       0  5013.2     0.1       0  5050.3    0.05       0
Bank Sta=4988.2,5013.2
Exp/Cntr=0.3,0.1

Type RM Length L Ch R = 1,42270,506,506,506
BEGIN DESCRIPTION:
Walnut Creek 51.0
END DESCRIPTION:
XS GIS Cut Line= 3
      2749268.06      6747149.94      2748177.76      6748344.42
      2746045.79      6750094.44
#Sta/Elev= 30
  3264.1  351.44  3322.8  352.10  3380.5  347.25  3430.7  341.56  3599.1  324.06
  3733.5  316.56  4030.8  309.31  4289.2  308.99  4558.4  309.33  4777.0  309.74
  4950.8  311.69  4958.7  308.69  4965.2  311.07  4973.1  306.28  4979.5  309.60
  4981.4  299.41  4983.9  298.91  5006.4  299.41  5014.7  300.06  5022.6  306.67
  5036.9  310.95  5051.3  311.25  5179.0  308.68  6017.2  307.03  6031.5  304.54
  6052.3  307.15  6365.2  304.89  6990.9  308.01  7374.1  333.70  7639.6  339.64
#Mann=8,-1,0
  3264.1    0.12       0  3380.5     0.1       0  3430.7    0.05       0
  4289.2    0.12       0  4558.4    0.05       0  4777.0    0.12       0
  4981.4    0.07       0  5006.4    0.05       0
Bank Sta=4981.4,5006.4
Exp/Cntr=0.3,0.1

Type RM Length L Ch R = 1,41764,631,631,631
BEGIN DESCRIPTION:
Walnut Creek 50.0
END DESCRIPTION:
XS GIS Cut Line= 4
      2748788.88      6746844.41      2747754.15      6748073.58
      2747726.37      6748226.36      2746178.52      6749926.91
#Sta/Elev= 30
  3304.5  353.87  3417.7  346.47  3566.6  342.08  3644.6  335.93  3687.5  330.56
  3857.9  318.02  4219.1  310.07  4272.6  309.04  4622.2  308.71  4959.5  309.83
  5000.1  310.00  5007.9  299.21  5010.4  298.71  5032.9  299.21  5038.1  304.93
  5050.9  310.25  5162.1  308.00  5628.3  306.94  5933.8  305.47  5954.7  306.73
  6039.9  306.47  6060.8  305.73  6075.0  303.28  6082.4  306.20  6422.3  304.30
  6875.0  306.04  6960.2  309.80  7143.9  327.96  7229.1  332.44  7366.0  336.14
#Mann=8,-1,0
  3304.5    0.05       0  4219.1    0.12       0  4272.6     0.1       0
  4622.2    0.05       0  4959.5    0.12       0  5007.9    0.07       0
  5032.9    0.12       0  5628.3    0.05       0
Bank Sta=5007.9,5032.9
Exp/Cntr=0.3,0.1

Type RM Length L Ch R = 1,41133,581,581,581
BEGIN DESCRIPTION:
Walnut Creek 49.0
END DESCRIPTION:
XS GIS Cut Line= 3
      2748575.99      6746461.01      2747176.00      6748061.00
      2746163.88      6749899.95
#Sta/Elev= 30
  2873.7  368.86  3199.7  346.52  3398.1  340.48  3469.3  333.27  3667.6  321.59
  3781.8  318.23  3785.2  318.20  3905.0  312.16  4184.0  308.15  4399.7  307.22
  4422.7  307.50  4805.2  307.66  5007.8  309.62  5022.7  298.43  5025.2  297.93
  5047.7  298.43  5052.1  307.01  5067.4  309.89  5289.8  307.87  5365.0  307.06
  5404.5  310.61  5420.6  306.45  5479.1  304.48  5536.2  306.87  5824.7  305.26
  5882.3  305.56  5926.3  303.17  6574.9  305.28  6898.8  329.37  7098.8  335.92
#Mann=15,-1,0
  2873.7    0.05       0  3781.8    0.12       0  3785.2     0.1       0
  3905.0    0.12       0  4184.0     0.1       0  4399.7    0.12       0
  4422.7     0.1       0  4805.2    0.12       0  5022.7    0.07       0
  5047.7    0.12       0  5052.1    0.05       0  5289.8    0.12       0
  5365.0    0.05       0  5824.7    0.12       0  5882.3    0.05       0
Bank Sta=5022.7,5047.7
Exp/Cntr=0.3,0.1

Type RM Length L Ch R = 1,40552,505,505,505
BEGIN DESCRIPTION:
Walnut Creek 48.0
END DESCRIPTION:
XS GIS Cut Line= 3
      2747779.29      6746594.45      2746654.32      6748021.50
      2746115.26      6749941.62
#Sta/Elev= 30
  3277.0  342.45  3384.1  335.26  3476.3  325.20  3690.3  318.62  3853.9  320.98
  3921.8  317.67  3922.8  317.58  3982.1  314.07  4572.3  307.21  4573.9  307.16
  4665.2  305.31  4696.4  307.34  4971.4  308.70  4973.4  296.98  4975.9  296.48
  4998.4  296.98  5014.7  307.28  5021.1  308.54  5063.7  307.98  5415.6  305.00
  5799.9  304.96  5820.7  302.54  5841.3  304.97  5975.6  304.44  6281.9  303.45
  6477.8  308.84  6630.8  318.99  6755.5  323.55  6917.9  333.69  7088.5  337.63
#Mann=11,-1,0
  3277.0    0.05       0  3921.8     0.1       0  3922.8    0.05       0
  4572.3    0.12       0  4573.9     0.1       0  4696.4    0.12       0
  4973.4    0.07       0  4998.4    0.12       0  5063.7    0.05       0
  5975.6     0.1       0  6281.9    0.05       0
Bank Sta=4973.4,4998.4
Exp/Cntr=0.3,0.1

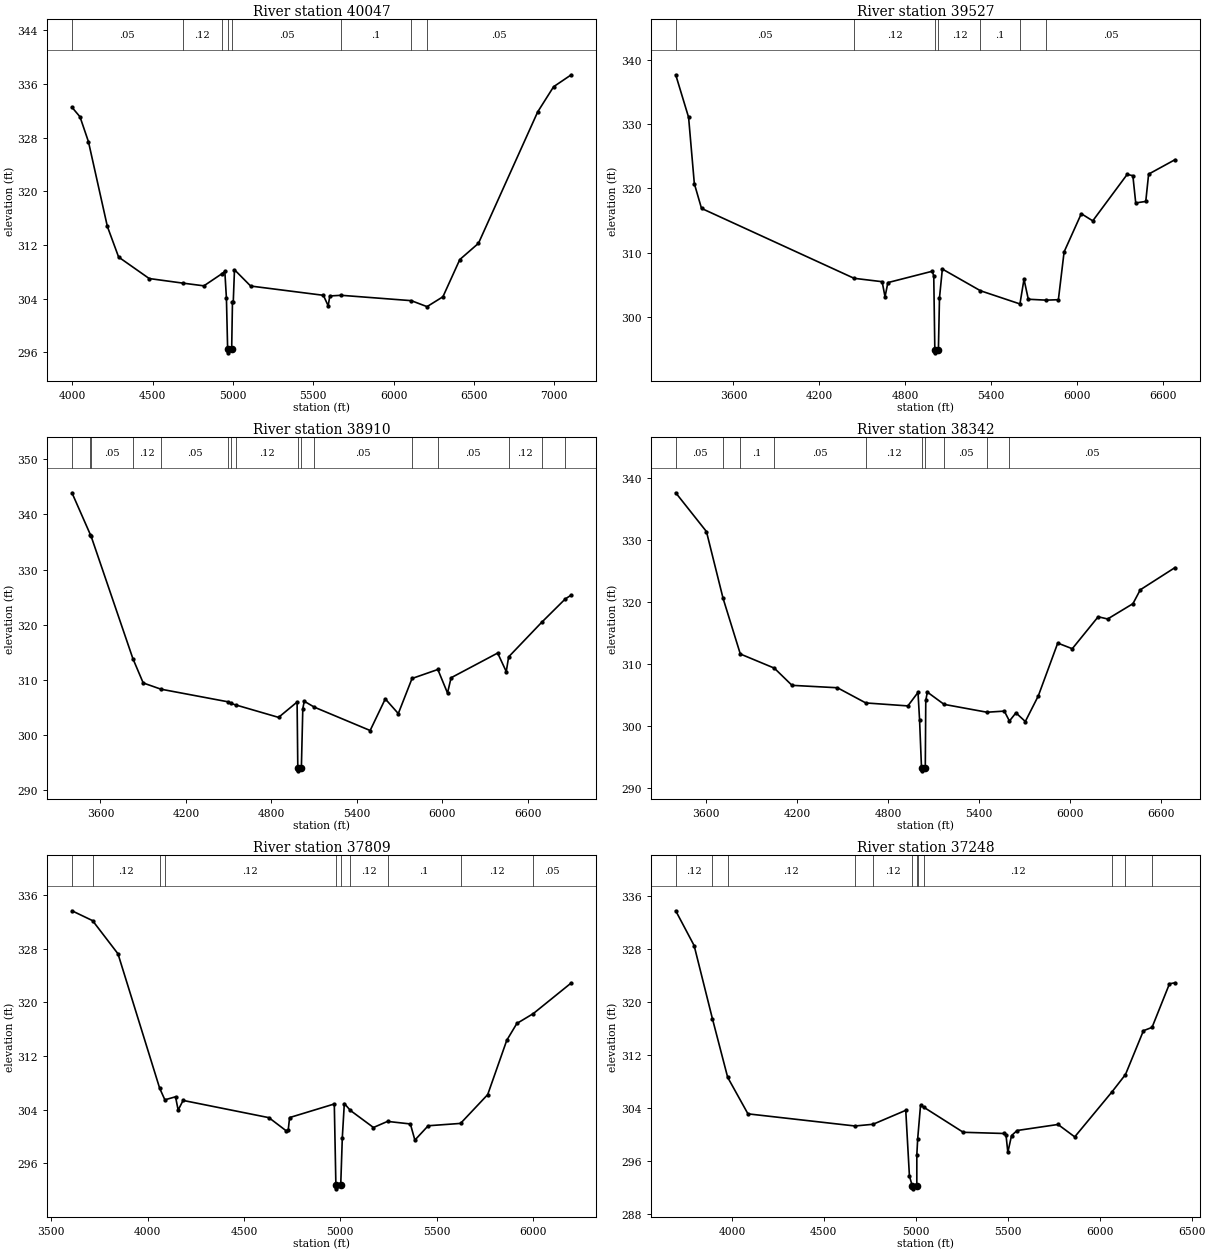
Type RM Length L Ch R = 1,40047,520,520,520
BEGIN DESCRIPTION:
Walnut Creek 47.0
END DESCRIPTION:
XS GIS Cut Line= 3
      2746326.00      6746860.97      2746276.00      6747861.00
      2746059.71      6749955.48
#Sta/Elev= 30
  3998.7  332.53  4048.8  331.10  4101.4  327.39  4219.0  314.76  4289.1  310.19
  4479.3  306.99  4686.9  306.31  4819.8  305.90  4933.3  307.73  4949.9  308.06
  4959.9  304.04  4967.5  296.41  4970.0  295.91  4992.5  296.41  4997.5  303.55
  5002.5  303.55  5010.0  308.30  5110.6  305.87  5563.0  304.49  5593.1  302.92
  5603.2  304.39  5673.8  304.49  6109.9  303.69  6208.1  302.80  6306.9  304.27
  6412.0  309.82  6528.1  312.24  6896.7  331.84  6995.6  335.59  7105.6  337.37
#Mann=8,-1,0
  3998.7    0.05       0  4686.9    0.12       0  4933.3    0.05       0
  4967.5    0.05       0  4992.5    0.05       0  5673.8     0.1       0
  6109.9    0.12       0  6208.1    0.05       0
Bank Sta=4967.5,4992.5
Exp/Cntr=0.3,0.1

Type RM Length L Ch R = 1,39527,617,617,617
BEGIN DESCRIPTION:
Walnut Creek 46.0
END DESCRIPTION:
XS GIS Cut Line= 3
      2745930.36      6746261.11      2745831.40      6747959.00
      2745758.49      6749745.44
#Sta/Elev= 30
  3196.3  337.68  3286.3  331.06  3326.4  320.74  3376.5  316.89  4442.4  306.01
  4638.6  305.48  4658.7  303.13  4678.7  305.34  4989.2  307.11  4999.2  306.36
  5006.7  294.91  5009.2  294.41  5031.7  294.91  5039.2  302.96  5059.2  307.45
  5325.6  304.07  5601.3  302.02  5629.7  305.86  5659.7  302.75  5783.5  302.61
  5869.9  302.68  5909.9  310.12  6030.0  316.06  6110.1  314.95  6350.3  322.17
  6390.3  321.98  6410.3  317.74  6480.4  317.97  6500.4  322.22  6685.0  324.47
#Mann=7,-1,0
  3196.3    0.05       0  4442.4    0.12       0  5006.7    0.07       0
  5031.7    0.12       0  5325.6     0.1       0  5601.3    0.12       0
  5783.5    0.05       0
Bank Sta=5006.7,5031.7
Exp/Cntr=0.3,0.1

Type RM Length L Ch R = 1,38910,568,568,568
BEGIN DESCRIPTION:
Walnut Creek 45.0
END DESCRIPTION:
XS GIS Cut Line= 3
      2745326.00      6746360.98      2745276.00      6747961.00
      2745482.45      6749854.88
#Sta/Elev= 30
  3399.6  343.93  3529.3  336.32  3534.7  336.01  3827.2  313.89  3899.9  309.46
  4024.4  308.33  4495.8  306.04  4514.1  305.76  4549.1  305.48  4850.3  303.22
  4980.4  306.00  4985.4  294.03  4987.9  293.53  5010.4  294.03  5020.5  304.80
  5030.6  306.14  5102.6  305.06  5493.3  300.84  5599.6  306.57  5691.0  303.91
  5787.4  310.27  5968.6  311.90  6036.5  307.63  6061.6  310.40  6388.6  314.88
  6448.9  311.52  6465.8  314.19  6697.3  320.44  6863.4  324.69  6905.5  325.39
#Mann=16,-1,0
  3399.6    0.05       0  3529.3    0.12       0  3534.7    0.05       0
  3827.2    0.12       0  4024.4    0.05       0  4495.8    0.12       0
  4514.1    0.05       0  4549.1    0.12       0  4985.4    0.07       0
  5010.4    0.12       0  5102.6    0.05       0  5787.4    0.12       0
  5968.6    0.05       0  6465.8    0.12       0  6697.3    0.05       0
  6863.4    0.12       0
Bank Sta=4985.4,5010.4
Exp/Cntr=0.3,0.1

Type RM Length L Ch R = 1,38342,533,533,533
BEGIN DESCRIPTION:
Walnut Creek 44.0
END DESCRIPTION:
XS GIS Cut Line= 4
      2745070.98      6746318.39      2744737.65      6746854.83
      2744748.07      6747755.88      2745143.90      6749474.61
#Sta/Elev= 30
  3398.3  337.61  3601.2  331.35  3711.1  320.56  3824.8  311.59  4049.0  309.31
  4166.0  306.53  4466.1  306.14  4653.0  303.69  4931.0  303.21  4997.8  305.39
  5008.1  300.98  5020.9  293.23  5023.4  292.73  5045.9  293.23  5049.1  304.09
  5059.4  305.44  5169.8  303.46  5452.9  302.19  5567.6  302.37  5601.4  300.77
  5644.3  302.09  5706.2  300.69  5791.9  304.82  5920.3  313.35  6016.1  312.44
  6187.3  317.60  6249.7  317.24  6416.7  319.71  6465.2  321.95  6694.7  325.54
#Mann=10,-1,0
  3398.3    0.05       0  3711.1    0.12       0  3824.8     0.1       0
  4049.0    0.05       0  4653.0    0.12       0  5020.9    0.07       0
  5045.9    0.12       0  5169.8    0.05       0  5452.9    0.12       0
  5601.4    0.05       0
Bank Sta=5020.9,5045.9
Exp/Cntr=0.3,0.1

Type RM Length L Ch R = 1,37809,561,561,561
BEGIN DESCRIPTION:
Walnut Creek 43.0
END DESCRIPTION:
XS GIS Cut Line= 3
      2743925.16      6746620.47      2744315.78      6748011.08
      2744776.01      6749061.01
#Sta/Elev= 30
  3607.8  333.68  3714.8  332.21  3846.7  327.26  4062.9  307.21  4089.9  305.48
  4145.2  305.93  4158.9  303.95  4184.5  305.39  4629.6  302.82  4719.8  300.85
  4730.1  300.99  4737.0  302.83  4969.0  304.86  4977.3  292.70  4979.8  292.20
  5002.3  292.70  5010.6  299.82  5021.0  304.93  5052.7  303.89  5172.2  301.35
  5245.1  302.26  5363.7  301.88  5387.1  299.47  5456.1  301.61  5624.0  301.96
  5765.0  306.26  5863.9  314.36  5916.2  316.87  6001.4  318.34  6198.6  322.92
#Mann=10,-1,0
  3607.8    0.05       0  3714.8    0.12       0  4062.9    0.05       0
  4089.9    0.12       0  4977.3    0.07       0  5002.3    0.12       0
  5052.7    0.12       0  5245.1     0.1       0  5624.0    0.12       0
  6001.4    0.05       0
Bank Sta=4977.3,5002.3
Exp/Cntr=0.3,0.1

Type RM Length L Ch R = 1,37248,536,536,536
BEGIN DESCRIPTION:
Walnut Creek 42.0
END DESCRIPTION:
XS GIS Cut Line= 3
      2743926.00      6746761.00      2743876.00      6748061.00
      2744076.00      6749461.03
#Sta/Elev= 30
  3694.5  333.74  3794.6  328.50  3893.9  317.50  3977.1  308.64  4087.3  303.14
  4669.6  301.31  4767.6  301.57  4945.4  303.67  4965.4  293.75  4980.5  292.34
  4983.0  291.84  5005.5  292.34  5005.6  296.95  5010.2  299.35  5025.8  304.44
  5045.6  304.10  5258.1  300.36  5480.3  300.18  5490.4  299.99  5500.5  297.34
  5520.7  299.87  5551.0  300.63  5773.3  301.54  5864.2  299.67  6067.0  306.46
  6140.1  309.06  6237.9  315.67  6284.6  316.17  6379.4  322.74  6409.7  322.89
#Mann=12,-1,0
  3694.5    0.12       0  3893.9    0.05       0  3977.1    0.12       0
  4669.6     0.1       0  4767.6    0.12       0  4980.5    0.07       0
  5005.5    0.12       0  5010.2     0.1       0  5045.6    0.12       0
  6067.0    0.05       0  6140.1    0.12       0  6284.6    0.05       0
Bank Sta=4980.5,5005.5
Exp/Cntr=0.3,0.1