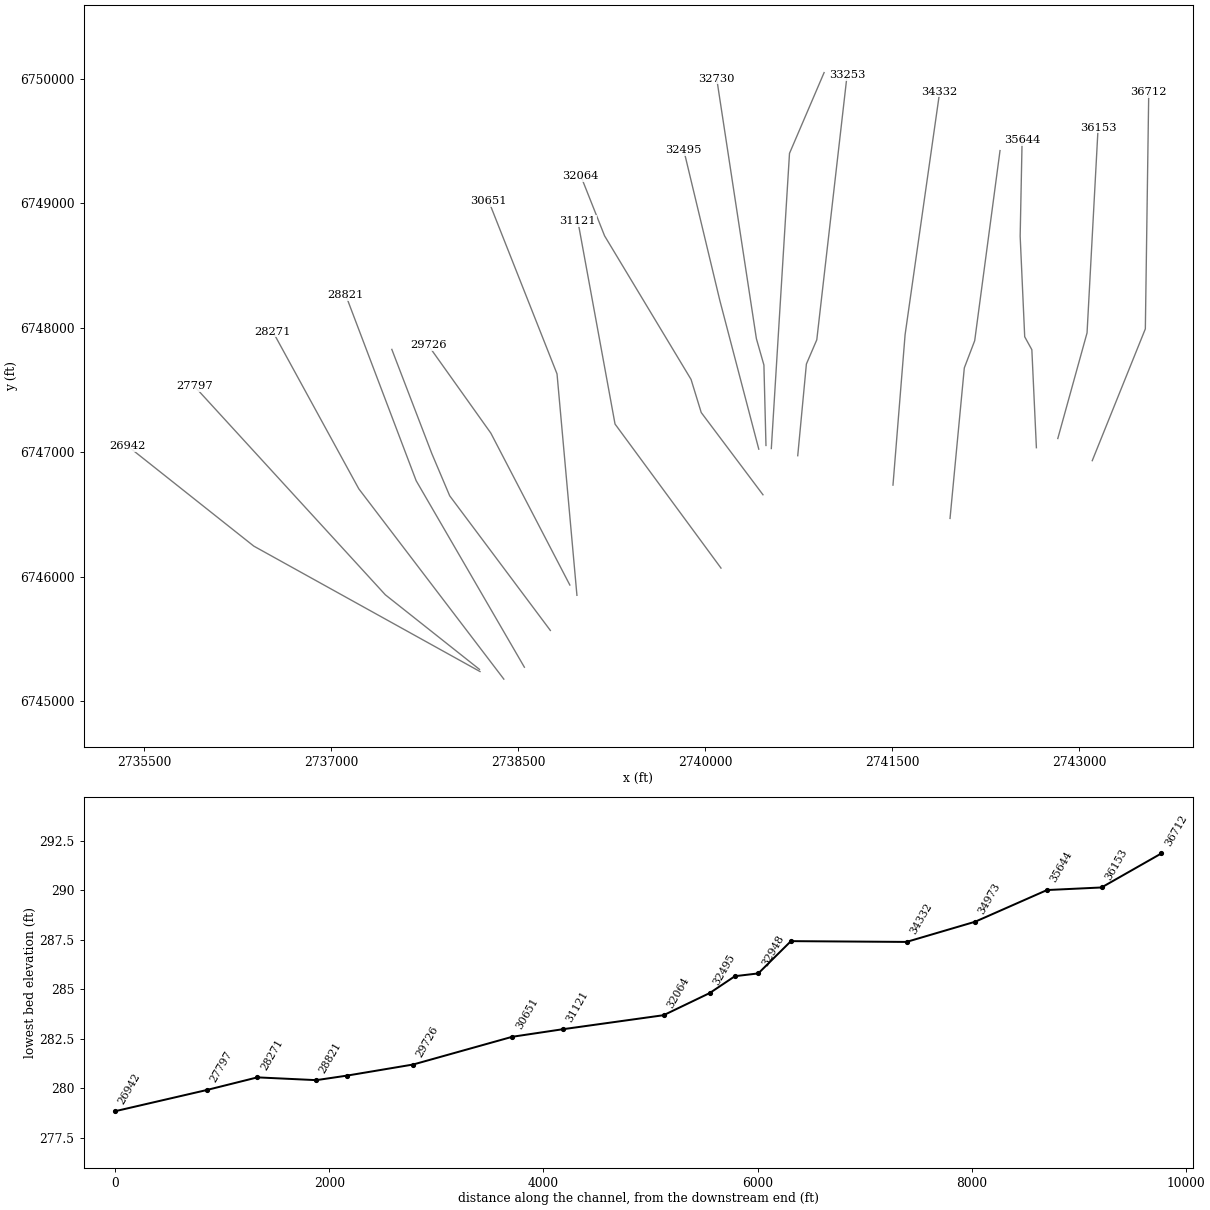
HEC-RAS study Walnut Creek.prj: Walnut Creek Base Level Engineering

--- Walnut Creek.g01 (geometry) --- (continued)

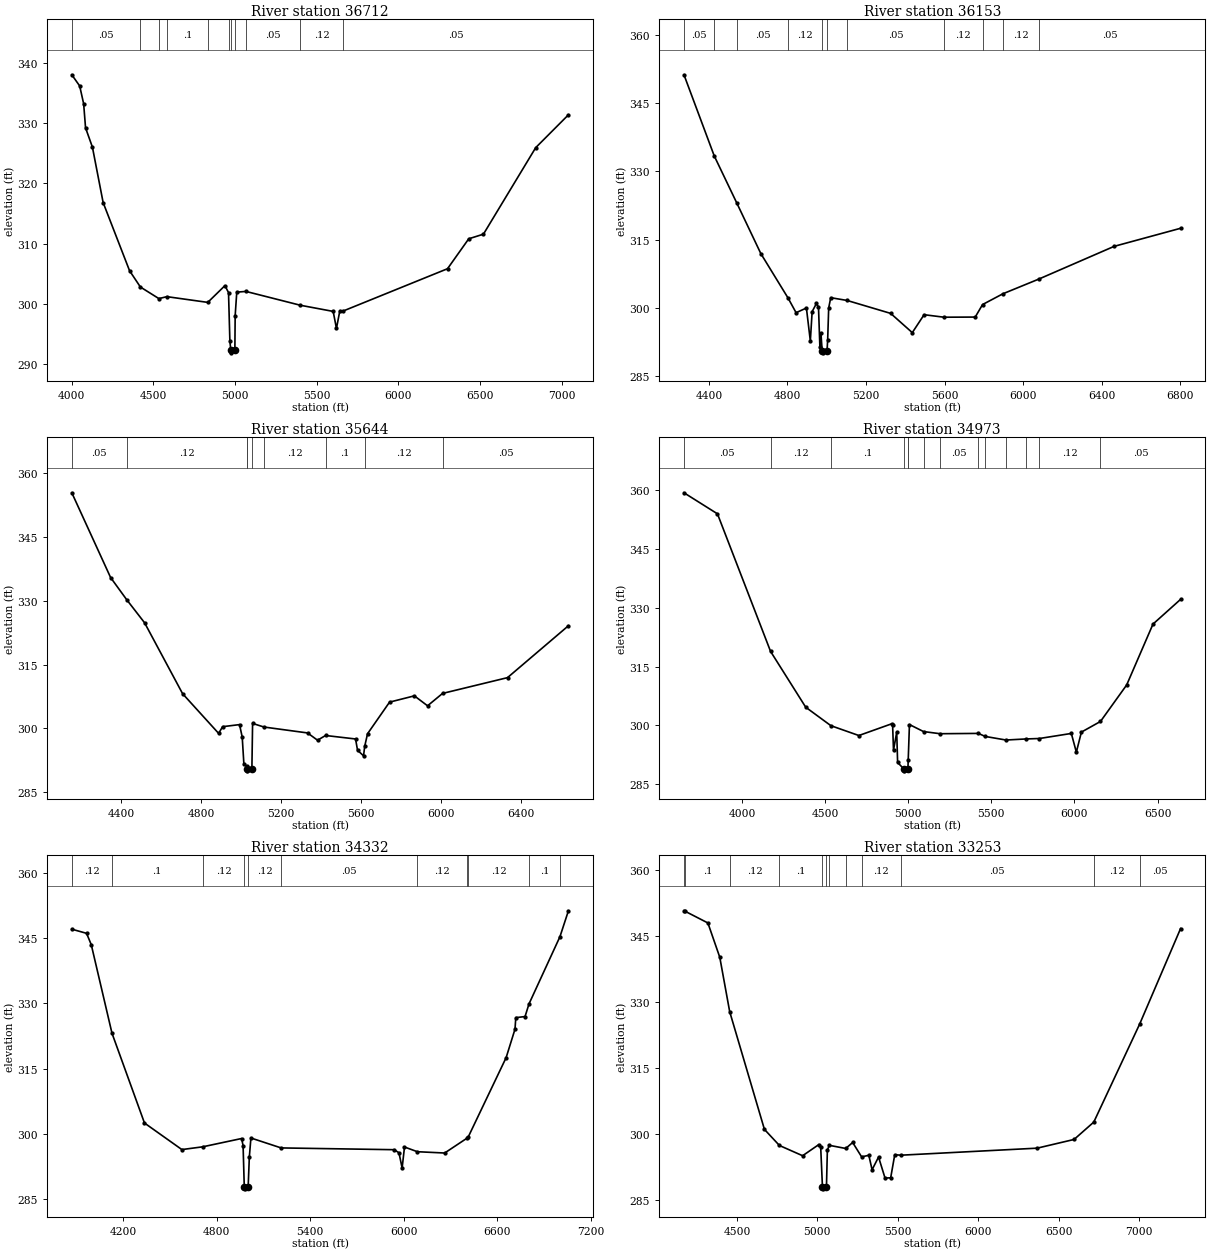
Type RM Length L Ch R = 1,36712,559,559,559
BEGIN DESCRIPTION:
Walnut Creek 41.0
END DESCRIPTION:
XS GIS Cut Line= 3
      2743102.25      6746932.98      2743528.08      6747991.21
      2743555.36      6749891.32
#Sta/Elev= 30
  3999.8  338.04  4048.1  336.18  4072.3  333.23  4083.9  329.23  4126.0  326.02
  4191.7  316.81  4353.4  305.50  4419.8  302.79  4532.9  300.87  4582.1  301.19
  4832.3  300.24  4937.4  303.02  4959.4  301.87  4967.8  293.77  4973.3  292.36
  4975.8  291.86  4998.3  292.36  5000.1  298.02  5009.9  301.94  5066.0  302.06
  5399.8  299.76  5600.3  298.74  5620.3  295.91  5640.3  298.74  5660.0  298.79
  6300.4  305.83  6430.4  310.80  6520.4  311.57  6840.5  325.94  7040.8  331.39
#Mann=11,-1,0
  3999.8    0.05       0  4419.8    0.12       0  4532.9    0.05       0
  4582.1     0.1       0  4832.3    0.12       0  4959.4     0.1       0
  4973.3    0.07       0  4998.3     0.1       0  5066.0    0.05       0
  5399.8    0.12       0  5660.0    0.05       0
Bank Sta=4973.3,4998.3
Exp/Cntr=0.3,0.1

Type RM Length L Ch R = 1,36153,509,509,509
BEGIN DESCRIPTION:
Walnut Creek 40.0
END DESCRIPTION:
XS GIS Cut Line= 3
      2742825.99      6747110.97      2743060.57      6747959.00
      2743149.11      6749604.85
#Sta/Elev= 30
  4273.3  351.24  4427.5  333.40  4542.0  323.08  4664.8  311.93  4803.1  302.19
  4844.0  298.96  4896.6  299.99  4916.6  292.75  4925.8  299.20  4947.7  301.00
  4958.1  300.19  4965.3  291.33  4970.5  294.50  4976.7  290.64  4979.2  290.14
  5001.7  290.64  5004.8  292.94  5010.0  300.00  5020.4  302.26  5103.7  301.65
  5325.4  298.81  5435.6  294.58  5495.7  298.52  5596.8  297.97  5756.0  298.00
  5793.3  300.75  5897.0  303.12  6078.2  306.32  6463.2  313.54  6801.4  317.51
#Mann=11,-1,0
  4273.3    0.05       0  4427.5    0.12       0  4542.0    0.05       0
  4803.1    0.12       0  4976.7    0.07       0  5001.7    0.12       0
  5103.7    0.05       0  5596.8    0.12       0  5793.3    0.05       0
  5897.0    0.12       0  6078.2    0.05       0
Bank Sta=4976.7,5001.7
Exp/Cntr=0.3,0.1

Type RM Length L Ch R = 1,35644,671,671,671
BEGIN DESCRIPTION:
Walnut Creek 39.0
END DESCRIPTION:
XS GIS Cut Line= 5
      2742654.32      6747037.13      2742617.86      6747823.58
      2742560.57      6747927.75      2742524.11      6748735.04
      2742539.74      6749505.89
#Sta/Elev= 30
  4153.6  355.38  4347.7  335.46  4427.9  330.27  4517.9  324.81  4708.1  308.14
  4888.3  298.82  4908.3  300.39  4993.0  300.88  5006.4  297.95  5014.8  291.58
  5028.2  291.15  5029.8  290.51  5032.3  290.01  5054.8  290.51  5058.3  301.16
  5115.0  300.31  5333.3  298.92  5383.4  297.21  5423.6  298.32  5573.6  297.50
  5583.6  294.84  5613.6  293.54  5619.5  295.81  5633.6  298.73  5743.7  306.16
  5867.9  307.64  5933.9  305.30  6009.0  308.21  6334.0  311.92  6638.9  324.12
#Mann=9,-1,0
  4153.6    0.05       0  4427.9    0.12       0  5028.2    0.05       0
  5029.8    0.07       0  5054.8    0.05       0  5115.0    0.12       0
  5423.6     0.1       0  5619.5    0.12       0  6009.0    0.05       0
Bank Sta=5029.8,5054.8
Exp/Cntr=0.3,0.1

Type RM Length L Ch R = 1,34973,641,641,641
BEGIN DESCRIPTION:
Walnut Creek 38.0
END DESCRIPTION:
XS GIS Cut Line= 4
      2741961.61      6746469.42      2742076.19      6747677.75
      2742159.53      6747896.50      2742362.65      6749422.50
#Sta/Elev= 30
  3651.3  359.35  3852.7  353.98  4172.2  318.88  4383.7  304.64  4535.1  299.93
  4703.3  297.42  4900.6  300.41  4906.3  300.12  4911.7  293.68  4931.1  298.28
  4936.4  290.55  4973.4  288.91  4975.9  288.41  4998.4  288.91  5000.3  291.25
  5007.6  300.22  5092.3  298.43  5191.9  297.88  5422.3  297.96  5462.9  297.19
  5588.4  296.27  5706.2  296.54  5789.1  296.66  5981.4  297.95  6011.6  293.17
  6041.9  298.29  6156.8  301.01  6314.3  310.32  6472.6  325.85  6638.6  332.16
#Mann=14,-1,0
  3651.3    0.05       0  4172.2    0.12       0  4535.1     0.1       0
  4973.4    0.07       0  4998.4     0.1       0  5000.3    0.12       0
  5092.3     0.1       0  5191.9    0.05       0  5422.3    0.12       0
  5462.9    0.05       0  5588.4    0.12       0  5706.2     0.1       0
  5789.1    0.12       0  6156.8    0.05       0
Bank Sta=4973.4,4998.4
Exp/Cntr=0.3,0.1

Type RM Length L Ch R = 1,34332,1079,1079,1079
BEGIN DESCRIPTION:
Walnut Creek 37.0
END DESCRIPTION:
XS GIS Cut Line= 3
      2741504.10      6746736.73      2741601.32      6747945.05
      2741879.07      6749896.26
#Sta/Elev= 30
  3872.5  347.04  3967.1  346.09  3997.2  343.48  4130.0  323.14  4338.3  302.51
  4578.0  296.41  4710.9  297.04  4960.7  298.95  4970.3  297.34  4977.9  287.89
  4980.4  287.39  5002.9  287.89  5010.4  294.74  5020.5  299.07  5214.2  296.79
  5939.2  296.38  5969.5  295.67  5989.7  292.17  6004.9  297.00  6087.3  295.92
  6262.4  295.62  6405.6  299.03  6413.9  299.34  6656.4  317.54  6713.2  324.08
  6718.2  326.72  6777.6  326.97  6802.7  329.86  7001.3  345.32  7055.6  351.27
#Mann=11,-1,0
  3872.5    0.12       0  4130.0     0.1       0  4710.9    0.12       0
  4977.9    0.07       0  5002.9    0.12       0  5214.2    0.05       0
  6087.3    0.12       0  6405.6    0.05       0  6413.9    0.12       0
  6802.7     0.1       0  7001.3    0.05       0
Bank Sta=4977.9,5002.9
Exp/Cntr=0.3,0.1

Type RM Length L Ch R = 1,33253,305,305,305
BEGIN DESCRIPTION:
Walnut Creek 36.0
END DESCRIPTION:
XS GIS Cut Line= 4
      2740740.21      6746972.84      2740809.66      6747708.94
      2740892.99      6747903.39      2741135.91      6750027.22
#Sta/Elev= 30
  4170.4  350.66  4176.9  350.56  4319.2  347.89  4393.1  340.09  4454.8  327.71
  4670.8  300.95  4764.0  297.29  4908.3  294.96  5009.6  297.51  5020.8  296.87
  5031.6  287.93  5034.1  287.43  5056.6  287.93  5062.2  296.16  5073.7  297.33
  5176.4  296.61  5219.6  297.97  5275.3  294.70  5320.2  295.06  5340.3  291.77
  5380.6  294.66  5420.9  289.88  5456.0  289.94  5481.3  295.19  5519.5  295.08
  6367.0  296.68  6596.6  298.66  6719.2  302.61  7004.3  324.88  7259.0  346.62
#Mann=12,-1,0
  4170.4    0.05       0  4176.9     0.1       0  4454.8    0.12       0
  4764.0     0.1       0  5031.6    0.07       0  5056.6     0.1       0
  5073.7    0.12       0  5176.4    0.05       0  5275.3    0.12       0
  5519.5    0.05       0  6719.2    0.12       0  7004.3    0.05       0
Bank Sta=5031.6,5056.6
Exp/Cntr=0.3,0.1

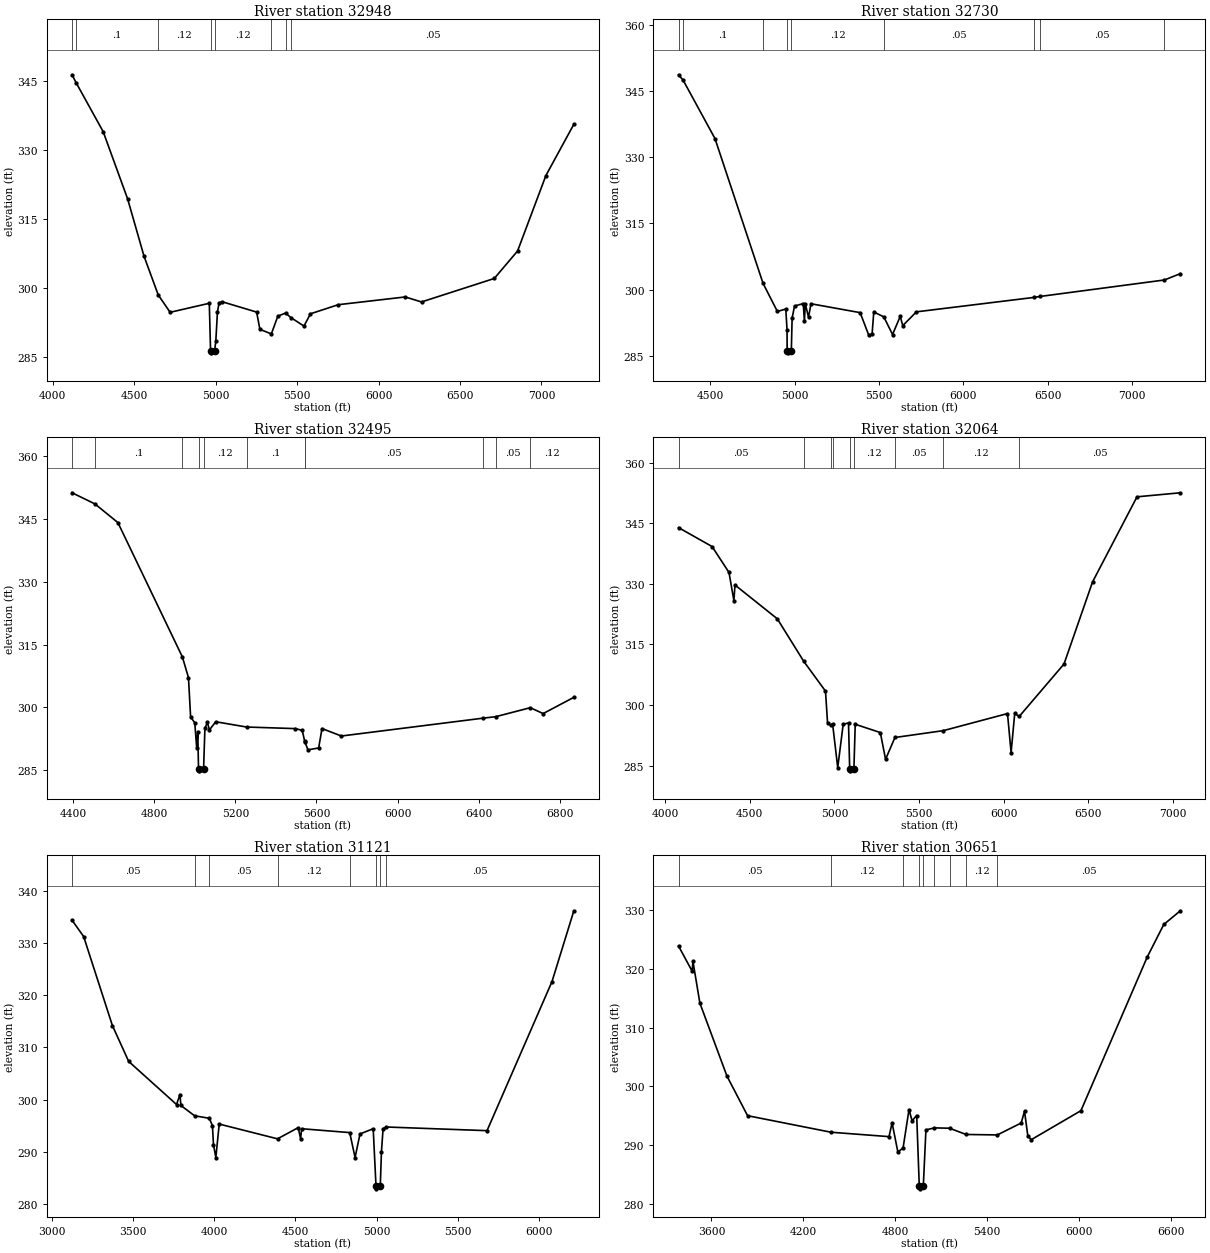
Type RM Length L Ch R = 1,32948,218,218,218
BEGIN DESCRIPTION:
Walnut Creek 35.5
END DESCRIPTION:
XS GIS Cut Line= 3
      2740528.33      6747030.44      2740674.16      6749400.27
      2740951.63      6750048.68
#Sta/Elev= 30
  4119.3  346.45  4143.6  344.76  4310.2  334.04  4460.5  319.35  4560.7  306.90
  4648.1  298.43  4721.0  294.64  4961.5  296.61  4969.2  286.30  4971.7  285.80
  4994.2  286.30  5001.5  288.35  5011.5  294.71  5021.6  296.72  5041.6  296.93
  5252.0  294.69  5272.0  290.93  5342.3  289.93  5382.2  293.80  5429.2  294.47
  5465.3  293.41  5542.5  291.64  5582.6  294.32  5752.9  296.30  6163.7  297.99
  6263.9  296.90  6710.4  302.02  6853.4  308.01  7027.4  324.48  7198.9  335.66
#Mann=8,-1,0
  4119.3    0.05       0  4143.6     0.1       0  4648.1    0.12       0
  4969.2    0.07       0  4994.2    0.12       0  5342.3    0.05       0
  5429.2    0.12       0  5465.3    0.05       0
Bank Sta=4969.2,4994.2
Exp/Cntr=0.3,0.1

Type RM Length L Ch R = 1,32730,235,235,235
BEGIN DESCRIPTION:
Walnut Creek 35.2
END DESCRIPTION:
XS GIS Cut Line= 4
      2740485.50      6747054.98      2740468.93      6747700.87
      2740408.63      6747912.35      2740090.68      6749998.35
#Sta/Elev= 30
  4311.1  348.67  4338.3  347.45  4527.2  334.22  4812.4  301.40  4897.3  295.04
  4947.3  295.58  4954.8  290.74  4955.2  286.16  4957.7  285.66  4980.2  286.16
  4984.7  293.51  4998.9  296.26  5050.9  296.83  5057.6  292.79  5062.8  296.79
  5082.1  293.73  5096.6  296.78  5388.2  294.77  5438.7  289.72  5459.0  289.88
  5469.1  294.92  5528.6  293.81  5580.4  289.81  5625.9  293.92  5641.1  291.83
  5722.0  294.95  6421.6  298.23  6456.0  298.44  7192.7  302.17  7287.2  303.61
#Mann=9,-1,0
  4311.1    0.05       0  4338.3     0.1       0  4812.4    0.12       0
  4955.2    0.07       0  4980.2    0.12       0  5528.6    0.05       0
  6421.6    0.12       0  6456.0    0.05       0  7192.7    0.12       0
Bank Sta=4955.2,4980.2
Exp/Cntr=0.3,0.1

Type RM Length L Ch R = 1,32495,431,431,431
BEGIN DESCRIPTION:
Walnut Creek 35.0
END DESCRIPTION:
XS GIS Cut Line= 3
      2740427.72      6747025.58      2740115.21      6748220.05
      2739826.37      6749425.96
#Sta/Elev= 30
  4394.9  351.32  4507.5  348.66  4620.9  344.19  4938.8  312.07  4969.0  307.11
  4979.5  297.69  5000.0  296.31  5009.6  290.29  5014.8  294.20  5018.5  285.31
  5021.0  284.81  5043.5  285.31  5050.1  294.97  5062.0  296.40  5072.4  294.61
  5103.4  296.55  5255.7  295.29  5496.2  294.91  5530.0  294.49  5541.5  292.00
  5542.6  291.82  5558.2  289.83  5610.9  290.28  5627.5  294.92  5723.1  293.14
  6421.8  297.41  6483.9  297.76  6654.6  299.91  6718.2  298.51  6869.6  302.39
#Mann=11,-1,0
  4394.9    0.05       0  4507.5     0.1       0  4938.8    0.12       0
  5018.5    0.07       0  5043.5    0.12       0  5255.7     0.1       0
  5541.5    0.12       0  5542.6    0.05       0  6421.8    0.12       0
  6483.9    0.05       0  6654.6    0.12       0
Bank Sta=5018.5,5043.5
Exp/Cntr=0.3,0.1

Type RM Length L Ch R = 1,32064,943,943,943
BEGIN DESCRIPTION:
Walnut Creek 34.0
END DESCRIPTION:
XS GIS Cut Line= 5
      2740461.44      6746659.28      2739966.22      6747319.46
      2739884.65      6747585.27      2739191.14      6748737.98
      2739000.41      6749219.08
#Sta/Elev= 30
  4078.5  343.95  4276.8  339.26  4376.8  332.84  4405.7  325.86  4412.2  329.73
  4662.2  321.36  4818.8  310.81  4947.2  303.44  4959.3  295.58  4978.6  294.95
  4989.2  295.31  5019.5  284.49  5051.8  295.22  5083.2  295.56  5090.1  284.19
  5092.6  283.69  5115.1  284.19  5123.0  295.23  5271.3  293.17  5302.3  286.55
  5357.6  291.95  5643.9  293.65  6023.0  297.88  6044.3  288.22  6065.7  297.90
  6092.4  297.17  6357.1  310.16  6525.9  330.51  6788.5  351.58  7044.6  352.58
#Mann=9,-1,0
  4078.5    0.05       0  4818.8    0.12       0  4978.6     0.1       0
  4989.2    0.12       0  5090.1    0.07       0  5115.1    0.12       0
  5357.6    0.05       0  5643.9    0.12       0  6092.4    0.05       0
Bank Sta=5090.1,5115.1
Exp/Cntr=0.3,0.1

Type RM Length L Ch R = 1,31121,470,470,470
BEGIN DESCRIPTION:
Walnut Creek 33.0
END DESCRIPTION:
XS GIS Cut Line= 3
      2740124.72      6746070.65      2739274.93      6747227.00
      2738976.59      6748857.51
#Sta/Elev= 30
  3123.4  334.32  3194.7  331.21  3372.2  314.17  3472.5  307.33  3767.2  299.10
  3788.0  301.00  3794.2  298.91  3878.7  296.94  3969.3  296.47  3988.6  295.04
  3994.8  291.45  4009.5  288.97  4030.3  295.36  4389.6  292.54  4517.2  294.68
  4531.8  292.57  4538.6  294.47  4834.6  293.73  4867.5  288.97  4898.0  293.47
  4979.3  294.47  4996.6  283.48  4999.2  282.98  5023.0  283.48  5030.1  290.07
  5040.3  294.49  5061.0  294.80  5680.8  294.10  6081.3  322.60  6216.0  336.13
#Mann=8,-1,0
  3123.4    0.05       0  3878.7     0.1       0  3969.3    0.05       0
  4389.6    0.12       0  4834.6     0.1       0  4996.6    0.07       0
  5023.0     0.1       0  5061.0    0.05       0
Bank Sta=4996.6,5023
Exp/Cntr=0.3,0.1

Type RM Length L Ch R = 1,30651,925,925,925
BEGIN DESCRIPTION:
Walnut Creek 32.5
END DESCRIPTION:
XS GIS Cut Line= 3
      2738969.38      6745852.01      2738809.66      6747629.78
      2738261.57      6749017.33
#Sta/Elev= 30
  3385.2  323.86  3474.2  319.58  3479.2  321.27  3524.7  314.15  3701.4  301.76
  3836.0  295.03  4381.0  292.22  4759.7  291.47  4779.8  293.82  4817.4  288.86
  4851.5  289.54  4890.2  296.07  4910.3  294.17  4940.4  295.06  4957.3  283.10
  4959.9  282.60  4983.7  283.10  5000.7  292.62  5056.7  292.96  5154.8  292.90
  5262.6  291.84  5466.9  291.76  5623.0  293.79  5644.5  295.79  5666.0  291.62
  5688.3  290.95  6012.9  295.88  6445.7  321.98  6553.9  327.52  6662.0  329.85
#Mann=9,-1,0
  3385.2    0.05       0  4381.0    0.12       0  4851.5     0.1       0
  4957.3    0.07       0  4983.7     0.1       0  5056.7    0.12       0
  5154.8    0.05       0  5262.6    0.12       0  5466.9    0.05       0
Bank Sta=4957.3,4983.7
Exp/Cntr=0.3,0.1

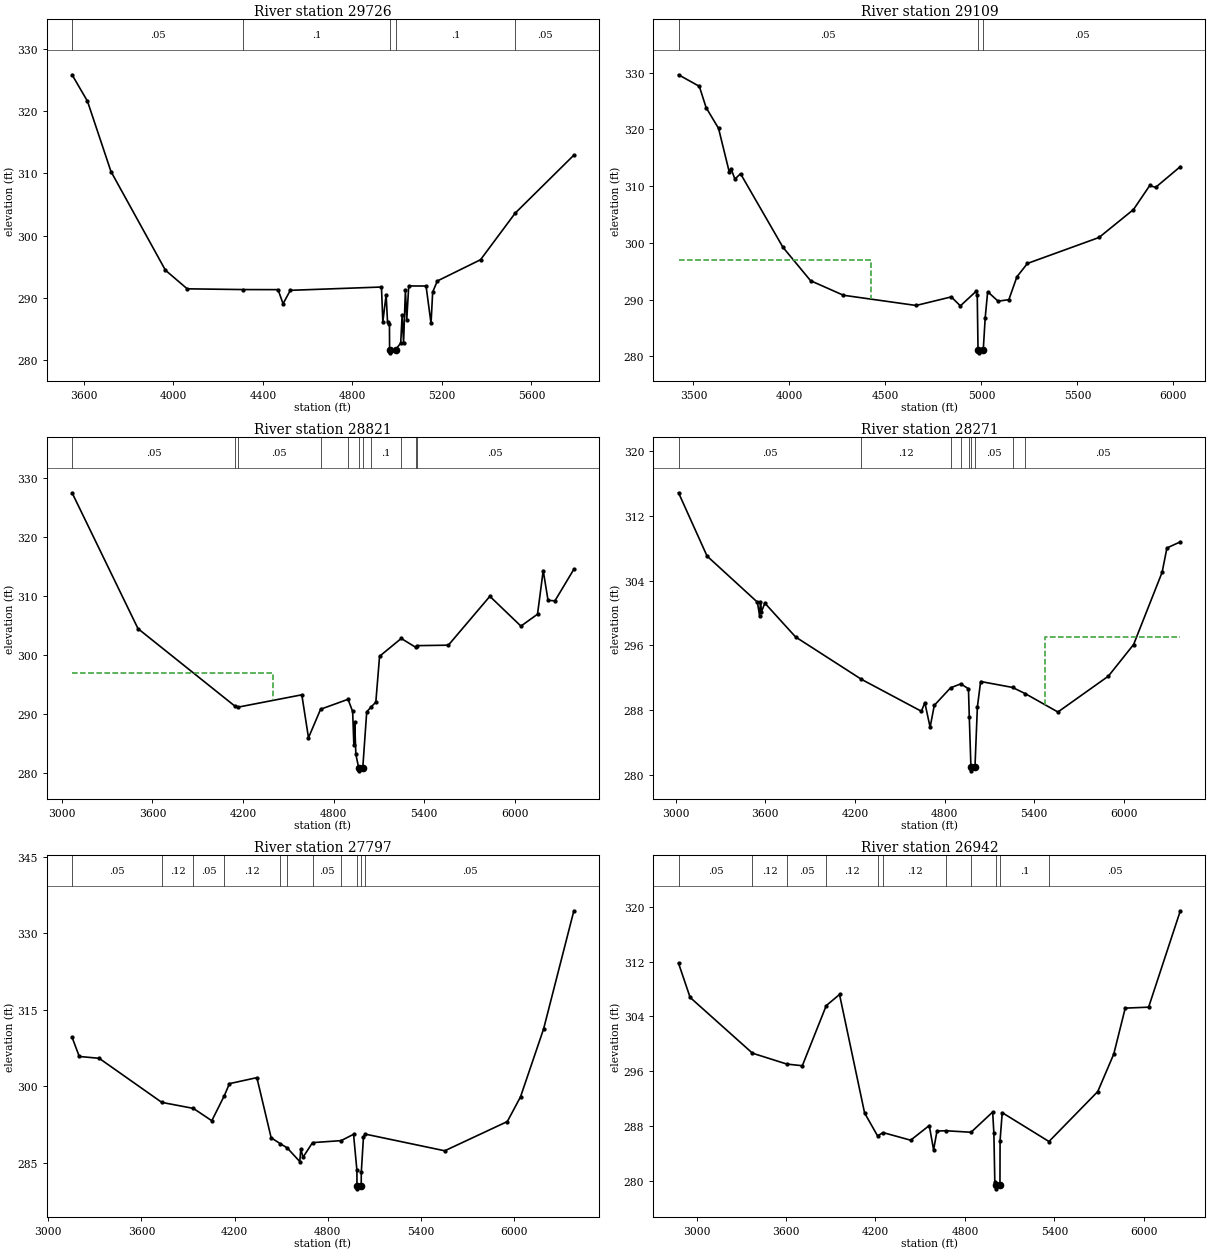
Type RM Length L Ch R = 1,29726,617,617,617
BEGIN DESCRIPTION:
Walnut Creek 32.0
END DESCRIPTION:
XS GIS Cut Line= 3
      2738912.51      6745934.48      2738278.84      6747154.08
      2737776.00      6747860.99
#Sta/Elev= 30
  3547.7  325.81  3616.5  321.57  3721.5  310.29  3964.7  294.46  4062.2  291.47
  4313.1  291.35  4467.9  291.34  4490.4  289.08  4522.8  291.23  4930.0  291.76
  4936.2  286.17  4950.9  290.54  4957.1  286.15  4965.7  285.84  4966.3  281.70
  4969.0  281.20  4993.0  281.70  5016.1  282.77  5022.3  287.28  5028.8  282.82
  5037.0  291.21  5043.1  286.54  5051.8  291.93  5129.2  291.92  5151.5  285.93
  5158.8  290.95  5179.7  292.73  5372.7  296.14  5527.4  303.61  5789.6  312.92
#Mann=5,-1,0
  3547.7    0.05       0  4313.1     0.1       0  4966.3    0.07       0
  4993.0     0.1       0  5527.4    0.05       0
Bank Sta=4966.3,4993
Exp/Cntr=0.3,0.1

Type RM Length L Ch R = 1,29109,288,288,288
BEGIN DESCRIPTION:
Walnut Creek 31.0
END DESCRIPTION:
XS GIS Cut Line= 4
      2738756.24      6745569.92      2737948.98      6746650.61
      2737805.75      6746989.15      2737484.73      6747826.41
#Sta/Elev= 30
  3422.7  329.60  3530.9  327.57  3566.4  323.81  3631.0  320.17  3687.3  312.42
  3695.6  313.08  3716.4  311.24  3745.6  312.18  3966.6  299.22  4110.4  293.34
  4281.4  290.78  4659.8  288.98  4843.0  290.49  4890.4  288.91  4972.3  291.47
  4978.3  290.79  4982.4  281.14  4985.1  280.64  5009.6  281.14  5019.7  286.81
  5032.6  291.40  5086.9  289.74  5142.9  290.00  5184.9  294.03  5239.6  296.38
  5612.4  300.95  5792.0  305.87  5876.8  310.11  5906.8  309.76  6035.9  313.43
#Mann=3,-1,0
  3422.7    0.05       0  4982.4    0.05       0  5009.6    0.05       0
#XS Ineff=2,0
    0.00 4425.00  297.00               0
Permanent Ineff=
       F       F
Bank Sta=4982.4,5009.6
Exp/Cntr=0.3,0.1

Type RM Length L Ch R = 1,28821,550,550,550
BEGIN DESCRIPTION:
Walnut Creek 30.7
END DESCRIPTION:
XS GIS Cut Line= 3
      2738547.93      6745274.76      2737679.88      6746772.14
      2737115.66      6748260.81
#Sta/Elev= 30
  3067.8  327.52  3504.4  304.50  4147.3  291.35  4164.7  291.19  4589.2  293.29
  4633.3  286.02  4713.7  290.85  4895.3  292.53  4925.7  290.47  4933.8  284.82
  4939.1  288.69  4947.1  283.22  4965.6  280.91  4968.2  280.41  4992.8  280.91
  5018.9  290.39  5047.2  291.22  5079.2  292.04  5104.0  299.82  5247.6  302.84
  5345.1  301.31  5350.7  301.62  5559.6  301.70  5834.4  309.98  6040.1  304.93
  6150.0  306.95  6187.6  314.35  6219.7  309.30  6265.2  309.21  6390.6  314.56
#Mann=11,-1,0
  3067.8    0.05       0  4147.3    0.12       0  4164.7    0.05       0
  4713.7    0.12       0  4895.3    0.05       0  4965.6    0.05       0
  4992.8    0.05       0  5047.2     0.1       0  5247.6    0.05       0
  5345.1     0.1       0  5350.7    0.05       0
#XS Ineff=2,0
    0.00 4400.00  297.00               0
Permanent Ineff=
       F       F
Bank Sta=4965.6,4992.8
Exp/Cntr=0.3,0.1

Type RM Length L Ch R = 1,28271,474,474,474
BEGIN DESCRIPTION:
Walnut Creek 30.3
END DESCRIPTION:
XS GIS Cut Line= 3
      2738383.00      6745179.26      2737219.81      6746707.03
      2736530.35      6747968.88
#Sta/Elev= 30
  3019.4  314.82  3210.3  307.02  3547.1  301.34  3561.6  299.68  3567.9  301.41
  3574.6  300.17  3597.0  301.22  3802.8  297.05  4243.3  291.83  4644.8  287.89
  4667.6  288.96  4703.0  285.92  4730.9  288.62  4839.8  290.78  4907.9  291.27
  4959.6  290.67  4965.3  287.15  4976.1  281.05  4978.7  280.55  5003.3  281.05
  5019.3  288.41  5041.2  291.56  5254.4  290.83  5340.3  290.06  5558.3  287.80
  5896.0  292.22  6064.9  296.12  6255.6  305.02  6287.9  308.02  6377.5  308.77
#Mann=9,-1,0
  3019.4    0.05       0  4243.3    0.12       0  4839.8    0.05       0
  4907.9    0.12       0  4965.3    0.05       0  4976.1    0.04       0
  5003.3    0.05       0  5254.4    0.12       0  5340.3    0.05       0
#XS Ineff=2,0
       0                 5470.00    0.00  297.00
Permanent Ineff=
       F       F
Bank Sta=4976.1,5003.3
Exp/Cntr=0.3,0.1

Type RM Length L Ch R = 1,27797,855,855,855
BEGIN DESCRIPTION:
Walnut Creek 30.0
END DESCRIPTION:
XS GIS Cut Line= 3
      2738187.66      6745257.41      2737432.49      6745856.34
      2735900.66      6747531.37
#Sta/Elev= 30
  3153.2  309.62  3199.6  305.86  3327.8  305.50  3731.3  296.86  3934.9  295.68
  4053.6  293.26  4134.2  298.16  4167.3  300.53  4344.2  301.71  4436.1  289.93
  4495.7  288.74  4539.2  287.95  4620.5  285.26  4627.3  287.71  4641.5  286.10
  4702.8  288.97  4886.9  289.36  4967.1  290.60  4988.7  283.58  4989.3  280.41
  4991.9  279.91  5016.5  280.41  5017.1  283.17  5031.2  290.14  5044.0  290.63
  5554.8  287.37  5958.1  293.10  6043.2  297.95  6191.8  311.25  6386.9  334.42
#Mann=11,-1,0
  3153.2    0.05       0  3731.3    0.12       0  3934.9    0.05       0
  4134.2    0.12       0  4495.7    0.05       0  4539.2    0.12       0
  4702.8    0.05       0  4886.9    0.12       0  4989.3    0.07       0
  5016.5    0.12       0  5044.0    0.05       0
Bank Sta=4989.3,5016.5
Exp/Cntr=0.3,0.1

Type RM Length L Ch R = 1,26942,538,538,538
BEGIN DESCRIPTION:
Walnut Creek 29.0
END DESCRIPTION:
XS GIS Cut Line= 3
      2738192.02      6745240.02      2736377.80      6746246.96
      2735366.53      6747049.90
#Sta/Elev= 30
  2878.7  311.77  2956.4  306.78  3374.7  298.64  3605.6  297.05  3709.1  296.81
  3869.7  305.59  3958.7  307.21  4126.9  289.91  4213.8  286.57  4250.9  287.05
  4435.9  285.94  4560.6  288.08  4589.7  284.54  4612.6  287.28  4672.5  287.32
  4841.0  287.10  4986.0  290.05  4994.1  286.99  5000.5  279.77  5007.7  279.34
  5010.3  278.84  5034.9  279.34  5035.7  285.89  5050.1  289.96  5363.7  285.75
  5691.0  293.04  5798.3  298.51  5875.3  305.22  6032.2  305.36  6244.9  319.43
#Mann=11,-1,0
  2878.7    0.05       0  3374.7    0.12       0  3605.6    0.05       0
  3869.7    0.12       0  4213.8    0.05       0  4250.9    0.12       0
  4672.5     0.1       0  4841.0    0.12       0  5007.7    0.07       0
  5034.9     0.1       0  5363.7    0.05       0
Bank Sta=5007.7,5034.9
Exp/Cntr=0.3,0.1