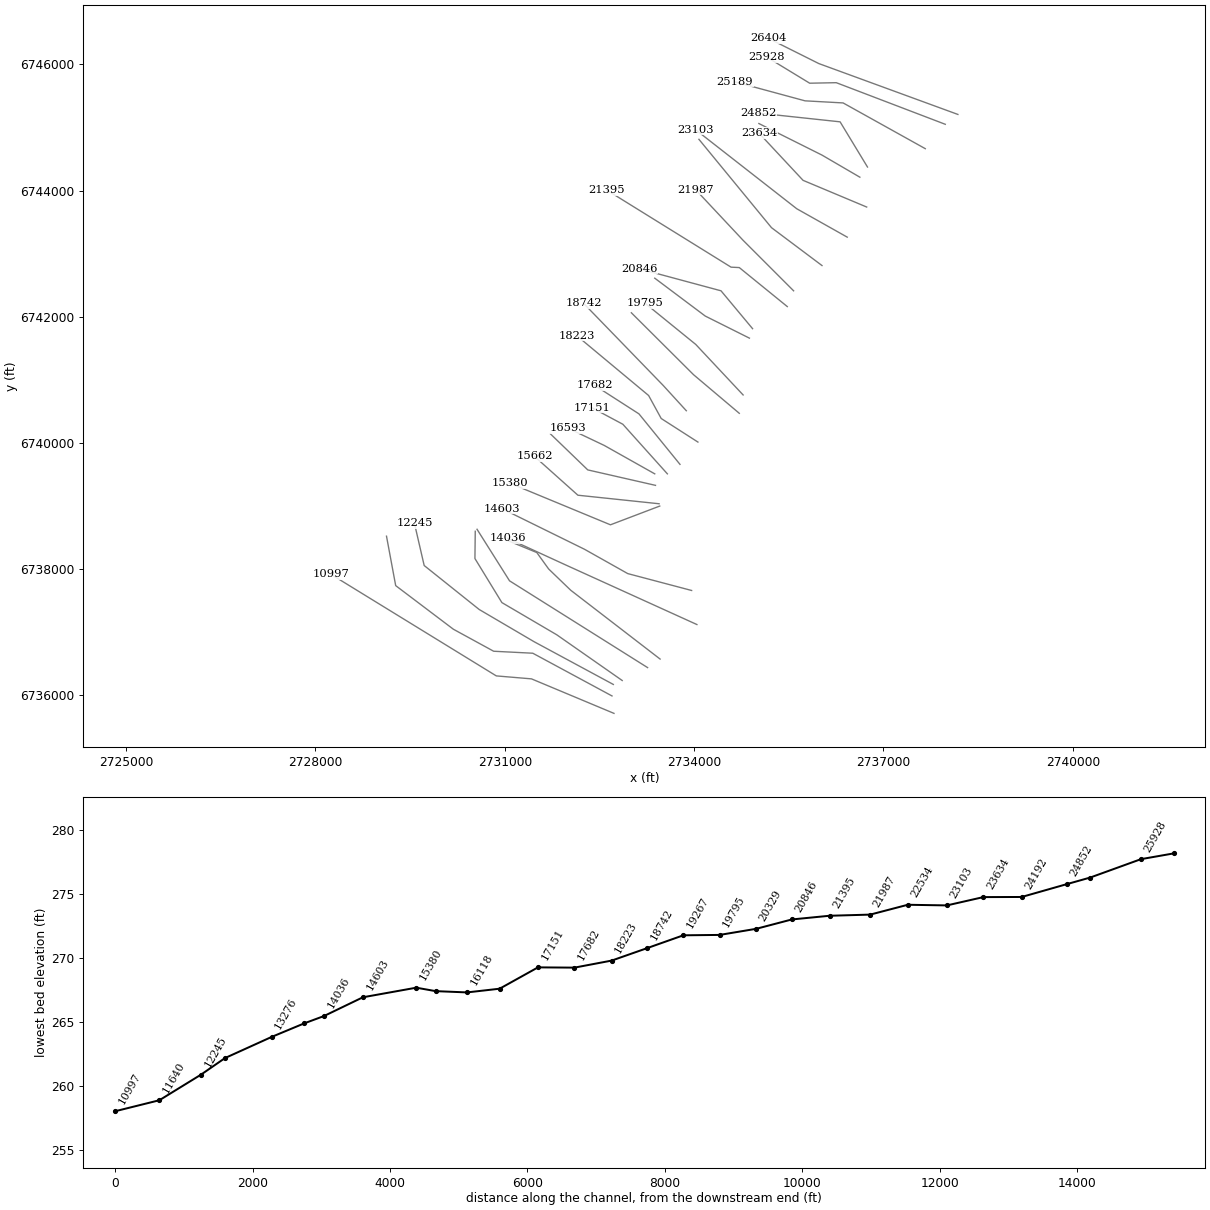
HEC-RAS study Walnut Creek.prj: Walnut Creek Base Level Engineering

--- Walnut Creek.g01 (geometry) --- (continued)

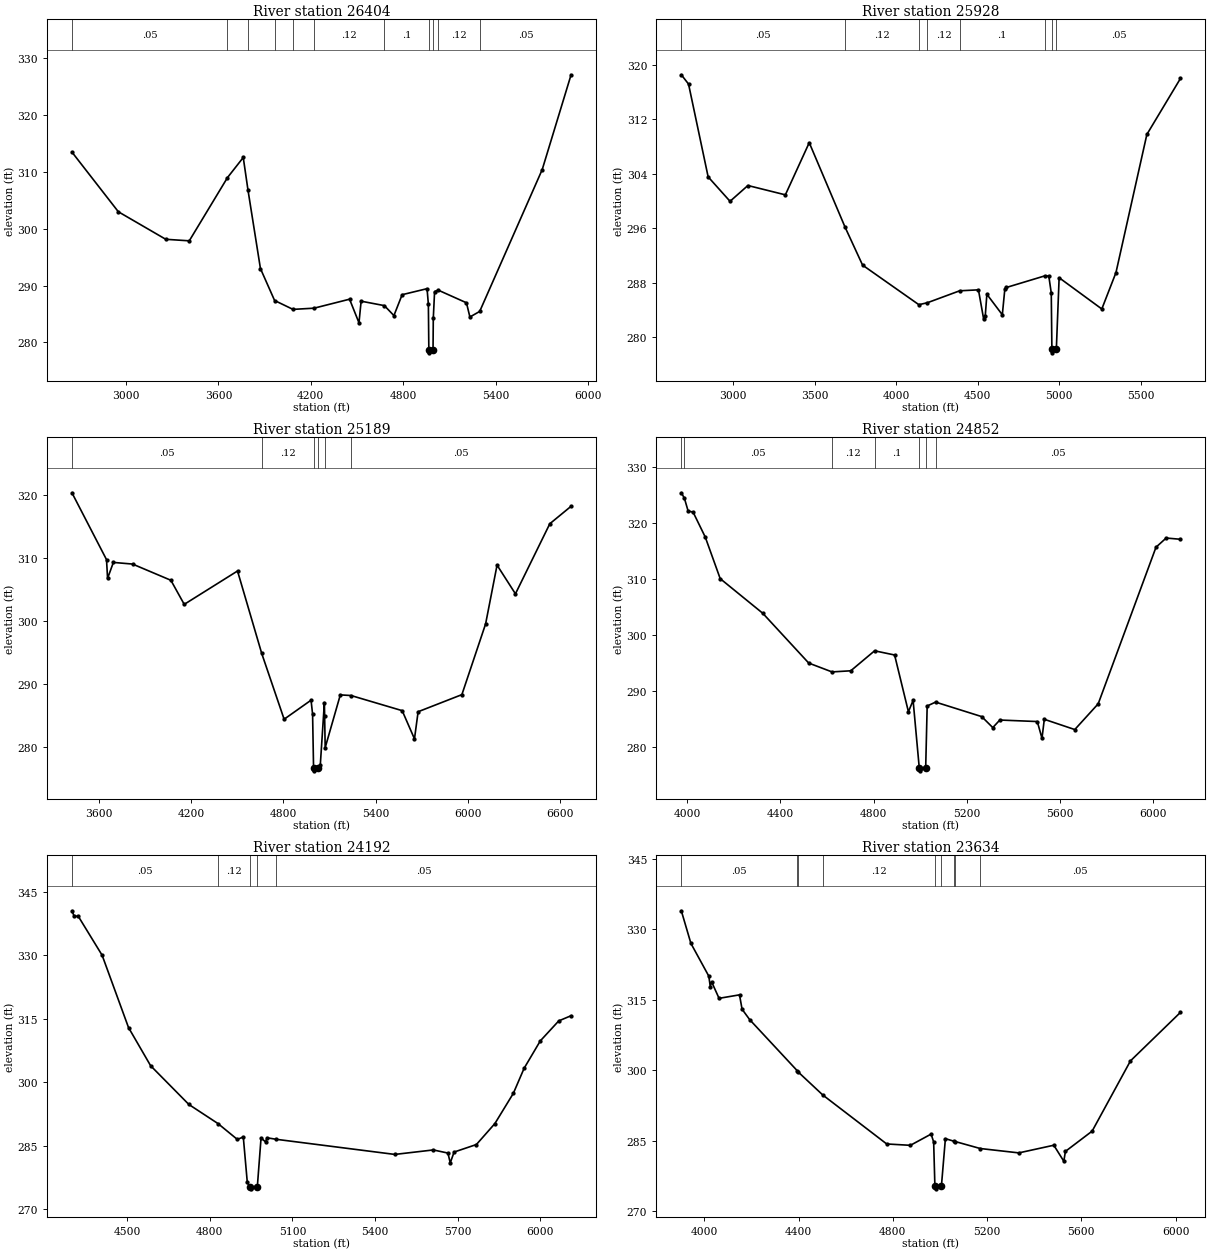
Type RM Length L Ch R = 1,26404,476,476,476
BEGIN DESCRIPTION:
Walnut Creek 28.0
END DESCRIPTION:
XS GIS Cut Line= 3
      2738178.97      6745205.31      2735976.00      6746011.00
      2735176.01      6746411.00
#Sta/Elev= 30
  2649.4  313.47  2950.7  302.98  3258.5  298.14  3411.1  297.87  3659.2  308.99
  3761.5  312.52  3792.4  306.76  3873.0  293.00  3964.9  287.38  4084.4  285.82
  4221.0  286.03  4451.6  287.61  4512.7  283.46  4526.6  287.26  4677.5  286.48
  4739.5  284.73  4792.8  288.40  4954.6  289.46  4963.1  286.74  4966.2  278.68
  4968.9  278.18  4993.4  278.68  4995.1  284.27  5003.5  288.94  5026.3  289.21
  5210.3  286.98  5232.7  284.48  5296.3  285.46  5702.2  310.40  5889.5  327.06
#Mann=11,-1,0
  2649.4    0.05       0  3659.2    0.12       0  3792.4    0.05       0
  3964.9    0.12       0  4084.4    0.05       0  4221.0    0.12       0
  4677.5     0.1       0  4966.2    0.07       0  4993.4     0.1       0
  5026.3    0.12       0  5296.3    0.05       0
Bank Sta=4966.2,4993.4
Exp/Cntr=0.3,0.1

Type RM Length L Ch R = 1,25928,739,739,739
BEGIN DESCRIPTION:
Walnut Creek 27.0
END DESCRIPTION:
XS GIS Cut Line= 4
      2737979.40      6745049.03      2736251.94      6745708.37
      2735830.92      6745700.09      2735153.81      6746112.44
#Sta/Elev= 30
  2681.6  318.56  2725.9  317.20  2846.2  303.57  2980.6  299.98  3090.2  302.30
  3320.1  300.93  3466.6  308.59  3685.6  296.23  3793.9  290.61  4139.3  284.80
  4191.8  285.09  4389.6  286.84  4504.9  286.98  4536.6  282.72  4546.6  283.11
  4556.6  286.33  4651.4  283.32  4666.6  287.05  4676.6  287.33  4910.5  289.02
  4936.6  289.01  4951.7  286.52  4955.6  278.23  4958.2  277.73  4982.8  278.23
  5000.0  288.76  5261.9  284.17  5348.7  289.51  5538.4  309.80  5744.5  318.02
#Mann=8,-1,0
  2681.6    0.05       0  3685.6    0.12       0  4139.3    0.05       0
  4191.8    0.12       0  4389.6     0.1       0  4910.5    0.05       0
  4955.6    0.04       0  4982.8    0.05       0
Bank Sta=4955.6,4982.8
Exp/Cntr=0.3,0.1

Type RM Length L Ch R = 1,25189,337,337,337
BEGIN DESCRIPTION:
Walnut Creek 26.0
END DESCRIPTION:
XS GIS Cut Line= 4
      2737662.53      6744662.76      2736360.44      6745387.59
      2735756.82      6745420.80      2734646.05      6745721.78
#Sta/Elev= 30
  3425.5  320.37  3650.4  309.77  3657.2  306.80  3695.0  309.33  3819.6  309.07
  4068.8  306.50  4155.7  302.68  4502.2  307.97  4659.4  294.91  4805.2  284.47
  4980.3  287.49  4990.3  285.28  4996.6  276.79  4999.3  276.29  5024.1  276.79
  5040.4  277.21  5067.1  287.12  5068.6  285.02  5072.2  279.97  5170.6  288.33
  5240.2  288.23  5572.9  285.83  5652.8  281.36  5676.5  285.66  5961.1  288.37
  6115.3  299.58  6189.8  308.90  6309.3  304.35  6532.8  315.46  6671.1  318.23
#Mann=6,-1,0
  3425.5    0.05       0  4659.4    0.12       0  4996.6    0.07       0
  5024.1    0.12       0  5068.6     0.1       0  5240.2    0.05       0
Bank Sta=4996.6,5024.1
Exp/Cntr=0.3,0.1

Type RM Length L Ch R = 1,24852,660,660,660
BEGIN DESCRIPTION:
Walnut Creek 25.0
END DESCRIPTION:
XS GIS Cut Line= 3
      2736746.70      6744372.00      2736312.69      6745088.11
      2735014.96      6745227.00
#Sta/Elev= 30
  3974.6  325.42  3987.8  324.45  4003.8  322.16  4025.1  321.97  4077.4  317.51
  4141.5  310.09  4324.2  303.91  4521.5  295.02  4621.4  293.44  4701.9  293.64
  4804.3  297.21  4890.1  296.46  4949.4  286.33  4969.5  288.36  4996.0  276.28
  4998.7  275.78  5023.5  276.28  5029.9  287.36  5066.1  288.05  5264.1  285.46
  5311.5  283.50  5341.7  284.85  5502.6  284.58  5522.7  281.59  5532.7  284.98
  5663.5  283.15  5764.1  287.75  6012.1  315.70  6055.7  317.34  6117.1  317.12
#Mann=7,-1,0
  3974.6    0.12       0  3987.8    0.05       0  4621.4    0.12       0
  4804.3     0.1       0  4996.0    0.07       0  5023.5     0.1       0
  5066.1    0.05       0
Bank Sta=4996,5023.5
Exp/Cntr=0.3,0.1

Type RM Length L Ch R = 1,24192,558,558,558
BEGIN DESCRIPTION:
Walnut Creek 24.0
END DESCRIPTION:
XS GIS Cut Line= 3
      2736626.04      6744210.98      2736026.00      6744561.00
      2735026.00      6745061.00
#Sta/Elev= 30
  4299.4  340.46  4307.3  339.21  4322.6  339.14  4409.0  329.96  4504.9  312.87
  4585.2  303.85  4724.1  294.70  4830.0  290.18  4900.2  286.44  4921.7  287.03
  4936.2  276.32  4945.2  275.27  4947.9  274.77  4972.7  275.27  4986.2  286.80
  5002.5  285.85  5008.0  286.83  5041.6  286.47  5472.0  282.90  5611.8  283.96
  5664.9  283.22  5673.3  280.90  5687.3  283.46  5768.3  285.24  5835.4  290.19
  5902.5  297.34  5941.6  303.26  6000.3  309.72  6067.4  314.45  6112.1  315.67
#Mann=5,-1,0
  4299.4    0.05       0  4830.0    0.12       0  4945.2    0.07       0
  4972.7    0.12       0  5041.6    0.05       0
Bank Sta=4945.2,4972.7
Exp/Cntr=0.3,0.1

Type RM Length L Ch R = 1,23634,531,531,531
BEGIN DESCRIPTION:
Walnut Creek 23.0
END DESCRIPTION:
XS GIS Cut Line= 3
      2736733.74      6743738.27      2735726.00      6744161.00
      2735026.02      6744910.98
#Sta/Elev= 30
  3902.1  333.93  3942.8  326.99  4018.9  320.01  4024.9  317.81  4030.4  318.84
  4062.3  315.30  4149.1  316.04  4160.0  312.98  4192.4  310.76  4394.4  299.88
  4397.0  299.68  4502.8  294.72  4773.9  284.31  4874.4  284.02  4962.4  286.41
  4973.2  284.73  4978.5  275.26  4981.2  274.76  5006.0  275.26  5023.0  285.44
  5061.1  284.86  5064.3  284.83  5170.9  283.34  5334.7  282.41  5483.2  284.04
  5525.7  280.63  5532.5  282.73  5645.9  287.04  5808.6  301.99  6020.8  312.31
#Mann=9,-1,0
  3902.1    0.05       0  4394.4    0.12       0  4397.0    0.05       0
  4502.8    0.12       0  4978.5    0.07       0  5006.0    0.12       0
  5061.1    0.05       0  5064.3    0.12       0  5170.9    0.05       0
Bank Sta=4978.5,5006
Exp/Cntr=0.3,0.1

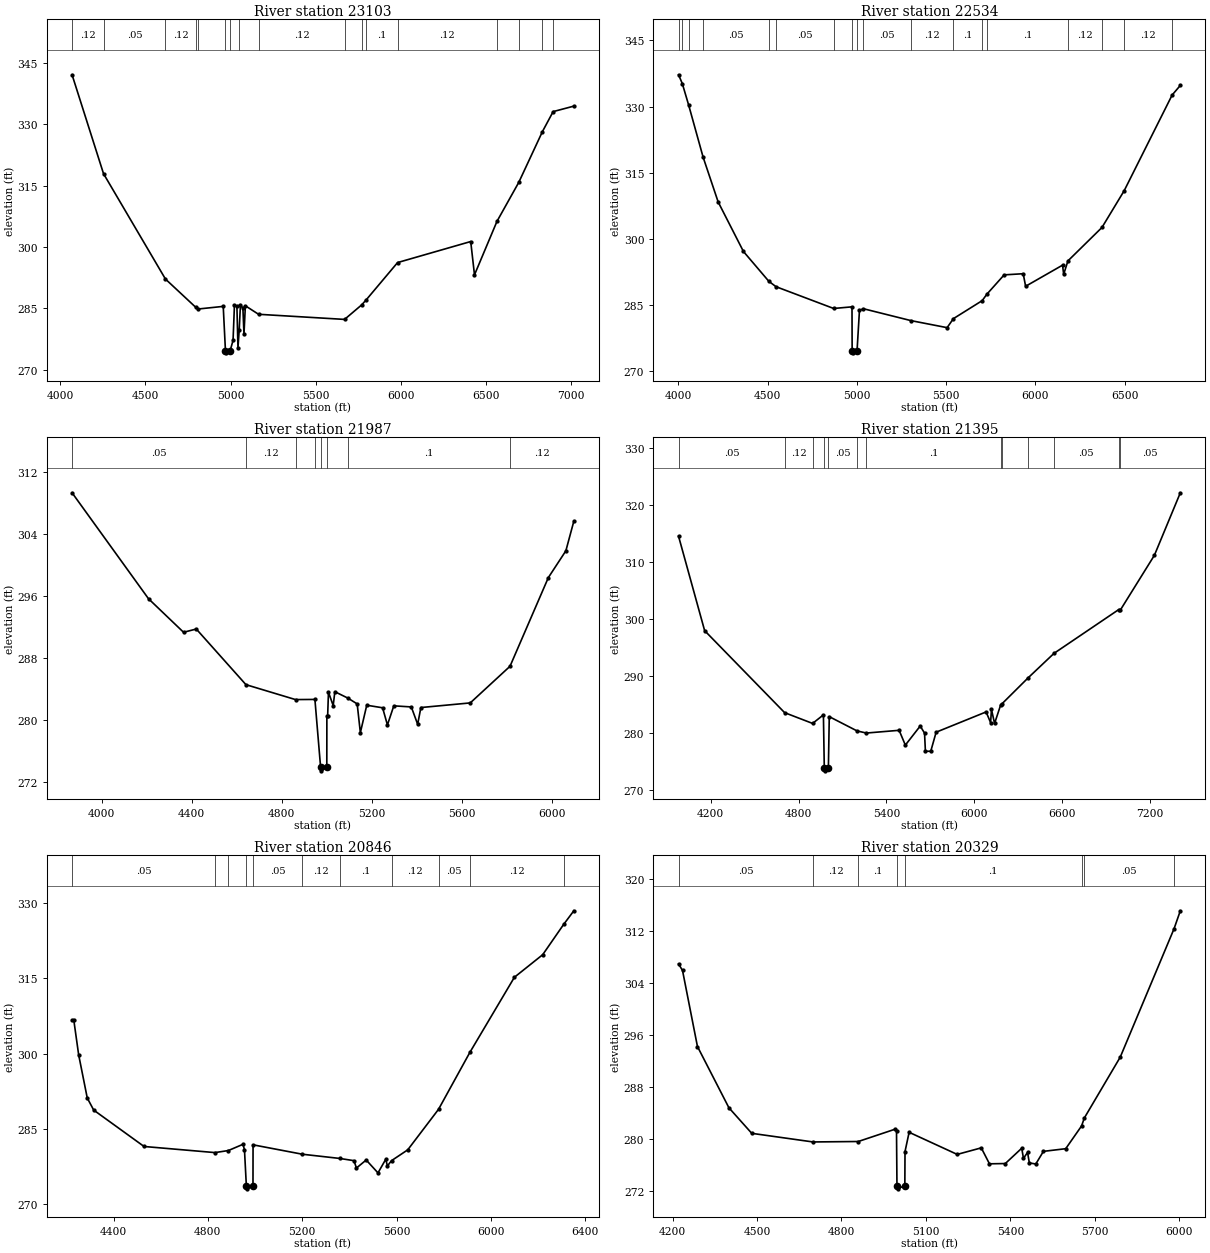
Type RM Length L Ch R = 1,23103,569,569,569
BEGIN DESCRIPTION:
Walnut Creek 22.0
END DESCRIPTION:
XS GIS Cut Line= 3
      2736425.98      6743261.01      2735626.00      6743711.00
      2734026.04      6744960.97
#Sta/Elev= 30
  4069.0  342.06  4253.9  317.88  4617.7  292.14  4795.9  285.23  4809.4  284.82
  4957.2  285.46  4970.2  274.61  4972.9  274.11  4997.8  274.61  5014.9  277.16
  5023.0  285.69  5037.5  285.52  5043.8  275.34  5051.1  279.69  5058.3  285.88
  5072.8  284.97  5079.1  278.68  5087.2  285.61  5164.8  283.53  5670.1  282.28
  5770.4  285.82  5798.1  287.10  5981.6  296.17  6411.3  301.31  6433.5  293.17
  6565.7  306.25  6693.7  315.77  6832.6  328.17  6895.6  333.06  7017.2  334.40
#Mann=17,-1,0
  4069.0    0.12       0  4253.9    0.05       0  4617.7    0.12       0
  4795.9    0.05       0  4809.4    0.12       0  4970.2    0.07       0
  4997.8    0.12       0  5051.1    0.05       0  5164.8    0.12       0
  5670.1     0.1       0  5770.4    0.12       0  5798.1     0.1       0
  5981.6    0.12       0  6565.7     0.1       0  6693.7    0.12       0
  6832.6    0.05       0  6895.6    0.12       0
Bank Sta=4970.2,4997.8
Exp/Cntr=0.3,0.1

Type RM Length L Ch R = 1,22534,547,547,547
BEGIN DESCRIPTION:
Walnut Creek 21.0
END DESCRIPTION:
XS GIS Cut Line= 3
      2736026.04      6742810.97      2735226.00      6743411.00
      2734076.01      6744810.99
#Sta/Elev= 30
  4000.4  337.21  4021.4  335.21  4057.2  330.31  4137.9  318.54  4222.3  308.37
  4364.0  297.14  4506.1  290.39  4546.4  289.16  4869.6  284.22  4972.3  284.59
  4973.1  274.66  4975.8  274.16  5000.7  274.66  5014.1  283.78  5036.5  284.16
  5303.4  281.46  5505.2  279.87  5540.8  281.92  5702.0  286.00  5728.2  287.46
  5824.9  291.84  5931.8  292.10  5945.2  289.25  6152.1  294.04  6158.5  291.98
  6182.4  295.01  6373.1  302.59  6497.4  310.91  6766.3  332.62  6812.2  334.80
#Mann=18,-1,0
  4000.4    0.12       0  4021.4     0.1       0  4057.2    0.12       0
  4137.9    0.05       0  4506.1    0.12       0  4546.4    0.05       0
  4869.6    0.12       0  4973.1    0.07       0  5000.7    0.12       0
  5036.5    0.05       0  5303.4    0.12       0  5540.8     0.1       0
  5702.0    0.12       0  5728.2     0.1       0  6182.4    0.12       0
  6373.1     0.1       0  6497.4    0.12       0  6766.3    0.05       0
Bank Sta=4973.1,5000.7
Exp/Cntr=0.3,0.1

Type RM Length L Ch R = 1,21987,592,592,592
BEGIN DESCRIPTION:
Walnut Creek 20.0
END DESCRIPTION:
XS GIS Cut Line= 3
      2735576.02      6742410.98      2734776.00      6743211.00
      2734025.99      6744011.01
#Sta/Elev= 30
  3868.6  309.37  4208.0  295.66  4363.6  291.32  4420.2  291.74  4640.7  284.54
  4860.8  282.61  4946.9  282.63  4972.1  273.89  4974.8  273.39  4999.7  273.89
  5000.0  280.45  5003.4  280.45  5007.1  283.57  5028.1  281.83  5035.4  283.63
  5093.4  282.80  5134.6  282.05  5148.7  278.33  5177.1  281.88  5247.4  281.55
  5268.9  279.33  5297.2  281.80  5374.9  281.66  5403.2  279.41  5417.4  281.58
  5636.7  282.18  5813.2  286.92  5983.5  298.40  6061.2  301.86  6096.6  305.69
#Mann=8,-1,0
  3868.6    0.05       0  4640.7    0.12       0  4860.8    0.05       0
  4946.9     0.1       0  4972.1    0.07       0  4999.7     0.1       0
  5093.4     0.1       0  5813.2    0.12       0
Bank Sta=4972.1,4999.7
Exp/Cntr=0.3,0.1

Type RM Length L Ch R = 1,21395,549,549,549
BEGIN DESCRIPTION:
Walnut Creek 19.0
END DESCRIPTION:
XS GIS Cut Line= 4
      2735475.98      6742161.02      2734715.47      6742779.08
      2734585.16      6742785.59      2732615.88      6744006.70
#Sta/Elev= 30
  3980.1  314.51  4158.2  297.93  4704.7  283.52  4895.6  281.63  4969.6  283.13
  4975.6  273.80  4978.3  273.30  5003.6  273.80  5009.6  282.82  5199.6  280.31
  5262.8  279.94  5486.8  280.42  5529.3  277.82  5630.8  281.17  5660.4  279.93
  5666.3  276.74  5702.9  276.74  5739.6  280.09  6081.0  283.65  6111.7  281.77
  6117.6  284.08  6138.8  281.62  6179.9  284.84  6186.8  285.01  6368.1  289.64
  6544.8  293.94  6986.9  301.63  6998.3  301.56  7230.4  311.16  7407.7  322.15
#Mann=13,-1,0
  3980.1    0.05       0  4704.7    0.12       0  4895.6    0.05       0
  4975.6    0.04       0  5003.6    0.05       0  5199.6    0.12       0
  5262.8     0.1       0  6179.9    0.12       0  6186.8     0.1       0
  6368.1    0.12       0  6544.8    0.05       0  6986.9     0.1       0
  6998.3    0.05       0
Bank Sta=4975.6,5003.6
Exp/Cntr=0.3,0.1

Type RM Length L Ch R = 1,20846,517,517,517
BEGIN DESCRIPTION:
Walnut Creek 18.0
END DESCRIPTION:
XS GIS Cut Line= 3
      2734925.99      6741811.02      2734426.00      6742411.00
      2733125.99      6742761.00
#Sta/Elev= 30
  4224.3  306.62  4231.4  306.75  4252.3  299.73  4288.7  291.13  4316.0  288.72
  4529.5  281.46  4830.2  280.24  4886.9  280.65  4948.7  281.89  4955.2  280.84
  4963.3  273.51  4966.1  273.01  4991.3  273.51  4991.6  281.79  5201.2  279.91
  5358.2  279.08  5419.5  278.63  5429.9  277.16  5471.3  278.76  5521.3  276.19
  5554.2  278.91  5561.2  277.58  5578.6  278.63  5647.4  280.79  5777.9  288.87
  5910.7  300.22  6099.7  315.22  6219.6  319.72  6308.4  325.76  6351.6  328.48
#Mann=11,-1,0
  4224.3    0.05       0  4830.2    0.12       0  4886.9    0.05       0
  4963.3    0.04       0  4991.3    0.05       0  5201.2    0.12       0
  5358.2     0.1       0  5578.6    0.12       0  5777.9    0.05       0
  5910.7    0.12       0  6308.4    0.05       0
Bank Sta=4963.3,4991.3
Exp/Cntr=0.3,0.1

Type RM Length L Ch R = 1,20329,534,534,534
BEGIN DESCRIPTION:
Walnut Creek 17.0
END DESCRIPTION:
XS GIS Cut Line= 3
      2734876.02      6741660.99      2734176.00      6742011.00
      2733376.04      6742610.97
#Sta/Elev= 30
  4221.2  306.95  4235.2  305.97  4288.3  294.23  4400.1  284.78  4481.2  280.84
  4698.9  279.51  4859.6  279.58  4989.9  281.47  4995.5  281.14  4997.1  272.78
  4999.9  272.28  5025.1  272.78  5025.7  278.03  5040.3  281.00  5211.1  277.59
  5296.6  278.60  5325.7  276.14  5382.0  276.18  5440.3  278.54  5446.6  276.98
  5461.1  277.90  5467.4  276.28  5490.3  276.11  5517.4  278.06  5596.6  278.47
  5653.0  281.98  5662.8  283.21  5790.3  292.59  5981.6  312.40  6003.8  315.16
#Mann=8,-1,0
  4221.2    0.05       0  4698.9    0.12       0  4859.6     0.1       0
  4997.1    0.07       0  5025.1     0.1       0  5653.0    0.12       0
  5662.8    0.05       0  5981.6    0.12       0
Bank Sta=4997.1,5025.1
Exp/Cntr=0.3,0.1

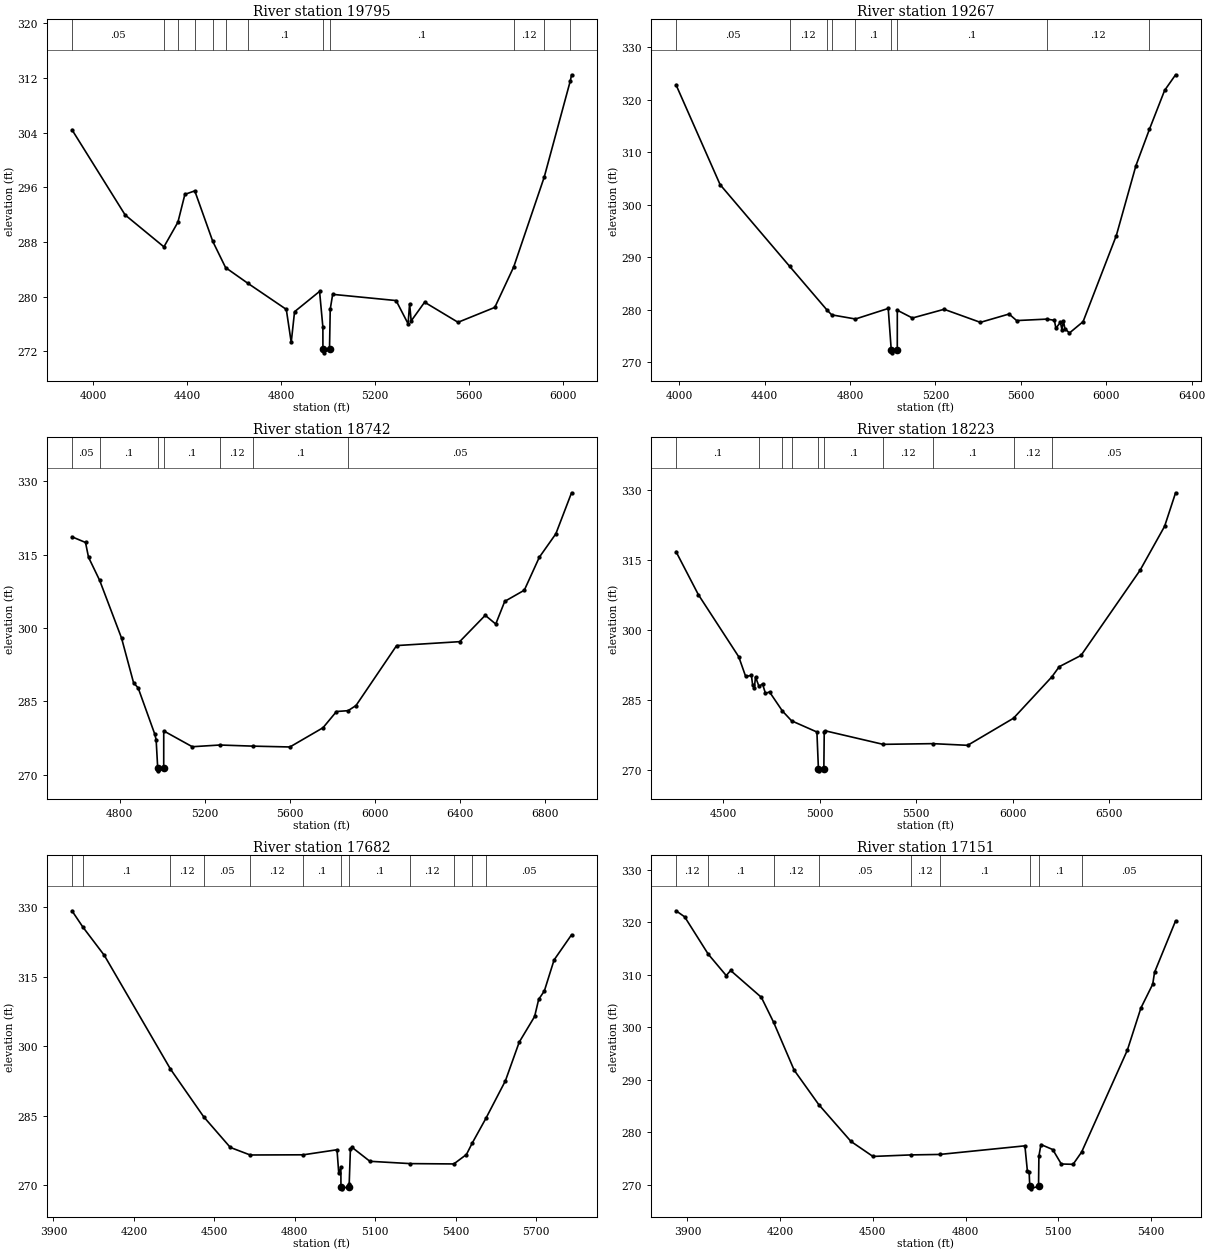
Type RM Length L Ch R = 1,19795,528,528,528
BEGIN DESCRIPTION:
Walnut Creek 16.0
END DESCRIPTION:
XS GIS Cut Line= 3
      2734776.02      6740760.98      2734026.00      6741561.00
      2733226.00      6742211.00
#Sta/Elev= 30
  3908.3  304.45  4134.7  291.98  4299.9  287.31  4359.5  290.92  4389.2  294.99
  4431.3  295.50  4507.9  288.11  4562.6  284.27  4656.4  282.00  4821.0  278.16
  4842.0  273.33  4856.2  277.82  4962.7  280.79  4976.8  275.56  4977.0  272.30
  4979.7  271.80  5005.0  272.30  5008.1  278.19  5018.5  280.36  5288.6  279.45
  5339.7  276.05  5346.1  278.99  5352.8  276.47  5410.0  279.21  5552.3  276.27
  5708.9  278.45  5789.6  284.39  5919.4  297.52  6030.8  311.65  6035.7  312.49
#Mann=12,-1,0
  3908.3    0.05       0  4299.9    0.12       0  4359.5    0.05       0
  4431.3    0.12       0  4507.9    0.05       0  4562.6    0.12       0
  4656.4     0.1       0  4977.0    0.07       0  5005.0     0.1       0
  5789.6    0.12       0  5919.4    0.05       0  6030.8    0.12       0
Bank Sta=4977,5005
Exp/Cntr=0.3,0.1

Type RM Length L Ch R = 1,19267,525,525,525
BEGIN DESCRIPTION:
Walnut Creek 15.0
END DESCRIPTION:
XS GIS Cut Line= 3
      2734715.48      6740470.04      2733990.65      6741082.03
      2733005.42      6742062.92
#Sta/Elev= 30
  3985.6  322.87  4192.1  303.83  4517.6  288.26  4693.6  279.88  4714.7  279.01
  4825.8  278.22  4979.2  280.23  4993.4  272.27  4996.2  271.77  5021.6  272.27
  5021.7  279.89  5092.4  278.41  5240.8  280.07  5410.6  277.58  5544.9  279.17
  5580.3  277.92  5722.2  278.20  5757.1  277.97  5764.1  276.45  5785.3  277.60
  5792.4  276.20  5799.5  277.85  5806.5  276.34  5827.8  275.56  5891.4  277.71
  6047.0  294.12  6138.9  307.46  6202.0  314.38  6273.2  321.80  6324.5  324.77
#Mann=9,-1,0
  3985.6    0.05       0  4517.6    0.12       0  4693.6    0.05       0
  4714.7    0.12       0  4825.8     0.1       0  4993.4    0.07       0
  5021.6     0.1       0  5722.2    0.12       0  6202.0    0.05       0
Bank Sta=4993.4,5021.6
Exp/Cntr=0.3,0.1

Type RM Length L Ch R = 1,18742,519,519,519
BEGIN DESCRIPTION:
Walnut Creek 14.0
END DESCRIPTION:
XS GIS Cut Line= 3
      2733875.98      6740511.02      2733508.87      6740912.76
      2732250.60      6742210.09
#Sta/Elev= 30
  4575.0  318.62  4638.8  317.46  4653.0  314.43  4705.4  309.71  4808.4  297.91
  4865.1  288.76  4886.5  287.73  4964.4  278.32  4971.2  277.13  4978.7  271.27
  4981.5  270.77  5006.9  271.27  5007.0  278.93  5141.3  275.70  5271.2  276.05
  5427.3  275.82  5600.9  275.65  5756.6  279.58  5820.1  282.90  5874.6  283.07
  5912.0  284.12  6103.1  296.38  6399.9  297.18  6520.3  302.57  6569.7  300.78
  6612.1  305.42  6704.2  307.70  6774.7  314.43  6852.6  319.23  6926.5  327.62
#Mann=7,-1,0
  4575.0    0.05       0  4705.4     0.1       0  4978.7    0.07       0
  5006.9     0.1       0  5271.2    0.12       0  5427.3     0.1       0
  5874.6    0.05       0
Bank Sta=4978.7,5006.9
Exp/Cntr=0.3,0.1

Type RM Length L Ch R = 1,18223,541,541,541
BEGIN DESCRIPTION:
Walnut Creek 13.0
END DESCRIPTION:
XS GIS Cut Line= 4
      2734060.06      6740014.34      2733478.49      6740387.59
      2733278.84      6740752.17      2732137.38      6741702.67
#Sta/Elev= 30
  4253.6  316.87  4369.5  307.63  4579.2  294.28  4614.9  290.07  4645.0  290.27
  4651.0  288.27  4660.2  287.66  4666.2  289.95  4684.2  287.91  4702.5  288.46
  4717.7  286.43  4738.9  286.73  4805.7  282.64  4853.3  280.53  4984.7  278.13
  4992.5  270.29  4995.3  269.79  5020.7  270.29  5022.7  278.03  5028.4  278.38
  5328.0  275.48  5586.6  275.63  5766.8  275.27  6004.8  281.09  6204.1  289.99
  6241.9  292.15  6355.2  294.58  6661.1  312.84  6788.7  322.30  6845.7  329.50
#Mann=10,-1,0
  4253.6     0.1       0  4684.2    0.05       0  4805.7    0.12       0
  4853.3     0.1       0  4992.5    0.07       0  5020.7     0.1       0
  5328.0    0.12       0  5586.6     0.1       0  6004.8    0.12       0
  6204.1    0.05       0
Bank Sta=4992.5,5020.7
Exp/Cntr=0.3,0.1

Type RM Length L Ch R = 1,17682,531,531,531
BEGIN DESCRIPTION:
Walnut Creek 12.0
END DESCRIPTION:
XS GIS Cut Line= 3
      2733776.01      6739660.99      2733126.00      6740461.00
      2732425.96      6740911.02
#Sta/Elev= 30
  3969.2  329.21  4009.9  325.70  4089.9  319.59  4336.6  295.06  4460.4  284.78
  4559.7  278.17  4633.8  276.54  4831.9  276.58  4957.6  277.67  4964.1  272.60
  4972.0  273.85  4972.3  269.74  4975.1  269.24  5000.5  269.74  5003.0  270.18
  5007.6  277.88  5013.5  278.19  5080.2  275.18  5231.1  274.68  5393.2  274.61
  5440.2  276.64  5461.6  279.08  5512.6  284.42  5585.5  292.53  5637.0  300.87
  5694.5  306.41  5709.6  310.10  5730.8  311.92  5767.1  318.61  5832.2  324.03
#Mann=12,-1,0
  3969.2    0.12       0  4009.9     0.1       0  4336.6    0.12       0
  4460.4    0.05       0  4633.8    0.12       0  4831.9     0.1       0
  4972.3    0.07       0  5000.5     0.1       0  5231.1    0.12       0
  5393.2    0.05       0  5461.6    0.12       0  5512.6    0.05       0
Bank Sta=4972.3,5000.5
Exp/Cntr=0.3,0.1

Type RM Length L Ch R = 1,17151,558,558,558
BEGIN DESCRIPTION:
Walnut Creek 11.0
END DESCRIPTION:
XS GIS Cut Line= 3
      2733576.00      6739511.00      2732870.85      6740296.44
      2732375.97      6740561.02
#Sta/Elev= 30
  3862.9  322.21  3890.9  321.06  3967.1  313.96  4025.5  309.87  4039.7  310.84
  4139.1  305.73  4178.6  301.00  4245.3  291.86  4324.9  285.30  4429.1  278.29
  4500.2  275.43  4622.7  275.72  4716.5  275.81  4992.0  277.45  5000.0  272.66
  5005.7  272.42  5007.7  269.76  5010.5  269.26  5036.1  269.76  5037.3  275.48
  5043.9  277.70  5082.1  276.74  5109.7  273.99  5147.9  273.93  5175.6  276.27
  5323.5  295.67  5367.4  303.70  5405.6  308.23  5411.5  310.49  5479.6  320.29
#Mann=9,-1,0
  3862.9    0.12       0  3967.1     0.1       0  4178.6    0.12       0
  4324.9    0.05       0  4622.7    0.12       0  4716.5     0.1       0
  5007.7    0.07       0  5036.1     0.1       0  5175.6    0.05       0
Bank Sta=5007.7,5036.1
Exp/Cntr=0.3,0.1

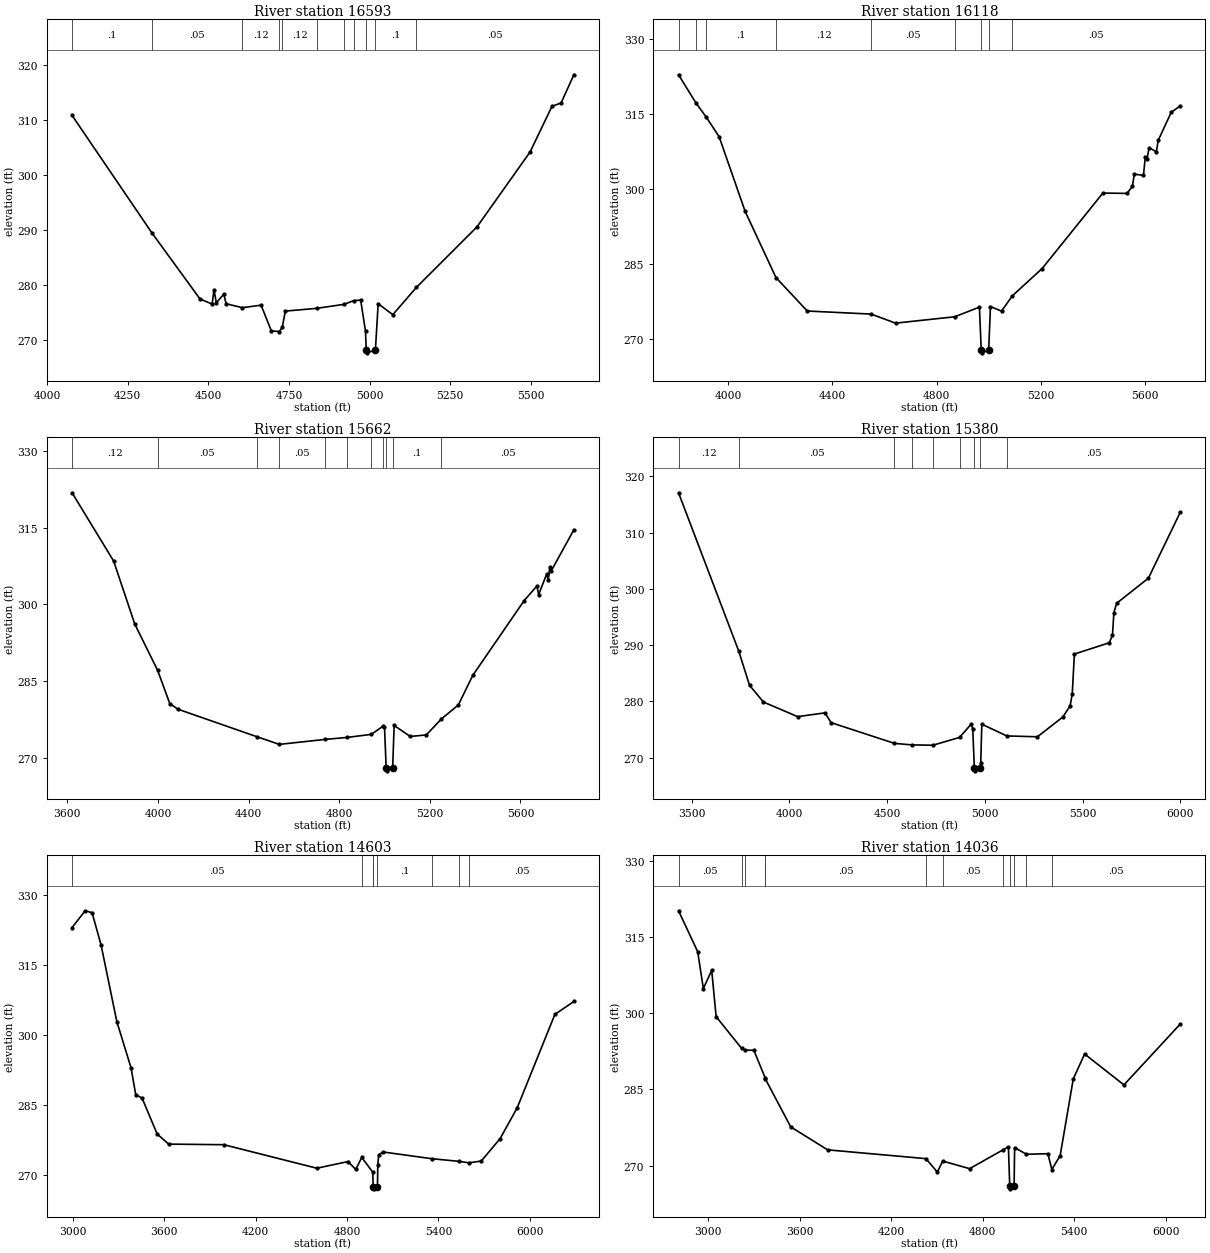
Type RM Length L Ch R = 1,16593,475,475,475
BEGIN DESCRIPTION:
Walnut Creek 10.0
END DESCRIPTION:
XS GIS Cut Line= 3
      2733375.98      6739511.01      2732576.00      6739961.00
      2731999.71      6740235.08
#Sta/Elev= 30
  4077.5  310.77  4324.9  289.42  4474.3  277.38  4511.9  276.46  4517.6  279.03
  4524.9  276.69  4547.9  278.26  4555.2  276.52  4605.5  275.80  4663.6  276.26
  4695.5  271.57  4720.6  271.47  4729.4  272.26  4738.8  275.18  4835.7  275.68
  4921.1  276.41  4950.7  277.08  4972.4  277.19  4987.4  271.52  4989.7  268.09
  4992.5  267.59  5018.1  268.09  5026.7  276.52  5072.1  274.53  5145.0  279.48
  5333.0  290.49  5497.6  304.11  5565.7  312.42  5594.0  313.04  5633.5  318.16
#Mann=11,-1,0
  4077.5     0.1       0  4324.9    0.05       0  4605.5    0.12       0
  4720.6     0.1       0  4729.4    0.12       0  4835.7     0.1       0
  4921.1    0.12       0  4950.7     0.1       0  4989.7    0.07       0
  5018.1     0.1       0  5145.0    0.05       0
Bank Sta=4989.7,5018.1
Exp/Cntr=0.3,0.1

Type RM Length L Ch R = 1,16118,456,456,456
BEGIN DESCRIPTION:
Walnut Creek 9.0
END DESCRIPTION:
XS GIS Cut Line= 3
      2733387.76      6739328.60      2732314.81      6739573.40
      2731721.21      6740146.17
#Sta/Elev= 30
  3809.6  322.90  3877.4  317.19  3915.5  314.47  3965.3  310.52  4065.2  295.58
  4183.5  282.35  4303.7  275.66  4548.7  275.05  4642.2  273.24  4869.1  274.51
  4964.1  276.44  4971.1  267.80  4973.9  267.30  4999.6  267.80  5006.5  276.56
  5048.9  275.64  5090.6  278.71  5204.6  284.15  5437.9  299.25  5530.0  299.18
  5551.1  300.57  5558.3  303.03  5593.5  302.79  5600.7  306.48  5607.7  306.12
  5614.9  308.30  5643.2  307.51  5650.1  309.78  5699.8  315.36  5735.0  316.70
#Mann=9,-1,0
  3809.6    0.05       0  3877.4    0.12       0  3915.5     0.1       0
  4183.5    0.12       0  4548.7    0.05       0  4869.1    0.12       0
  4971.1    0.07       0  4999.6    0.12       0  5090.6    0.05       0
Bank Sta=4971.1,4999.6
Exp/Cntr=0.3,0.1

Type RM Length L Ch R = 1,15662,282,282,282
BEGIN DESCRIPTION:
Walnut Creek 8.5
END DESCRIPTION:
XS GIS Cut Line= 3
      2733445.00      6739036.94      2732158.56      6739172.35
      2731471.59      6739786.47
#Sta/Elev= 30
  3620.9  321.83  3804.4  308.47  3897.5  296.15  3998.7  287.06  4052.3  280.56
  4088.5  279.46  4436.0  274.09  4535.8  272.58  4735.2  273.54  4835.0  273.94
  4942.0  274.54  4994.8  276.18  5000.0  276.04  5007.5  267.90  5010.3  267.40
  5036.0  267.90  5042.6  276.28  5113.7  274.13  5184.7  274.43  5251.2  277.56
  5326.0  280.30  5389.6  286.08  5616.1  300.70  5672.9  303.59  5680.4  301.89
  5715.6  305.88  5722.7  304.73  5729.8  307.30  5736.5  306.57  5835.9  314.59
#Mann=11,-1,0
  3620.9    0.12       0  3998.7    0.05       0  4436.0    0.12       0
  4535.8    0.05       0  4735.2    0.12       0  4835.0    0.05       0
  4942.0    0.12       0  4994.8     0.1       0  5007.5    0.07       0
  5036.0     0.1       0  5251.2    0.05       0
Bank Sta=5007.5,5036
Exp/Cntr=0.3,0.1

Type RM Length L Ch R = 1,15380,777,777,777
BEGIN DESCRIPTION:
Walnut Creek 8.0
END DESCRIPTION:
XS GIS Cut Line= 3
      2733455.40      6739000.47      2732674.19      6738703.60
      2731075.22      6739365.07
#Sta/Elev= 30
  3433.3  317.07  3740.9  288.97  3796.4  282.87  3867.0  279.90  4042.4  277.30
  4182.3  277.97  4213.6  276.23  4537.5  272.55  4625.7  272.28  4734.2  272.22
  4870.3  273.61  4930.9  276.00  4938.0  275.08  4946.0  268.17  4948.8  267.67
  4974.5  268.17  4978.7  268.99  4984.2  275.96  5112.3  273.87  5268.7  273.72
  5399.1  277.25  5435.8  279.22  5446.6  281.29  5457.7  288.42  5635.8  290.42
  5652.3  291.74  5659.7  295.79  5673.9  297.44  5836.2  301.90  5999.4  313.63
#Mann=9,-1,0
  3433.3    0.12       0  3740.9    0.05       0  4537.5    0.12       0
  4625.7    0.05       0  4734.2    0.12       0  4870.3    0.05       0
  4946.0    0.07       0  4974.5    0.05       0  5112.3    0.05       0
Bank Sta=4946,4974.5
Exp/Cntr=0.3,0.1

Type RM Length L Ch R = 1,14603,567,567,567
BEGIN DESCRIPTION:
Walnut Creek 7.0
END DESCRIPTION:
XS GIS Cut Line= 4
      2733960.35      6737663.03      2732948.46      6737930.41
      2732262.73      6738316.10      2730950.65      6738961.73
#Sta/Elev= 30
  2994.5  323.06  3080.5  326.66  3125.9  326.25  3185.2  319.28  3288.6  302.83
  3381.7  292.94  3412.7  287.13  3454.1  286.43  3553.2  278.71  3628.6  276.53
  3991.9  276.40  4601.8  271.35  4807.1  272.78  4857.7  271.08  4897.1  273.66
  4969.5  270.51  4971.8  267.42  4974.6  266.92  5000.3  267.42  5002.5  272.10
  5008.5  274.22  5036.5  274.84  5356.3  273.40  5534.0  272.83  5603.0  272.51
  5682.4  272.90  5806.1  277.72  5918.4  284.36  6165.6  304.40  6290.2  307.17
#Mann=8,-1,0
  2994.5    0.05       0  4897.1    0.12       0  4969.5     0.1       0
  4971.8    0.07       0  5000.3     0.1       0  5356.3    0.05       0
  5534.0     0.1       0  5603.0    0.05       0
Bank Sta=4971.8,5000.3
Exp/Cntr=0.3,0.1

Type RM Length L Ch R = 1,14036,286,286,286
BEGIN DESCRIPTION:
Walnut Creek 6.0
END DESCRIPTION:
XS GIS Cut Line= 3
      2734044.02      6737123.38      2731945.02      6738076.52
      2731050.07      6738487.57
#Sta/Elev= 30
  2805.9  320.14  2931.6  312.09  2968.5  304.85  3023.4  308.40  3052.5  299.31
  3219.6  293.08  3241.7  292.74  3299.7  292.70  3374.0  287.27  3375.5  287.04
  3541.4  277.64  3783.2  273.12  4428.0  271.39  4502.9  268.74  4537.8  270.91
  4714.7  269.42  4930.5  273.07  4968.8  273.69  4977.6  265.95  4980.4  265.45
  5006.1  265.95  5009.5  273.55  5087.1  272.25  5227.7  272.36  5253.6  269.24
  5308.2  272.00  5394.1  287.07  5468.5  291.97  5726.3  285.89  6096.0  297.88
#Mann=12,-1,0
  2805.9    0.05       0  3219.6     0.1       0  3241.7    0.05       0
  3374.0     0.1       0  3375.5    0.05       0  4428.0    0.12       0
  4537.8    0.05       0  4930.5    0.12       0  4977.6    0.07       0
  5006.1    0.12       0  5087.1     0.1       0  5253.6    0.05       0
Bank Sta=4977.6,5006.1
Exp/Cntr=0.3,0.1

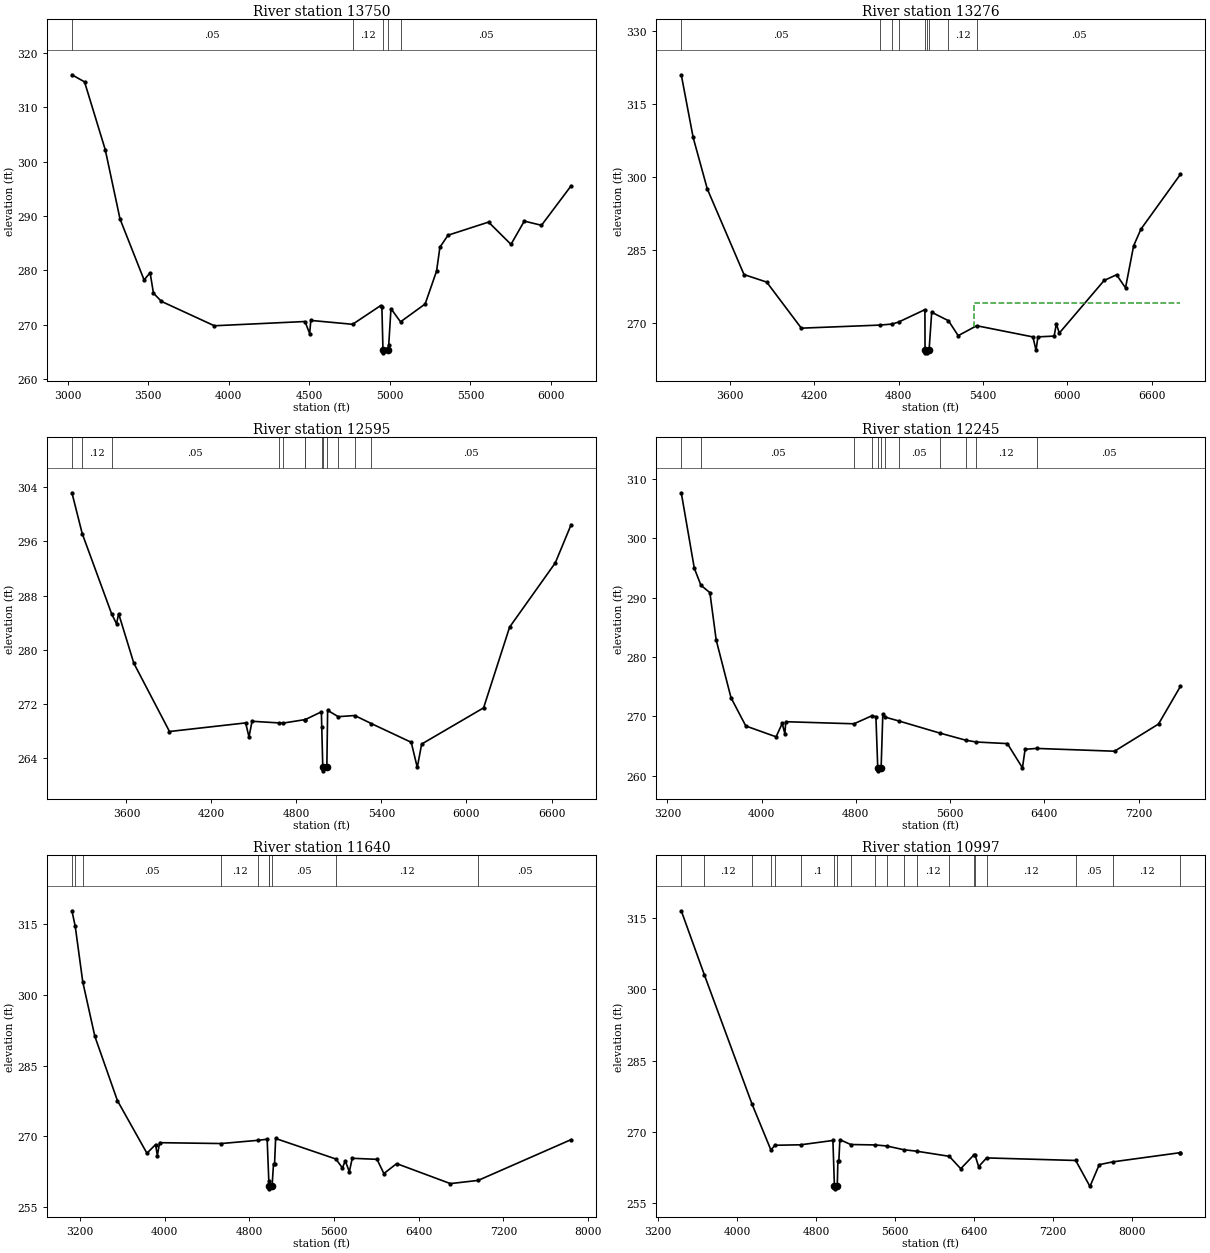
Type RM Length L Ch R = 1,13750,474,474,474
BEGIN DESCRIPTION:
Walnut Creek 5.0
END DESCRIPTION:
XS GIS Cut Line= 5
      2733460.68      6736576.50      2732045.28      6737666.41
      2731695.02      6738003.60      2731507.52      6738264.02
      2731040.82      6738455.89
#Sta/Elev= 30
  3026.6  315.92  3104.8  314.62  3233.5  302.15  3325.0  289.45  3474.4  278.26
  3511.7  279.59  3532.5  275.83  3582.3  274.32  3910.3  269.85  4472.9  270.63
  4501.9  268.42  4509.2  270.83  4768.5  270.12  4943.0  273.56  4950.2  273.32
  4957.0  265.38  4959.8  264.88  4985.6  265.38  4992.5  266.23  5006.6  272.99
  5065.9  270.57  5218.8  273.85  5289.6  279.89  5310.3  284.26  5360.6  286.47
  5612.2  288.88  5751.4  284.79  5834.1  289.06  5940.8  288.29  6124.7  295.54
#Mann=5,-1,0
  3026.6    0.05       0  4768.5    0.12       0  4957.0    0.07       0
  4985.6    0.12       0  5065.9    0.05       0
Bank Sta=4957,4985.6
Exp/Cntr=0.3,0.1

Type RM Length L Ch R = 1,13276,681,681,681
BEGIN DESCRIPTION:
Walnut Creek 4.0
END DESCRIPTION:
XS GIS Cut Line= 3
      2733262.69      6736441.13      2731075.23      6737816.10
      2730560.30      6738632.70
#Sta/Elev= 30
  3255.4  320.94  3339.9  308.06  3440.5  297.48  3701.5  279.90  3862.8  278.35
  4109.0  268.89  4666.7  269.52  4754.1  269.73  4800.2  270.14  4987.6  272.69
  4988.6  264.32  4991.4  263.82  5000.0  263.82  5017.2  264.32  5035.9  272.15
  5154.9  270.42  5224.4  267.35  5355.9  269.39  5755.5  267.09  5777.9  264.32
  5790.9  267.10  5906.6  267.26  5921.9  269.76  5943.1  267.88  6262.0  278.69
  6350.3  279.86  6413.9  277.16  6471.5  285.80  6523.3  289.22  6804.5  300.50
#Mann=9,-1,0
  3255.4    0.05       0  4666.7    0.12       0  4754.1    0.05       0
  4800.2    0.12       0  4988.6    0.07       0  5000.0     0.1       0
  5017.2    0.05       0  5154.9    0.12       0  5355.9    0.05       0
#XS Ineff=2,0
       0                 5340.00    0.00  274.00
Permanent Ineff=
       F       F
Bank Sta=4988.6,5017.2
Exp/Cntr=0.3,0.1

Type RM Length L Ch R = 1,12595,350,350,350
BEGIN DESCRIPTION:
Walnut Creek 3.7
END DESCRIPTION:
XS GIS Cut Line= 5
      2732860.43      6736236.71      2731823.97      6736960.67
      2730954.18      6737471.09      2730527.10      6738169.00
      2730532.31      6738601.29
#Sta/Elev= 30
  3215.2  303.17  3287.6  297.16  3496.2  285.27  3530.0  283.85  3544.8  285.34
  3652.1  278.03  3903.7  267.96  4441.4  269.23  4464.8  267.16  4486.5  269.47
  4675.1  269.23  4708.2  269.21  4862.0  269.72  4862.1  269.72  4975.7  270.86
  4978.5  268.61  4985.7  262.66  4988.5  262.16  5014.3  262.66  5019.9  271.08
  5094.8  270.15  5211.2  270.32  5327.5  269.14  5610.0  266.37  5652.6  262.66
  5683.5  266.11  6120.7  271.45  6304.4  283.36  6626.7  292.83  6738.5  298.47
#Mann=13,-1,0
  3215.2    0.05       0  3287.6    0.12       0  3496.2    0.05       0
  4675.1     0.1       0  4708.2    0.05       0  4862.0     0.1       0
  4862.1    0.05       0  4978.5     0.1       0  4985.7    0.07       0
  5014.3     0.1       0  5094.8    0.12       0  5211.2     0.1       0
  5327.5    0.05       0
Bank Sta=4985.7,5014.3
Exp/Cntr=0.3,0.1

Type RM Length L Ch R = 1,12245,605,605,605
BEGIN DESCRIPTION:
Walnut Creek 3.5
END DESCRIPTION:
XS GIS Cut Line= 5
      2732719.82      6736174.21      2731464.60      6736851.29
      2730594.81      6737361.71      2729723.03      6738058.46
      2729568.79      6738726.19
#Sta/Elev= 30
  3318.4  307.61  3429.1  294.92  3485.2  292.06  3561.3  290.82  3614.8  282.85
  3740.5  273.15  3866.1  268.40  4123.2  266.58  4174.9  268.83  4197.6  267.09
  4205.1  269.12  4783.8  268.77  4937.5  270.13  4970.1  269.97  4985.7  261.36
  4988.5  260.86  5014.3  261.36  5028.8  270.43  5050.7  269.88  5167.0  269.23
  5510.6  267.22  5731.0  266.02  5819.5  265.71  6085.5  265.44  6213.6  261.36
  6236.0  264.48  6333.6  264.63  6994.9  264.16  7368.2  268.73  7554.4  275.07
#Mann=12,-1,0
  3318.4    0.12       0  3485.2    0.05       0  4783.8    0.12       0
  4937.5     0.1       0  4985.7    0.07       0  5014.3     0.1       0
  5050.7    0.12       0  5167.0    0.05       0  5510.6    0.12       0
  5731.0    0.05       0  5819.5    0.12       0  6333.6    0.05       0
Bank Sta=4985.7,5014.3
Exp/Cntr=0.3,0.1

Type RM Length L Ch R = 1,11640,643,643,643
BEGIN DESCRIPTION:
Walnut Creek 3.4
END DESCRIPTION:
XS GIS Cut Line= 6
      2732698.97      6735991.92      2731443.76      6736669.00
      2730823.97      6736700.25      2730185.61      6737049.02
      2729271.65      6737739.92      2729126.05      6738523.21
#Sta/Elev= 30
  3123.5  317.84  3154.8  314.52  3225.9  302.74  3339.9  291.21  3553.2  277.57
  3832.1  266.41  3914.0  268.26  3930.2  265.91  3952.1  268.65  4535.2  268.47
  4884.5  269.16  4968.0  269.38  4983.7  260.49  4985.7  259.36  4988.5  258.86
  5014.3  259.36  5028.0  264.11  5038.1  264.22  5048.1  269.54  5617.0  265.19
  5678.9  263.30  5706.4  264.80  5744.4  262.47  5771.9  265.34  6006.2  265.12
  6070.8  262.10  6191.5  264.21  6699.2  259.97  6961.7  260.65  7840.1  269.30
#Mann=10,-1,0
  3123.5    0.05       0  3154.8    0.12       0  3225.9    0.05       0
  4535.2    0.12       0  4884.5     0.1       0  4983.7    0.05       0
  4985.7    0.04       0  5014.3    0.05       0  5617.0    0.12       0
  6961.7    0.05       0
Bank Sta=4985.7,5014.3
Exp/Cntr=0.3,0.1

Type RM Length L Ch R = 1,10997,498,498,498
BEGIN DESCRIPTION:
Walnut Creek 3.2
END DESCRIPTION:
XS GIS Cut Line= 4
      2732730.21      6735715.88      2731422.93      6736262.75
      2730865.64      6736309.63      2728245.81      6737919.02
#Sta/Elev= 30
  3435.9  316.53  3670.5  302.99  4152.5  275.81  4342.7  266.19  4383.5  267.17
  4643.6  267.27  4970.3  268.18  4985.7  258.50  4988.5  258.00  5014.3  258.50
  5020.5  263.83  5030.5  263.90  5040.6  268.35  5150.5  267.33  5400.1  267.24
  5515.4  267.02  5688.0  266.23  5818.4  265.92  6147.3  264.85  6263.8  262.24
  6399.1  265.18  6407.6  265.16  6444.6  262.67  6525.5  264.51  7427.1  263.97
  7571.3  258.50  7665.3  263.09  7803.0  263.68  8486.5  265.62  8486.9  265.62
#Mann=20,-1,0
  3435.9    0.05       0  3670.5    0.12       0  4152.5    0.05       0
  4342.7    0.12       0  4383.5    0.05       0  4643.6     0.1       0
  4985.7    0.07       0  5014.3     0.1       0  5150.5    0.12       0
  5400.1    0.05       0  5515.4    0.12       0  5688.0    0.05       0
  5818.4    0.12       0  6147.3    0.05       0  6399.1    0.12       0
  6407.6    0.05       0  6525.5    0.12       0  7427.1    0.05       0
  7803.0    0.12       0  8486.5    0.05       0
Bank Sta=4985.7,5014.3
Exp/Cntr=0.3,0.1