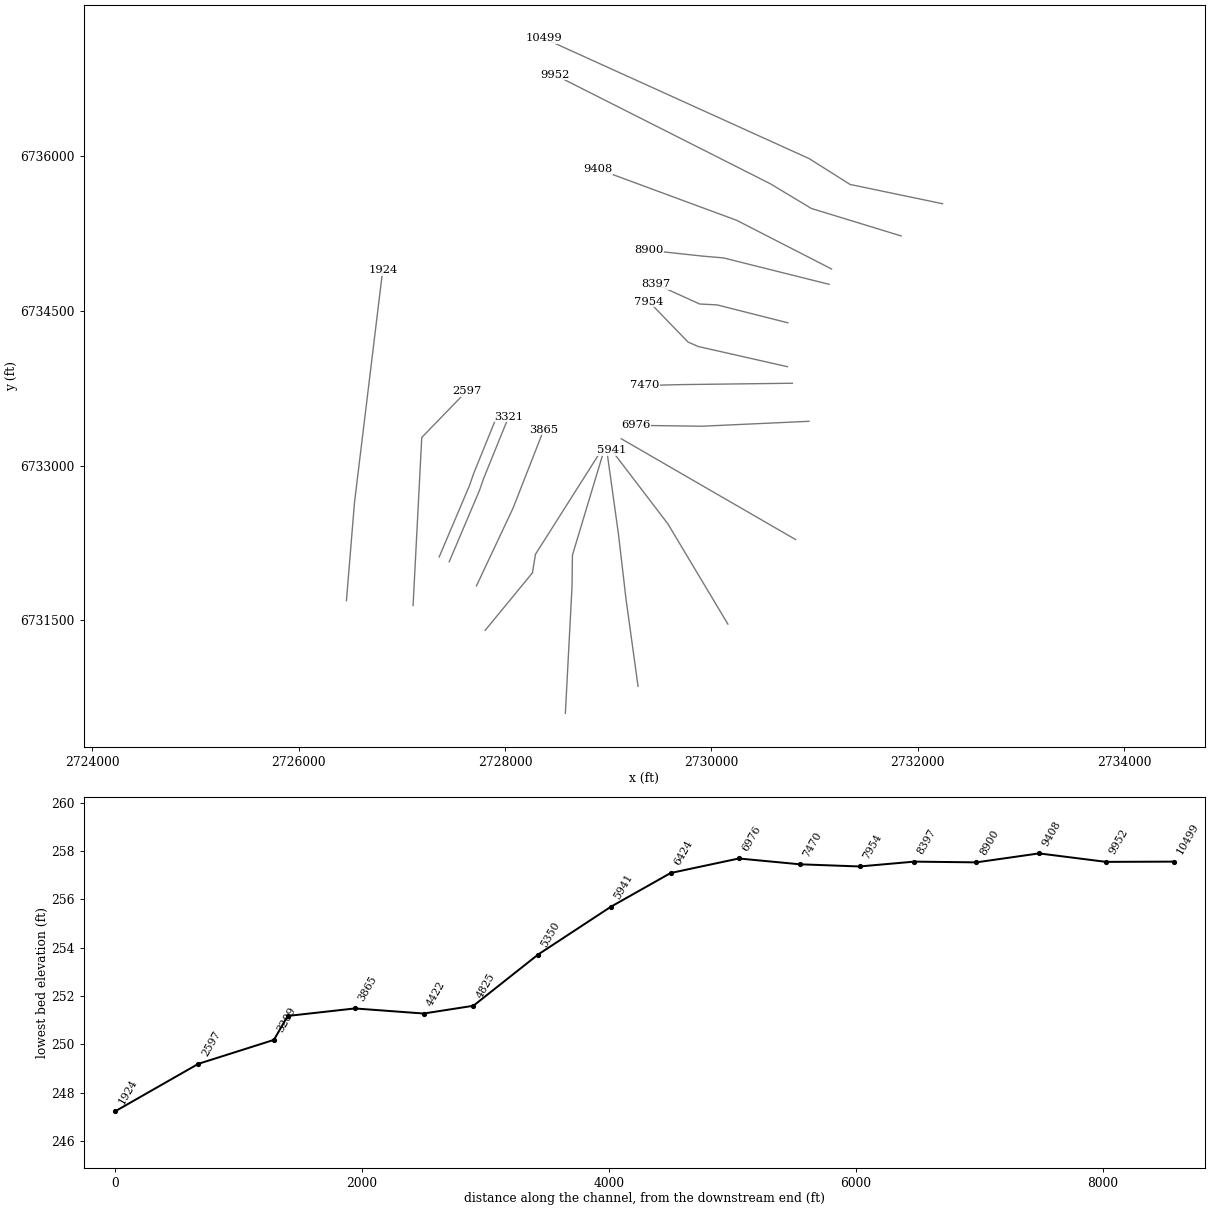
HEC-RAS study Walnut Creek.prj: Walnut Creek Base Level Engineering

--- Walnut Creek.g01 (geometry) --- (continued)

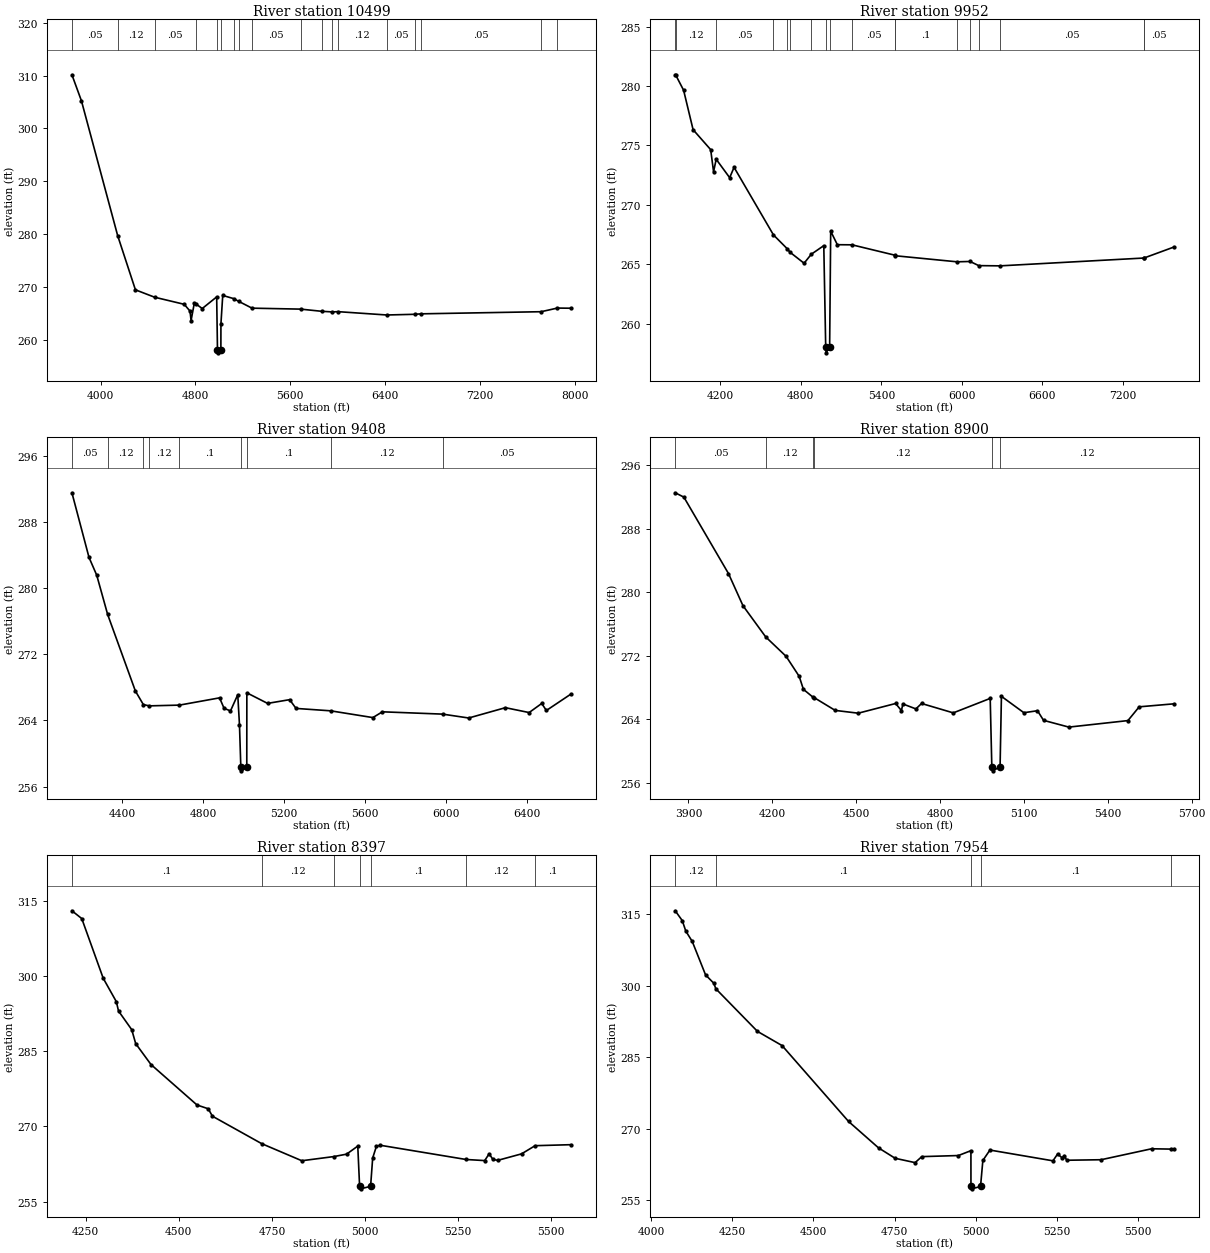
Type RM Length L Ch R = 1,10499,547,547,547
BEGIN DESCRIPTION:
Walnut Creek 3.1
END DESCRIPTION:
XS GIS Cut Line= 4
      2732240.34      6735539.75      2731344.81      6735726.29
      2730948.97      6735976.29      2728376.05      6737142.96
#Sta/Elev= 30
  3758.0  310.16  3838.4  305.22  4143.7  279.74  4293.6  269.48  4455.7  268.08
  4705.3  266.74  4754.1  265.45  4762.9  263.66  4790.1  266.94  4804.3  266.81
  4857.1  265.94  4978.9  268.14  4985.7  258.06  4988.5  257.56  5014.3  258.06
  5014.8  263.06  5030.0  268.42  5121.8  267.82  5163.8  267.31  5277.1  266.01
  5687.5  265.83  5863.4  265.42  5954.8  265.30  6002.1  265.35  6413.8  264.72
  6647.9  264.85  6705.8  264.94  7715.3  265.34  7852.7  266.03  7966.0  266.00
#Mann=18,-1,0
  3758.0    0.05       0  4143.7    0.12       0  4455.7    0.05       0
  4804.3     0.1       0  4985.7    0.07       0  5014.3     0.1       0
  5121.8    0.05       0  5163.8    0.12       0  5277.1    0.05       0
  5687.5     0.1       0  5863.4    0.12       0  5954.8     0.1       0
  6002.1    0.12       0  6413.8    0.05       0  6647.9    0.12       0
  6705.8    0.05       0  7715.3    0.12       0  7852.7    0.05       0
Bank Sta=4985.7,5014.3
Exp/Cntr=0.3,0.1

Type RM Length L Ch R = 1,9952,544,544,544
BEGIN DESCRIPTION:
Walnut Creek 3.0
END DESCRIPTION:
XS GIS Cut Line= 4
      2731839.29      6735227.26      2730969.42      6735493.61
      2730571.58      6735732.99      2728479.46      6736790.84
#Sta/Elev= 30
  3863.8  280.95  3866.5  280.95  3926.3  279.65  3997.0  276.33  4128.1  274.65
  4149.6  272.79  4169.2  273.84  4269.6  272.29  4302.4  273.16  4596.2  267.47
  4700.4  266.29  4718.9  266.02  4824.2  265.09  4878.2  265.85  4971.1  266.57
  4985.4  258.05  4988.2  257.55  5014.7  258.05  5022.6  267.79  5072.1  266.65
  5181.6  266.64  5499.9  265.77  5504.0  265.72  5964.5  265.21  6061.1  265.24
  6126.0  264.89  6285.5  264.87  7359.4  265.53  7360.2  265.54  7582.2  266.46
#Mann=18,-1,0
  3863.8    0.05       0  3866.5    0.12       0  4169.2    0.05       0
  4596.2    0.12       0  4700.4    0.05       0  4718.9    0.12       0
  4878.2     0.1       0  4985.4    0.07       0  5014.7     0.1       0
  5181.6    0.05       0  5499.9    0.12       0  5504.0     0.1       0
  5964.5    0.12       0  6061.1    0.05       0  6126.0    0.12       0
  6285.5    0.05       0  7359.4    0.12       0  7360.2    0.05       0
Bank Sta=4985.4,5014.7
Exp/Cntr=0.3,0.1

Type RM Length L Ch R = 1,9408,508,508,508
BEGIN DESCRIPTION:
Walnut Creek 2.9
END DESCRIPTION:
XS GIS Cut Line= 3
      2731165.00      6734906.95      2730244.54      6735378.98
      2728902.68      6735874.59
#Sta/Elev= 30
  4150.9  291.58  4235.3  283.75  4273.4  281.60  4327.4  276.84  4464.4  267.57
  4503.7  265.93  4532.5  265.77  4681.9  265.86  4880.3  266.74  4902.7  265.47
  4934.3  265.16  4970.2  267.12  4978.7  263.48  4985.3  258.40  4988.2  257.90
  5014.8  258.40  5015.1  267.35  5117.5  266.07  5226.4  266.52  5258.2  265.46
  5428.9  265.17  5637.7  264.35  5684.8  265.05  5982.1  264.77  6111.2  264.30
  6292.5  265.55  6409.7  264.96  6472.0  266.06  6495.0  265.21  6615.8  267.19
#Mann=9,-1,0
  4150.9    0.05       0  4327.4    0.12       0  4503.7    0.05       0
  4532.5    0.12       0  4681.9     0.1       0  4985.3    0.07       0
  5014.8     0.1       0  5428.9    0.12       0  5982.1    0.05       0
Bank Sta=4985.3,5014.8
Exp/Cntr=0.3,0.1

Type RM Length L Ch R = 1,8900,503,503,503
BEGIN DESCRIPTION:
Walnut Creek 2.8
END DESCRIPTION:
XS GIS Cut Line= 4
      2731140.80      6734758.41      2730116.51      6735014.49
      2729912.51      6735031.85      2729391.71      6735088.27
#Sta/Elev= 30
  3852.9  292.50  3883.9  291.95  4043.4  282.34  4095.2  278.30  4176.6  274.37
  4249.5  271.93  4296.2  269.42  4311.4  267.78  4346.8  266.76  4350.7  266.72
  4425.1  265.13  4507.5  264.78  4641.2  266.00  4661.9  265.11  4667.3  265.94
  4713.7  265.32  4734.0  266.00  4847.4  264.82  4979.5  266.64  4985.3  258.03
  4988.2  257.53  5014.8  258.03  5019.6  266.90  5099.9  264.84  5148.6  265.09
  5170.3  263.88  5260.8  263.03  5472.1  263.85  5512.3  265.58  5637.3  265.96
#Mann=6,-1,0
  3852.9    0.05       0  4176.6    0.12       0  4346.8    0.05       0
  4350.7    0.12       0  4985.3    0.07       0  5014.8    0.12       0
Bank Sta=4985.3,5014.8
Exp/Cntr=0.3,0.1

Type RM Length L Ch R = 1,8397,443,443,443
BEGIN DESCRIPTION:
Walnut Creek 2.6
END DESCRIPTION:
XS GIS Cut Line= 4
      2730741.55      6734385.14      2730055.74      6734558.76
      2729886.47      6734567.44      2729465.49      6734758.40
#Sta/Elev= 30
  4213.1  312.98  4239.5  311.43  4297.1  299.53  4332.3  294.87  4338.2  293.00
  4373.6  289.29  4384.3  286.50  4425.3  282.34  4548.9  274.27  4579.0  273.52
  4590.2  272.04  4722.4  266.57  4830.2  263.16  4916.0  263.99  4950.3  264.47
  4980.4  266.08  4985.3  258.06  4988.1  257.56  5014.8  258.06  5020.4  263.70
  5030.4  266.03  5040.4  266.25  5271.1  263.41  5321.1  263.19  5333.1  264.55
  5343.1  263.42  5356.2  263.24  5420.0  264.53  5456.4  266.16  5552.3  266.36
#Mann=7,-1,0
  4213.1     0.1       0  4722.4    0.12       0  4916.0     0.1       0
  4985.3    0.07       0  5014.8     0.1       0  5271.1    0.12       0
  5456.4     0.1       0
Bank Sta=4985.3,5014.8
Exp/Cntr=0.3,0.1

Type RM Length L Ch R = 1,7954,484,484,484
BEGIN DESCRIPTION:
Walnut Creek 2.4
END DESCRIPTION:
XS GIS Cut Line= 4
      2730737.17      6733959.80      2729873.45      6734155.11
      2729773.62      6734198.52      2729396.00      6734589.16
#Sta/Elev= 30
  4073.8  315.72  4095.5  313.66  4106.4  311.46  4126.3  309.28  4167.3  302.27
  4192.7  300.51  4199.0  299.35  4327.4  290.40  4403.1  287.43  4608.1  271.50
  4700.4  265.96  4751.7  263.77  4813.2  262.86  4833.7  264.12  4946.5  264.35
  4985.2  265.37  4985.3  257.86  4988.1  257.36  5014.8  257.86  5022.0  263.32
  5043.8  265.50  5238.1  263.24  5252.2  264.66  5266.4  263.87  5273.3  264.34
  5280.3  263.36  5386.5  263.47  5542.2  265.77  5602.0  265.70  5611.5  265.77
#Mann=5,-1,0
  4073.8    0.12       0  4199.0     0.1       0  4985.3    0.07       0
  5014.8     0.1       0  5602.0    0.12       0
Bank Sta=4985.3,5014.8
Exp/Cntr=0.3,0.1

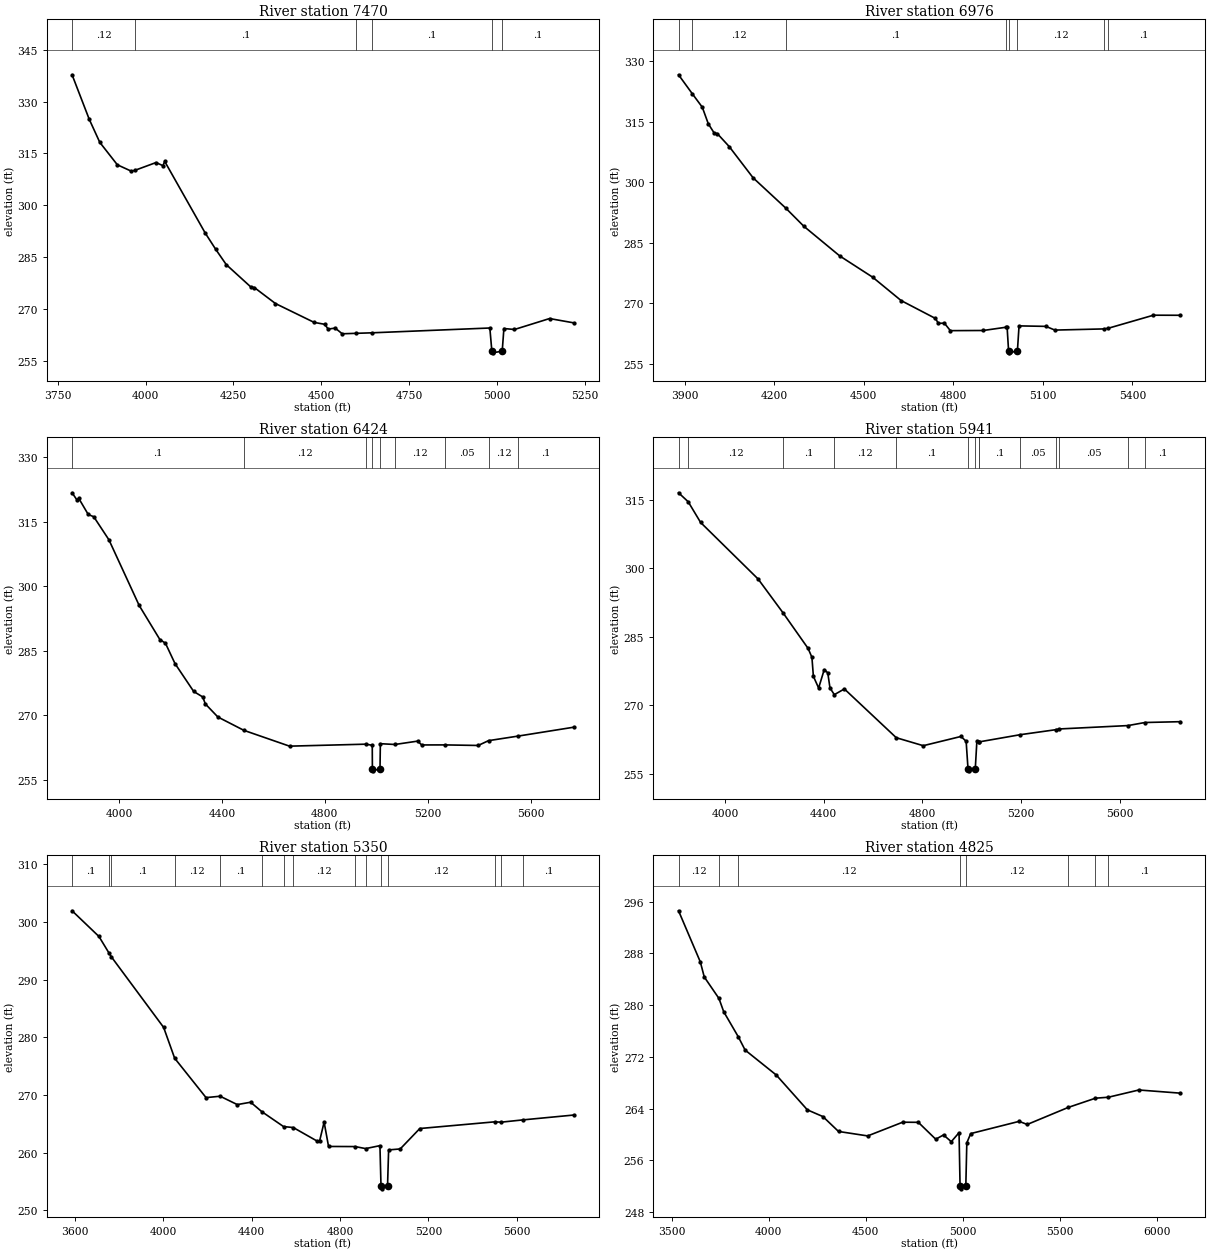
Type RM Length L Ch R = 1,7470,494,494,494
BEGIN DESCRIPTION:
Walnut Creek 2.2
END DESCRIPTION:
XS GIS Cut Line= 3
      2730784.87      6733799.21      2729717.20      6733786.19
      2729356.96      6733777.51
#Sta/Elev= 30
  3790.6  337.72  3839.5  324.86  3869.5  318.21  3919.5  311.73  3959.5  309.88
  3969.6  310.14  4029.5  312.38  4049.2  311.48  4054.2  312.72  4169.5  292.04
  4199.5  287.32  4229.5  282.91  4299.5  276.45  4309.5  276.29  4369.5  271.68
  4479.5  266.24  4509.5  265.69  4519.5  264.31  4539.5  264.59  4559.5  262.95
  4598.2  263.08  4643.9  263.23  4979.6  264.62  4985.3  257.95  4988.1  257.45
  5014.8  257.95  5019.6  264.47  5049.6  264.19  5149.6  267.35  5218.7  266.10
#Mann=6,-1,0
  3790.6    0.12       0  3969.6     0.1       0  4598.2    0.12       0
  4643.9     0.1       0  4985.3    0.07       0  5014.8     0.1       0
Bank Sta=4985.3,5014.8
Exp/Cntr=0.3,0.1

Type RM Length L Ch R = 1,6976,552,552,552
BEGIN DESCRIPTION:
Walnut Creek 2.0
END DESCRIPTION:
XS GIS Cut Line= 3
      2730945.50      6733430.29      2729908.17      6733382.54
      2729265.86      6733391.22
#Sta/Elev= 30
  3879.7  326.61  3925.4  321.95  3959.3  318.57  3979.3  314.48  3999.3  312.14
  4009.3  312.05  4049.4  308.82  4129.5  301.07  4238.2  293.61  4299.6  289.05
  4419.8  281.70  4529.9  276.44  4625.2  270.65  4740.1  266.22  4750.1  265.00
  4770.1  265.05  4790.2  263.19  4900.3  263.23  4977.0  264.04  4980.3  264.07
  4985.2  258.19  4988.1  257.69  5014.8  258.19  5020.3  264.37  5110.3  264.25
  5140.3  263.33  5304.6  263.62  5318.9  263.78  5470.4  267.02  5560.5  267.00
#Mann=8,-1,0
  3879.7     0.1       0  3925.4    0.12       0  4238.2     0.1       0
  4977.0    0.12       0  4985.2    0.07       0  5014.8    0.12       0
  5304.6    0.12       0  5318.9     0.1       0
Bank Sta=4985.2,5014.8
Exp/Cntr=0.3,0.1

Type RM Length L Ch R = 1,6424,483,483,483
BEGIN DESCRIPTION:
Walnut Creek 1.8
END DESCRIPTION:
XS GIS Cut Line= 3
      2730815.26      6732284.47      2729869.11      6732831.33
      2729126.93      6733261.01
#Sta/Elev= 30
  3817.9  321.75  3837.7  320.01  3843.4  320.50  3880.7  316.71  3902.3  316.17
  3961.1  310.82  4078.8  295.54  4159.2  287.62  4180.8  286.77  4218.1  282.02
  4290.6  275.55  4325.8  274.27  4335.8  272.66  4384.6  269.61  4485.6  266.51
  4663.1  262.83  4959.3  263.29  4984.7  263.04  4985.2  257.59  4988.1  257.09
  5014.8  257.59  5016.2  263.40  5072.9  263.22  5161.1  264.00  5176.9  263.11
  5268.7  263.12  5396.4  262.99  5436.6  264.11  5552.6  265.18  5768.3  267.24
#Mann=9,-1,0
  3817.9     0.1       0  4485.6    0.12       0  4959.3     0.1       0
  4985.2    0.07       0  5014.8     0.1       0  5072.9    0.12       0
  5268.7    0.05       0  5436.6    0.12       0  5552.6     0.1       0
Bank Sta=4985.2,5014.8
Exp/Cntr=0.3,0.1

Type RM Length L Ch R = 1,5941,591,591,591
BEGIN DESCRIPTION:
Walnut Creek 1.6
END DESCRIPTION:
XS GIS Cut Line= 3
      2730159.90      6731464.15      2729578.31      6732436.36
      2729031.42      6733152.53
#Sta/Elev= 30
  3811.9  316.51  3851.0  314.55  3901.4  310.02  4134.5  297.65  4234.9  290.30
  4337.1  282.47  4352.6  280.52  4358.5  276.37  4379.8  273.81  4402.5  277.85
  4416.8  277.13  4425.8  273.83  4443.4  272.36  4484.1  273.61  4694.6  262.94
  4803.9  261.20  4956.9  263.22  4977.7  262.16  4985.2  256.20  4988.1  255.70
  5014.8  256.20  5021.3  262.26  5028.7  262.02  5029.1  262.02  5197.6  263.61
  5341.5  264.70  5355.8  264.86  5634.0  265.60  5702.5  266.27  5845.9  266.45
#Mann=14,-1,0
  3811.9    0.05       0  3851.0    0.12       0  4234.9     0.1       0
  4443.4    0.12       0  4694.6     0.1       0  4985.2    0.07       0
  5014.8     0.1       0  5028.7    0.12       0  5029.1     0.1       0
  5197.6    0.05       0  5341.5    0.12       0  5355.8    0.05       0
  5634.0    0.12       0  5702.5     0.1       0
Bank Sta=4985.2,5014.8
Exp/Cntr=0.3,0.1

Type RM Length L Ch R = 1,5350,525,525,525
BEGIN DESCRIPTION:
Walnut Creek 1.4
END DESCRIPTION:
XS GIS Cut Line= 4
      2729289.52      6730860.45      2729172.75      6731706.06
      2729100.27      6732330.16      2728991.56      6733111.30
#Sta/Elev= 30
  3587.3  301.94  3709.0  297.48  3754.9  294.58  3765.4  293.94  4001.7  281.71
  4051.5  276.37  4193.5  269.54  4257.3  269.78  4334.9  268.33  4395.4  268.74
  4445.7  267.11  4544.1  264.52  4588.3  264.35  4697.6  261.97  4707.7  262.07
  4727.8  265.29  4747.9  261.07  4867.7  261.05  4915.8  260.70  4980.4  261.21
  4985.2  254.22  4988.1  253.72  5014.8  254.22  5019.7  260.47  5072.2  260.64
  5160.9  264.18  5499.8  265.34  5528.7  265.28  5628.2  265.68  5857.9  266.52
#Mann=15,-1,0
  3587.3     0.1       0  3754.9    0.12       0  3765.4     0.1       0
  4051.5    0.12       0  4257.3     0.1       0  4445.7    0.12       0
  4544.1    0.05       0  4588.3    0.12       0  4867.7     0.1       0
  4915.8    0.12       0  4985.2    0.07       0  5014.8    0.12       0
  5499.8    0.05       0  5528.7    0.12       0  5628.2     0.1       0
Bank Sta=4985.2,5014.8
Exp/Cntr=0.3,0.1

Type RM Length L Ch R = 1,4825,403,403,403
BEGIN DESCRIPTION:
Walnut Creek 1.2
END DESCRIPTION:
XS GIS Cut Line= 4
      2728584.88      6730598.78      2728649.31      6731826.85
      2728653.33      6732132.86      2728955.32      6733135.47
#Sta/Elev= 30
  3536.1  294.58  3648.2  286.68  3668.5  284.35  3744.1  281.03  3768.6  278.98
  3843.7  275.10  3878.8  273.05  4039.3  269.19  4199.2  263.81  4279.3  262.77
  4359.5  260.47  4509.7  259.78  4689.9  261.90  4770.4  261.88  4860.0  259.27
  4900.0  259.93  4940.0  258.89  4980.0  260.28  4985.2  252.10  4988.1  251.60
  5014.9  252.10  5020.0  258.71  5040.0  260.14  5289.3  262.03  5331.0  261.55
  5542.4  264.19  5682.1  265.61  5748.5  265.76  5905.5  266.88  6119.0  266.39
#Mann=8,-1,0
  3536.1    0.12       0  3744.1     0.1       0  3843.7    0.12       0
  4985.2    0.07       0  5014.9    0.12       0  5542.4     0.1       0
  5682.1    0.12       0  5748.5     0.1       0
Bank Sta=4985.2,5014.9
Exp/Cntr=0.3,0.1

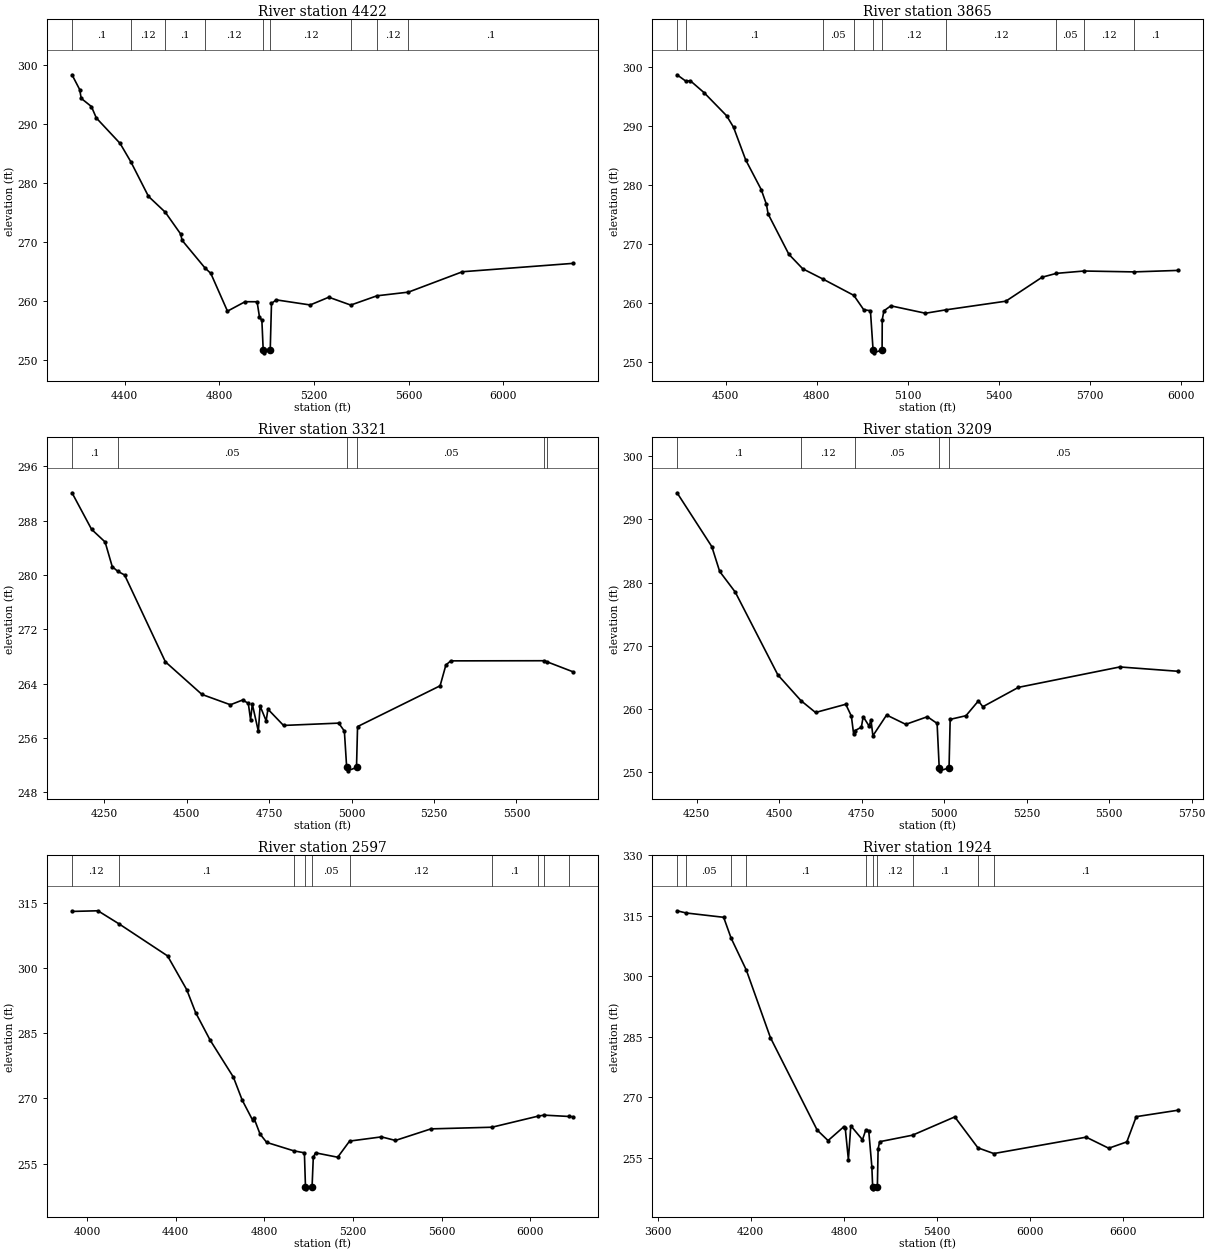
Type RM Length L Ch R = 1,4422,557,557,557
BEGIN DESCRIPTION:
Walnut Creek 1.0
END DESCRIPTION:
XS GIS Cut Line= 4
      2727807.80      6731404.11      2728265.83      6731961.23
      2728294.98      6732140.91      2728943.22      6733163.61
#Sta/Elev= 30
  4177.6  298.32  4210.0  295.82  4216.5  294.33  4259.5  292.95  4280.4  291.01
  4380.7  286.71  4426.0  283.61  4500.6  277.75  4571.6  275.07  4636.2  271.40
  4642.7  270.31  4738.9  265.66  4763.9  264.72  4834.3  258.33  4908.7  259.93
  4959.4  259.92  4969.5  257.34  4979.6  256.78  4985.2  251.78  4988.1  251.28
  5014.9  251.78  5020.2  259.64  5040.4  260.24  5183.6  259.38  5262.3  260.69
  5355.0  259.36  5465.8  260.93  5598.6  261.55  5826.9  265.00  6291.7  266.41
#Mann=9,-1,0
  4177.6     0.1       0  4426.0    0.12       0  4571.6     0.1       0
  4738.9    0.12       0  4985.2    0.07       0  5014.9    0.12       0
  5355.0    0.05       0  5465.8    0.12       0  5598.6     0.1       0
Bank Sta=4985.2,5014.9
Exp/Cntr=0.3,0.1

Type RM Length L Ch R = 1,3865,544,544,544
BEGIN DESCRIPTION:
Walnut Creek 0.8
END DESCRIPTION:
XS GIS Cut Line= 3
      2727723.22      6731834.91      2728077.55      6732587.85
      2728374.96      6733347.46
#Sta/Elev= 30
  4339.8  298.76  4368.9  297.67  4383.4  297.75  4429.0  295.71  4502.9  291.80
  4525.7  289.85  4565.7  284.30  4616.9  279.25  4633.9  276.76  4639.7  275.09
  4708.0  268.24  4753.6  265.78  4819.5  264.05  4921.8  261.26  4954.4  258.82
  4976.5  258.65  4985.2  251.99  4988.1  251.49  5014.9  251.99  5015.4  257.13
  5020.9  258.63  5043.7  259.48  5157.7  258.22  5225.1  258.80  5422.3  260.27
  5541.9  264.35  5588.7  265.00  5679.7  265.40  5844.5  265.25  5987.7  265.50
#Mann=10,-1,0
  4339.8    0.12       0  4368.9     0.1       0  4819.5    0.05       0
  4921.8    0.12       0  4985.2    0.05       0  5014.9    0.12       0
  5225.1    0.12       0  5588.7    0.05       0  5679.7    0.12       0
  5844.5     0.1       0
Bank Sta=4985.2,5014.9
Exp/Cntr=0.3,0.1

Type RM Length L Ch R = 1,3321,112,112,112
BEGIN DESCRIPTION:
Walnut Creek 0.6
END DESCRIPTION:
XS GIS Cut Line= 4
      2727458.94      6732068.59      2727753.92      6732763.91
      2727792.21      6732875.20      2728034.85      6733473.25
#Sta/Elev= 30
  4151.8  292.09  4211.2  286.71  4252.2  284.85  4273.9  281.22  4290.7  280.53
  4311.3  280.00  4435.1  267.22  4546.0  262.42  4632.4  260.90  4669.8  261.61
  4686.7  261.10  4693.5  258.70  4698.9  260.98  4717.1  257.00  4722.5  260.71
  4740.8  258.54  4746.2  260.25  4793.5  257.86  4960.9  258.20  4978.1  257.03
  4985.1  251.68  4988.0  251.18  5014.9  251.68  5018.1  257.69  5268.5  263.69
  5286.1  266.75  5300.8  267.36  5584.6  267.38  5593.6  267.21  5670.2  265.78
#Mann=6,-1,0
  4151.8     0.1       0  4290.7    0.05       0  4985.1    0.05       0
  5014.9    0.05       0  5584.6    0.12       0  5593.6    0.05       0
Bank Sta=4985.1,5014.9
Exp/Cntr=0.3,0.1

Type RM Length L Ch R = 1,3209,612,612,612
BEGIN DESCRIPTION:
Walnut Creek 0.4
END DESCRIPTION:
XS GIS Cut Line= 4
      2727361.63      6732114.74      2727656.63      6732810.08
      2727694.91      6732921.36      2727936.87      6733517.73
#Sta/Elev= 30
  4190.7  294.22  4296.1  285.69  4319.8  281.77  4367.1  278.49  4496.3  265.37
  4566.3  261.30  4610.3  259.43  4701.9  260.73  4718.9  258.86  4725.6  256.09
  4729.5  256.55  4749.2  257.10  4754.7  258.77  4772.9  257.26  4778.3  258.30
  4784.1  255.74  4825.7  259.03  4883.8  257.55  4949.2  258.76  4978.7  257.70
  4985.1  250.69  4988.0  250.19  5014.9  250.69  5018.3  258.34  5066.2  258.92
  5103.8  261.26  5117.3  260.34  5225.2  263.41  5532.4  266.64  5707.3  265.96
#Mann=5,-1,0
  4190.7     0.1       0  4566.3    0.12       0  4729.5    0.05       0
  4985.1    0.05       0  5014.9    0.05       0
Bank Sta=4985.1,5014.9
Exp/Cntr=0.3,0.1

Type RM Length L Ch R = 1,2597,673,673,673
BEGIN DESCRIPTION:
Walnut Creek 0.3
END DESCRIPTION:
XS GIS Cut Line= 3
      2727108.81      6731644.18      2727193.09      6733273.61
      2727628.51      6733723.08
#Sta/Elev= 30
  3932.1  313.00  4049.1  313.15  4146.0  310.08  4363.1  302.77  4449.6  295.00
  4489.7  289.73  4555.0  283.41  4659.9  274.90  4699.9  269.59  4746.9  264.98
  4751.9  265.60  4780.1  261.81  4810.1  259.88  4931.8  257.95  4980.3  257.48
  4985.1  249.70  4988.0  249.20  5014.9  249.70  5020.4  256.46  5030.4  257.48
  5130.5  256.47  5184.1  260.18  5327.7  261.15  5390.9  260.33  5551.1  262.99
  5826.2  263.37  6036.0  265.94  6061.6  266.15  6174.8  265.84  6189.5  265.79
#Mann=10,-1,0
  3932.1    0.12       0  4146.0     0.1       0  4931.8    0.05       0
  4985.1    0.03       0  5014.9    0.05       0  5184.1    0.12       0
  5826.2     0.1       0  6036.0    0.12       0  6061.6     0.1       0
  6174.8    0.12       0
Bank Sta=4985.1,5014.9
Exp/Cntr=0.3,0.1

Type RM Length L Ch R = 1,1924,0,0,0
BEGIN DESCRIPTION:
Walnut Creek 0.1
END DESCRIPTION:
XS GIS Cut Line= 3
      2726462.91      6731691.95      2726541.04      6732642.51
      2726814.48      6734895.11
#Sta/Elev= 30
  3725.3  316.27  3782.9  315.73  4025.4  314.65  4073.3  309.49  4171.8  301.51
  4326.4  284.79  4627.4  261.84  4697.7  259.22  4798.4  262.63  4808.5  262.25
  4828.6  254.50  4844.2  262.89  4919.3  259.43  4940.1  261.80  4959.6  261.68
  4979.7  252.74  4984.9  247.74  4987.8  247.24  5015.2  247.74  5020.0  257.17
  5030.1  258.94  5241.5  260.56  5513.6  265.10  5662.8  257.42  5764.9  256.00
  6359.8  260.07  6505.1  257.32  6621.7  258.90  6682.2  265.16  6948.2  266.74
#Mann=10,-1,0
  3725.3    0.12       0  3782.9    0.05       0  4073.3    0.12       0
  4171.8     0.1       0  4940.1    0.12       0  4984.9    0.07       0
  5015.2    0.12       0  5241.5     0.1       0  5662.8    0.12       0
  5764.9     0.1       0
Bank Sta=4984.9,5015.2
Exp/Cntr=0.3,0.1

Chan Stop Cuts=-1