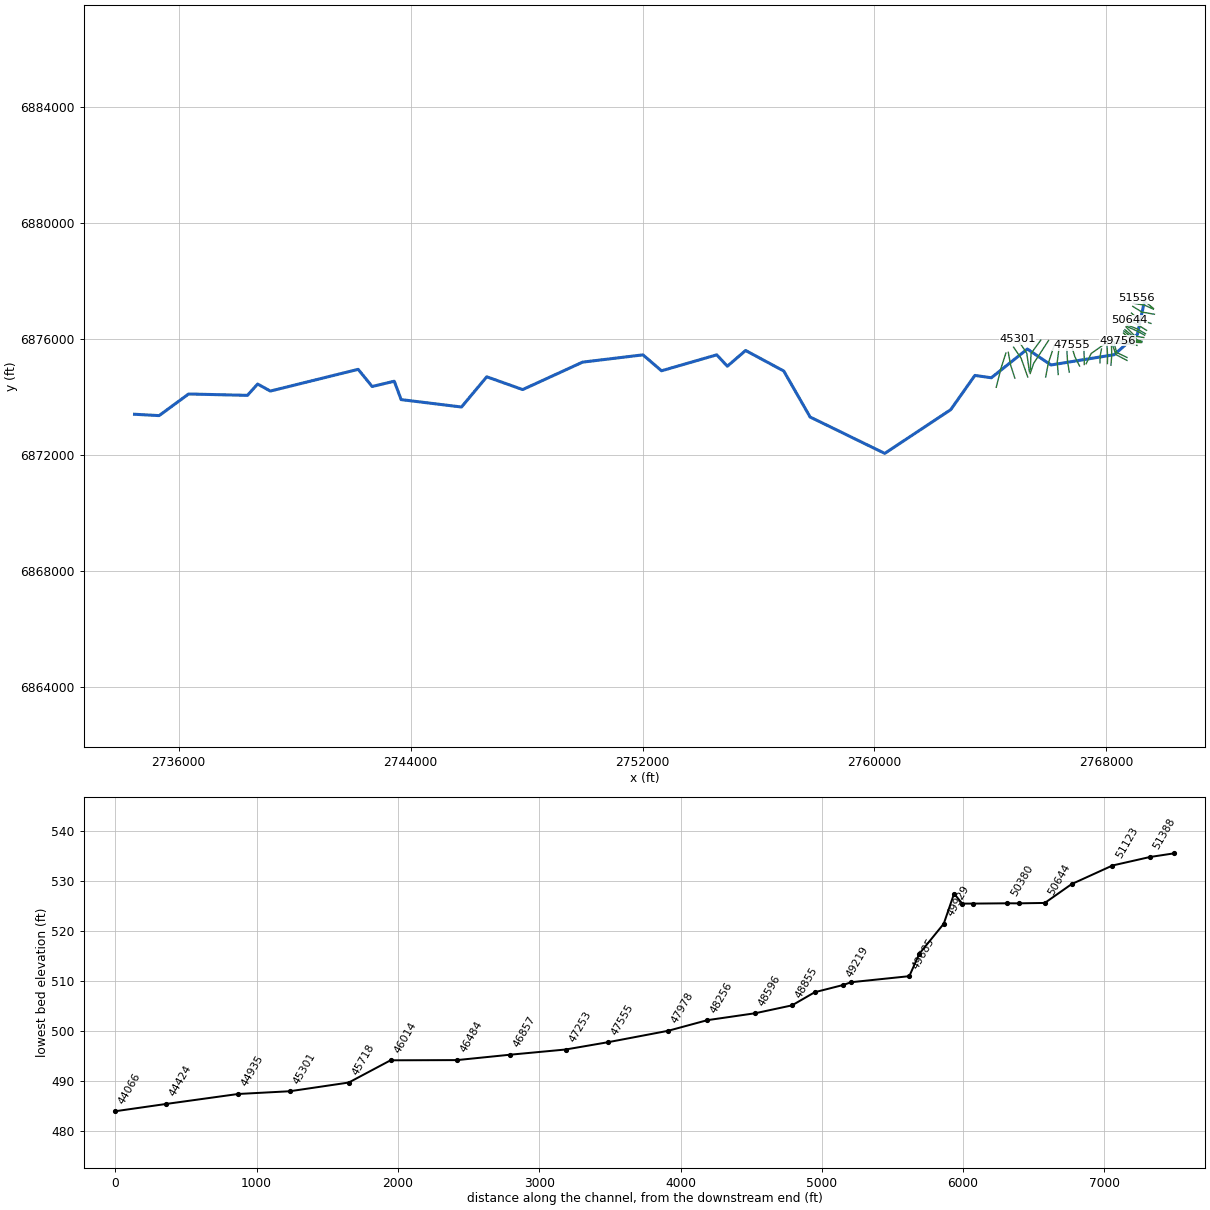
--- Wet Lacy Fork.prj (project) ---

Proj Title=Wet Lacy Fork Base Level Engineering
Current Plan=p01
Default Exp/Contr=0.3,0.1
English Units
Geom File=g01
Flow File=f01
Plan File=p01
Y Axis Title=Elevation
X Axis Title(PF)=Main Channel Distance
X Axis Title(XS)=Station
BEGIN DESCRIPTION:
Wet Lacy Fork
END DESCRIPTION:
DSS Export Rating Curves= 0
DSS Export Rating Curve Sorted= 0
DSS Export Volume Flow Curves= 0
DXF OffsetX= 0
DXF OffsetY= 0
DXF ScaleX= 1
DXF ScaleY= 10

--- Wet Lacy Fork.p01 (plan) ---

Plan Title=Multiple Run
Short Identifier=Multiple
Geom File=g01
Flow File=f01
Subcritical Flow
K Sum by GR= 0
Std Step Tol= 0.01
Critical Tol= 0.01
Num of Std Step Trials= 20
Max Error Tol= 0.3
Flow Tol Ratio= 0.001
Split Flow NTrial= 30
Split Flow Tol= 0.02
Split Flow Ratio= 0.02
Log Output Level= 0
Friction Slope Method= 1
Unsteady Friction Slope Method= 2
Unsteady Bridges Friction Slope Method= 1
Parabolic Critical Depth
Global Vel Dist=  1 , 1 , 1
Global Log Level= 0
CheckData=True
Encroach Param= -1, 0, 0, 0
BEGIN DESCRIPTION:
Multiple Run
END DESCRIPTION:

--- Wet Lacy Fork.f01 (steady flow) ---

Flow Title=Multiple
Number of Profiles=7
Profile Names=10-year,25-year,50-year,1pct_min,100-year,1pct_plu,500-year
River Rch & RM= Wet Lacy Fork,Reach-1,51556
     537     723     876     528    1054    2102    1527
River Rch & RM= Wet Lacy Fork,Reach-1,49016
     948    1320    1633    1005    2004    3999    3025
River Rch & RM= Wet Lacy Fork,Reach-1,45301
    1105    1545    1919    1183    2360    4709    3578
River Rch & RM= Wet Lacy Fork,Reach-1,41118
    1325    1858    2311    1425    2843    5673    4315
River Rch & RM= Wet Lacy Fork,Reach-1,31712
    2143    3063    3857    2404    4797    9572    7442
River Rch & RM= Wet Lacy Fork,Reach-1,26901
    2181    3106    3902    2425    4839    9655    7464
River Rch & RM= Wet Lacy Fork,Reach-1,22377
    2271    3238    4069    2530    5047   10071    7791
River Rch & RM= Wet Lacy Fork,Reach-1,22130
    3445    4992    6346    3986    7954   15870   12533
River Rch & RM= Wet Lacy Fork,Reach-1,21094
    3337    4815    6101    3821    7623   15210   11935
River Rch & RM= Wet Lacy Fork,Reach-1,18377
    3220    4624    5840    3644    7270   14506   11301
River Rch & RM= Wet Lacy Fork,Reach-1,16251
    3664    5284    6692    4186    8353   16667   13051
River Rch & RM= Wet Lacy Fork,Reach-1,14523
    3633    5231    6619    4136    8253   16467   12867
River Rch & RM= Wet Lacy Fork,Reach-1,13898
    3703    5334    6750    4219    8419   16797   13131
River Rch & RM= Wet Lacy Fork,Reach-1,12295
    3690    5309    6713    4192    8363   16687   13019
River Rch & RM= Wet Lacy Fork,Reach-1,9559
    3690    5294    6681    4163    8307   16574   12877
River Rch & RM= Wet Lacy Fork,Reach-1,3922
    6961   10052   12729    7927   15816   31557   24413
Boundary for River Rch & Prof#=Wet Lacy Fork,Reach-1,1
Up Type=0
Dn Type=1
Dn Known WS=403.69
Boundary for River Rch & Prof#=Wet Lacy Fork,Reach-1,2
Up Type=0
Dn Type=1
Dn Known WS=404.48
Boundary for River Rch & Prof#=Wet Lacy Fork,Reach-1,3
Up Type=0
Dn Type=1
Dn Known WS=405.05
Boundary for River Rch & Prof#=Wet Lacy Fork,Reach-1,4
Up Type=0
Dn Type=1
Dn Known WS=403.97
Boundary for River Rch & Prof#=Wet Lacy Fork,Reach-1,5
Up Type=0
Dn Type=1
Dn Known WS=405.62
Boundary for River Rch & Prof#=Wet Lacy Fork,Reach-1,6
Up Type=0
Dn Type=1
Dn Known WS=407.78
Boundary for River Rch & Prof#=Wet Lacy Fork,Reach-1,7
Up Type=0
Dn Type=1
Dn Known WS=406.9

--- Wet Lacy Fork.g01 (geometry) ---

Geom Title=Existing Conditions
Program Version=4.10

River Reach=Wet Lacy Fork   ,Reach-1
Reach XY= 30
        2769326.        6877361.      2769073.09      6876168.91
      2768270.92      6875466.08       2766091.7      6875111.02
        2765276.        6875661.      2764033.07      6874669.99
      2763465.84      6874750.64      2762632.17      6873568.86
      2760355.79      6872060.64      2757781.45      6873316.22
      2756872.93      6874902.71       2755555.9       6875611.1
      2754926.25      6875067.99      2754560.53      6875461.01
      2752655.81      6874910.71      2752015.52      6875460.45
      2749931.41      6875208.88      2747865.47      6874262.07
        2746626.      6874703.44      2745755.82      6873660.71
        2743673.      6873916.15       2743435.7      6874550.82
       2742672.9      6874368.51      2742191.18      6874960.64
      2739160.73      6874211.38      2738722.42      6874453.52
      2738370.51      6874062.96      2736341.28      6874110.37
       2735324.5      6873364.47        2734476.        6873411.

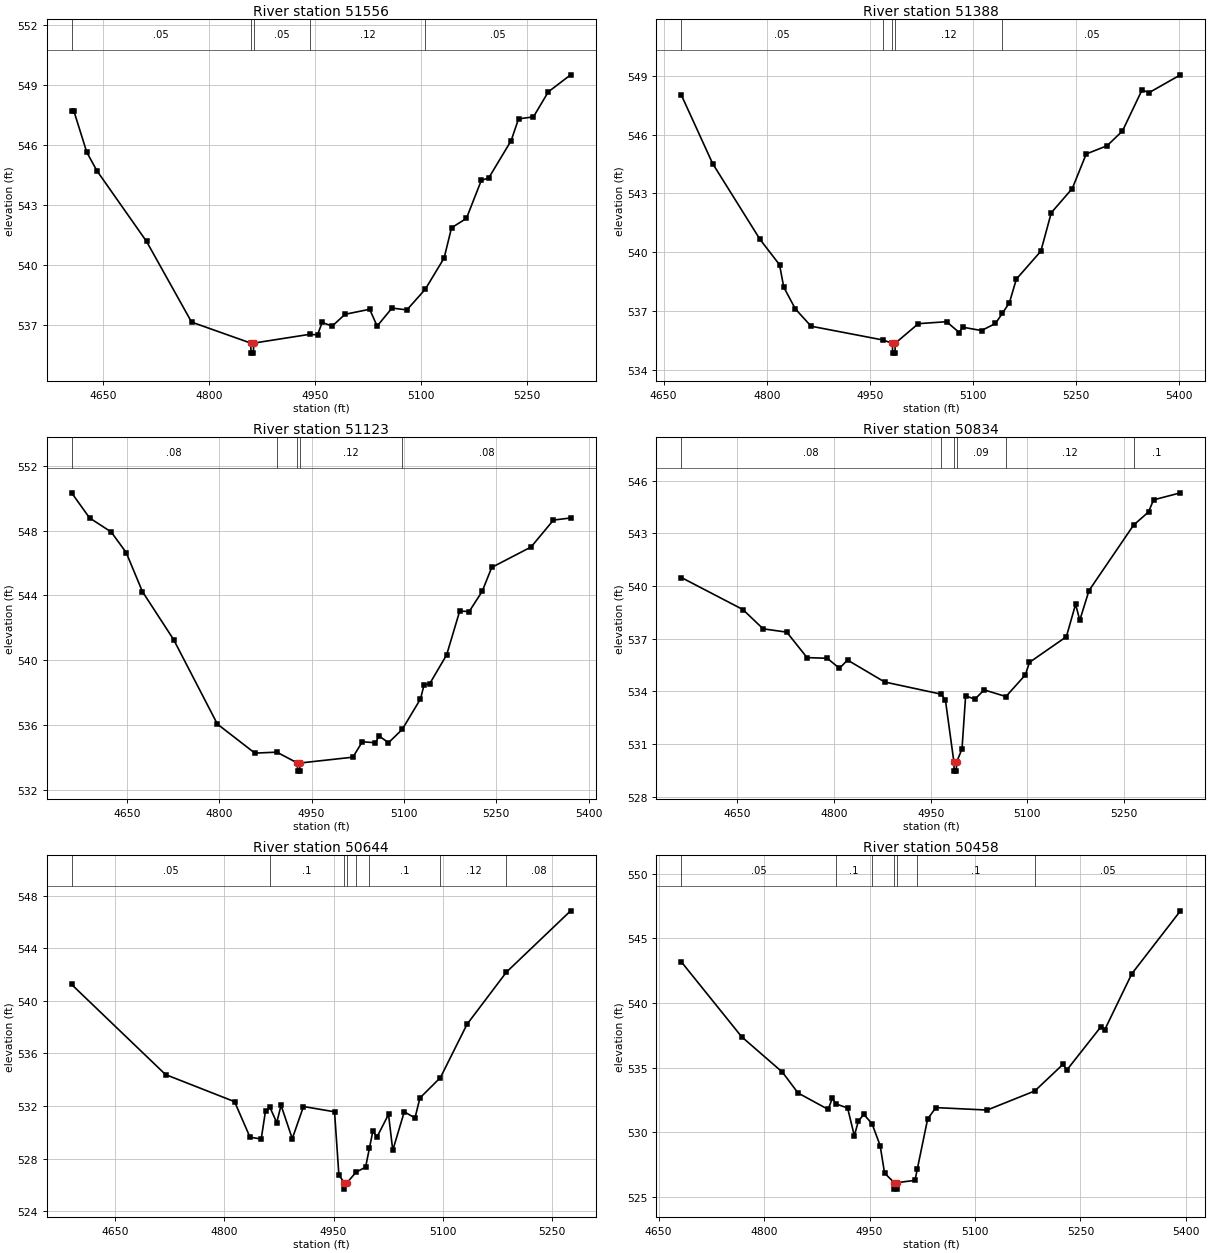
Type RM Length L Ch R = 1 ,51556   ,168,168,168
BEGIN DESCRIPTION:
Wet Lacy Fork 19
END DESCRIPTION:
XS GIS Cut Line= 3
      2769626.04      6877060.97        2769326.        6877311.
      2769025.99        6877411.
#Sta/Elev= 30
  4605.2  547.67  4608.5  547.67  4626.7  545.62    4641   544.7  4711.3  541.17
  4775.1  537.14    4859  536.09  4859.3  535.59  4862.8  535.59    4863  536.09
  4942.5  536.53  4953.5   536.5    4960  537.12  4974.3  536.94  4992.5  537.53
  5027.4  537.78  5037.9  536.94    5059  537.84  5080.1  537.75  5106.1  538.78
  5132.8  540.34  5143.3  541.85  5164.4  542.32  5185.5  544.22    5196  544.34
  5227.7   546.2  5238.2  547.29  5259.3  547.39  5280.4  548.64    5312  549.49
#Mann= 5 ,-1 , 0
  4605.2     .05       0    4859     .07       0    4863     .05       0
  4942.5     .12       0  5106.1     .05       0
Bank Sta=4859,4863
XS Rating Curve= 0 ,0
Exp/Cntr=0.3,0.1

Type RM Length L Ch R = 1 ,51388   ,265,265,265
BEGIN DESCRIPTION:
Wet Lacy Fork 3529
END DESCRIPTION:
XS GIS Cut Line= 3
      2769621.18      6877036.53      2769328.72      6877171.31
      2768930.92      6877241.11
#Sta/Elev= 30
  4675.9     548  4721.3  544.52  4790.2  540.66  4818.6  539.37  4824.7  538.23
  4841.6  537.12  4864.5  536.24  4968.8  535.54  4982.8  535.37  4983.1  534.87
  4986.6  534.87  4986.8  535.37  5020.5  536.37  5061.6  536.47  5079.9  535.92
  5084.9  536.19  5112.4  536.02  5132.7  536.38  5142.6  536.89    5153  537.44
  5163.1  538.64  5198.7  540.06  5213.9  542.02  5244.4  543.25  5264.7  545.01
  5295.1  545.43  5317.4  546.18  5345.9  548.27    5356  548.13  5401.8  549.04
#Mann= 5 ,-1 , 0
  4675.9     .05       0  4968.8     .12       0  4982.8     .07       0
  4986.8     .12       0  5142.6     .05       0
Bank Sta=4982.8,4986.8
XS Rating Curve= 0 ,0
Exp/Cntr=0.3,0.1

Type RM Length L Ch R = 1 ,51123   ,289,289,289
BEGIN DESCRIPTION:
Wet Lacy Fork 3530
END DESCRIPTION:
XS GIS Cut Line= 3
      2769659.24      6876860.84       2769227.4      6876936.74
       2768911.4       6877133.3
#Sta/Elev= 30
  4560.3  550.33  4589.5  548.78  4624.5  547.92  4648.9  546.65  4675.3  544.24
    4726  541.28  4797.1  536.07    4858  534.28  4893.7  534.34  4927.1  533.67
  4927.4  533.17  4930.9  533.17  4931.1  533.67  5017.2  534.03  5032.5  534.98
  5053.8  534.92  5059.7  535.34    5075  534.92  5097.3  535.74    5127  537.62
  5132.9   538.5  5141.7  538.54  5169.5  540.34  5190.7  543.04  5206.1  543.01
  5227.3  544.26  5242.7  545.73  5306.6  546.99    5343  548.65  5370.9  548.78
#Mann= 5 ,-1 , 0
  4560.3     .08       0  4893.7     .12       0  4927.1     .04       0
  4931.1     .12       0  5097.3     .08       0
Bank Sta=4927.1,4931.1
XS Rating Curve= 0 ,0
Exp/Cntr=0.3,0.1

Type RM Length L Ch R = 1 ,50834   ,190,190,190
BEGIN DESCRIPTION:
Wet Lacy Fork 3528
END DESCRIPTION:
XS GIS Cut Line= 3
      2769537.97      6876544.36      2769119.12      6876686.41
       2768865.8      6876900.11
#Sta/Elev= 30
  4563.6  540.48  4658.8  538.66  4690.2  537.56  4726.9  537.37  4758.3  535.92
  4789.7  535.88  4808.6  535.31  4821.1  535.78  4878.6  534.53  4965.7  533.84
  4972.8  533.52  4986.1  529.95  4986.3  529.45  4989.8  529.45  4990.1  529.95
  4998.6  530.72  5004.2  533.74  5018.6  533.55  5032.9  534.08  5066.7   533.7
  5096.7  534.93  5103.2  535.65  5160.4  537.11  5174.7  538.96  5181.2  538.05
  5195.5  539.74  5264.6  543.47  5287.8  544.22  5295.6  544.91  5337.3  545.31
#Mann= 6 ,-1 , 0
  4563.6     .08       0  4965.7     .08       0  4986.1     .04       0
  4990.1     .09       0  5066.7     .12       0  5264.6      .1       0
Bank Sta=4986.1,4990.1
XS Rating Curve= 0 ,0
Exp/Cntr=0.3,0.1

Type RM Length L Ch R = 1 ,50644   ,186,186,186
BEGIN DESCRIPTION:
Wet Lacy Fork 3525
END DESCRIPTION:
XS GIS Cut Line= 3
       2769388.3      6876306.85      2769055.94      6876511.67
      2768800.97      6876658.84
#Sta/Elev= 30
  4590.5  541.24  4719.4  534.39  4814.1  532.33  4835.3  529.63  4850.7  529.49
  4856.6  531.64  4862.7  531.89    4872  530.74  4877.9  532.05  4893.3  529.52
  4908.7  531.96  4951.3  531.56  4957.3  526.73  4964.7  526.18  4964.9  525.68
  4968.7  526.18  4980.8  526.97  4993.9  527.35  4999.1  528.77  5003.9  530.09
  5009.6  529.65  5025.4  531.36  5031.2  528.63    5047  531.56  5061.7  531.09
  5068.5  532.61  5096.6  534.16  5133.2  538.22  5187.2  542.18  5275.3  546.84
#Mann= 8 ,-1 , 0
  4590.5     .05       0  4862.7      .1       0  4964.7     .07       0
  4968.7      .1       0  4980.8     .05       0  4999.1      .1       0
  5096.6     .12       0  5187.2     .08       0
Bank Sta=4964.7,4968.7
XS Rating Curve= 0 ,0
Exp/Cntr=0.3,0.1

Type RM Length L Ch R = 1 ,50458   ,78,78,78
BEGIN DESCRIPTION:
Wet Lacy Fork 3524
END DESCRIPTION:
XS GIS Cut Line= 3
      2769350.06       6876189.9      2769068.63      6876354.39
      2768711.71      6876496.12
#Sta/Elev= 30
  4682.4  543.18  4768.1  537.39  4826.1  534.65  4848.3  533.04  4891.2  531.77
    4897  532.63  4902.5  532.19  4918.8  531.88  4928.4  529.73  4934.2  530.88
  4941.9  531.38  4953.6  530.66  4965.1  528.97  4971.4  526.84  4985.1   526.1
  4985.4   525.6  4988.9   525.6  4989.1   526.1  5014.7  526.28    5018  527.16
  5032.7  531.03  5044.4  531.91  5117.3  531.72  5185.2   533.2  5225.3  535.26
  5230.6  534.81  5279.3  538.17  5284.6  537.93  5323.2  542.27  5392.4  547.14
#Mann= 7 ,-1 , 0
  4682.4     .05       0  4902.5      .1       0  4953.6     .05       0
  4985.1     .05       0  4989.1     .05       0    5018      .1       0
  5185.2     .05       0
Bank Sta=4985.1,4989.1
XS Rating Curve= 0 ,0
Exp/Cntr=0.3,0.1

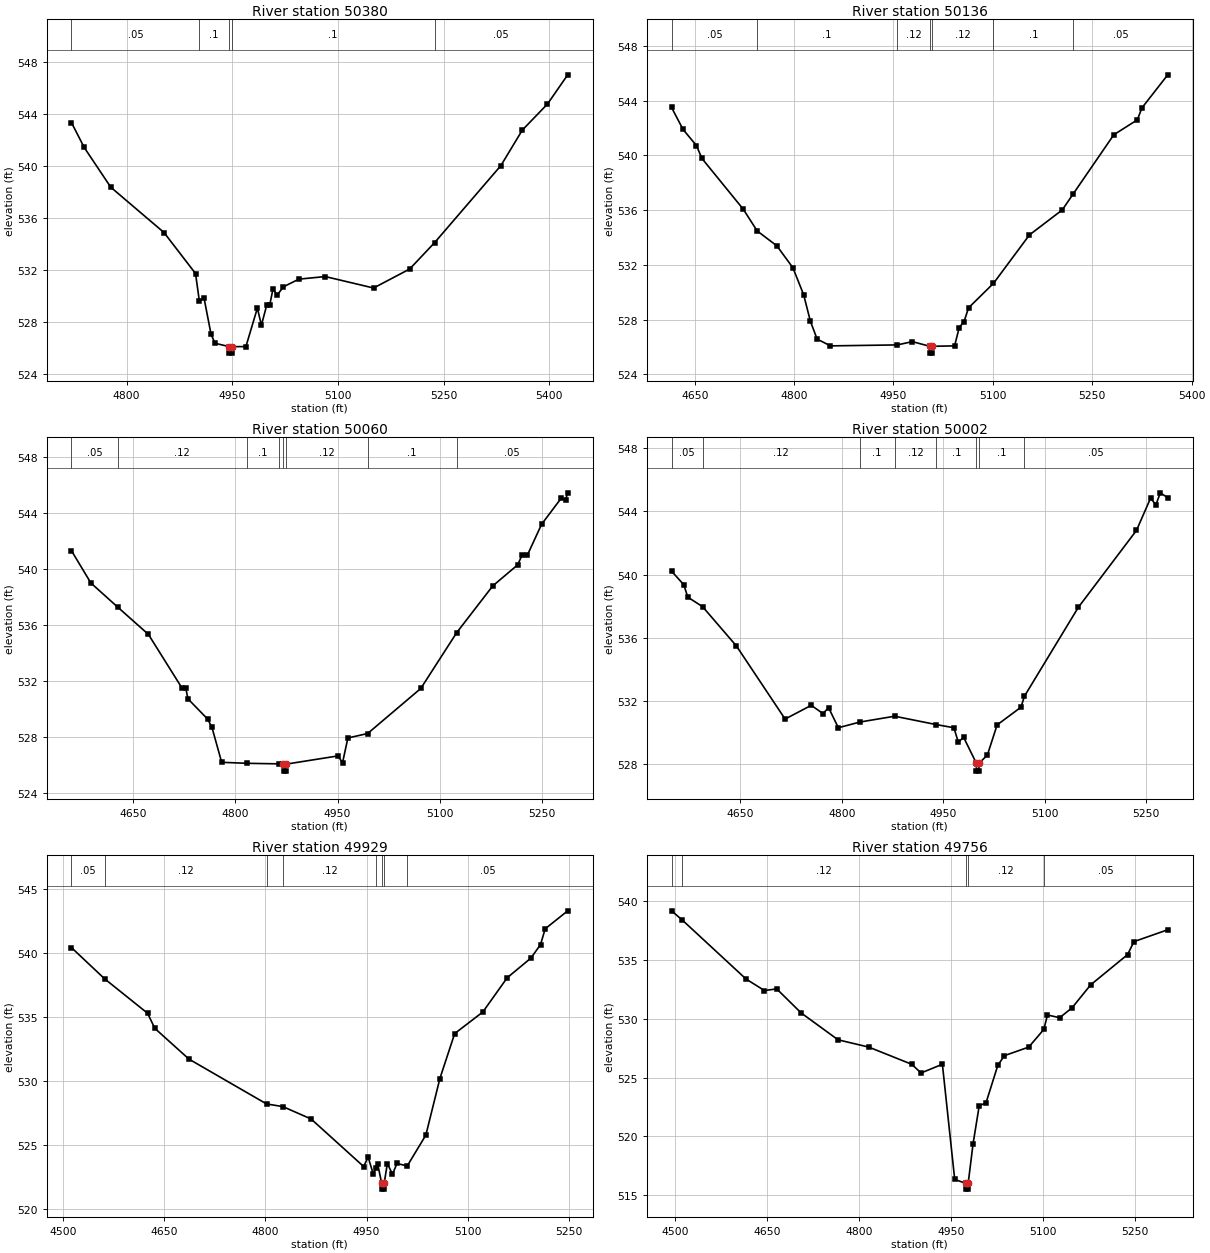
Type RM Length L Ch R = 1 ,50380   ,244,244,244
BEGIN DESCRIPTION:
Wet Lacy Fork 3526
END DESCRIPTION:
XS GIS Cut Line= 3
      2769321.95       6876140.7      2769073.58      6876273.11
      2768689.98      6876451.94
#Sta/Elev= 30
  4721.6  543.31  4739.7   541.4  4777.4  538.35    4853  534.87  4897.8  531.72
  4903.1  529.64  4909.7  529.88  4919.8  527.06  4925.4  526.37  4945.4  526.11
  4945.6  525.61  4949.1  525.61  4949.4  526.11  4969.3  526.11  4985.6  529.07
  4991.3  527.75  4998.9   529.3  5003.1   529.3  5007.9  530.57  5013.4  530.04
  5022.5   530.7  5044.5  531.29    5082  531.49  5150.6  530.61  5201.9  532.07
  5237.2  534.09  5331.4  540.01  5361.9  542.74  5397.6  544.74  5426.3  546.98
#Mann= 5 ,-1 , 0
  4721.6     .05       0  4903.1      .1       0  4945.4     .07       0
  4949.4      .1       0  5237.2     .05       0
Bank Sta=4945.4,4949.4
XS Rating Curve= 0 ,0
Exp/Cntr=0.3,0.1

Type RM Length L Ch R = 1 ,50136   ,76,76,76
BEGIN DESCRIPTION:
Wet Lacy Fork 3527
END DESCRIPTION:
XS GIS Cut Line= 3
      2769293.18      6876058.59      2768989.68      6876104.78
      2768681.01      6876421.02
#Sta/Elev= 30
    4615  543.51  4632.4   541.9  4652.6  540.72  4660.9  539.78  4723.4  536.06
  4744.3  534.48    4774  533.39  4798.2  531.79  4814.4  529.82  4824.6  527.88
  4834.7  526.58  4854.9  526.08  4955.7  526.15  4978.5  526.39  5004.8  526.05
    5005  525.55  5008.5  525.55  5008.8  526.05  5042.2  526.08  5049.2  527.42
  5056.4  527.85  5063.3  528.86  5100.9  530.65  5155.2  534.19  5204.8  536.02
  5221.1  537.18  5282.5  541.51    5318   542.6  5324.9  543.47  5363.9  545.89
#Mann= 7 ,-1 , 0
    4615     .05       0  4744.3      .1       0  4955.7     .12       0
  5004.8     .07       0  5008.8     .12       0  5100.9      .1       0
  5221.1     .05       0
Bank Sta=5004.8,5008.8
XS Rating Curve= 0 ,0
Exp/Cntr=0.3,0.1

Type RM Length L Ch R = 1 ,50060   ,58,58,58
BEGIN DESCRIPTION:
Wet Lacy Fork 3523
END DESCRIPTION:
XS GIS Cut Line= 3
      2769233.31      6875925.51      2769075.16      6875971.81
      2768640.12       6876329.2
#Sta/Elev= 30
  4559.8  541.31  4588.3     539  4627.3  537.29  4672.6  535.33  4721.5  531.52
  4727.3  531.52  4730.6  530.72  4759.3  529.28  4765.7   528.7  4780.1  526.18
  4816.9  526.11  4863.6  526.07  4870.6  526.05  4870.9  525.55  4874.4  525.55
  4874.6  526.05  4950.9  526.64  4957.3  526.14  4965.2  527.92  4994.2  528.24
  5072.1  531.46  5124.9  535.46  5177.6  538.79  5214.2   540.3  5220.6  540.99
  5228.2  540.97  5249.3   543.2    5278  545.06  5284.5  544.96  5287.6  545.45
#Mann= 8 ,-1 , 0
  4559.8     .05       0  4627.3     .12       0  4816.9      .1       0
  4863.6     .12       0  4870.6     .07       0  4874.6     .12       0
  4994.2      .1       0  5124.9     .05       0
Bank Sta=4870.6,4874.6
XS Rating Curve= 0 ,0
Exp/Cntr=0.3,0.1

Type RM Length L Ch R = 1 ,50002   ,73,73,73
BEGIN DESCRIPTION:
Wet Lacy Fork 3521
END DESCRIPTION:
XS GIS Cut Line= 3
      2769213.42      6875899.04      2768996.13      6875962.93
      2768603.72      6876283.99
#Sta/Elev= 30
  4548.4  540.22  4566.6  539.35  4572.4  538.57  4594.4  537.96  4644.4  535.47
  4716.3  530.84  4754.9  531.71  4772.3  531.19  4780.6  531.56    4795  530.29
  4826.7  530.65  4878.2  531.02  4939.7  530.49  4965.8  530.29  4972.3  529.38
  4980.2  529.68    4999  528.04  4999.2  527.54  5002.7  527.54    5003  528.04
  5015.3  528.56  5029.7  530.47  5064.9  531.59  5070.1  532.29  5149.7  537.92
  5235.7   542.8  5256.5  544.84  5264.4  544.42  5270.9  545.18  5281.9  544.87
#Mann= 8 ,-1 , 0
  4548.4     .05       0  4594.4     .12       0  4826.7      .1       0
  4878.2     .12       0  4939.7      .1       0    4999     .07       0
    5003      .1       0  5070.1     .05       0
Bank Sta=4999,5003
XS Rating Curve= 0 ,0
Exp/Cntr=0.3,0.1

Type RM Length L Ch R = 1 ,49929   ,173,173,173
BEGIN DESCRIPTION:
Wet Lacy Fork 3522
END DESCRIPTION:
XS GIS Cut Line= 3
      2769218.08      6875888.76      2768908.77      6875934.79
      2768590.87      6876212.61
#Sta/Elev= 30
    4513  540.43    4562  537.99  4625.7  535.29  4636.4  534.11    4687   531.7
  4801.9  528.19  4826.1  527.98  4867.9  527.01  4945.7  523.29  4952.3  524.03
  4959.9  522.71  4963.9  523.16  4966.6  523.46  4972.2  522.02  4972.4  521.52
  4975.9  521.52  4976.2  522.02  4980.8  523.52  4988.4  522.69  4995.1  523.53
  5010.2  523.33  5037.8  525.75  5058.6  530.18  5080.5   533.7  5122.2  535.39
  5158.3  538.07  5193.4  539.61  5207.7  540.67  5214.5   541.9  5247.9  543.31
#Mann= 8 ,-1 , 0
    4513     .05       0    4562     .12       0  4801.9      .1       0
  4826.1     .12       0  4963.9      .1       0  4972.2     .07       0
  4976.2      .1       0  5010.2     .05       0
Bank Sta=4972.2,4976.2
XS Rating Curve= 0 ,0
Exp/Cntr=0.3,0.1

Type RM Length L Ch R = 1 ,49756   ,71,71,71
BEGIN DESCRIPTION:
Wet Lacy Fork 3519
END DESCRIPTION:
XS GIS Cut Line= 3
       2769187.4       6875882.8      2768678.93      6875911.79
       2768381.4      6875954.67
#Sta/Elev= 30
  4493.8  539.18  4511.3   538.4  4615.4  533.38  4645.5   532.4  4665.5  532.54
  4705.5  530.49  4765.6  528.21  4815.7  527.59  4885.8  526.13  4901.1  525.39
  4935.9  526.13    4956  516.33    4974  516.01  4974.2  515.51  4977.7  515.51
    4978  516.01    4986  519.38    4996   522.6  5007.1  522.85  5026.3  526.03
    5037  526.86  5076.8  527.59  5101.4  529.09  5107.4  530.32  5127.3  530.09
  5147.5  530.93  5177.8  532.88  5238.2  535.46  5248.5  536.56  5303.7  537.57
#Mann= 5 ,-1 , 0
  4493.8     .05       0  4511.3     .12       0    4974     .07       0
    4978     .12       0  5101.4     .05       0
Bank Sta=4974,4978
XS Rating Curve= 0 ,0
Exp/Cntr=0.3,0.1

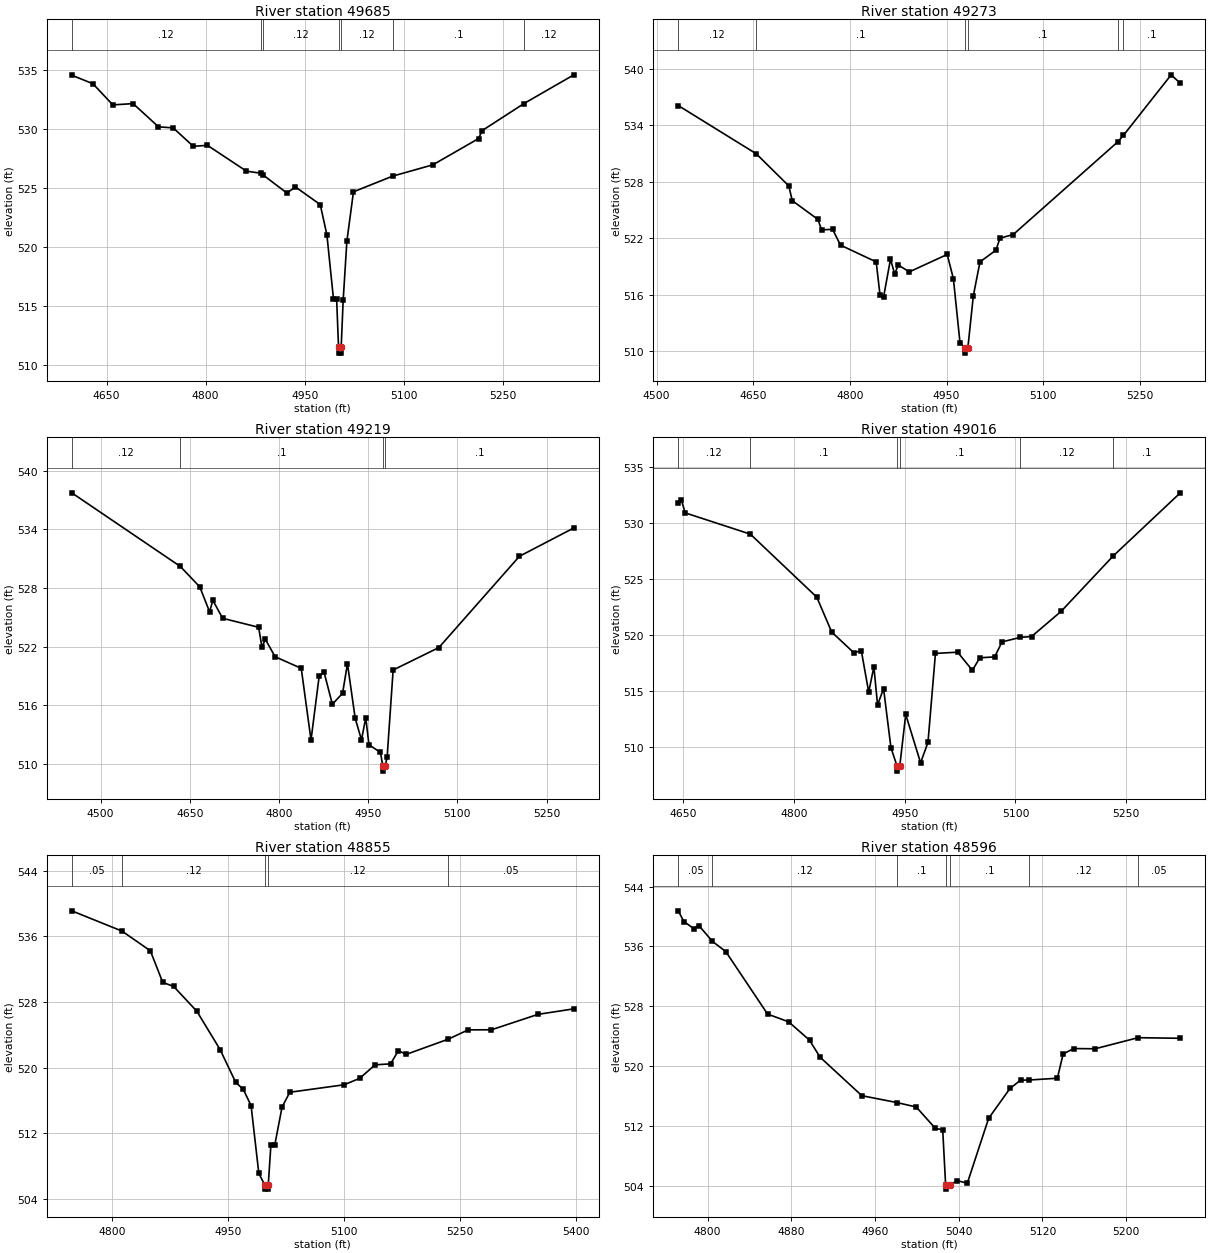
Type RM Length L Ch R = 1 ,49685   ,412,412,412
BEGIN DESCRIPTION:
Wet Lacy Fork 3520
END DESCRIPTION:
XS GIS Cut Line= 3
      2769057.76      6875786.07      2768661.49      6875845.55
      2768303.01      6875862.67
#Sta/Elev= 30
  4597.4   534.6  4629.5  533.87  4659.5  532.08  4690.2  532.19  4728.6  530.22
  4750.9  530.13  4781.2  528.57  4802.7  528.65  4861.7  526.46  4883.1  526.29
  4887.3  526.12  4922.8  524.61  4935.8  525.12  4973.3  523.63  4983.4  521.06
  4993.3  515.65  4998.1  515.65    5001  511.53  5001.3  511.03  5004.8  511.03
    5005  511.53    5008   515.5  5013.6  520.52  5023.6  524.71  5082.9  526.04
  5143.8     527    5213  529.23    5218  529.89  5281.4  532.19    5357  534.63
#Mann= 7 ,-1 , 0
  4597.4     .12       0  4883.1      .1       0  4887.3     .12       0
    5001     .07       0    5005     .12       0  5082.9      .1       0
  5281.4     .12       0
Bank Sta=5001,5005
XS Rating Curve= 0 ,0
Exp/Cntr=0.3,0.1

Type RM Length L Ch R = 1 ,49273   ,54,54,54
BEGIN DESCRIPTION:
Wet Lacy Fork 3512
END DESCRIPTION:
XS GIS Cut Line= 3
      2768713.41      6875371.01      2768355.12      6875541.84
      2768257.93      6875911.75
#Sta/Elev= 30
  4533.5  536.12  4654.7  530.99    4705  527.59  4710.6  526.01  4750.4  524.02
    4756  522.91  4773.1  522.97  4785.4  521.29  4840.8  519.51  4846.8  515.95
  4852.3  515.79    4863   519.8  4869.5  518.22    4875  519.18  4892.2  518.45
    4951   520.3  4960.6  517.74  4970.9  510.92    4979  510.32  4979.3  509.82
    4983  510.32  4991.6  515.91  5001.9  519.51  5026.6  520.75    5033  522.03
  5053.6  522.42  5215.5  532.24  5224.7  532.96  5298.7  539.38  5312.9  538.48
#Mann= 6 ,-1 , 0
  4533.5     .12       0  4654.7      .1       0    4979     .07       0
    4983      .1       0  5215.5     .12       0  5224.7      .1       0
Bank Sta=4979,4983
XS Rating Curve= 0 ,0
Exp/Cntr=0.3,0.1

Type RM Length L Ch R = 1 ,49219   ,203,203,203
BEGIN DESCRIPTION:
Wet Lacy Fork 3513
END DESCRIPTION:
XS GIS Cut Line= 3
      2768714.16      6875267.11       2768333.1       6875467.7
       2768193.6      6875857.14
#Sta/Elev= 30
  4451.5  537.74  4634.1  530.21  4666.8  528.12  4683.2  525.58  4688.8  526.74
  4705.2  524.91  4765.7  523.99  4771.3  521.97  4777.1  522.75  4793.4  520.98
  4837.4  519.79  4853.8  512.46  4867.6  519.02  4875.8  519.39  4889.7  516.12
  4906.9  517.24  4915.1  520.27  4928.1  514.68  4938.7  512.47  4945.9  514.75
  4951.2  511.98  4970.6  511.19  4974.6  509.78  4974.9  509.28  4978.6  509.78
  4981.9  510.77  4991.9  519.62  5068.9  521.92  5204.3  531.25  5295.8  534.15
#Mann= 4 ,-1 , 0
  4451.5     .12       0  4634.1      .1       0  4974.6     .07       0
  4978.6      .1       0
Bank Sta=4974.6,4978.6
XS Rating Curve= 0 ,0
Exp/Cntr=0.3,0.1

Type RM Length L Ch R = 1 ,49016   ,161,161,161
BEGIN DESCRIPTION:
Wet Lacy Fork 3511
END DESCRIPTION:
XS GIS Cut Line= 3
      2768160.47      6875104.06      2768188.27      6875464.12
      2768176.75      6875782.08
#Sta/Elev= 30
  4643.7  531.78  4648.1  531.99  4653.1  530.88  4741.3  528.98  4831.2  523.35
  4851.3  520.24  4881.3  518.39  4891.4  518.58  4901.4  514.87  4908.4  517.14
  4913.4  513.73  4921.5  515.19  4931.5  509.91  4939.5  508.32  4939.8  507.82
  4943.5  508.32  4951.5  512.88  4971.6  508.56  4981.6  510.39  4991.7  518.33
  5021.7  518.44  5041.7  516.82  5051.7  517.94  5071.8  518.02  5081.8  519.36
  5106.4  519.76  5121.8  519.84  5161.8  522.09    5232  527.02    5323  532.67
#Mann= 6 ,-1 , 0
  4643.7     .12       0  4741.3      .1       0  4939.5     .07       0
  4943.5      .1       0  5106.4     .12       0    5232      .1       0
Bank Sta=4939.5,4943.5
XS Rating Curve= 0 ,0
Exp/Cntr=0.3,0.1

Type RM Length L Ch R = 1 ,48855   ,259,259,259
BEGIN DESCRIPTION:
Wet Lacy Fork 3510
END DESCRIPTION:
XS GIS Cut Line= 3
      2768038.03       6875159.5       2768044.5      6875417.27
      2768022.07      6875807.27
#Sta/Elev= 30
  4748.4  539.09  4813.3  536.62  4849.9  534.22  4865.9  530.37  4879.9  529.89
    4910  526.85    4940  522.19    4960  518.22    4970  517.33    4980  515.36
    4990  507.11  4997.7  505.69  4998.2  505.19  5001.8  505.19  5002.2  505.69
  5005.6  510.57  5010.6  510.57    5020  515.18    5030  516.99  5100.1   517.9
  5120.2  518.68  5140.2  520.33  5160.2  520.45  5170.3  522.06  5180.3   521.6
  5234.8  523.46  5260.4  524.59  5290.5   524.6  5350.6  526.48  5396.9  527.15
#Mann= 5 ,-1 , 0
  4748.4     .05       0  4813.3     .12       0  4997.7     .07       0
  5002.2     .12       0  5234.8     .05       0
Bank Sta=4997.7,5002.2
XS Rating Curve= 0 ,0
Exp/Cntr=0.3,0.1

Type RM Length L Ch R = 1 ,48596   ,340,340,340
BEGIN DESCRIPTION:
Wet Lacy Fork 3509
END DESCRIPTION:
XS GIS Cut Line= 3
      2767780.55      6875185.58      2767785.95      6875413.05
      2767833.02      6875660.99
#Sta/Elev= 30
  4771.9  540.76  4777.3  539.33  4786.6   538.4  4791.6   538.8  4804.6  536.68
  4817.3  535.33  4857.3  526.98  4877.4  525.95  4897.4   523.5  4907.4  521.24
  4947.4  516.09    4981  515.17  4999.4  514.58  5017.7  511.72  5024.7  511.54
  5027.5  504.12    5028  503.62  5032.1  504.12  5038.1  504.77  5048.2  504.41
  5068.6  513.07    5089  517.05  5099.1  518.16  5107.3  518.18  5134.3  518.42
  5139.8  521.66    5150  522.38  5170.4  522.35  5211.4  523.83  5251.8  523.75
#Mann= 7 ,-1 , 0
  4771.9     .05       0  4804.6     .12       0    4981      .1       0
  5027.5     .07       0  5032.1      .1       0  5107.3     .12       0
  5211.4     .05       0
Bank Sta=5027.5,5032.1
XS Rating Curve= 0 ,0
Exp/Cntr=0.3,0.1

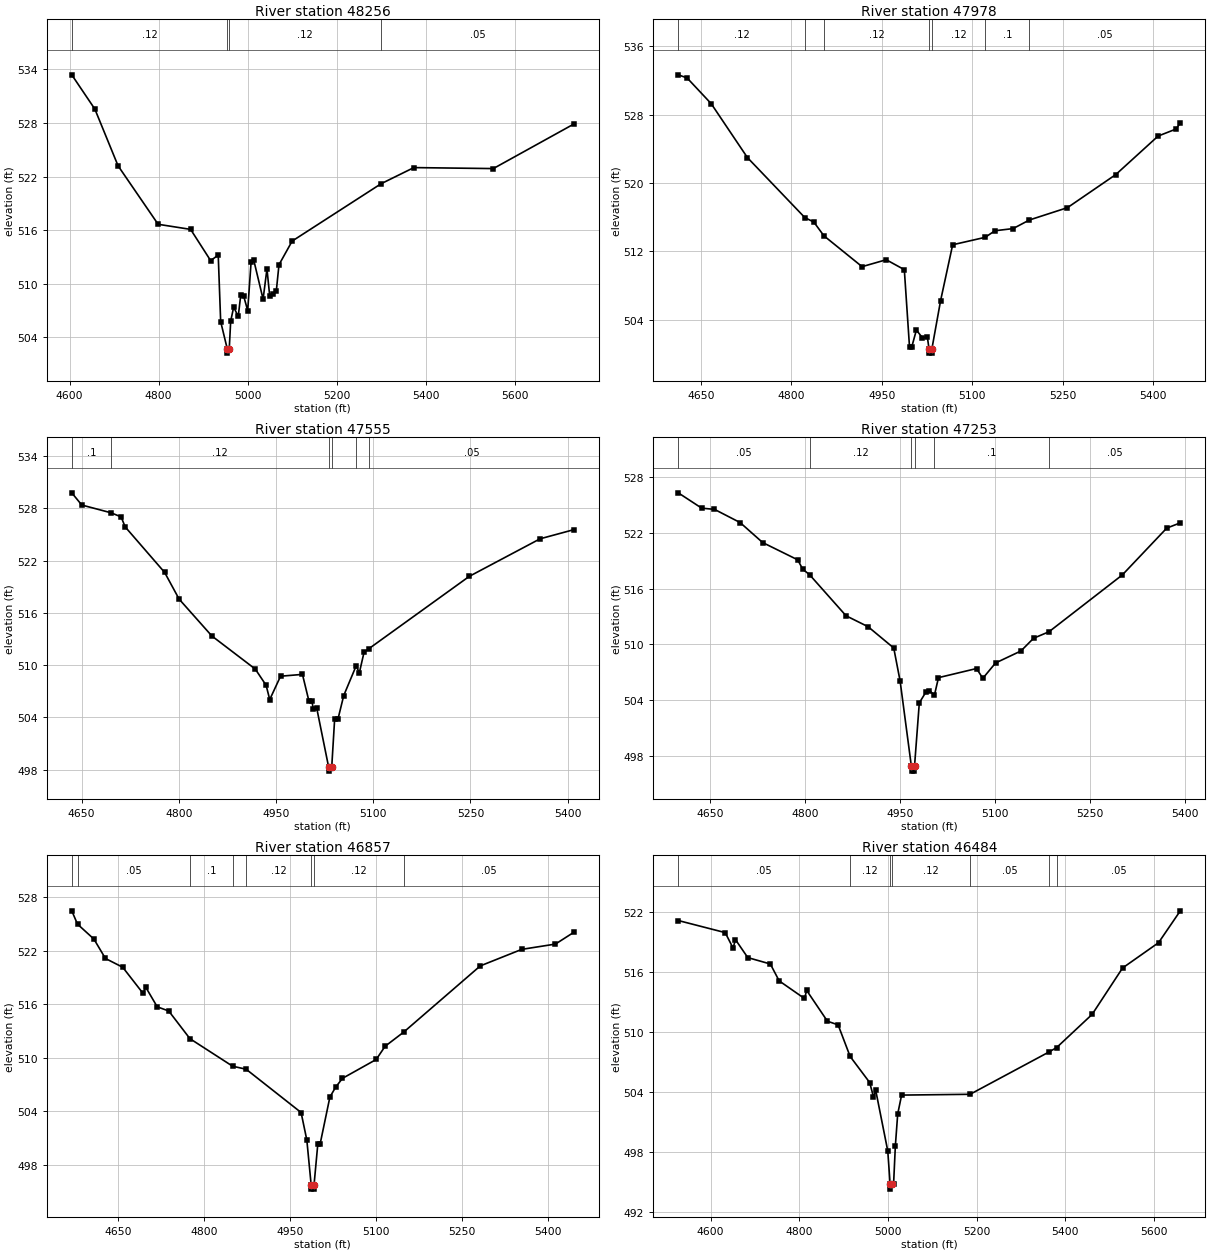
Type RM Length L Ch R = 1 ,48256   ,278,278,278
BEGIN DESCRIPTION:
Wet Lacy Fork 3508
END DESCRIPTION:
XS GIS Cut Line= 3
      2767304.36      6875154.39      2767477.27      6875507.18
      2768077.68      6875931.15
#Sta/Elev= 30
    4605   533.4  4656.9  529.56    4709  523.21    4799  516.66    4872  516.09
    4917  512.59    4934  513.21  4939.5  505.76  4954.2  502.73  4954.6  502.23
  4958.8  502.73    4962  505.81  4968.7  507.38    4979  506.34  4984.5  508.71
    4991  508.65  5000.2     507  5007.8  512.39  5013.9  512.63  5034.8  508.27
  5043.5  511.67  5049.6  508.66  5057.5  508.89  5064.4  509.15  5070.5  512.13
  5100.1  514.78  5299.8   521.2  5373.5  523.01    5552   522.9  5732.9  527.89
#Mann= 4 ,-1 , 0
    4605     .12       0  4954.2     .07       0  4958.8     .12       0
  5299.8     .05       0
Bank Sta=4954.2,4958.8
XS Rating Curve= 0 ,0
Exp/Cntr=0.3,0.1

Type RM Length L Ch R = 1 ,47978   ,423,423,423
BEGIN DESCRIPTION:
Wet Lacy Fork 3507
END DESCRIPTION:
XS GIS Cut Line= 3
      2767239.93      6875126.37      2767232.58      6875513.26
      2767208.46      6875957.75
#Sta/Elev= 30
  4612.7  532.64  4627.3  532.28  4667.3  529.27  4727.4  522.96  4822.6  515.94
  4837.4  515.43  4854.1  513.82  4917.4  510.21  4957.4  511.02  4987.4  509.86
    4996  500.82  4999.7  500.82  5007.4   502.8  5017.4  501.89  5025.6  501.98
  5028.3   500.6  5028.8   500.1  5032.5   500.1  5033.1   500.6  5047.5  506.24
  5067.5  512.77  5121.4  513.64  5137.6  514.41  5167.6  514.66  5194.8  515.67
  5257.8  517.11  5337.9  520.98    5408  525.48    5438  526.31  5444.8  527.05
#Mann= 7 ,-1 , 0
  4612.7     .12       0  4822.6      .1       0  4854.1     .12       0
  5028.3     .07       0  5033.1     .12       0  5121.4      .1       0
  5194.8     .05       0
Bank Sta=5028.3,5033.1
XS Rating Curve= 0 ,0
Exp/Cntr=0.3,0.1

Type RM Length L Ch R = 1 ,47555   ,302,302,302
BEGIN DESCRIPTION:
Wet Lacy Fork 3506
END DESCRIPTION:
XS GIS Cut Line= 3
      2767078.34      6875073.04      2766911.68      6875404.04
      2766794.27      6875790.82
#Sta/Elev= 30
  4634.8  529.79  4650.2  528.39  4695.3   527.5  4710.9  527.03  4717.2  525.88
  4778.1  520.65  4800.5  517.58    4851  513.35    4918  509.55  4934.7  507.69
  4940.3  506.05    4957  508.73  4990.8  508.94  5000.9  505.84  5005.4  505.84
  5007.6  504.96  5012.8  505.07  5031.1  498.33  5031.7  497.83    5036  498.33
  5040.5  503.86  5045.7  503.84  5054.5  506.51  5073.6  509.91  5078.6  509.13
  5085.8  511.47  5093.3  511.89  5248.3   520.2  5357.5  524.51  5409.6  525.56
#Mann= 6 ,-1 , 0
  4634.8      .1       0  4695.3     .12       0  5031.1     .07       0
    5036     .12       0  5073.6      .1       0  5093.3     .05       0
Bank Sta=5031.1,5036
XS Rating Curve= 0 ,0
Exp/Cntr=0.3,0.1

Type RM Length L Ch R = 1 ,47253   ,396,396,396
BEGIN DESCRIPTION:
Wet Lacy Fork 3490
END DESCRIPTION:
XS GIS Cut Line= 3
      2766721.25      6874864.37      2766659.86        6875265.
      2766636.44      6875652.48
#Sta/Elev= 30
  4599.3  526.31  4636.4  524.66  4656.6  524.53  4697.1  523.11  4732.7  520.96
  4788.1   519.1  4796.1  518.09  4807.1  517.48  4864.5  513.08  4899.4   511.9
  4939.9  509.61    4950  506.04  4967.8  496.86  4968.4  496.36  4972.1  496.36
  4972.7  496.86  4980.3  503.71  4990.4  504.83  4996.3  505.03  5004.2  504.53
  5010.6  506.42  5070.7   507.4  5080.7  506.35  5100.8     508  5140.9  509.29
  5160.9  510.66  5185.3  511.36  5301.1  517.47  5371.3  522.51  5392.8  523.08
#Mann= 6 ,-1 , 0
  4599.3     .05       0  4807.1     .12       0  4967.8     .07       0
  4972.7     .12       0  5004.2      .1       0  5185.3     .05       0
Bank Sta=4967.8,4972.7
XS Rating Curve= 0 ,0
Exp/Cntr=0.3,0.1

Type RM Length L Ch R = 1 ,46857   ,373,373,373
BEGIN DESCRIPTION:
Wet Lacy Fork 3489
END DESCRIPTION:
XS GIS Cut Line= 3
      2766340.88       6874782.5      2766306.47       6875214.2
      2766363.02       6875652.8
#Sta/Elev= 30
  4569.4  526.44  4579.4  524.95    4608  523.28  4628.1  521.11  4658.2  520.13
  4693.5  517.22  4698.5  517.88  4718.4   515.7  4738.4  515.24  4775.4  512.14
  4849.8  509.06  4873.4  508.72  4969.2  503.88  4979.2   500.8  4986.7  495.81
  4987.3  495.31  4991.1  495.31  4991.8  495.81  4998.4   500.4  5002.5   500.4
  5019.4  505.61  5029.5  506.72  5041.3   507.7  5100.1  509.81  5115.7  511.29
  5148.2  512.88  5281.6  520.28  5353.9  522.13  5412.6  522.72  5444.7  524.04
#Mann= 8 ,-1 , 0
  4569.4     .12       0  4579.4     .05       0  4775.4      .1       0
  4849.8     .05       0  4873.4     .12       0  4986.7     .07       0
  4991.8     .12       0  5148.2     .05       0
Bank Sta=4986.7,4991.8
XS Rating Curve= 0 ,0
Exp/Cntr=0.3,0.1

Type RM Length L Ch R = 1 ,46484   ,470,470,470
BEGIN DESCRIPTION:
Wet Lacy Fork 3488
END DESCRIPTION:
XS GIS Cut Line= 3
      2765907.11      6874697.03      2765998.44      6875171.55
      2766202.63      6875787.57
#Sta/Elev= 30
  4527.2  521.12  4633.1  519.91    4651  518.35  4656.1  519.22    4684  517.41
  4734.9  516.77  4754.8  515.08  4811.8  513.32  4816.9  514.12  4863.7  511.04
  4887.7  510.68  4914.8  507.52  4958.9  504.91  4967.5  503.47  4972.6  504.11
  4999.7  498.06    5005  494.74  5005.7  494.24  5010.1  494.74  5012.8  494.74
  5016.8  498.56  5022.1  501.76  5030.9  503.65  5185.3  503.73  5363.5  507.97
  5380.6  508.41  5460.6  511.73  5529.2  516.37  5610.3   518.9  5659.4  522.09
#Mann= 7 ,-1 , 0
  4527.2     .05       0  4914.8     .12       0    5005     .07       0
  5010.1     .12       0  5185.3     .05       0  5363.5     .12       0
  5380.6     .05       0
Bank Sta=5005,5010.1
XS Rating Curve= 0 ,0
Exp/Cntr=0.3,0.1

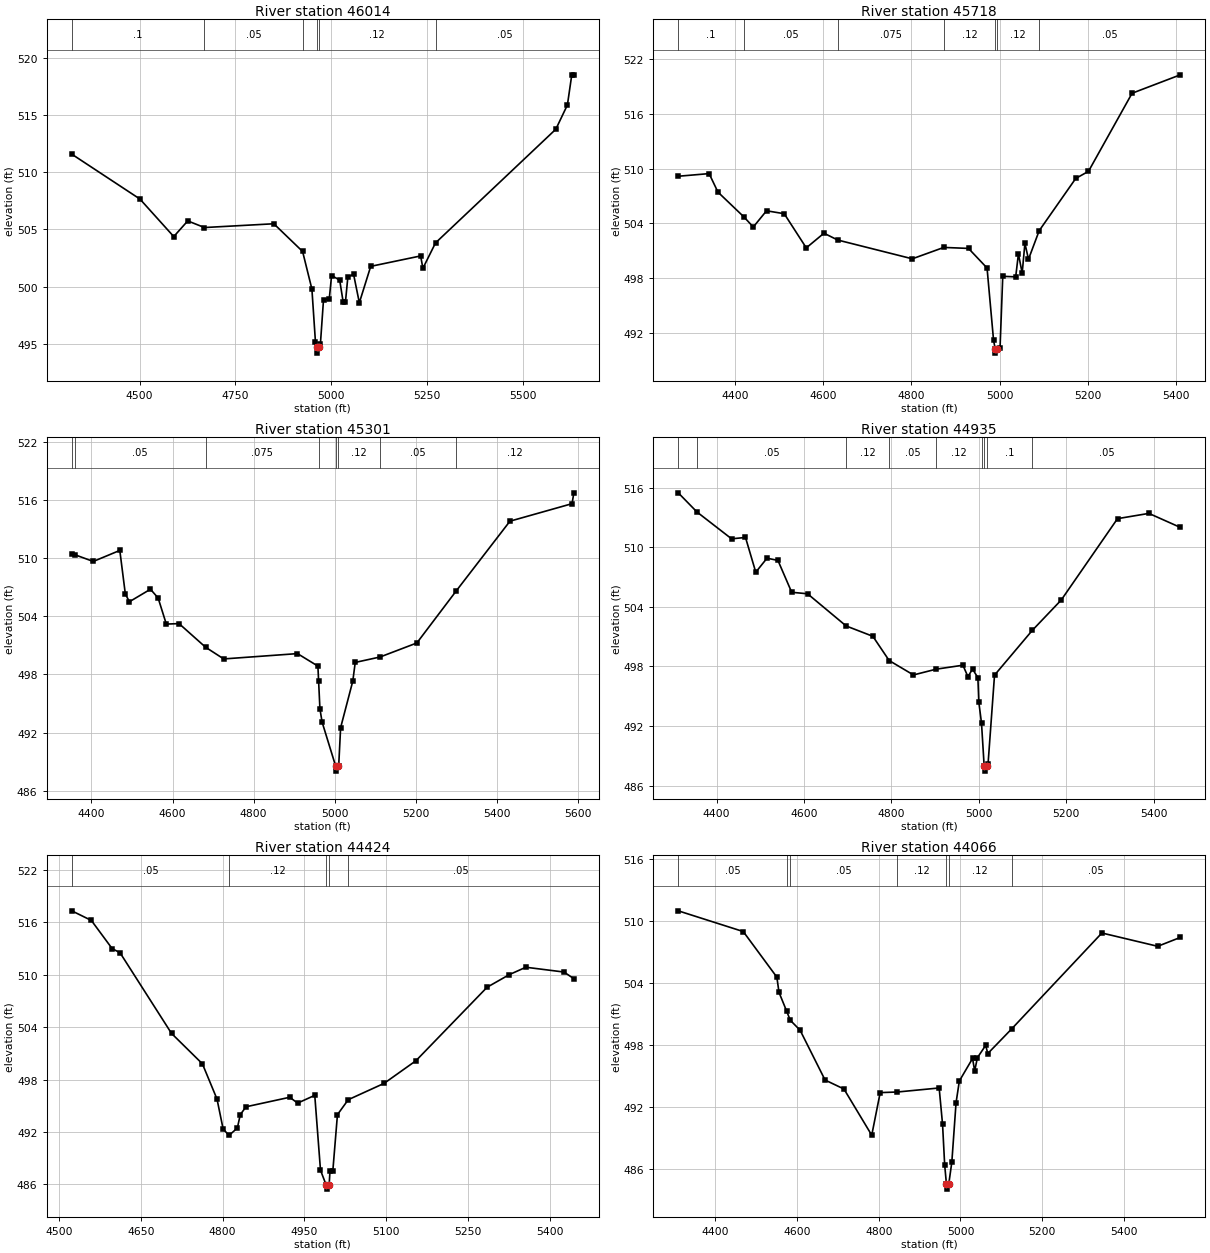
Type RM Length L Ch R = 1 ,46014   ,296,296,296
BEGIN DESCRIPTION:
Wet Lacy Fork 3485
END DESCRIPTION:
XS GIS Cut Line= 3
      2765373.17      6874817.15      2765495.23      6875170.85
      2766006.91      6875955.01
#Sta/Elev= 30
  4323.1  511.58    4501  507.66  4589.3  504.38  4625.8  505.75  4669.4  505.17
  4850.5   505.5  4925.6  503.08  4949.9  499.79  4959.1   495.2  4962.5   494.7
  4963.2   494.2  4967.7   494.7  4972.1  495.01  4980.2  498.87  4995.3  498.97
  5001.3  500.98  5022.4  500.58  5031.5  498.66  5037.5  498.69  5043.7  500.84
  5058.6   501.1  5073.7   498.6  5103.4  501.78  5233.7  502.69  5239.6  501.61
  5272.6  503.83  5586.6  513.76  5616.8  515.88  5628.2  518.51  5633.6  518.51
#Mann= 6 ,-1 , 0
  4323.1      .1       0  4669.4     .05       0  4925.6     .12       0
  4962.5     .07       0  4967.7     .12       0  5272.6     .05       0
Bank Sta=4962.5,4967.7
XS Rating Curve= 0 ,0
Exp/Cntr=0.3,0.1

Type RM Length L Ch R = 1 ,45718   ,417,417,417
BEGIN DESCRIPTION:
Wet Lacy Fork 3484
END DESCRIPTION:
XS GIS Cut Line= 3
      2765376.06      6874941.11      2765403.73       6875507.6
      2765739.08      6875969.43
#Sta/Elev= 30
  4271.4  509.16  4341.4  509.45  4361.4  507.42  4420.4  504.69  4441.5  503.59
  4471.5  505.37  4511.6  505.05  4561.6   501.3  4601.7  502.91  4632.9  502.16
  4801.9   500.1  4873.3  501.35  4929.3  501.24  4971.3  499.09    4986  491.18
  4989.6  490.25  4990.3  489.75  4994.8  490.25  5000.7  490.28  5006.9  498.18
  5036.2  498.12  5042.4  500.64  5050.9  498.53  5057.1   501.8  5065.2  500.05
  5089.5  503.19  5172.3  508.92  5201.2   509.7    5300  518.27  5409.3  520.29
#Mann= 7 ,-1 , 0
  4271.4      .1       0  4420.4     .05       0  4632.9    .075       0
  4873.3     .12       0  4989.6     .07       0  4994.8     .12       0
  5089.5     .05       0
Bank Sta=4989.6,4994.8
XS Rating Curve= 0 ,0
Exp/Cntr=0.3,0.1

Type RM Length L Ch R = 1 ,45301   ,366,366,366
BEGIN DESCRIPTION:
Wet Lacy Fork 3486
END DESCRIPTION:
XS GIS Cut Line= 3
      2765348.08      6874870.33      2765254.88      6875517.96
      2764930.45      6876002.47
#Sta/Elev= 30
  4351.7  510.49  4359.6  510.36  4404.7  509.67  4470.1  510.81  4483.7  506.31
  4493.8  505.51  4545.6   506.8  4564.5   505.9  4584.7   503.2  4616.1  503.25
  4681.5  500.81  4726.2   499.6    4908  500.15  4958.3  498.86  4960.1  497.27
  4963.3  494.44  4968.7  493.07  5002.2  488.51  5003.1  488.01  5007.8  488.51
  5009.5  488.51  5014.3   492.5  5044.3  497.31  5050.3  499.24  5111.5   499.8
  5202.2  501.25  5299.1  506.62  5431.6  513.83  5584.7  515.64  5589.1  516.76
#Mann= 8 ,-1 , 0
  4351.7      .1       0  4359.6     .05       0  4681.5    .075       0
  4960.1     .12       0  5002.2     .07       0  5007.8     .12       0
  5111.5     .05       0  5299.1     .12       0
Bank Sta=5002.2,5007.8
XS Rating Curve= 0 ,0
Exp/Cntr=0.3,0.1

Type RM Length L Ch R = 1 ,44935   ,511,511,511
BEGIN DESCRIPTION:
Wet Lacy Fork 3487
END DESCRIPTION:
XS GIS Cut Line= 3
      2765288.97      6874695.86      2765061.08      6875342.52
      2764800.69      6875725.55
#Sta/Elev= 30
  4312.2  515.47  4355.1  513.54  4434.3  510.84  4466.1  510.98  4489.6  507.48
  4515.3  508.89  4540.3  508.67  4571.8  505.46  4608.1  505.31  4696.4  502.07
  4757.5  501.03  4794.8  498.59  4850.4  497.14  4902.2  497.72  4963.6  498.12
    4975  496.97  4985.6  497.73  4997.8  496.87    5000  494.39  5006.1   492.3
  5012.2  487.96    5013  487.46  5017.8  487.96    5021  488.13  5035.9  497.12
  5122.6  501.64  5188.5  504.68  5317.3  512.87  5389.1   513.4    5461  511.99
#Mann= 9 ,-1 , 0
  4312.2     .12       0  4355.1     .05       0  4696.4     .12       0
  4794.8     .05       0  4902.2     .12       0  5006.1      .1       0
  5012.2     .07       0  5017.8      .1       0  5122.6     .05       0
Bank Sta=5012.2,5017.8
XS Rating Curve= 0 ,0
Exp/Cntr=0.3,0.1

Type RM Length L Ch R = 1 ,44424   ,358,358,358
BEGIN DESCRIPTION:
Wet Lacy Fork 3483
END DESCRIPTION:
XS GIS Cut Line= 3
      2764844.17       6874656.8      2764698.31      6875109.16
      2764618.42      6875547.54
#Sta/Elev= 30
  4523.5  517.33  4559.4  516.23  4597.6     513    4612  512.53  4706.5  503.29
  4763.1  499.81  4789.9  495.77  4801.1  492.35  4811.9  491.61  4827.2  492.46
  4832.6  493.99  4843.1  494.89  4923.4  495.98  4937.7  495.31  4969.2   496.2
  4979.7  487.63  4989.9  485.96  4990.8  485.46  4995.6  485.96  4997.1  487.53
  5002.3  487.53  5010.8  493.99  5030.6   495.7  5096.3  497.57  5154.7  500.16
  5285.3  508.58  5325.9  510.02  5356.4  510.87  5426.3  510.32  5444.4  509.56
#Mann= 5 ,-1 , 0
  4523.5     .05       0  4811.9     .12       0  4989.9     .07       0
  4995.6     .12       0  5030.6     .05       0
Bank Sta=4989.9,4995.6
XS Rating Curve= 0 ,0
Exp/Cntr=0.3,0.1

Type RM Length L Ch R = 1 ,44066   ,674,674,674
BEGIN DESCRIPTION:
Wet Lacy Fork 3482
END DESCRIPTION:
XS GIS Cut Line= 3
      2764202.06      6874341.84      2764371.75      6875014.62
      2764535.57      6875523.66
#Sta/Elev= 30
  4309.3     511  4468.4  508.99  4550.6  504.57  4555.9  503.09  4574.7  501.26
  4583.4  500.39  4607.5  499.42  4668.6  494.59  4714.8  493.72  4782.8  489.24
  4803.5  493.37  4845.8  493.43  4947.8  493.82  4956.1  490.29  4961.3  486.34
  4965.6  484.51  4966.5  484.01  4971.3  484.51  4978.8  486.63  4989.1  492.38
  4997.2   494.5  5029.5  496.68  5034.7  495.48  5041.4  496.76  5061.6  497.95
  5066.8  497.16    5125  499.54    5346  508.85  5482.6  507.56  5537.9  508.42
#Mann= 7 ,-1 , 0
  4309.3     .05       0  4574.7     .12       0  4583.4     .05       0
  4845.8     .12       0  4965.6     .07       0  4971.3     .12       0
    5125     .05       0
Bank Sta=4965.6,4971.3
XS Rating Curve= 0 ,0
Exp/Cntr=0.3,0.1