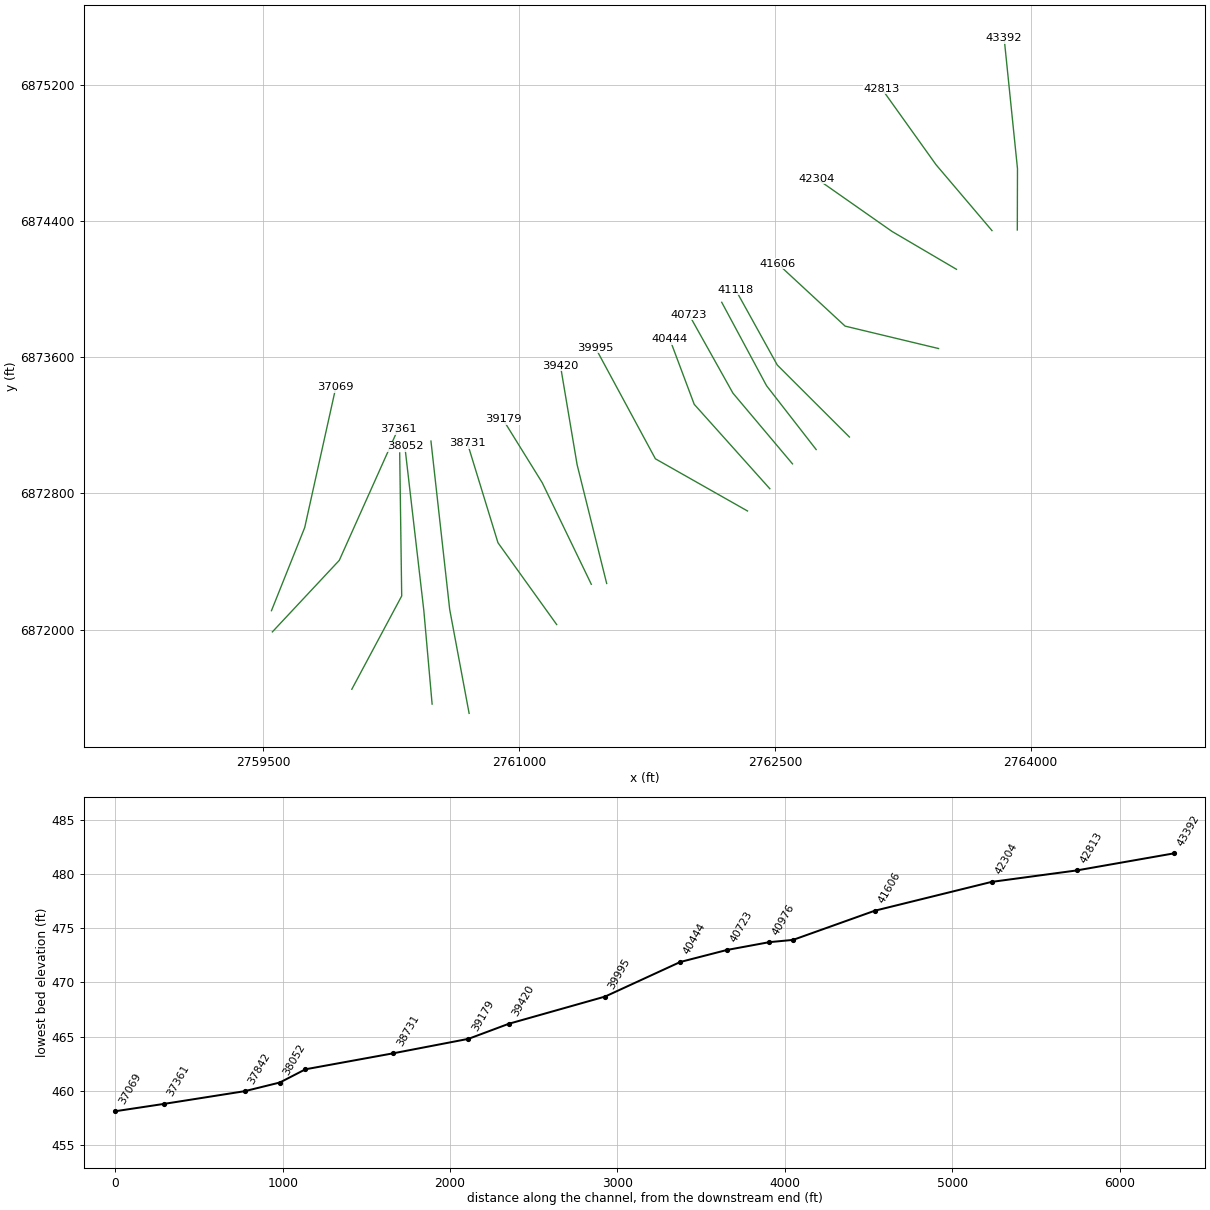
HEC-RAS study Wet Lacy Fork.prj: Wet Lacy Fork Base Level Engineering

--- Wet Lacy Fork.g01 (geometry) --- (continued)

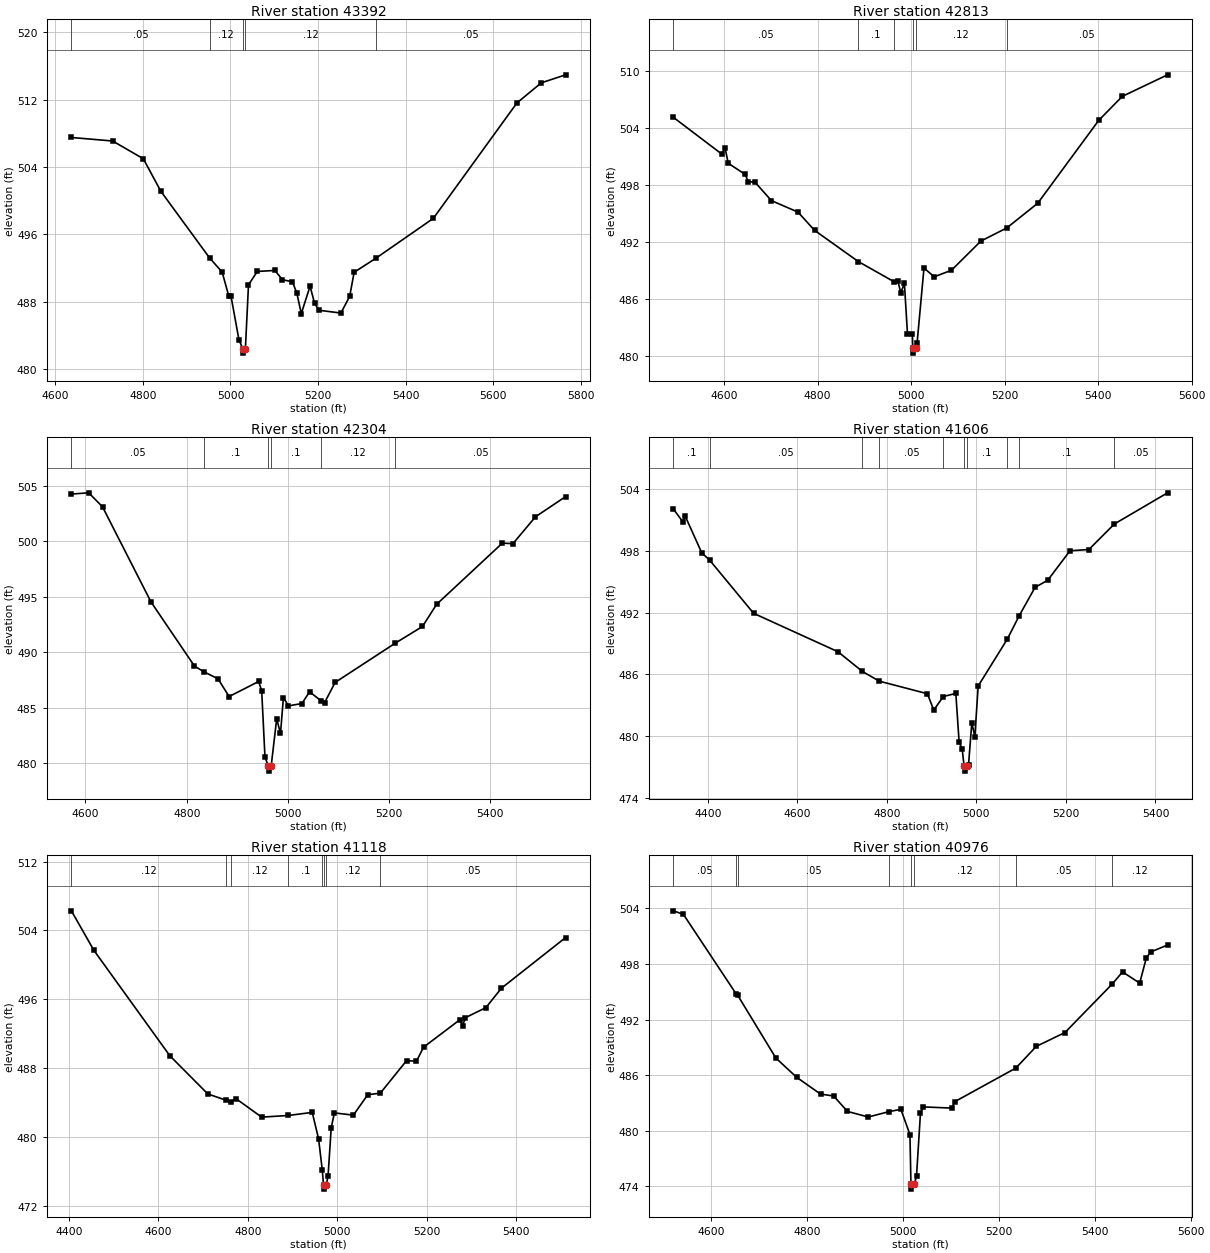
Type RM Length L Ch R = 1 ,43392   ,579,579,579
BEGIN DESCRIPTION:
Wet Lacy Fork 3481
END DESCRIPTION:
XS GIS Cut Line= 3
      2763922.56      6874346.63      2763923.62      6874706.69
      2763845.39      6875471.64
#Sta/Elev= 30
  4636.6  507.51    4731  507.09    4801  504.98    4841  501.12  4952.7  493.18
    4981  491.53  4996.3  488.65  5001.3  488.65  5019.3  483.51  5028.2   482.4
  5029.1   481.9  5034.1   482.4  5041.2  490.01  5061.3   491.6  5101.5  491.72
  5118.7  490.62  5141.7  490.37  5151.8  488.99  5161.8  486.59  5181.9  489.86
    5192  487.84    5202  486.99  5252.3  486.66  5272.4  488.64  5282.5   491.5
  5331.4  493.14  5463.4   497.9  5654.4  511.61  5710.1     514  5765.6  514.95
#Mann= 5 ,-1 , 0
  4636.6     .05       0  4952.7     .12       0  5028.2     .07       0
  5034.1     .12       0  5331.4     .05       0
Bank Sta=5028.2,5034.1
XS Rating Curve= 0 ,0
Exp/Cntr=0.3,0.1

Type RM Length L Ch R = 1 ,42813   ,509,509,509
BEGIN DESCRIPTION:
Wet Lacy Fork 3480
END DESCRIPTION:
XS GIS Cut Line= 3
      2763774.04      6874342.99      2763445.57      6874730.02
      2763126.23      6875177.04
#Sta/Elev= 30
  4491.4  505.14  4594.6  501.29  4602.3  501.86  4608.8  500.31  4645.1  499.13
  4651.7  498.37    4666  498.32  4701.1  496.38  4758.2  495.16  4793.4  493.25
  4887.2  489.96  4962.8  487.86  4971.4  487.95  4977.9  486.69  4985.6  487.68
  4992.2  482.37  5002.7  482.36  5003.6  480.83  5004.6  480.33  5009.6  480.83
  5012.8  481.42  5027.5  489.28  5049.4  488.36  5086.3  489.05  5149.2  492.12
  5204.6   493.5  5270.8   496.1  5401.1  504.81  5451.5  507.34  5548.4  509.61
#Mann= 6 ,-1 , 0
  4491.4     .05       0  4887.2      .1       0  4962.8     .12       0
  5003.6     .07       0  5009.6     .12       0  5204.6     .05       0
Bank Sta=5003.6,5009.6
XS Rating Curve= 0 ,0
Exp/Cntr=0.3,0.1

Type RM Length L Ch R = 1 ,42304   ,698,698,698
BEGIN DESCRIPTION:
Wet Lacy Fork 3479
END DESCRIPTION:
XS GIS Cut Line= 3
      2763565.65      6874115.75      2763187.72      6874337.93
      2762747.25      6874646.68
#Sta/Elev= 30
  4572.2  504.23  4606.5  504.34  4633.7  503.08  4729.5  494.51  4815.4  488.73
  4834.8   488.2  4861.8  487.59  4883.8  485.99  4942.4  487.35  4948.2  486.47
  4954.6  480.56  4960.8  479.77  4961.8  479.27    4967  479.77  4977.8  483.98
  4985.3  482.66  4991.1   485.9    5001  485.15  5027.8  485.36  5042.7  486.42
    5065  485.62  5072.3  485.43  5093.2  487.26  5211.8  490.79  5265.8   492.3
  5293.6  494.29  5423.6  499.81  5444.5  499.76    5489  502.18  5548.5     504
#Mann= 6 ,-1 , 0
  4572.2     .05       0  4834.8      .1       0  4960.8     .07       0
    4967      .1       0    5065     .12       0  5211.8     .05       0
Bank Sta=4960.8,4967
XS Rating Curve= 0 ,0
Exp/Cntr=0.3,0.1

Type RM Length L Ch R = 1 ,41606   ,488,488,488
BEGIN DESCRIPTION:
Wet Lacy Fork 3470
END DESCRIPTION:
XS GIS Cut Line= 3
      2763460.48      6873650.63      2762912.35      6873782.22
      2762516.23      6874149.21
#Sta/Elev= 30
  4323.2  502.08  4344.7  500.82  4349.9  501.37  4386.7  497.82  4404.1  497.12
  4502.6  491.94  4690.9  488.21  4745.6  486.29  4783.3  485.35  4890.6  484.13
  4904.8  482.54  4926.2  483.86  4954.1  484.16  4961.5   479.4  4968.3  478.78
  4972.5  477.11  4973.5  476.61  4978.7  477.11  4982.5  477.24  4989.8   481.3
  4996.6  479.96    5004  484.88    5069  489.43  5095.9  491.73    5131  494.46
  5159.4  495.16  5209.1  498.02  5251.2  498.14  5308.1  500.62  5426.9  503.65
#Mann= 10 ,-1 , 0
  4323.2      .1       0  4404.1     .05       0  4745.6      .1       0
  4783.3     .05       0  4926.2      .1       0  4972.5     .07       0
  4978.7      .1       0    5069     .12       0  5095.9      .1       0
  5308.1     .05       0
Bank Sta=4972.5,4978.7
XS Rating Curve= 0 ,0
Exp/Cntr=0.3,0.1

Type RM Length L Ch R = 1 ,41118   ,142,142,142
BEGIN DESCRIPTION:
Wet Lacy Fork 18
END DESCRIPTION:
XS GIS Cut Line= 3
      2762937.52      6873131.22      2762514.35      6873553.82
      2762269.22        6873997.
#Sta/Elev= 30
  4405.7  506.27  4456.1  501.67  4625.8  489.42  4710.7  484.98  4751.9  484.25
    4762  484.03  4774.3  484.41  4830.9  482.29  4890.4  482.48    4944  482.84
  4958.2  479.75  4966.5   476.1  4969.2  474.42  4970.2  473.92  4975.5  474.42
  4979.4  475.49  4986.4  481.06  4993.5  482.78  5035.9  482.52    5068  484.89
  5096.2  485.08    5155  488.87  5176.8  488.78  5192.8  490.42  5274.2  493.62
  5279.9   492.9  5286.2  493.85  5331.9  495.01  5366.9  497.28  5510.2  503.16
#Mann= 8 ,-1 , 0
  4405.7     .12       0  4751.9     .05       0    4762     .12       0
  4890.4      .1       0  4966.5     .12       0  4969.2     .07       0
  4975.5     .12       0  5096.2     .05       0
Bank Sta=4969.2,4975.5
XS Rating Curve= 0 ,0
Exp/Cntr=0.3,0.1

Type RM Length L Ch R = 1 ,40976   ,253,253,253
BEGIN DESCRIPTION:
Wet Lacy Fork 3468
END DESCRIPTION:
XS GIS Cut Line= 3
      2762742.45      6873057.62      2762451.46      6873432.35
      2762188.49      6873922.07
#Sta/Elev= 30
  4521.5  503.73  4542.5  503.35  4652.6  494.76  4655.6  494.63  4735.3  487.85
  4778.7  485.77  4828.5  483.96  4855.6  483.76  4884.6  482.09    4928  481.49
  4971.1  482.07  4995.9  482.32  5014.8  479.59  5016.9  474.21    5018  473.71
  5023.9  474.21  5028.5  475.14  5036.7  481.89  5042.3  482.58  5102.4  482.45
  5108.1  483.14  5235.6  486.77  5278.2  489.11  5337.9   490.6  5436.6  495.84
    5458  497.14  5493.8  495.93  5507.5  498.65  5516.5  499.29  5551.8  500.04
#Mann= 8 ,-1 , 0
  4521.5     .05       0  4652.6     .12       0  4655.6     .05       0
  4971.1     .12       0  5016.9     .07       0  5023.9     .12       0
  5235.6     .05       0  5436.6     .12       0
Bank Sta=5016.9,5023.9
XS Rating Curve= 0 ,0
Exp/Cntr=0.3,0.1

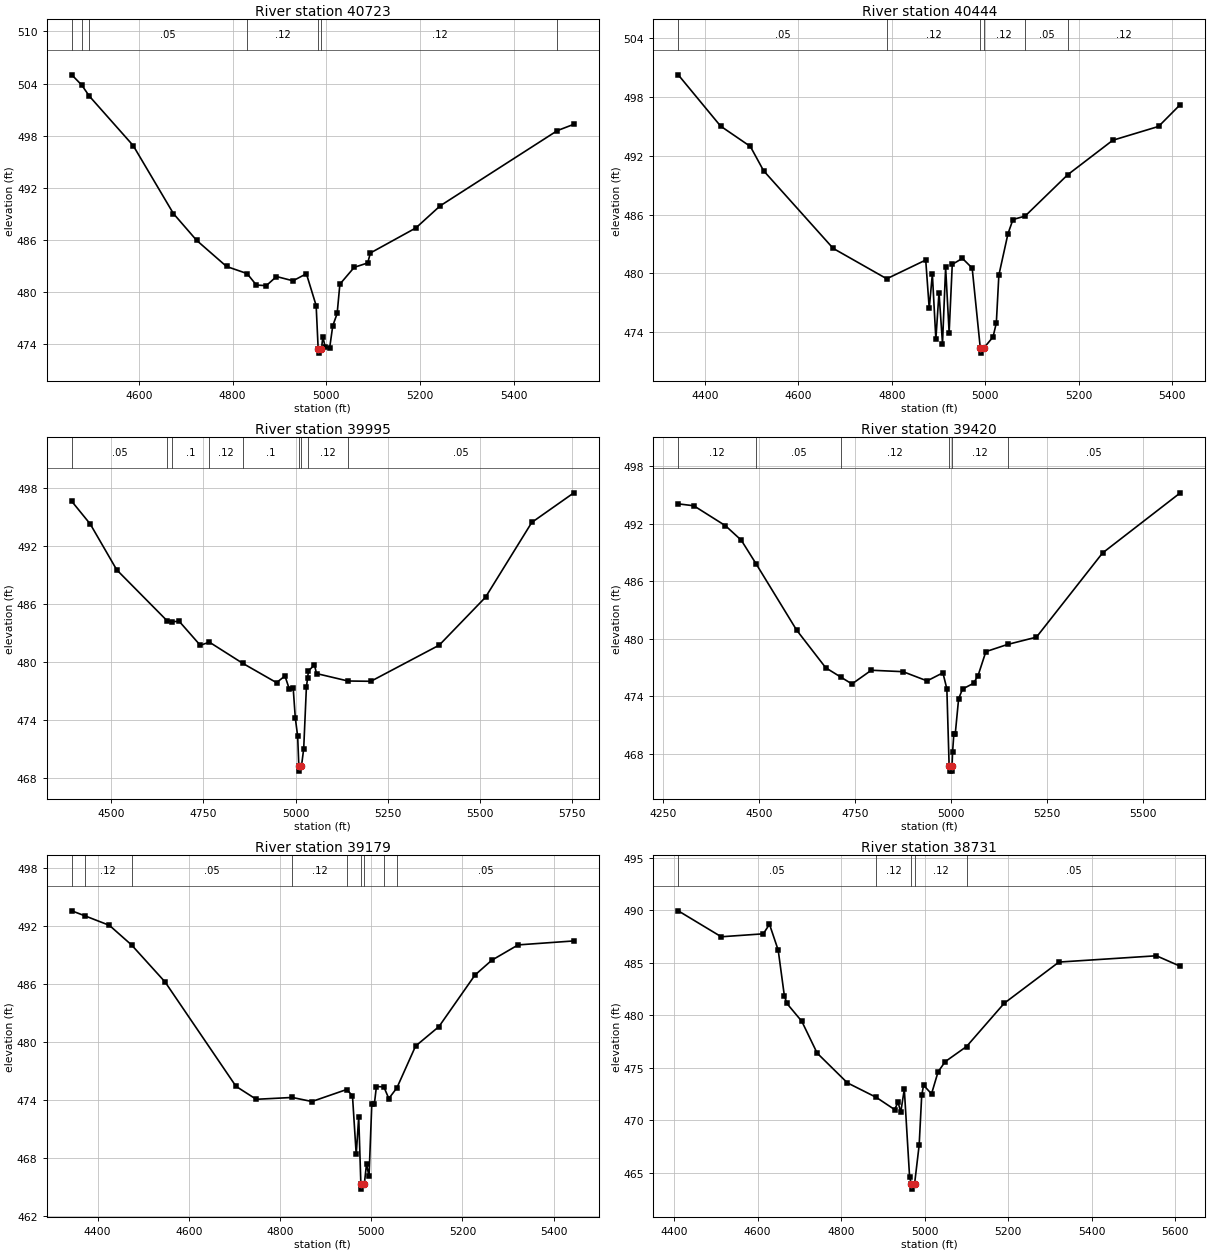
Type RM Length L Ch R = 1 ,40723   ,279,279,279
BEGIN DESCRIPTION:
Wet Lacy Fork 3469
END DESCRIPTION:
XS GIS Cut Line= 3
      2762603.63      6872973.66      2762254.41      6873388.55
      2761996.51      6873849.86
#Sta/Elev= 30
  4456.9     505  4478.2  503.82  4494.2  502.56  4587.9  496.86  4673.7  489.04
  4723.2  485.96  4786.9  482.96  4830.8  482.14  4850.6  480.82  4871.7  480.75
  4893.5   481.8  4928.7  481.31  4957.3  482.12  4978.1  478.46  4982.4  473.49
  4983.5  472.99  4989.4  473.49  4992.4  474.85  4997.5  473.68    5007  473.63
  5013.5  476.12  5022.9  477.55  5028.7  480.92  5059.3  482.86    5088  483.36
  5093.8  484.51  5190.8  487.39  5242.6  489.93  5492.7  498.59  5527.7  499.31
#Mann= 7 ,-1 , 0
  4456.9     .05       0  4478.2     .12       0  4494.2     .05       0
  4830.8     .12       0  4982.4     .07       0  4989.4     .12       0
  5492.7     .05       0
Bank Sta=4982.4,4989.4
XS Rating Curve= 0 ,0
Exp/Cntr=0.3,0.1

Type RM Length L Ch R = 1 ,40444   ,449,449,449
BEGIN DESCRIPTION:
Wet Lacy Fork 3466
END DESCRIPTION:
XS GIS Cut Line= 3
      2762470.73      6872827.52      2762027.05      6873323.23
      2761883.52      6873706.36
#Sta/Elev= 30
  4342.8  500.25  4433.5  495.02  4497.1  492.95  4525.5  490.47  4674.3  482.56
    4789  479.46  4872.4  481.37  4879.9  476.44  4886.6  479.94  4894.1   473.3
  4900.8  478.06  4908.3  472.86    4915  480.61  4922.5  473.97  4929.2  480.93
  4950.9  481.54  4971.8  480.55  4989.2  472.38  4990.3  471.88  4996.3  472.38
  5016.4  473.52  5023.5  474.96  5028.9  479.83  5048.4  484.05  5059.1   485.5
  5085.1  485.85  5176.1  490.06  5272.7  493.58  5370.7  494.99  5417.2  497.22
#Mann= 6 ,-1 , 0
  4342.8     .05       0    4789     .12       0  4989.2     .07       0
  4996.3     .12       0  5085.1     .05       0  5176.1     .12       0
Bank Sta=4989.2,4996.3
XS Rating Curve= 0 ,0
Exp/Cntr=0.3,0.1

Type RM Length L Ch R = 1 ,39995   ,575,575,575
BEGIN DESCRIPTION:
Wet Lacy Fork 3467
END DESCRIPTION:
XS GIS Cut Line= 3
      2762339.65      6872697.02      2761799.33      6873003.33
      2761446.78      6873656.57
#Sta/Elev= 30
  4392.4  496.59  4442.6  494.24  4514.6   489.5  4650.7  484.26  4665.7  484.14
    4684  484.19  4741.4   481.7    4766  482.03  4856.2  479.85  4948.4  477.84
  4971.3  478.53  4983.5  477.14  4993.6  477.31  4999.4  474.19  5005.8   472.3
    5009  469.19  5010.1  468.69  5016.1  469.19  5022.2     471  5029.5  477.34
  5032.7  478.31  5035.2  479.06  5051.4  479.67    5057  478.78  5142.5  478.01
  5204.6  477.98  5390.3  481.72  5515.9  486.67  5641.6  494.41  5755.8  497.47
#Mann= 9 ,-1 , 0
  4392.4     .05       0  4650.7     .12       0  4665.7      .1       0
    4766     .12       0  4856.2      .1       0    5009     .07       0
  5016.1      .1       0  5032.7     .12       0  5142.5     .05       0
Bank Sta=5009,5016.1
XS Rating Curve= 0 ,0
Exp/Cntr=0.3,0.1

Type RM Length L Ch R = 1 ,39420   ,241,241,241
BEGIN DESCRIPTION:
Wet Lacy Fork 3465
END DESCRIPTION:
XS GIS Cut Line= 3
      2761513.44      6872271.58      2761340.06       6872968.7
      2761242.16      6873550.77
#Sta/Elev= 30
  4289.2  494.05  4329.8  493.85  4412.3  491.77  4453.5  490.26    4493  487.74
  4597.7  480.89  4673.6  476.96  4712.3     476    4742  475.27  4792.4   476.7
  4875.1  476.55  4937.8  475.59    4979  476.43  4989.3  474.77  4995.3  466.68
  4996.5  466.18  5001.7  466.18  5002.8  466.68  5004.2  468.13  5007.6   470.1
  5011.3   470.1    5020  473.73  5030.2  474.74  5058.9  475.34  5070.7  476.15
    5091  478.64  5147.6  479.39  5222.8  480.15  5395.2  488.93  5597.8   495.2
#Mann= 6 ,-1 , 0
  4289.2     .12       0    4493     .05       0  4712.3     .12       0
  4995.3     .07       0  5002.8     .12       0  5147.6     .05       0
Bank Sta=4995.3,5002.8
XS Rating Curve= 0 ,0
Exp/Cntr=0.3,0.1

Type RM Length L Ch R = 1 ,39179   ,448,448,448
BEGIN DESCRIPTION:
Wet Lacy Fork 3464
END DESCRIPTION:
XS GIS Cut Line= 3
       2761423.3      6872266.75      2761135.72      6872862.39
      2760904.25      6873235.96
#Sta/Elev= 30
  4343.4  493.54  4371.8  493.03  4425.9  492.04  4474.6  490.01    4548  486.19
  4703.5  475.41  4747.9  474.07  4826.9  474.26    4870  473.84  4946.1  475.08
  4958.9  474.44  4967.1  468.37  4972.6  472.25  4977.3  465.29  4978.5  464.79
  4984.8  465.29  4989.7  467.39  4995.2   466.1  5001.3  473.62    5007  473.62
  5011.4  475.39  5027.7  475.35  5038.6  474.15  5056.3  475.25  5097.3  479.57
  5148.5  481.58  5227.6  486.91  5264.2  488.43  5322.1  490.02  5444.3  490.43
#Mann= 9 ,-1 , 0
  4343.4     .05       0  4371.8     .12       0  4474.6     .05       0
  4826.9     .12       0  4946.1      .1       0  4977.3     .07       0
  4984.8      .1       0  5027.7     .12       0  5056.3     .05       0
Bank Sta=4977.3,4984.8
XS Rating Curve= 0 ,0
Exp/Cntr=0.3,0.1

Type RM Length L Ch R = 1 ,38731   ,526,526,526
BEGIN DESCRIPTION:
Wet Lacy Fork 3463
END DESCRIPTION:
XS GIS Cut Line= 3
      2761219.94      6872030.56      2760875.75      6872510.52
      2760696.31      6873095.82
#Sta/Elev= 30
  4409.7  489.96  4512.8  487.49  4613.5  487.77  4628.3  488.68  4649.2  486.21
  4663.9  481.88    4670  481.14  4705.7  479.44  4742.5  476.41  4814.9  473.58
  4884.1   472.2  4927.9  471.04  4936.5  471.73  4942.7  470.77  4951.3  472.97
    4964  464.59  4968.3  463.96  4969.5  463.46  4975.9  463.96  4986.9  467.67
    4993  472.41  4997.5  473.35  5016.5  472.53  5032.2  474.63  5049.3   475.6
  5100.4  477.04  5190.7  481.16  5321.7  485.08  5555.2  485.68  5612.5  484.68
#Mann= 5 ,-1 , 0
  4409.7     .05       0  4884.1     .12       0  4968.3     .07       0
  4975.9     .12       0  5100.4     .05       0
Bank Sta=4968.3,4975.9
XS Rating Curve= 0 ,0
Exp/Cntr=0.3,0.1

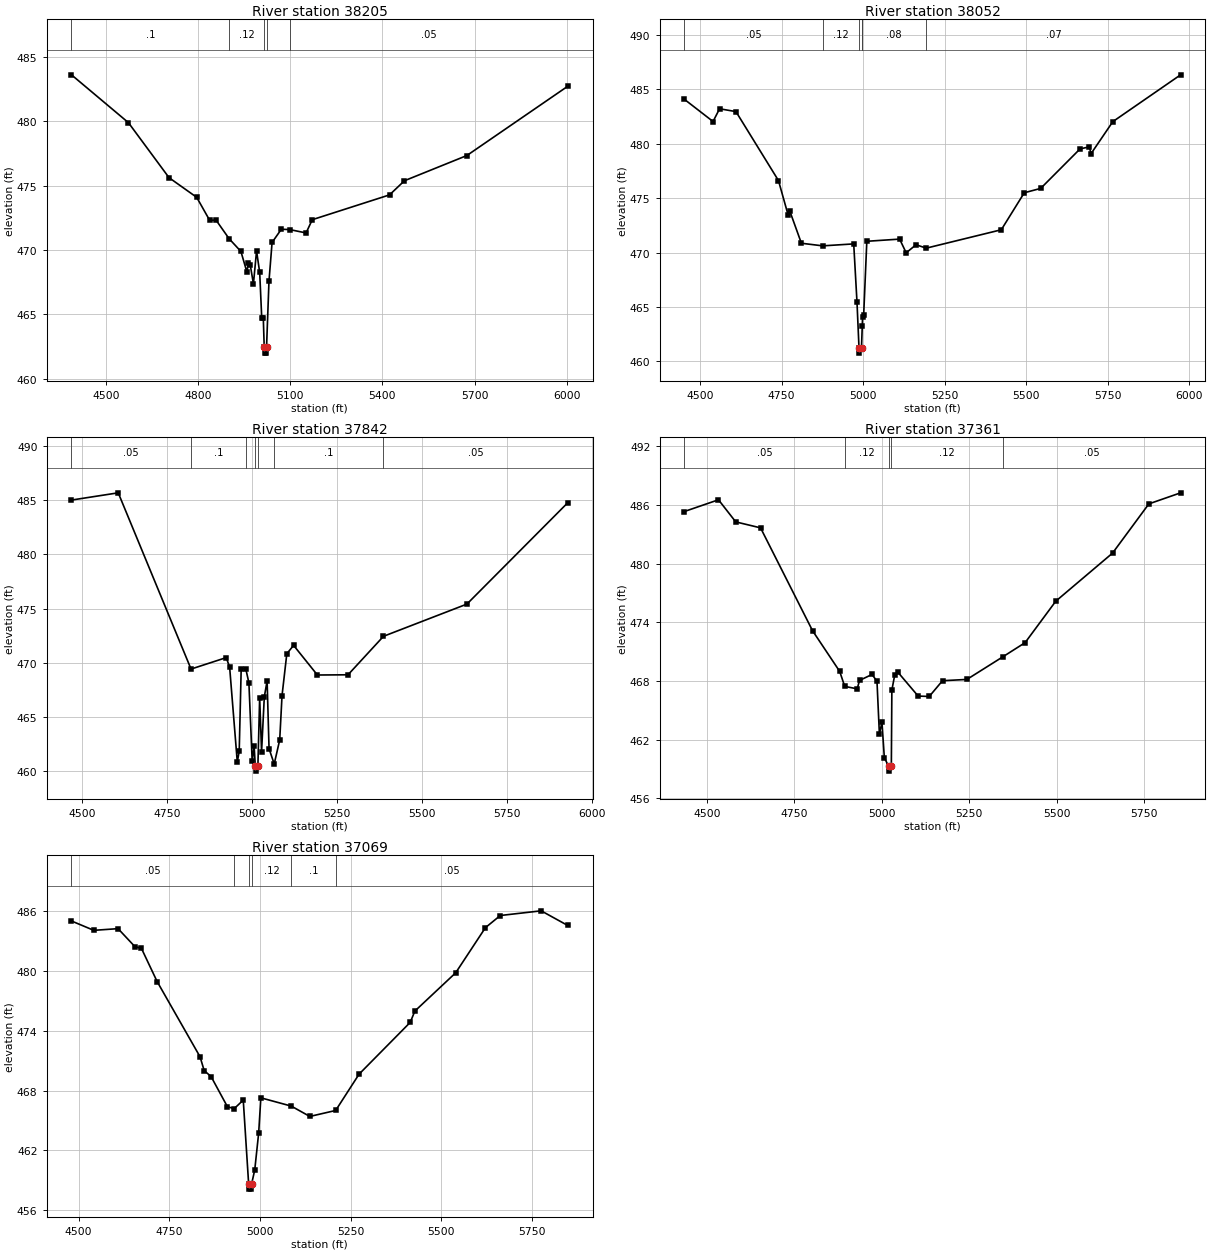
Type RM Length L Ch R = 1 ,38205   ,153,153,153
BEGIN DESCRIPTION:
Wet Lacy Fork 3462
END DESCRIPTION:
XS GIS Cut Line= 3
      2760706.52      6871508.86      2760592.52      6872119.13
       2760482.6      6873107.41
#Sta/Elev= 30
    4388  483.63  4573.3  479.91  4705.5  475.63  4795.6   474.1  4837.8  472.31
  4858.5  472.33  4901.1  470.88  4939.5  469.89  4958.7  468.31  4963.8  468.96
    4970  468.82  4980.2  467.37  4990.4  469.93  5000.6  468.26  5007.2  464.74
  5012.3  464.74  5015.3  462.48  5016.5  461.98  5021.9  461.98    5023  462.48
  5030.8  467.56  5040.9  470.59  5071.1  471.62  5098.6  471.59  5151.6  471.33
  5171.7  472.36  5423.2  474.29  5471.7  475.39  5674.8  477.35  6003.2  482.74
#Mann= 5 ,-1 , 0
    4388      .1       0  4901.1     .12       0  5015.3     .07       0
    5023     .12       0  5098.6     .05       0
Bank Sta=5015.3,5023
XS Rating Curve= 0 ,0
Exp/Cntr=0.3,0.1

Type RM Length L Ch R = 1 ,38052   ,210,210,210
BEGIN DESCRIPTION:
Wet Lacy Fork 3459
END DESCRIPTION:
XS GIS Cut Line= 3
      2760489.43      6871563.32      2760440.77      6872112.82
      2760329.25      6873077.54
#Sta/Elev= 30
  4451.4  484.09  4539.4  482.05  4559.5  483.22  4609.7  482.96  4740.2  476.62
  4769.5  473.49  4774.5  473.86  4810.5  470.86  4876.1  470.62  4971.1   470.8
  4981.1  465.48  4987.3  461.26  4988.5  460.76    4995  461.26  4997.3  463.21
  4998.3  464.06  5001.7   464.3  5011.3  471.04    5112  471.24  5132.1  469.98
  5162.3  470.72  5193.8  470.41    5424   472.1  5494.5   475.5  5544.8   475.9
  5665.6  479.53  5694.2  479.72  5699.3  479.09  5766.3  482.04  5974.2  486.34
#Mann= 6 ,-1 , 0
  4451.4     .05       0  4876.1     .12       0  4987.3     .05       0
    4995     .12       0  4997.3     .08       0  5193.8     .07       0
Bank Sta=4987.3,4995
XS Rating Curve= 0 ,0
Exp/Cntr=0.3,0.1

Type RM Length L Ch R = 1 ,37842   ,481,481,481
BEGIN DESCRIPTION:
Wet Lacy Fork 3460
END DESCRIPTION:
XS GIS Cut Line= 3
      2760018.35      6871650.47      2760310.99      6872197.97
      2760299.25      6873037.68
#Sta/Elev= 30
  4469.1  485.03  4606.7   485.7    4821   469.4  4924.6  470.46  4934.6  469.58
  4957.1  460.81  4962.8   461.8  4968.6  469.43    4982  469.44  4991.3  468.13
    5001  460.86  5006.7  462.26  5010.1  460.46  5011.3  459.96  5017.8  460.46
    5023  466.75  5028.6  461.75  5036.6  466.81  5044.9  468.32  5050.6  462.04
  5065.8  460.62    5082  462.85  5088.8  466.94  5102.9  470.82  5122.9  471.59
  5192.9  468.85    5283  468.87  5387.4  472.43    5633  475.41  5929.7  484.78
#Mann= 7 ,-1 , 0
  4469.1     .05       0    4821      .1       0    4982     .12       0
  5010.1     .07       0  5017.8     .12       0  5065.8      .1       0
  5387.4     .05       0
Bank Sta=5010.1,5017.8
XS Rating Curve= 0 ,0
Exp/Cntr=0.3,0.1

Type RM Length L Ch R = 1 ,37361   ,292,292,292
BEGIN DESCRIPTION:
Wet Lacy Fork 3461
END DESCRIPTION:
XS GIS Cut Line= 3
      2759552.18      6871987.18      2759944.82      6872407.23
      2760289.09      6873176.41
#Sta/Elev= 30
  4436.1  485.32  4533.6  486.52  4582.9  484.26  4653.8  483.65  4802.3  473.14
  4879.9  468.98  4894.2  467.45  4929.8   467.2  4936.6  468.06  4972.3  468.67
  4986.4  467.97  4993.3  462.57  5000.6   463.8  5007.4  460.17  5019.5  459.29
  5020.7  458.79  5027.4  459.29  5028.9  467.06  5037.1  468.62  5046.6  468.88
    5104  466.46  5135.7  466.42  5173.6  468.03  5243.2  468.16  5345.9  470.47
  5409.6  471.92  5497.3  476.16  5659.4  481.07  5763.1   486.1  5853.8  487.23
#Mann= 5 ,-1 , 0
  4436.1     .05       0  4894.2     .12       0  5019.5     .07       0
  5027.4     .12       0  5345.9     .05       0
Bank Sta=5019.5,5027.4
XS Rating Curve= 0 ,0
Exp/Cntr=0.3,0.1

Type RM Length L Ch R = 1 ,37069   ,725,725,725
BEGIN DESCRIPTION:
Wet Lacy Fork 3458
END DESCRIPTION:
XS GIS Cut Line= 3
      2759546.97      6872111.79      2759741.98       6872599.7
      2759924.42      6873422.48
#Sta/Elev= 30
  4480.2  485.04  4541.8   484.1  4608.6  484.27  4654.9  482.47  4673.2  482.28
  4716.3  478.96  4834.7   471.4  4846.1  470.01    4865  469.42  4910.1  466.39
  4928.7  466.19  4953.8  467.05  4968.7  458.61  4969.9  458.11  4975.5  458.11
  4976.7  458.61  4985.5  460.04  4996.3  463.75  5002.3  467.28  5086.1  466.45
  5137.3  465.41  5208.6  466.01  5273.2  469.66  5414.2  474.86  5426.9  475.99
  5539.6  479.84  5621.5  484.37  5662.5  485.59  5775.2  486.06  5848.4  484.59
#Mann= 6 ,-1 , 0
  4480.2     .05       0  4928.7     .12       0  4968.7     .07       0
  4976.7     .12       0  5086.1      .1       0  5208.6     .05       0
Bank Sta=4968.7,4976.7
XS Rating Curve= 0 ,0
Exp/Cntr=0.3,0.1