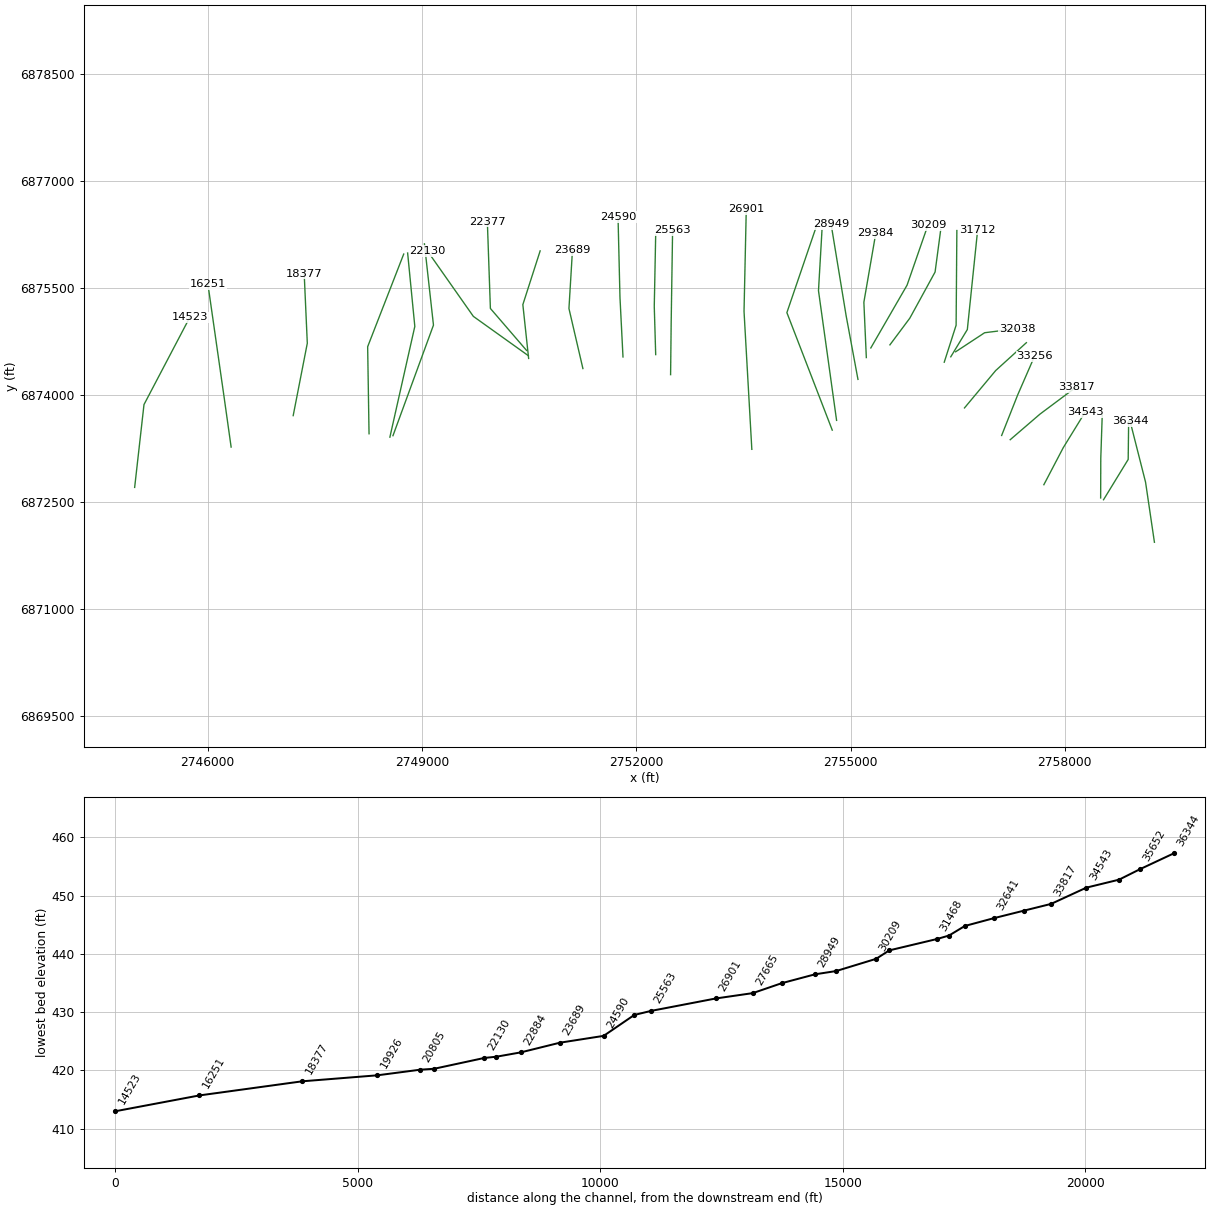
HEC-RAS study Wet Lacy Fork.prj: Wet Lacy Fork Base Level Engineering

--- Wet Lacy Fork.g01 (geometry) --- (continued)

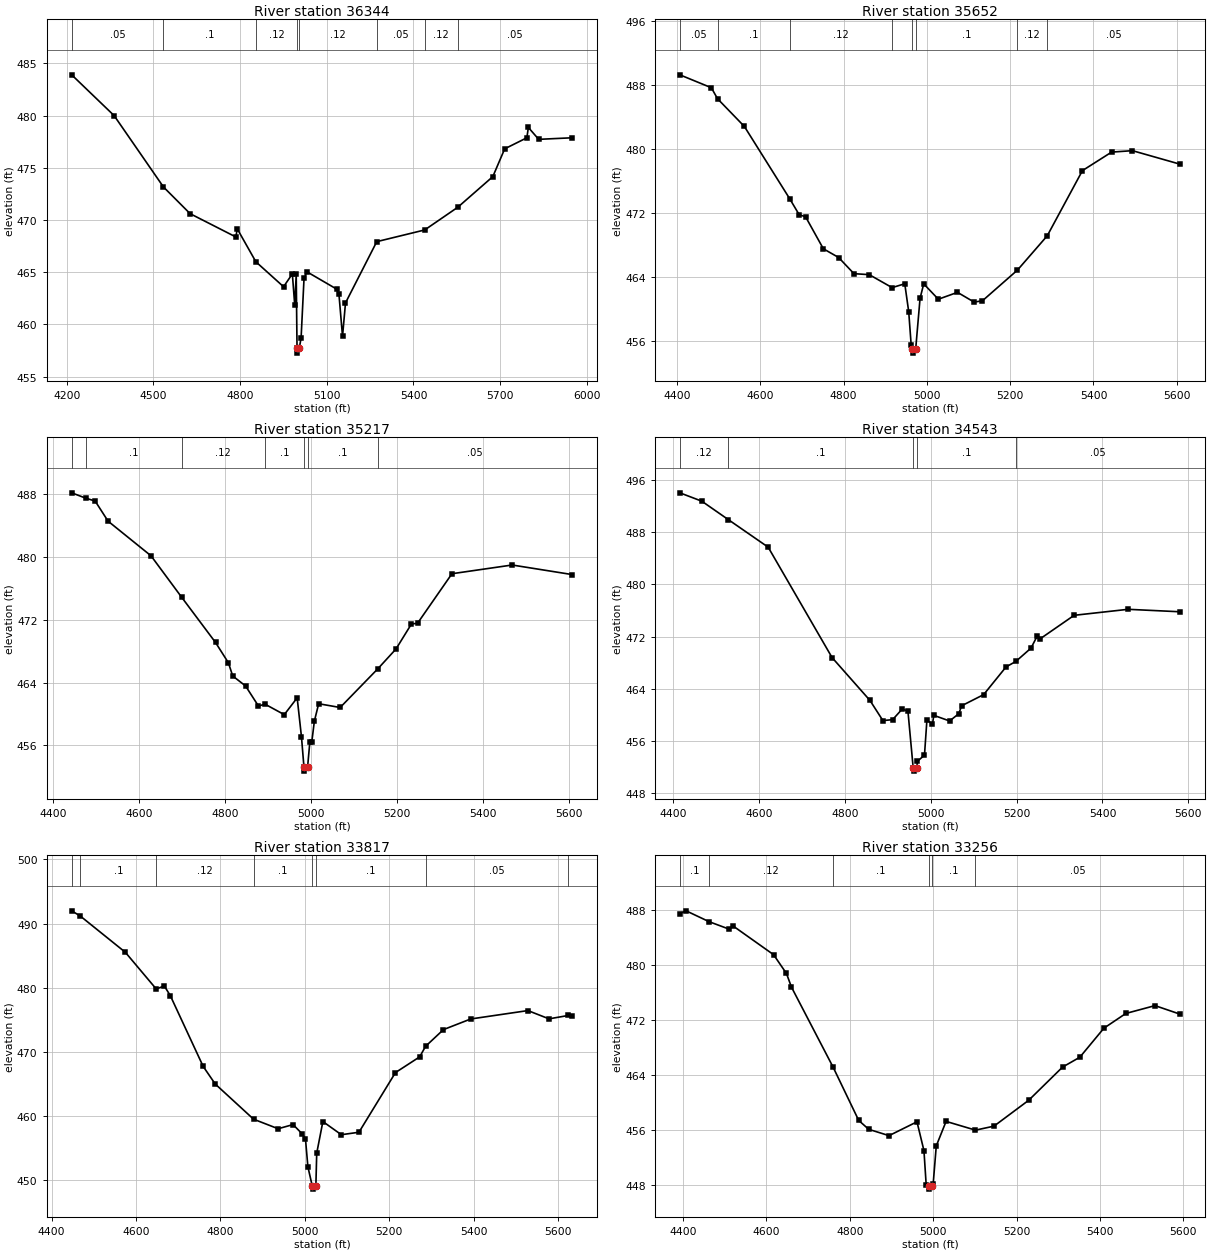
Type RM Length L Ch R = 1 ,36344   ,692,692,692
BEGIN DESCRIPTION:
Wet Lacy Fork 3457
END DESCRIPTION:
XS GIS Cut Line= 3
      2759254.05       6871935.7      2759130.03      6872776.98
      2758913.23      6873631.54
#Sta/Elev= 30
  4217.5   483.9  4364.4  479.99  4534.9  473.16  4627.2   470.6  4785.4  468.37
  4790.5  469.14  4854.8  465.99  4950.6   463.6    4981  464.83  4989.3  461.82
  4994.4  464.78  4997.2  457.74  4998.4  457.24  5005.2  457.74  5011.3  458.71
  5021.4  464.39  5031.5  465.03  5133.9  463.38  5142.2  462.89  5154.6  458.85
  5164.9  462.05  5273.1  467.92    5439  469.04  5553.7  471.22  5674.7  474.15
  5715.7  476.81  5792.5  477.87  5797.6  478.86  5833.4  477.72  5949.5  477.87
#Mann= 8 ,-1 , 0
  4217.5     .05       0  4534.9      .1       0  4854.8     .12       0
  4997.2     .07       0  5005.2     .12       0  5273.1     .05       0
    5439     .12       0  5553.7     .05       0
Bank Sta=4997.2,5005.2
XS Rating Curve= 0 ,0
Exp/Cntr=0.3,0.1

Type RM Length L Ch R = 1 ,35652   ,435,435,435
BEGIN DESCRIPTION:
Wet Lacy Fork 3456
END DESCRIPTION:
XS GIS Cut Line= 3
      2758541.61      6872531.42      2758886.69      6873095.76
       2758893.3      6873636.14
#Sta/Elev= 30
  4406.8  489.29  4482.4  487.68  4497.4   486.3  4561.8  482.84  4670.7  473.81
  4693.3  471.83  4708.8  471.56  4751.4  467.57  4788.1  466.48  4824.9  464.46
  4861.6  464.34  4916.5  462.72  4946.9   463.2  4956.4   459.7  4962.3  455.54
  4964.8  455.04    4966  454.54  4973.1  455.04  4983.6  461.38  4992.4  463.19
  5027.5  461.27  5073.5  462.13  5113.5  460.91  5133.5  461.08  5217.5  464.91
    5289  469.19  5373.5  477.33  5443.5  479.64  5493.6  479.82  5608.7  478.12
#Mann= 8 ,-1 , 0
  4406.8     .05       0  4497.4      .1       0  4670.7     .12       0
  4916.5      .1       0  4964.8     .07       0  4973.1      .1       0
  5217.5     .12       0    5289     .05       0
Bank Sta=4964.8,4973.1
XS Rating Curve= 0 ,0
Exp/Cntr=0.3,0.1

Type RM Length L Ch R = 1 ,35217   ,674,674,674
BEGIN DESCRIPTION:
Wet Lacy Fork 3455
END DESCRIPTION:
XS GIS Cut Line= 3
      2758501.37      6872556.45      2758503.16      6873114.97
       2758523.6       6873720.7
#Sta/Elev= 30
    4444   488.2  4476.7  487.52  4498.6  487.15  4528.6  484.59  4628.6  480.17
  4699.6  474.91  4778.6  469.13  4808.6  466.54  4818.6  464.86  4848.6  463.58
  4878.6  461.02  4893.6  461.27  4938.6  459.93  4968.6  462.07  4978.6   457.1
  4984.4  453.23  4985.6  452.73  4992.8  453.23    4998   456.4  5002.5   456.4
  5008.6   459.1  5018.6  461.32  5068.6  460.84  5156.9  465.81  5198.7  468.31
  5234.4  471.48  5248.7  471.58  5328.7  477.89  5468.8     479  5608.6  477.78
#Mann= 7 ,-1 , 0
    4444     .05       0  4476.7      .1       0  4699.6     .12       0
  4893.6      .1       0  4984.4     .07       0  4992.8      .1       0
  5156.9     .05       0
Bank Sta=4984.4,4992.8
XS Rating Curve= 0 ,0
Exp/Cntr=0.3,0.1

Type RM Length L Ch R = 1 ,34543   ,726,726,726
BEGIN DESCRIPTION:
Wet Lacy Fork 3454
END DESCRIPTION:
XS GIS Cut Line= 3
      2757706.49      6872742.23      2757977.85      6873260.62
      2758281.73      6873754.73
#Sta/Elev= 30
  4416.2  494.03  4467.3  492.75  4529.1  489.92  4621.8   485.7  4770.6  468.77
  4858.9  462.19  4888.9  459.11  4911.5  459.25    4934  460.89  4947.2  460.54
  4959.4  451.86  4960.6  451.36  4967.9  451.86  4969.3  452.87  4985.7  453.81
  4991.3  459.14  5004.3  458.61  5007.5  459.91  5044.2  459.05  5065.5  460.16
  5072.2  461.38  5123.4  463.09  5175.6  467.34  5198.2  468.17  5233.5  470.21
  5248.3  472.09  5254.8  471.64  5334.1  475.25  5459.6  476.17  5581.4  475.79
#Mann= 5 ,-1 , 0
  4416.2     .12       0  4529.1      .1       0  4959.4     .07       0
  4967.9      .1       0  5198.2     .05       0
Bank Sta=4959.4,4967.9
XS Rating Curve= 0 ,0
Exp/Cntr=0.3,0.1

Type RM Length L Ch R = 1 ,33817   ,561,561,561
BEGIN DESCRIPTION:
Wet Lacy Fork 3453
END DESCRIPTION:
XS GIS Cut Line= 3
      2757235.45      6873372.43      2757651.59      6873730.65
      2758161.38      6874111.62
#Sta/Elev= 30
  4447.7  491.98  4468.2  491.16  4574.8  485.51  4647.9  479.79    4667  480.26
  4681.2  478.76  4759.1  467.71  4787.6  464.97  4878.4  459.48  4936.6  457.99
    4972  458.64  4992.8  457.24  5001.3  456.46  5007.1  452.06  5017.4  449.07
  5018.7  448.57    5026  449.07    5028  454.17  5042.6  459.11  5086.3  457.06
    5128  457.44  5214.5  466.75  5271.8   469.2  5285.9  470.85  5328.1  473.45
  5392.7  475.11  5528.2  476.42  5578.2  475.13    5624  475.66  5633.2   475.6
#Mann= 8 ,-1 , 0
  4447.7     .12       0  4468.2      .1       0  4647.9     .12       0
  4878.4      .1       0  5017.4     .07       0    5026      .1       0
  5285.9     .05       0    5624     .12       0
Bank Sta=5017.4,5026
XS Rating Curve= 0 ,0
Exp/Cntr=0.3,0.1

Type RM Length L Ch R = 1 ,33256   ,615,615,615
BEGIN DESCRIPTION:
Wet Lacy Fork 3452
END DESCRIPTION:
XS GIS Cut Line= 3
      2757115.48      6873431.85      2757339.43       6873998.4
      2757575.69      6874540.99
#Sta/Elev= 30
  4392.2  487.45  4407.3  487.84  4462.5  486.26  4509.6   485.2  4520.9   485.6
  4617.1  481.47    4648  478.74  4660.1  476.75  4760.2   465.1  4821.4  457.39
  4845.4   456.1  4894.1  455.18  4961.2  457.19  4977.9  453.01  4983.3  448.02
  4989.1  447.91  4990.4  447.41  4997.8  447.91  5000.1  448.21  5007.5  453.69
    5031  457.25  5101.6  455.98    5146  456.56  5229.3  460.32  5310.5  465.14
  5351.9  466.57  5409.7  470.79  5462.3  472.93  5532.3  474.07  5593.2  472.81
#Mann= 6 ,-1 , 0
  4392.2      .1       0  4462.5     .12       0  4760.2      .1       0
  4989.1     .07       0  4997.8      .1       0  5101.6     .05       0
Bank Sta=4989.1,4997.8
XS Rating Curve= 0 ,0
Exp/Cntr=0.3,0.1

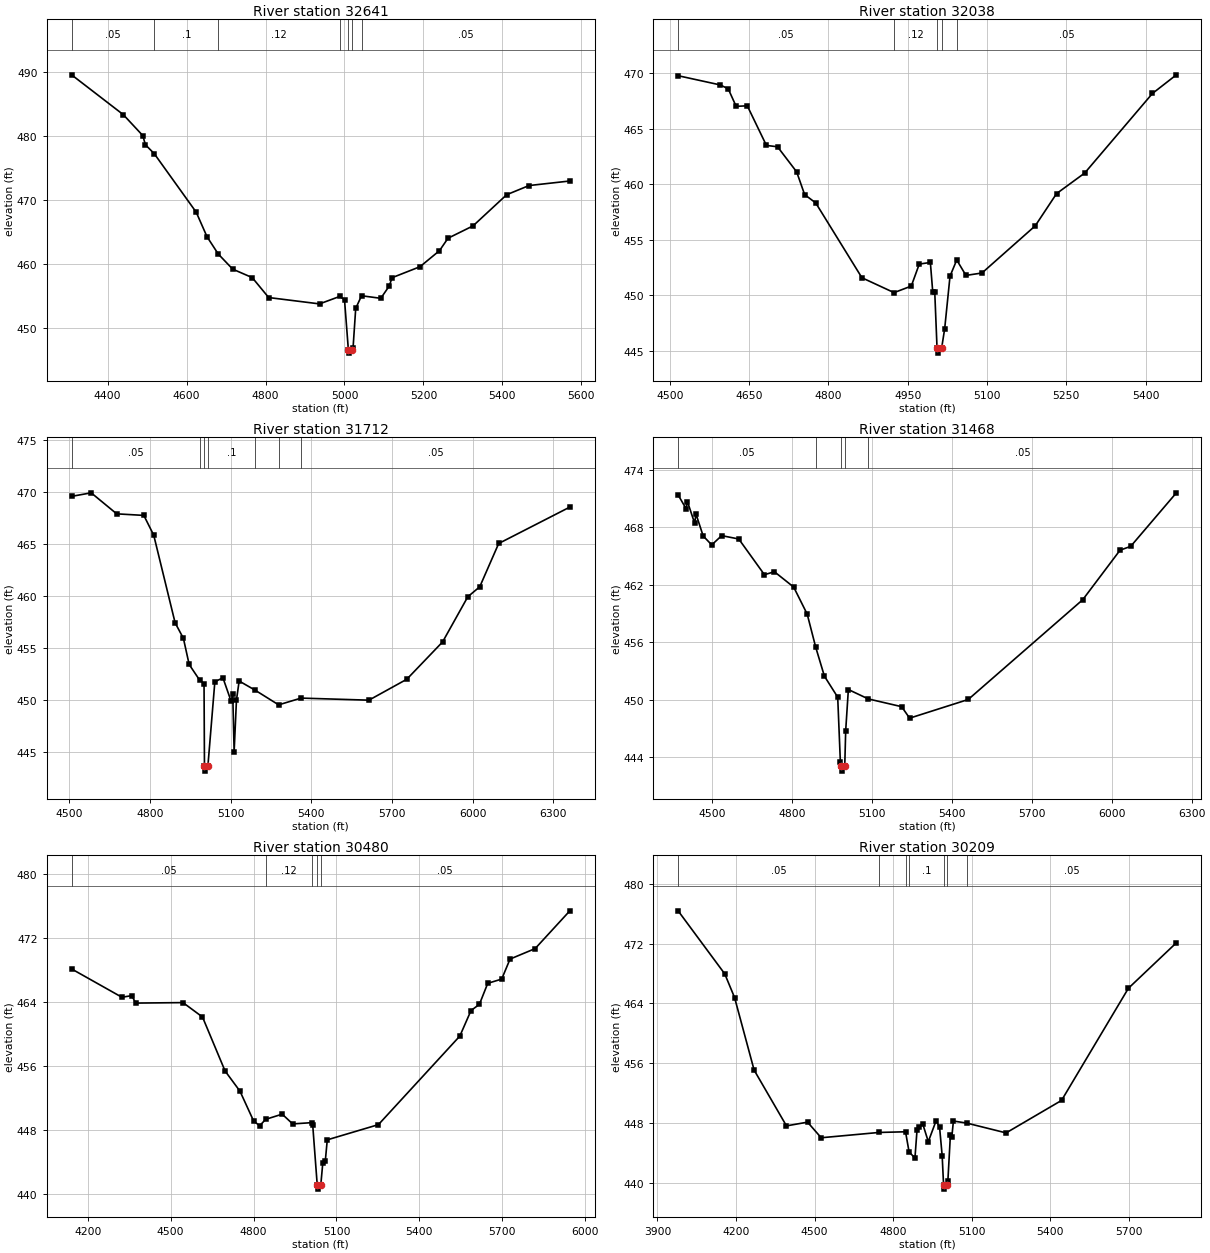
Type RM Length L Ch R = 1 ,32641   ,603,603,603
BEGIN DESCRIPTION:
Wet Lacy Fork 3451
END DESCRIPTION:
XS GIS Cut Line= 3
      2756595.34      6873817.48       2757031.7      6874340.73
      2757461.71      6874731.55
#Sta/Elev= 30
  4308.6  489.54  4439.6  483.33  4489.1  480.06  4495.6  478.64  4518.2  477.23
  4624.4  468.11  4651.8  464.28  4680.2  461.59  4716.8  459.23  4766.3  457.91
    4808   454.8  4936.8  453.81  4987.9  454.97  5000.1  454.47  5009.9  446.63
  5011.2  446.13  5018.7  446.63  5021.8  446.97  5028.5  453.11  5043.3  455.08
    5092  454.68  5113.7  456.62  5120.4  457.89  5191.4  459.61  5240.7  462.11
  5262.3  464.05  5325.8  465.98    5411  470.84  5467.7  472.27    5571  472.98
#Mann= 7 ,-1 , 0
  4308.6     .05       0  4518.2      .1       0  4680.2     .12       0
  4987.9      .1       0  5009.9     .07       0  5018.7      .1       0
  5043.3     .05       0
Bank Sta=5009.9,5018.7
XS Rating Curve= 0 ,0
Exp/Cntr=0.3,0.1

Type RM Length L Ch R = 1 ,32038   ,326,326,326
BEGIN DESCRIPTION:
Wet Lacy Fork 3245
END DESCRIPTION:
XS GIS Cut Line= 3
      2756471.62      6874604.07      2756877.35      6874870.94
      2757330.96      6874927.87
#Sta/Elev= 30
  4515.5  469.77  4595.2  468.94  4610.3  468.59  4625.3  467.01  4646.4  467.06
  4682.6  463.49  4703.6  463.37  4739.8  461.11  4754.9  459.06  4775.9  458.31
  4863.3  451.57  4924.1  450.23  4956.7  450.82  4971.8   452.8  4992.8  452.95
  4997.3   450.3  5001.1   450.3  5005.4  445.28  5006.7  444.78  5014.3  445.28
  5019.9  446.98    5030  451.71  5042.7  453.17  5060.2  451.78  5090.5     452
  5191.3  456.25  5231.6  459.15  5284.8     461    5413  468.17  5458.3  469.85
#Mann= 5 ,-1 , 0
  4515.5     .05       0  4924.1     .12       0  5005.4     .07       0
  5014.3     .12       0  5042.7     .05       0
Bank Sta=5005.4,5014.3
XS Rating Curve= 0 ,0
Exp/Cntr=0.3,0.1

Type RM Length L Ch R = 1 ,31712   ,244,244,244
BEGIN DESCRIPTION:
Wet Lacy Fork 3243
END DESCRIPTION:
XS GIS Cut Line= 3
      2756403.31      6874533.54      2756635.14      6874915.52
      2756779.99      6876314.21
#Sta/Elev= 30
    4508  469.55  4580.9  469.89  4675.8  467.87  4776.7  467.72  4813.5  465.82
    4893   457.4  4923.9   455.9  4945.3  453.39  4984.2  451.89  5000.6  451.56
  5002.2  443.64    5004  443.14    5015  443.64  5040.8  451.73  5070.9  452.11
  5101.1  449.87  5107.4  450.54  5112.5     445  5121.2  449.98  5131.2   451.8
  5190.6  450.92  5278.1  449.51  5361.4  450.16  5613.8  449.96  5754.6  451.97
  5887.8  455.56  5981.6   459.9    6026  460.86  6096.4  465.02    6361  468.52
#Mann= 7 ,-1 , 0
    4508     .05       0  4984.2      .1       0  5002.2     .07       0
    5015      .1       0  5190.6     .05       0  5278.1     .12       0
  5361.4     .05       0
Bank Sta=5002.2,5015
XS Rating Curve= 0 ,0
Exp/Cntr=0.3,0.1

Type RM Length L Ch R = 1 ,31468   ,988,988,988
BEGIN DESCRIPTION:
Wet Lacy Fork 3244
END DESCRIPTION:
XS GIS Cut Line= 3
      2756311.81      6874457.86      2756478.11      6874975.95
       2756488.6      6876302.48
#Sta/Elev= 30
    4372  471.39  4401.8  469.96  4407.1  470.69  4433.9  468.45  4439.2  469.39
    4466  467.11  4498.2  466.17  4535.5  467.14  4599.7  466.79  4696.1  463.06
  4733.5  463.37  4805.9  461.77  4856.7  458.94  4888.6  455.49  4921.2  452.47
  4971.2  450.27  4981.2   443.5  4984.8  443.05  4986.6  442.55  4997.6  443.05
  5001.2  446.79  5011.2  451.07    5086  450.09  5211.2  449.28  5241.2  448.08
  5461.2  450.03  5891.2  460.45  6031.2  465.62  6071.2  466.02  6242.7  471.61
#Mann= 5 ,-1 , 0
    4372     .05       0  4888.6      .1       0  4984.8     .07       0
  4997.6      .1       0    5086     .05       0
Bank Sta=4984.8,4997.6
XS Rating Curve= 0 ,0
Exp/Cntr=0.3,0.1

Type RM Length L Ch R = 1 ,30480   ,271,271,271
BEGIN DESCRIPTION:
Wet Lacy Fork 3240
END DESCRIPTION:
XS GIS Cut Line= 4
      2755551.42        6874701.      2755830.12      6875074.92
      2756183.85      6875721.43      2756262.74       6876315.4
#Sta/Elev= 30
  4141.8  468.11  4323.9  464.57  4359.4  464.77    4374  463.84  4544.9   463.9
  4615.4   462.1    4697  455.36    4751  452.83  4800.3  449.11  4822.2  448.51
  4843.8  449.31  4903.7  449.96  4941.6  448.74  5011.4   448.9  5014.1  448.62
  5030.5  441.09  5032.3  440.59  5043.3  441.09  5050.7   443.9  5059.7  444.12
  5066.8  446.75  5251.8  448.65  5546.4  459.72  5586.8  462.91  5617.1  463.68
  5647.3  466.31  5697.8  466.84    5728  469.34  5818.8  470.65  5944.3  475.37
#Mann= 5 ,-1 , 0
  4141.8     .05       0  4843.8     .12       0  5011.4     .05       0
  5030.5     .07       0  5043.3     .05       0
Bank Sta=5030.5,5043.3
XS Rating Curve= 0 ,0
Exp/Cntr=0.3,0.1

Type RM Length L Ch R = 1 ,30209   ,825,825,825
BEGIN DESCRIPTION:
Wet Lacy Fork 3239
END DESCRIPTION:
XS GIS Cut Line= 3
      2755284.13       6874657.8      2755791.65       6875537.5
      2756082.37      6876375.19
#Sta/Elev= 30
    3979  476.41  4157.2  467.96  4194.6  464.79  4269.2  455.08  4392.7  447.61
  4473.2  448.11  4525.3  446.02  4746.1  446.73  4847.3  446.82  4860.7  444.14
  4883.2  443.29  4891.1  447.03  4896.9  447.48  4912.7   447.9  4934.2   445.5
    4964   448.3  4977.3  447.41  4987.1  443.64  4992.6  439.64  4994.5  439.14
  5005.5  439.64  5008.9  440.23  5018.6   446.4  5023.9   446.1  5030.1  448.26
  5081.5  447.98  5231.2  446.67  5442.9  451.02  5698.2  466.04  5881.3  472.13
#Mann= 7 ,-1 , 0
    3979     .05       0  4746.1      .1       0  4847.3     .12       0
  4860.7      .1       0  4992.6     .07       0  5005.5      .1       0
  5081.5     .05       0
Bank Sta=4992.6,5005.5
XS Rating Curve= 0 ,0
Exp/Cntr=0.3,0.1

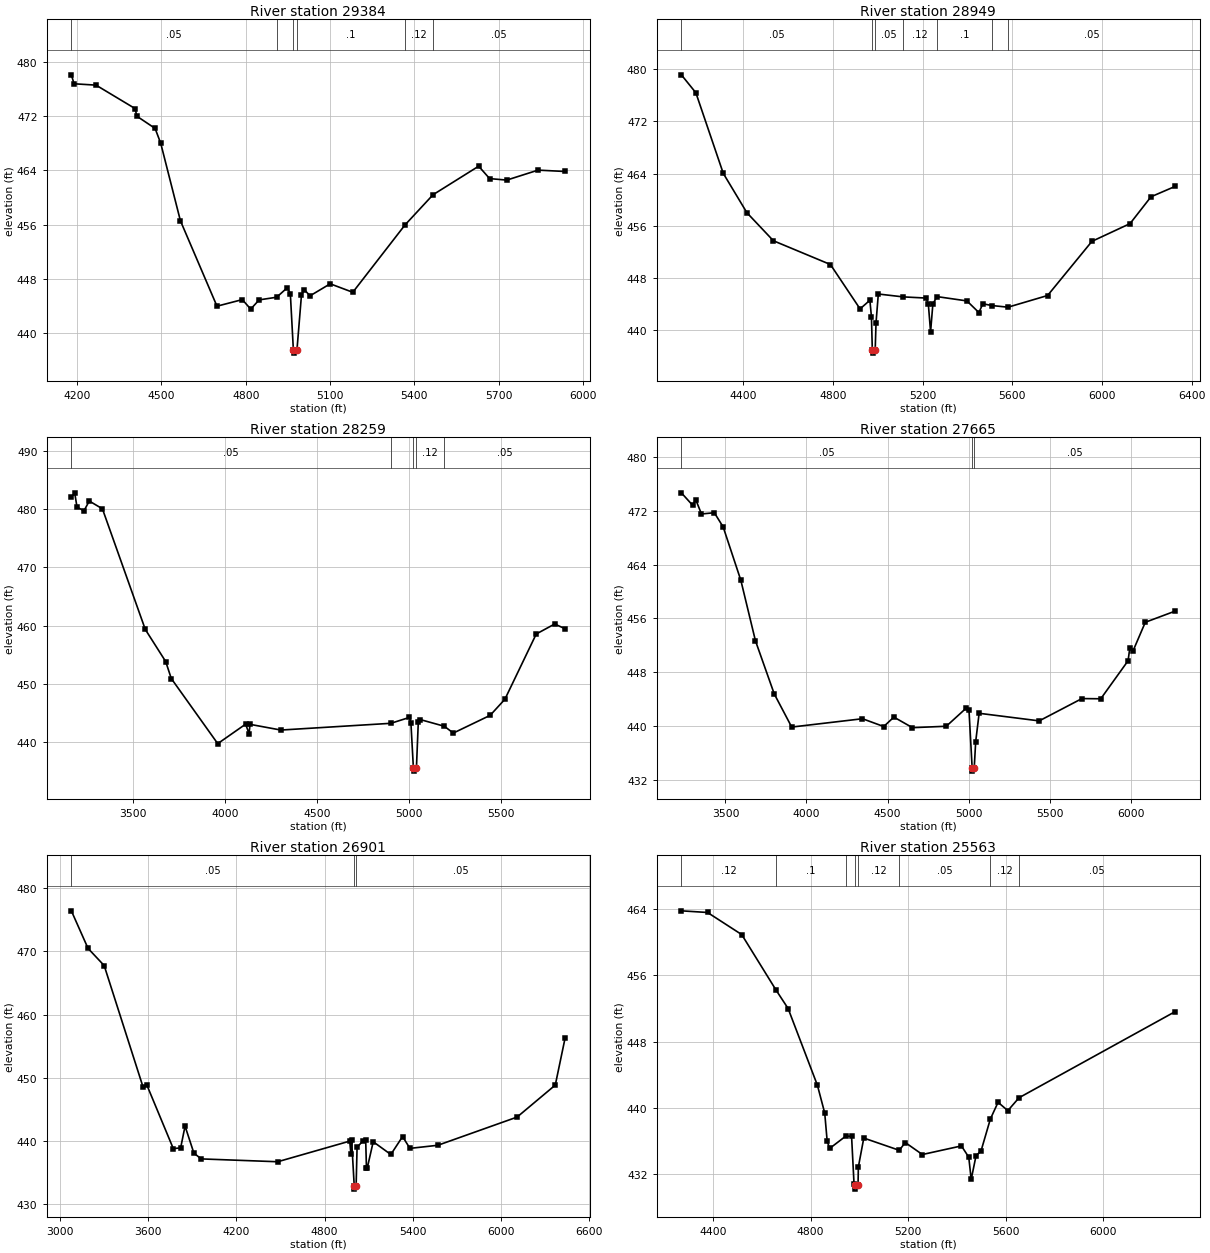
Type RM Length L Ch R = 1 ,29384   ,435,435,435
BEGIN DESCRIPTION:
Wet Lacy Fork 3242
END DESCRIPTION:
XS GIS Cut Line= 3
      2755221.28      6874523.14       2755186.9      6875297.93
      2755353.94      6876265.77
#Sta/Elev= 30
  4179.1  478.07  4188.7  476.75    4267  476.55  4406.6  473.08  4411.6  471.99
  4477.2  470.17  4497.3  467.97  4567.3  456.56  4697.5  443.96  4787.6  444.93
  4817.6  443.53  4847.6  444.89    4910  445.28  4947.7  446.68  4958.7   445.8
  4969.4  437.54  4971.2  437.04  4982.3  437.54  4998.4  445.66  5008.5  446.38
  5028.8  445.49  5100.6  447.26    5181  446.01  5366.9  455.94  5466.6  460.39
  5629.1   464.6  5668.1  462.77    5729  462.55  5840.6  464.02  5936.8  463.82
#Mann= 6 ,-1 , 0
  4179.1     .05       0    4910      .1       0  4969.4     .07       0
  4982.3      .1       0  5366.9     .12       0  5466.6     .05       0
Bank Sta=4969.4,4982.3
XS Rating Curve= 0 ,0
Exp/Cntr=0.3,0.1

Type RM Length L Ch R = 1 ,28949   ,690,690,690
BEGIN DESCRIPTION:
Wet Lacy Fork 3241
END DESCRIPTION:
XS GIS Cut Line= 3
      2755104.26      6874217.43      2754938.72      6875108.33
      2754728.93      6876387.09
#Sta/Elev= 30
  4124.2  479.13  4188.9  476.38  4311.1  464.03  4416.7  457.99  4534.7   453.7
    4789  450.06  4921.2  443.26    4965  444.58    4972  442.02  4975.8  436.98
  4977.6  436.48  4988.7  436.98  4992.4  441.14  5002.6  445.54  5112.9   445.1
  5215.5  444.92  5225.6  444.02  5235.7  439.73  5245.9  444.03  5264.6  445.14
  5397.9  444.48  5451.1   442.7  5468.8  444.04  5509.7  443.77    5581  443.52
  5757.5  445.31  5955.2  453.61  6125.3  456.33  6218.7  460.44  6326.2  462.03
#Mann= 7 ,-1 , 0
  4124.2     .05       0  4975.8     .04       0  4988.7     .05       0
  5112.9     .12       0  5264.6      .1       0  5509.7     .12       0
    5581     .05       0
Bank Sta=4975.8,4988.7
XS Rating Curve= 0 ,0
Exp/Cntr=0.3,0.1

Type RM Length L Ch R = 1 ,28259   ,594,594,594
BEGIN DESCRIPTION:
Wet Lacy Fork 3237
END DESCRIPTION:
XS GIS Cut Line= 3
      2754804.91      6873643.06      2754551.67      6875459.66
      2754600.64      6876307.68
#Sta/Elev= 30
  3165.3   482.1  3183.4  482.85  3196.1  480.39  3233.9  479.75  3262.6  481.44
  3334.1   480.1  3567.1  459.34  3678.1  453.81  3708.4  450.89  3960.9  439.68
  4112.3  443.03  4131.3  441.41  4136.4     443  4304.1  442.02  4901.7  443.18
  5002.6  444.19  5010.8  443.29  5024.4  435.45  5026.2  434.95  5037.3  435.45
  5040.9  435.54  5050.9  443.32  5060.9  443.83  5192.7  442.67  5241.2   441.5
  5441.5  444.55  5521.7  447.32    5692  458.55  5792.1  460.27  5848.9  459.46
#Mann= 5 ,-1 , 0
  3165.3     .05       0  4901.7     .12       0  5024.4     .07       0
  5037.3     .12       0  5192.7     .05       0
Bank Sta=5024.4,5037.3
XS Rating Curve= 0 ,0
Exp/Cntr=0.3,0.1

Type RM Length L Ch R = 1 ,27665   ,764,764,764
BEGIN DESCRIPTION:
Wet Lacy Fork 3238
END DESCRIPTION:
XS GIS Cut Line= 3
      2754744.26      6873506.56      2754109.28      6875152.44
      2754523.21      6876364.92
#Sta/Elev= 30
  3228.2  474.68  3297.7  472.83    3317  473.66  3352.3  471.53  3431.5  471.72
  3486.1   469.6  3595.2  461.65  3685.1  452.66    3801  444.75  3908.8  439.81
  4345.4  441.05  4476.3  439.89  4539.1  441.29  4653.6  439.72  4862.2  439.93
  4986.5  442.66  5002.1  442.39  5021.7  433.75  5023.5  433.25  5034.6  433.75
  5043.6  437.65  5064.8  441.86  5435.4  440.73  5698.8  444.05    5815  444.02
  5983.4  449.68  5994.6  451.65  6014.8  451.19  6089.7  455.41  6273.5  457.07
#Mann= 3 ,-1 , 0
  3228.2     .05       0  5021.7     .04       0  5034.6     .05       0
Bank Sta=5021.7,5034.6
XS Rating Curve= 0 ,0
Exp/Cntr=0.3,0.1

Type RM Length L Ch R = 1 ,26901   ,1338,1338,1338
BEGIN DESCRIPTION:
Wet Lacy Fork 3236
END DESCRIPTION:
XS GIS Cut Line= 3
      2753618.62      6873237.62      2753509.39      6875170.27
      2753540.73      6876597.89
#Sta/Elev= 30
  3075.3  476.44  3188.9  470.49    3299  467.76  3564.6  448.45  3589.5  448.84
  3769.8  438.75  3819.9  438.87  3849.9  442.32    3910  438.04  3960.1  437.12
  4480.9  436.67  4971.7  439.94  4979.6  437.97  4984.6   440.1  5002.4  432.83
  5004.2  432.33  5015.3  432.83  5021.8  438.95  5061.8  439.98  5080.6  440.05
  5085.6  435.75  5091.8  435.74  5131.8  439.84  5251.8  437.82  5331.8  440.66
  5381.9  438.79  5571.9  439.28    6112  443.75  6372.1  448.82    6439  456.28
#Mann= 3 ,-1 , 0
  3075.3     .05       0  5002.4     .04       0  5015.3     .05       0
Bank Sta=5002.4,5015.3
XS Rating Curve= 0 ,0
Exp/Cntr=0.3,0.1

Type RM Length L Ch R = 1 ,25563   ,341,341,341
BEGIN DESCRIPTION:
Wet Lacy Fork 3234
END DESCRIPTION:
XS GIS Cut Line= 3
      2752481.55      6874283.76      2752489.62      6875011.35
      2752509.62      6876306.16
#Sta/Elev= 30
  4270.9  463.81  4378.1  463.61  4518.2  460.94  4658.7  454.24  4708.2  452.01
  4828.2  442.74  4858.2  439.38  4868.2  435.99  4878.2   435.1  4944.7   436.6
  4968.2  436.56  4978.2  430.85  4981.6  430.69  4983.5  430.19  4994.7  430.69
  4995.9  432.85  5018.2  436.36  5163.7  434.88  5188.2  435.82  5258.2  434.37
  5418.2  435.41  5448.2  434.05  5458.2  431.36  5478.2  434.25  5498.2  434.77
  5536.6  438.65  5568.3  440.68  5608.3  439.67  5654.2  441.23  6293.5  451.63
#Mann= 8 ,-1 , 0
  4270.9     .12       0  4658.7      .1       0  4944.7     .12       0
  4981.6     .07       0  4994.7     .12       0  5163.7     .05       0
  5536.6     .12       0  5654.2     .05       0
Bank Sta=4981.6,4994.7
XS Rating Curve= 0 ,0
Exp/Cntr=0.3,0.1

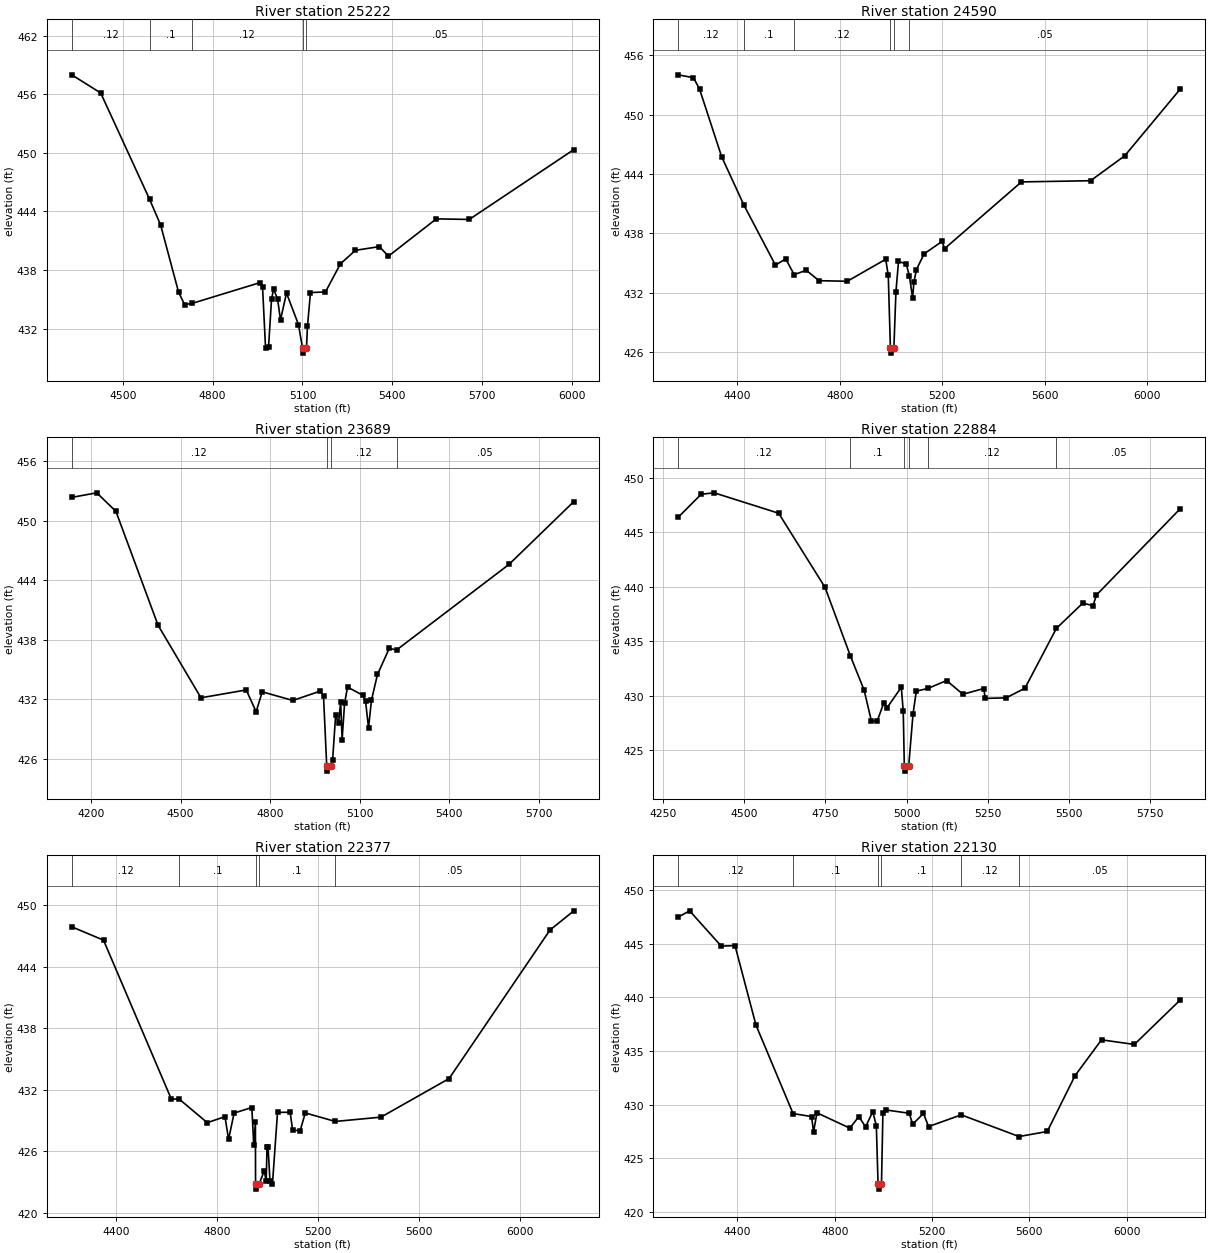
Type RM Length L Ch R = 1 ,25222   ,632,632,632
BEGIN DESCRIPTION:
Wet Lacy Fork 3233
END DESCRIPTION:
XS GIS Cut Line= 3
      2752272.96      6874564.49      2752252.96      6875239.41
      2752272.76        6876240.
#Sta/Elev= 30
    4330  457.98  4426.6  456.12  4589.8  445.24  4626.6  442.61  4686.7  435.72
  4706.7  434.47  4731.8  434.59  4956.8   436.7  4966.8  436.29  4976.8  430.07
  4986.8  430.08  4996.8  434.99  5003.5  436.06  5016.8  435.07  5026.8   432.9
  5046.8  435.65  5086.8  432.42  5100.3     430  5102.1   429.5  5113.4     430
  5116.8  432.24  5126.8   435.7  5176.8  435.76  5226.9  438.64  5276.9  440.02
  5356.9   440.4  5386.9  439.42  5546.9  443.24  5656.9  443.18    6006  450.33
#Mann= 5 ,-1 , 0
    4330     .12       0  4589.8      .1       0  4731.8     .12       0
  5100.3     .07       0  5113.4     .05       0
Bank Sta=5100.3,5113.4
XS Rating Curve= 0 ,0
Exp/Cntr=0.3,0.1

Type RM Length L Ch R = 1 ,24590   ,901,901,901
BEGIN DESCRIPTION:
Wet Lacy Fork 3235
END DESCRIPTION:
XS GIS Cut Line= 3
      2751815.14      6874531.75      2751772.93      6875366.34
      2751745.72      6876491.35
#Sta/Elev= 30
    4169  454.03  4228.3  453.74  4252.1   452.6  4338.5  445.76  4425.8  440.85
  4548.7   434.8  4588.8  435.44  4621.7  433.84  4668.9  434.28    4719  433.23
  4829.1  433.17  4979.3  435.39  4989.3  433.78  4997.7  426.41  4999.6  425.91
  5011.2  426.41  5019.3   432.1  5029.3  435.17  5059.3  434.93  5071.9   433.7
  5084.4  431.47  5089.4  433.06  5099.3  434.35  5129.4  435.94  5199.4   437.2
  5209.4  436.47  5509.5  443.21  5779.5  443.33    5913  445.85    6130   452.6
#Mann= 6 ,-1 , 0
    4169     .12       0  4425.8      .1       0  4621.7     .12       0
  4997.7     .07       0  5011.2     .12       0  5071.9     .05       0
Bank Sta=4997.7,5011.2
XS Rating Curve= 0 ,0
Exp/Cntr=0.3,0.1

Type RM Length L Ch R = 1 ,23689   ,805,805,805
BEGIN DESCRIPTION:
Wet Lacy Fork 3066
END DESCRIPTION:
XS GIS Cut Line= 3
      2751253.94      6874369.35      2751058.62      6875210.14
      2751108.04      6876027.77
#Sta/Elev= 30
  4135.5  452.36  4219.3  452.82  4283.6  450.94  4424.6  439.46  4568.4  432.14
  4720.1  432.93  4753.2  430.73  4773.7  432.74  4876.4  431.87  4968.8  432.82
    4979  432.32  4989.8  425.24  4991.7  424.74  5003.4  425.24  5009.6  425.91
  5019.6  430.36  5029.6   429.6  5036.4  431.74  5041.4  427.93  5049.6  431.59
  5059.6  433.22  5109.7  432.41  5119.8  431.81  5129.8  429.11  5139.8  431.91
  5159.8  434.49  5199.4  437.13  5223.7  436.96  5600.6   445.6  5817.8  451.94
#Mann= 4 ,-1 , 0
  4135.5     .12       0  4989.8     .07       0  5003.4     .12       0
  5223.7     .05       0
Bank Sta=4989.8,5003.4
XS Rating Curve= 0 ,0
Exp/Cntr=0.3,0.1

Type RM Length L Ch R = 1 ,22884   ,507,507,507
BEGIN DESCRIPTION:
Wet Lacy Fork 3065
END DESCRIPTION:
XS GIS Cut Line= 3
      2750494.36      6874510.72      2750413.41      6875264.69
      2750655.63      6876017.37
#Sta/Elev= 30
  4295.7  446.36  4366.4  448.47  4406.6   448.6  4605.5  446.73  4748.6  439.93
  4827.1  433.62  4869.3   430.5  4891.8  427.65  4909.5  427.67  4929.6  429.31
  4939.7  428.88  4983.9  430.77  4989.9  428.57  4993.2  423.58  4995.2  423.08
  5006.8  423.58  5020.1  428.34  5030.2  430.41  5066.7  430.67  5123.7  431.39
  5173.8  430.13    5238  430.65  5243.2  429.75  5307.4   429.8  5365.3  430.68
  5462.4  436.17  5543.9  438.49  5575.4  438.25  5585.9  439.23  5844.7  447.15
#Mann= 6 ,-1 , 0
  4295.7     .12       0  4827.1      .1       0  4993.2     .07       0
  5006.8      .1       0  5066.7     .12       0  5462.4     .05       0
Bank Sta=4993.2,5006.8
XS Rating Curve= 0 ,0
Exp/Cntr=0.3,0.1

Type RM Length L Ch R = 1 ,22377   ,247,247,247
BEGIN DESCRIPTION:
Wet Lacy Fork 3063
END DESCRIPTION:
XS GIS Cut Line= 3
      2750465.26      6874622.97      2749959.04      6875210.85
      2749916.51      6876425.51
#Sta/Elev= 30
  4223.8  447.91  4349.7  446.61  4618.6  431.11  4649.3  431.12  4761.2  428.81
  4831.4   429.4  4845.7  427.18  4867.6  429.75  4937.9  430.29  4945.5  426.64
  4952.1  428.86  4952.7  422.83  4954.7  422.33  4966.8  422.83  4987.2  424.11
  4994.9  423.08  4998.1  426.45  5002.2  426.45  5009.8  423.16  5019.8  422.86
  5039.8  429.81  5089.8  429.83  5099.8  428.07  5129.8  428.04  5149.8  429.76
    5269  428.93    5450  429.35  5720.2  433.11  6120.4   447.6    6215  449.47
#Mann= 5 ,-1 , 0
  4223.8     .12       0  4649.3      .1       0  4952.7     .07       0
  4966.8      .1       0    5269     .05       0
Bank Sta=4952.7,4966.8
XS Rating Curve= 0 ,0
Exp/Cntr=0.3,0.1

Type RM Length L Ch R = 1 ,22130   ,1036,1036,1036
BEGIN DESCRIPTION:
Wet Lacy Fork 3064
END DESCRIPTION:
XS GIS Cut Line= 3
      2750490.15      6874549.55      2749720.67      6875099.89
      2749077.83      6876015.66
#Sta/Elev= 30
  4156.3  447.47  4203.1  448.05  4333.3  444.76  4389.8  444.81  4475.9  437.41
  4628.6  429.16  4704.4  428.88    4713  427.48  4726.9  429.23  4862.2   427.8
  4899.1  428.88  4926.8  427.92  4956.3  429.34    4971  428.04  4978.1  422.62
  4980.1  422.12  4992.2  422.62    4998  429.17  5012.8  429.49  5106.1  429.19
  5120.6  428.17  5164.8  429.17  5185.9  427.95  5320.3  429.04    5558  427.02
    5674  427.49  5787.9  432.68  5897.1  436.03  6032.2   435.6  6221.2  439.75
#Mann= 6 ,-1 , 0
  4156.3     .12       0  4628.6      .1       0  4978.1     .07       0
  4992.2      .1       0  5320.3     .12       0    5558     .05       0
Bank Sta=4978.1,4992.2
XS Rating Curve= 0 ,0
Exp/Cntr=0.3,0.1

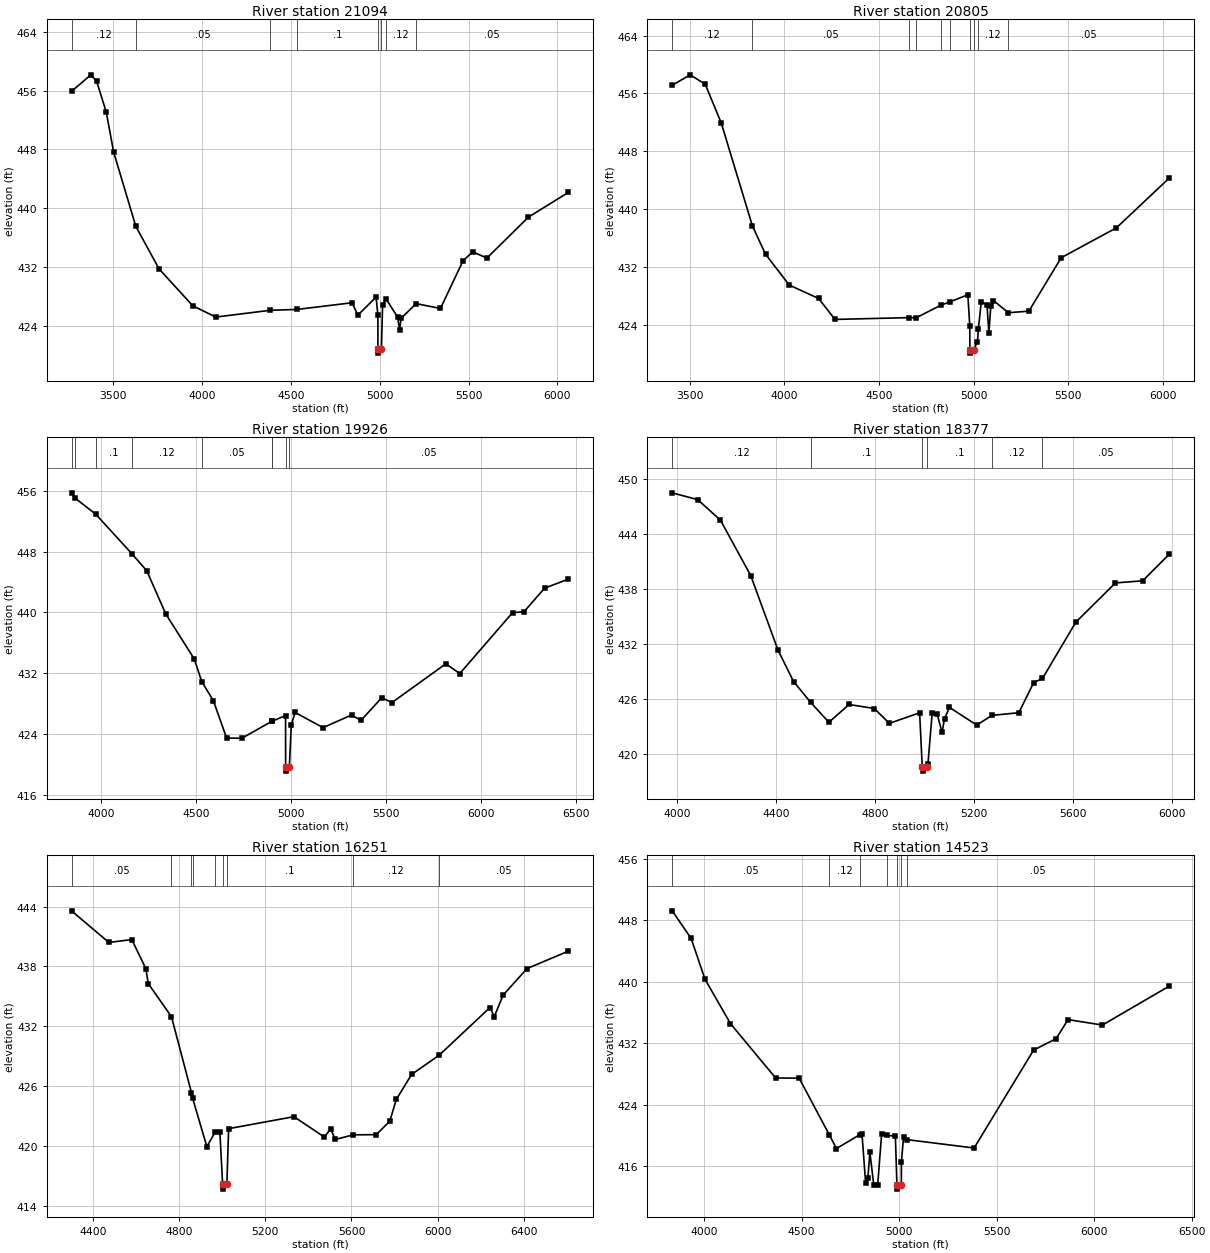
Type RM Length L Ch R = 1 ,21094   ,289,289,289
BEGIN DESCRIPTION:
Wet Lacy Fork 3062
END DESCRIPTION:
XS GIS Cut Line= 3
      2748595.33       6873428.4      2749162.29      6874977.32
      2749035.78      6876115.99
#Sta/Elev= 30
  3266.6   455.9  3375.9  458.15  3407.8  457.28    3462  453.08  3503.6  447.64
  3628.5  437.51  3759.2  431.73  3948.9   426.7  4078.7  425.17  4384.4  426.09
  4536.1  426.21  4845.4  427.12  4877.3  425.42  4980.1  427.89  4990.2  425.44
  4990.5  420.76  4992.5  420.26    5010  420.76  5016.8  426.88  5036.7  427.62
  5100.8  425.18  5112.4  423.45    5121     425  5205.4     427  5342.3  426.34
  5469.6  432.85  5523.4  434.04  5603.9  433.21  5836.8  438.77  6061.7  442.14
#Mann= 8 ,-1 , 0
  3266.6     .12       0  3628.5     .05       0  4384.4     .12       0
  4536.1      .1       0  4990.5     .07       0    5010      .1       0
  5036.7     .12       0  5205.4     .05       0
Bank Sta=4990.5,5010
XS Rating Curve= 0 ,0
Exp/Cntr=0.3,0.1

Type RM Length L Ch R = 1 ,20805   ,879,879,879
BEGIN DESCRIPTION:
Wet Lacy Fork 3046
END DESCRIPTION:
XS GIS Cut Line= 3
      2748552.25      6873408.07      2748901.22      6874959.54
      2748800.63       6875987.8
#Sta/Elev= 30
  3407.9  457.14  3503.2  458.58  3582.2  457.28  3667.1   451.9  3831.3  437.69
  3900.6  433.78  4025.9  429.51  4180.8  427.66  4267.4  424.76  4660.7  425.01
  4694.7  424.97  4826.8  426.73  4874.9  427.19  4968.9  428.17  4979.1  423.86
  4979.6   420.6  4981.6   420.1  4999.1   420.6  5019.7  421.63  5024.3  423.41
  5039.8  427.21  5069.9  426.78    5080  422.92    5090  426.58  5104.1  427.37
  5182.8  425.69    5291   425.9  5461.8  433.29  5753.2  437.42  6031.3  444.28
#Mann= 10 ,-1 , 0
  3407.9     .12       0  3831.3     .05       0  4660.7     .12       0
  4694.7      .1       0  4826.8     .12       0  4874.9      .1       0
  4979.6     .07       0  4999.1      .1       0  5024.3     .12       0
  5182.8     .05       0
Bank Sta=4979.6,4999.1
XS Rating Curve= 0 ,0
Exp/Cntr=0.3,0.1

Type RM Length L Ch R = 1 ,19926   ,1549,1549,1549
BEGIN DESCRIPTION:
Wet Lacy Fork 3047
END DESCRIPTION:
XS GIS Cut Line= 3
      2748260.52       6873455.6      2748241.07      6874674.77
      2748745.78      6875972.99
#Sta/Elev= 30
  3845.3  455.73  3866.2  454.99  3972.3  452.93  4165.3  447.65  4240.7  445.49
  4340.8  439.81  4490.8  433.88  4529.9  430.92  4590.8  428.42  4660.8  423.49
  4740.8  423.46  4898.4  425.69  4900.3   425.7  4970.8  426.45    4971  419.64
    4973  419.14  4990.6  419.64  5000.8  425.23  5020.8  426.85  5167.9  424.86
  5318.1  426.52  5367.2  425.81    5476  428.78  5530.4  428.16  5813.3  433.25
  5886.7  431.97  6164.3  439.98  6224.1  440.09  6332.9   443.2  6457.5  444.38
#Mann= 9 ,-1 , 0
  3845.3      .1       0  3866.2     .12       0  3972.3      .1       0
  4165.3     .12       0  4529.9     .05       0  4898.4     .12       0
  4900.3     .05       0    4971     .04       0  4990.6     .05       0
Bank Sta=4971,4990.6
XS Rating Curve= 0 ,0
Exp/Cntr=0.3,0.1

Type RM Length L Ch R = 1 ,18377   ,2126,2126,2126
BEGIN DESCRIPTION:
Wet Lacy Fork 3037
END DESCRIPTION:
XS GIS Cut Line= 3
       2747198.7      6873709.48      2747396.28      6874723.91
      2747352.71      6875697.55
#Sta/Elev= 30
  3979.8  448.51  4083.2  447.76  4174.9  445.52  4297.2  439.47  4407.2  431.34
  4470.4  427.89  4539.1  425.63    4613  423.44  4694.5  425.39  4796.4  424.95
  4857.5  423.33  4979.8  424.48  4990.3  418.61  4992.3  418.11    5010  418.61
  5013.3  418.85  5030.4  424.42  5050.4  424.38  5070.4  422.33  5080.4  423.83
  5100.5  425.07  5210.6  423.14  5272.1   424.2  5380.7  424.49  5440.8  427.78
  5476.3  428.23    5611  434.38  5771.1  438.67  5881.2   438.9  5987.9  441.78
#Mann= 6 ,-1 , 0
  3979.8     .12       0  4539.1      .1       0  4990.3     .07       0
    5010      .1       0  5272.1     .12       0  5476.3     .05       0
Bank Sta=4990.3,5010
XS Rating Curve= 0 ,0
Exp/Cntr=0.3,0.1

Type RM Length L Ch R = 1 ,16251   ,1728,1728,1728
BEGIN DESCRIPTION:
Wet Lacy Fork 2943
END DESCRIPTION:
XS GIS Cut Line= 3
        2746330.      6873269.28       2746230.9       6873973.5
      2746005.16      6875550.97
#Sta/Elev= 30
  4301.3  443.57  4474.7   440.4    4581  440.69  4646.4  437.76  4657.2  436.28
  4764.8  432.97  4857.9  425.34  4862.9   424.8  4929.1  419.94  4968.2  421.41
  4989.7  421.36  5002.2  416.18  5004.2  415.68    5022  416.18  5030.1  421.74
  5333.2  422.94  5474.6  420.89  5502.9  421.73  5525.1  420.66  5608.4  421.12
  5714.8  421.14  5777.7  422.49    5808  424.67  5878.7  427.17  6006.8   429.1
  6242.4  433.88  6262.6  432.97    6303  435.11  6414.1  437.78    6606  439.53
#Mann= 9 ,-1 , 0
  4301.3     .05       0  4764.8     .12       0  4857.9     .05       0
  4862.9     .12       0  4968.2      .1       0  5002.2     .07       0
    5022      .1       0  5608.4     .12       0  6006.8     .05       0
Bank Sta=5002.2,5022
XS Rating Curve= 0 ,0
Exp/Cntr=0.3,0.1

Type RM Length L Ch R = 1 ,14523   ,625,625,625
BEGIN DESCRIPTION:
Wet Lacy Fork 2904
END DESCRIPTION:
XS GIS Cut Line= 3
      2744979.61      6872704.18      2745110.29      6873864.61
        2745751.        6875086.
#Sta/Elev= 30
  3837.1  449.25  3934.2  445.65    4005  440.34  4135.8  434.54  4367.2  427.46
    4488  427.43    4642  420.07  4679.2  418.26  4799.3  420.08    4810  420.16
  4828.8  413.71  4840.2  414.41  4850.3  417.77  4870.4   413.5  4890.5  413.54
  4910.7  420.16  4938.3  419.99  4981.1  419.87  4989.2  413.47  4991.5  412.97
  5011.8  413.47  5012.1   416.5  5022.8  419.74  5041.4  419.42  5384.7  418.33
  5689.6  431.09  5805.5  432.59  5866.1  435.07  6042.5  434.36  6384.1  439.42
#Mann= 7 ,-1 , 0
  3837.1     .05       0    4642     .12       0  4799.3      .1       0
  4938.3     .12       0  4989.2     .07       0  5011.8     .12       0
  5041.4     .05       0
Bank Sta=4989.2,5011.8
XS Rating Curve= 0 ,0
Exp/Cntr=0.3,0.1