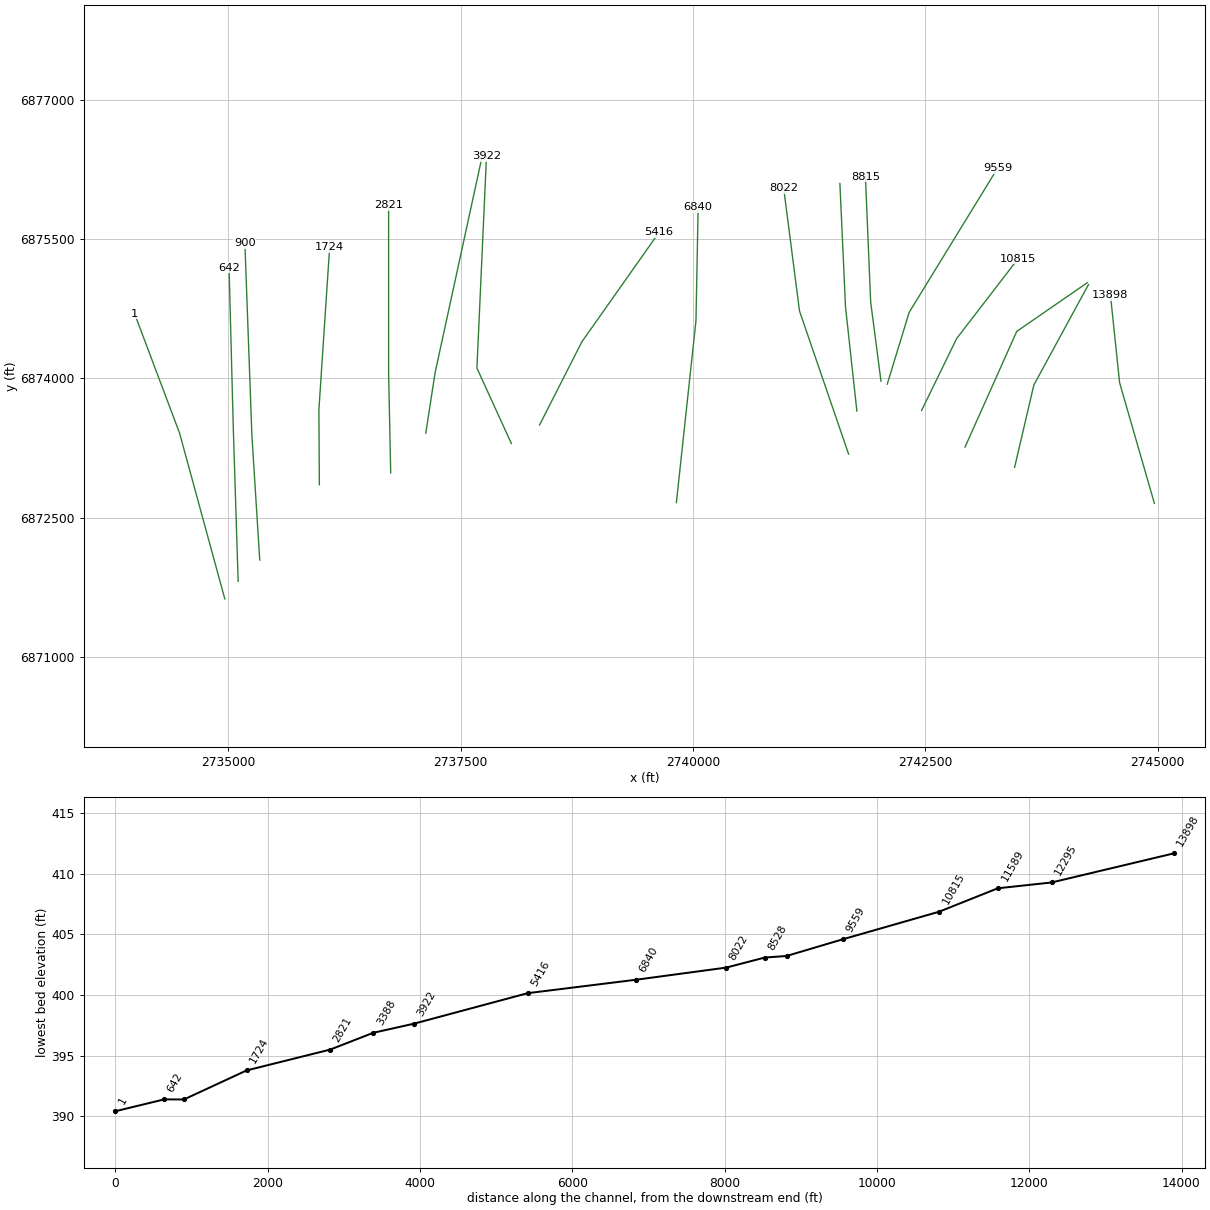
HEC-RAS study Wet Lacy Fork.prj: Wet Lacy Fork Base Level Engineering

--- Wet Lacy Fork.g01 (geometry) --- (continued)

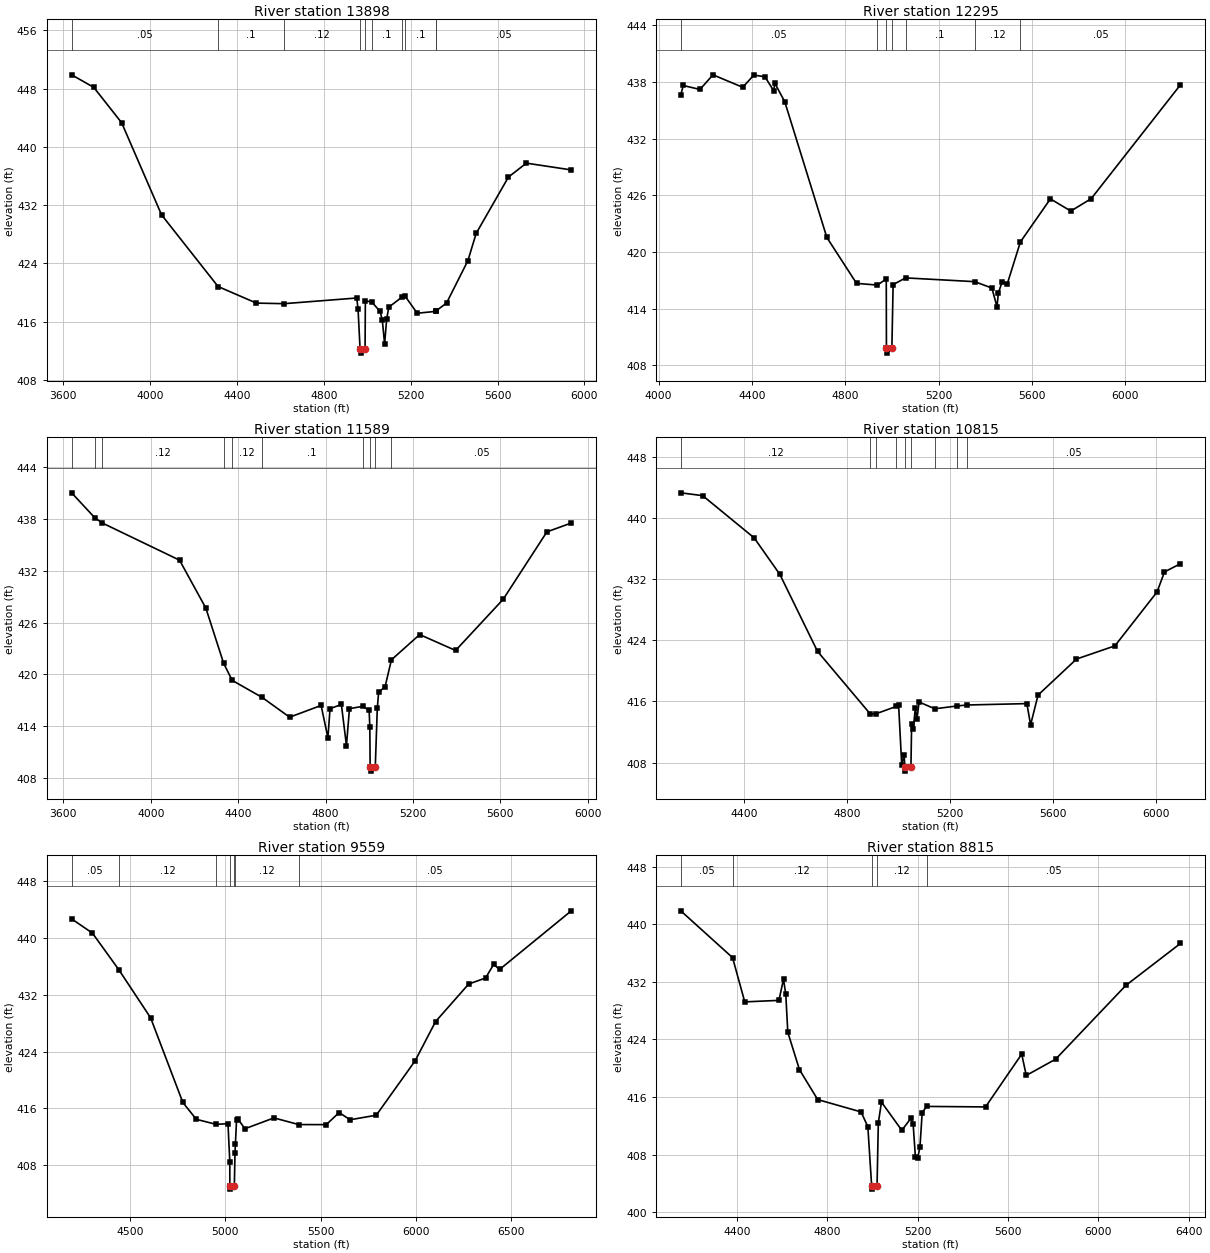
Type RM Length L Ch R = 1 ,13898   ,1603,1603,1603
BEGIN DESCRIPTION:
Wet Lacy Fork 2903
END DESCRIPTION:
XS GIS Cut Line= 3
      2744964.32      6872653.22      2744589.73      6873953.44
      2744491.24      6874897.01
#Sta/Elev= 30
    3638  449.91  3739.8  448.19  3868.3  443.33  4052.2  430.68  4312.4  420.84
    4489  418.56  4615.9  418.48  4951.3  419.26  4957.3  417.78  4966.8  412.19
  4969.1  411.69  4989.6  412.19  4991.1  418.86  5019.8  418.74    5059  417.41
  5069.1  416.23  5079.7  412.94  5089.2  416.38  5099.2  418.01  5160.1  419.39
  5174.5   419.5    5230  417.17  5314.4  417.42  5318.4  417.53  5364.9  418.56
  5463.4  424.39  5501.4  428.13  5650.2  435.87  5732.7  437.78  5939.8  436.85
#Mann= 10 ,-1 , 0
    3638     .05       0  4312.4      .1       0  4615.9     .12       0
  4966.8     .07       0  4989.6     .12       0  5019.8      .1       0
  5160.1     .12       0  5174.5      .1       0  5314.4     .12       0
  5318.4     .05       0
Bank Sta=4966.8,4989.6
XS Rating Curve= 0 ,0
Exp/Cntr=0.3,0.1

Type RM Length L Ch R = 1 ,12295   ,706,706,706
BEGIN DESCRIPTION:
Wet Lacy Fork 2902
END DESCRIPTION:
XS GIS Cut Line= 3
       2743459.7      6873041.01      2743667.38      6873929.18
      2744254.95      6875010.07
#Sta/Elev= 30
  4094.8  436.64  4105.4  437.64  4176.9  437.22  4232.9  438.77  4360.4  437.45
    4408  438.74  4455.6  438.57    4493  437.09  4498.1  437.87  4540.6  435.93
  4721.2  421.54  4848.4  416.68  4937.8   416.5  4975.9  417.14  4976.6  409.79
    4979  409.29  4999.9  409.79  5005.3  416.55  5058.8  417.26  5355.6  416.86
  5428.9  416.18  5450.7  414.19  5456.4  415.64  5472.6  416.84  5494.4   416.6
    5551  421.07  5679.7  425.63  5767.1  424.34  5854.5  425.65  6237.2  437.71
#Mann= 7 ,-1 , 0
  4094.8     .05       0  4937.8     .12       0  4976.6     .07       0
  4999.9     .12       0  5058.8      .1       0  5355.6     .12       0
    5551     .05       0
Bank Sta=4976.6,4999.9
XS Rating Curve= 0 ,0
Exp/Cntr=0.3,0.1

Type RM Length L Ch R = 1 ,11589   ,774,774,774
BEGIN DESCRIPTION:
Wet Lacy Fork 2870
END DESCRIPTION:
XS GIS Cut Line= 3
      2742926.78      6873260.25      2743483.62      6874506.14
      2744242.39      6875029.98
#Sta/Elev= 30
  3637.7  441.01  3742.7  438.15  3777.1  437.53  4131.4  433.22  4251.9  427.67
  4333.2  421.29  4372.4  419.31  4508.8  417.35  4635.3  415.05  4779.3  416.41
  4810.5  412.67  4820.2  416.04  4872.1  416.52  4895.3  411.77  4909.1  416.04
  4968.8   416.3  4999.1  415.85  5002.3  413.91  5003.7  409.31  5006.1  408.81
  5027.3  409.31  5036.5   416.1  5042.6  417.92  5072.3   418.6  5101.2  421.69
  5230.5  424.61  5394.8  422.77  5612.5  428.69  5812.6  436.49  5924.4  437.52
#Mann= 10 ,-1 , 0
  3637.7     .12       0  3742.7      .1       0  3777.1     .12       0
  4333.2     .05       0  4372.4     .12       0  4508.8      .1       0
  4968.8     .12       0  5003.7     .07       0  5027.3     .12       0
  5101.2     .05       0
Bank Sta=5003.7,5027.3
XS Rating Curve= 0 ,0
Exp/Cntr=0.3,0.1

Type RM Length L Ch R = 1 ,10815   ,1256,1256,1256
BEGIN DESCRIPTION:
Wet Lacy Fork 2869
END DESCRIPTION:
XS GIS Cut Line= 3
      2742459.46      6873654.32      2742836.81      6874428.76
      2743497.18      6875287.41
#Sta/Elev= 30
  4152.2  443.35  4237.5  442.98  4437.7  437.45  4537.8  432.66  4684.4  422.57
    4890  414.35  4912.1  414.39  4991.7  415.36    5000  415.57  5012.1  407.71
  5021.7  408.96  5024.3  407.37  5026.7  406.87    5048  407.37  5050.7  413.04
    5057  412.41  5065.2  415.14  5071.5  413.69  5079.6  415.93  5140.9  415.04
  5227.5  415.41  5266.7  415.54  5499.2  415.72  5513.7  412.94  5542.8  416.84
  5692.3  421.56  5841.8  423.29  6005.8  430.35  6034.8  432.98  6096.9  434.06
#Mann= 9 ,-1 , 0
  4152.2     .12       0    4890      .1       0  4912.1     .12       0
  4991.7      .1       0  5024.3     .07       0    5048      .1       0
  5140.9     .05       0  5227.5      .1       0  5266.7     .05       0
Bank Sta=5024.3,5048
XS Rating Curve= 0 ,0
Exp/Cntr=0.3,0.1

Type RM Length L Ch R = 1 ,9559    ,744,744,744
BEGIN DESCRIPTION:
Wet Lacy Fork 17
END DESCRIPTION:
XS GIS Cut Line= 3
      2742090.17      6873938.14        2742326.        6874711.
        2743276.      6876260.99
#Sta/Elev= 30
  4191.8   442.7    4301   440.7  4439.7  435.54  4606.8  428.76  4776.1  416.83
    4847  414.45  4951.5  413.74  5013.4  413.84    5023  408.48  5023.2  405.11
  5025.5  404.61  5046.9  405.11  5050.2  409.71  5052.4  410.95  5058.5  414.39
  5065.6   414.5  5102.3  413.12  5255.1  414.65  5385.4  413.71  5529.8   413.7
  5597.4   415.4  5655.4  414.39  5792.8  415.03  5996.8  422.69  6104.2  428.22
  6278.3  433.52  6367.2  434.37  6409.8   436.3  6440.6  435.57  6817.8  443.84
#Mann= 7 ,-1 , 0
  4191.8     .05       0  4439.7     .12       0  4951.5      .1       0
  5023.2     .07       0  5046.9      .1       0  5052.4     .12       0
  5385.4     .05       0
Bank Sta=5023.2,5046.9
XS Rating Curve= 0 ,0
Exp/Cntr=0.3,0.1

Type RM Length L Ch R = 1 ,8815    ,287,287,287
BEGIN DESCRIPTION:
Wet Lacy Fork 2868
END DESCRIPTION:
XS GIS Cut Line= 3
      2742022.62      6873970.31      2741911.63      6874823.14
      2741855.55      6876172.55
#Sta/Elev= 30
  4152.2  441.85  4381.4  435.35  4435.3  429.21  4586.5  429.42  4606.7  432.35
  4616.8  430.28  4625.7     425  4677.3   419.8    4758  415.65  4949.6  413.94
  4979.8   411.9  4996.6  403.72    4999  403.22  5020.6  403.72  5026.2   412.4
  5040.1   415.3  5130.2  411.38  5170.2  413.05  5180.2  412.28  5190.2  407.71
  5200.2  407.53  5210.3  409.03  5220.3  413.85    5240   414.7  5500.5  414.63
  5660.6  421.96  5680.7     419  5810.8  421.26    6121  431.49  6362.8  437.32
#Mann= 5 ,-1 , 0
  4152.2     .05       0  4381.4     .12       0  4996.6     .07       0
  5020.6     .12       0    5240     .05       0
Bank Sta=4996.6,5020.6
XS Rating Curve= 0 ,0
Exp/Cntr=0.3,0.1

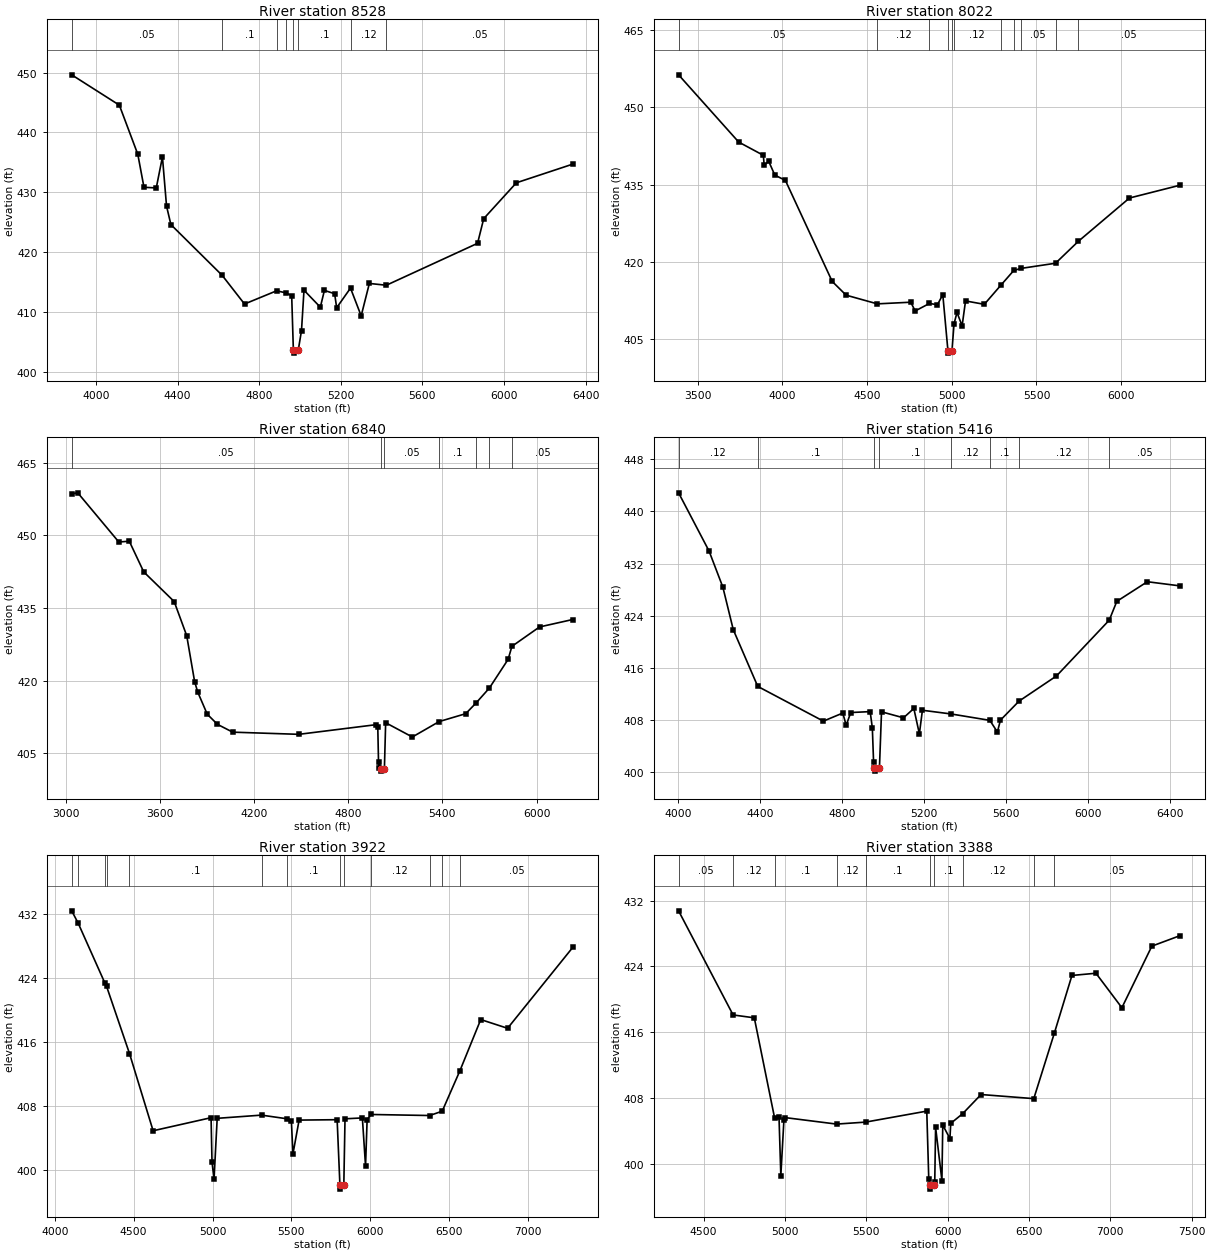
Type RM Length L Ch R = 1 ,8528    ,506,506,506
BEGIN DESCRIPTION:
Wet Lacy Fork 2866
END DESCRIPTION:
XS GIS Cut Line= 3
       2741763.2       6873648.9      2741640.99      6874771.65
      2741580.75       6876097.2
#Sta/Elev= 30
  3881.1  449.62  4114.6  444.55  4205.1  436.33  4235.3  430.82  4295.6  430.71
  4325.8  435.89  4345.9  427.68  4367.3  424.58  4618.8  416.09  4728.2   411.3
  4885.5  413.51  4933.7  413.15  4959.5  412.67  4967.7  403.59  4970.1  403.09
  4991.7  403.59  5007.6  406.87  5019.8  413.61  5099.9  410.77  5119.9  413.58
    5170  413.02    5180  410.68  5247.8  413.96  5300.1  409.32  5340.2  414.74
  5423.4  414.44  5870.7  421.45  5900.8  425.57  6060.9  431.57  6337.4  434.69
#Mann= 8 ,-1 , 0
  3881.1     .05       0  4618.8      .1       0  4885.5     .12       0
  4933.7      .1       0  4967.7     .07       0  4991.7      .1       0
  5247.8     .12       0  5423.4     .05       0
Bank Sta=4967.7,4991.7
XS Rating Curve= 0 ,0
Exp/Cntr=0.3,0.1

Type RM Length L Ch R = 1 ,8022    ,1182,1182,1182
BEGIN DESCRIPTION:
Wet Lacy Fork 2867
END DESCRIPTION:
XS GIS Cut Line= 3
      2741674.09       6873185.3      2741146.05      6874726.06
      2740976.28      6876044.64
#Sta/Elev= 30
    3387  456.32  3741.9  443.26  3887.3  440.69  3892.6  438.71  3918.6  439.56
  3955.2  436.84  4017.7  435.81  4293.9  416.19  4376.1  413.52  4560.3  411.83
  4757.8  412.15  4783.8  410.45  4868.3  411.91  4915.2  411.66    4947  413.62
  4977.2  402.76  4979.6  402.26  5001.3  402.76  5013.2  407.94  5030.8  410.16
    5061  407.56  5081.2   412.4  5192.1  411.74  5288.4   415.4  5366.4  418.33
  5409.3  418.72  5612.4  419.72  5747.6  423.99  6049.1  432.39  6345.2  434.86
#Mann= 11 ,-1 , 0
    3387     .05       0  4560.3     .12       0  4868.3      .1       0
  4977.2     .07       0  5001.3      .1       0  5013.2     .12       0
  5288.4      .1       0  5366.4     .12       0  5409.3     .05       0
  5612.4     .12       0  5747.6     .05       0
Bank Sta=4977.2,5001.3
XS Rating Curve= 0 ,0
Exp/Cntr=0.3,0.1

Type RM Length L Ch R = 1 ,6840    ,1424,1424,1424
BEGIN DESCRIPTION:
Wet Lacy Fork 2865
END DESCRIPTION:
XS GIS Cut Line= 3
      2739821.58      6872662.68      2740032.49      6874620.71
      2740055.84      6875842.63
#Sta/Elev= 30
  3039.4  458.62  3077.9  458.82  3339.4  448.65  3406.2  448.81  3498.1  442.47
  3692.1  436.33  3771.9  429.27  3822.2  419.78  3842.3  417.59  3902.7  413.03
  3967.9  410.93  4064.9  409.32    4486  408.87  4978.9  410.87  4988.9  410.45
  4994.4  401.97  4999.4  403.17  5006.9  401.76  5009.4  401.26  5031.1  401.76
  5039.1  411.27  5209.1  408.32  5379.8  411.51  5549.1  413.14  5616.2   415.4
  5699.7  418.44  5819.2  424.38  5843.3  427.07  6019.2  431.08  6230.9  432.62
#Mann= 7 ,-1 , 0
  3039.4     .05       0  5006.9     .04       0  5031.1     .05       0
  5379.8      .1       0  5616.2     .05       0  5699.7     .12       0
  5843.3     .05       0
Bank Sta=5006.9,5031.1
XS Rating Curve= 0 ,0
Exp/Cntr=0.3,0.1

Type RM Length L Ch R = 1 ,5416    ,1494,1494,1494
BEGIN DESCRIPTION:
Wet Lacy Fork 1983
END DESCRIPTION:
XS GIS Cut Line= 3
      2738349.93      6873498.35      2738804.15      6874392.33
      2739634.59      6875570.64
#Sta/Elev= 30
  4004.2  442.85    4153  433.91  4220.3  428.37  4271.1  421.84  4390.4  413.15
  4710.6  407.82  4805.2  409.06  4821.9  407.18  4844.1  409.14  4938.8  409.28
  4949.4   406.8  4955.4  401.62  4959.6  400.65    4962  400.15  4984.1  400.65
  4994.2  409.25  5101.4  408.33  5151.9  409.76  5178.9  405.87  5193.7  409.49
  5333.7  408.92  5522.7  407.94  5559.5  406.15  5574.3  407.97  5665.1  410.89
  5847.7  414.75  6105.1  423.31  6142.1   426.2    6291  429.21  6448.5  428.58
#Mann= 8 ,-1 , 0
  4004.2     .12       0  4390.4      .1       0  4959.6     .07       0
  4984.1      .1       0  5333.7     .12       0  5522.7      .1       0
  5665.1     .12       0  6105.1     .05       0
Bank Sta=4959.6,4984.1
XS Rating Curve= 0 ,0
Exp/Cntr=0.3,0.1

Type RM Length L Ch R = 1 ,3922    ,534,534,534
BEGIN DESCRIPTION:
Wet Lacy Fork 16
END DESCRIPTION:
XS GIS Cut Line= 3
      2738046.47      6873298.84        2737676.        6874111.
      2737779.19       6876394.1
#Sta/Elev= 30
    4107  432.34  4148.4  430.78    4317  423.35  4328.3  422.91  4473.5  414.54
  4623.3  404.91  4990.9  406.54  4996.9  401.01  5009.7  398.85  5029.7  406.46
    5311  406.86  5473.8   406.4  5500.2  406.15  5510.2  402.02  5549.3  406.24
  5790.5  406.29  5808.2  398.13  5810.7  397.63  5832.9  398.13  5840.5   406.4
  5950.6  406.51  5970.7  400.51  5980.7  406.28  6005.1  406.94  6377.3  406.81
    6457  407.35  6569.6  412.41  6701.4  418.78  6871.6  417.69  7285.1  427.78
#Mann= 13 ,-1 , 0
    4107      .1       0  4148.4     .12       0    4317      .1       0
  4328.3     .12       0  4473.5      .1       0    5311     .12       0
  5473.8      .1       0  5808.2     .07       0  5832.9      .1       0
  6005.1     .12       0  6377.3      .1       0    6457     .12       0
  6569.6     .05       0
Bank Sta=5808.2,5832.9
XS Rating Curve= 0 ,0
Exp/Cntr=0.3,0.1

Type RM Length L Ch R = 1 ,3388    ,567,567,567
BEGIN DESCRIPTION:
Wet Lacy Fork 15
END DESCRIPTION:
XS GIS Cut Line= 3
        2737126.      6873411.01        2737226.        6874061.
      2737740.43       6876427.8
#Sta/Elev= 30
  4346.7  430.77  4681.8  418.09  4812.1  417.74  4936.7  405.56  4963.9  405.69
  4975.2  398.53  4994.2  405.31  5001.8  405.59  5317.5   404.8  5495.7  405.04
  5872.2  406.38  5884.4  398.17  5892.4  397.38  5894.9  396.88  5917.4  397.38
  5921.3  397.79  5926.5  404.41  5965.3  397.93  5970.5  404.69  6014.5  403.03
  6019.6  404.89  6091.9  406.05  6205.9   408.4    6530   407.9  6656.3  415.87
  6764.5   422.9    6912  423.17  7071.5  418.97  7255.7  426.47  7426.4  427.73
#Mann= 10 ,-1 , 0
  4346.7     .05       0  4681.8     .12       0  4936.7      .1       0
  5317.5     .12       0  5495.7      .1       0  5892.4     .07       0
  5917.4      .1       0  6091.9     .12       0    6530      .1       0
  6656.3     .05       0
Bank Sta=5892.4,5917.4
XS Rating Curve= 0 ,0
Exp/Cntr=0.3,0.1

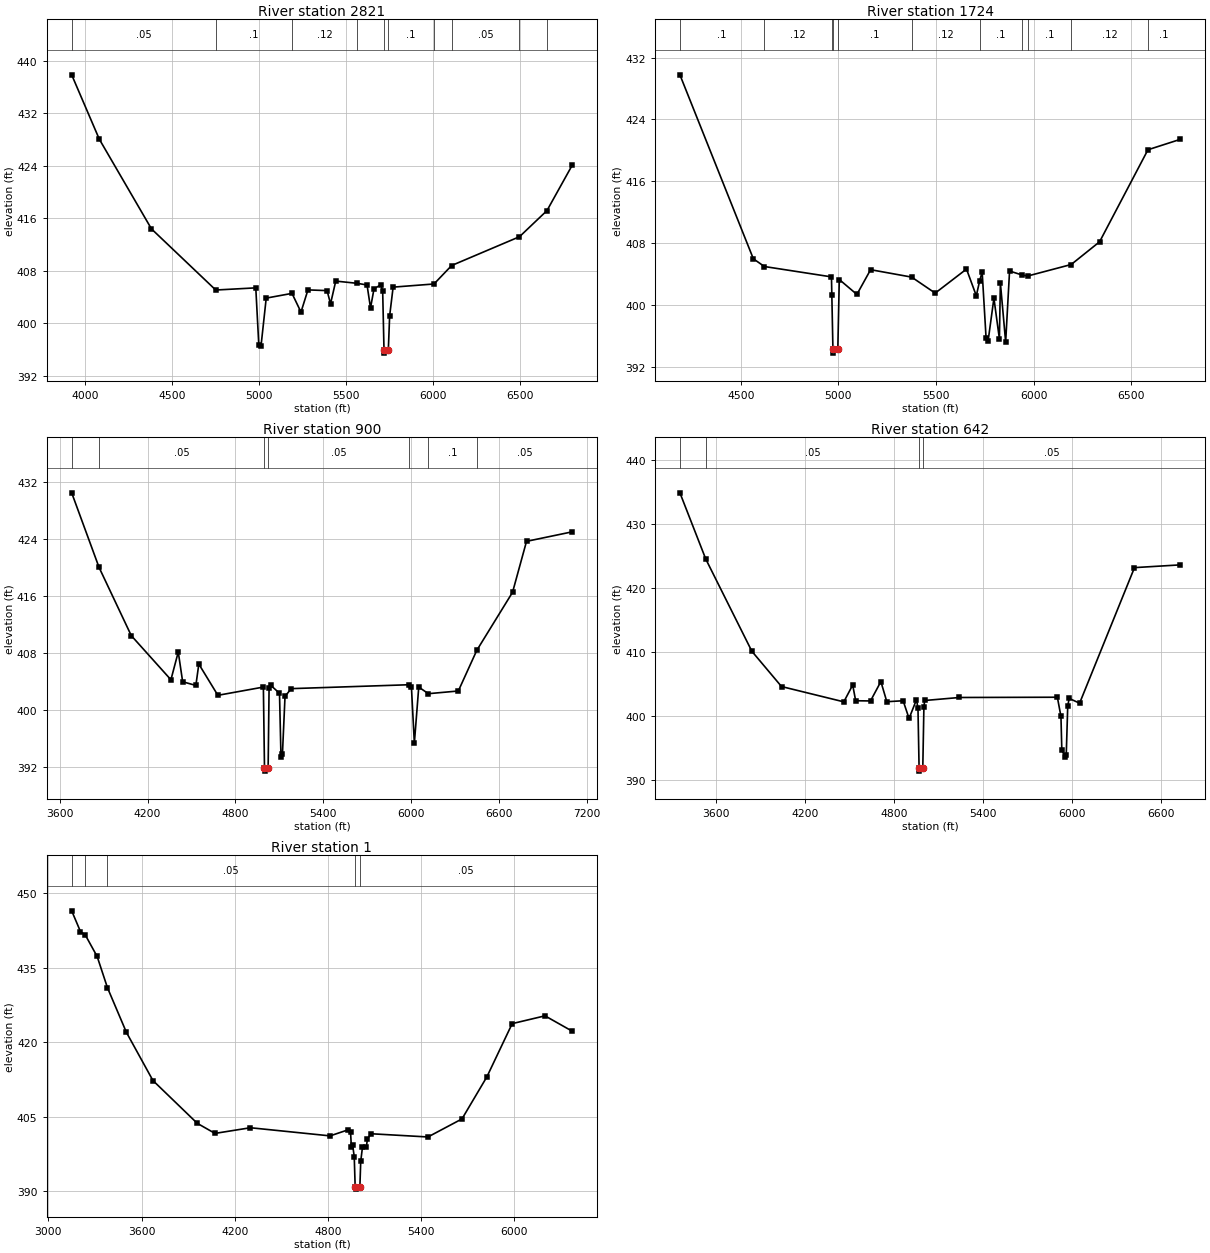
Type RM Length L Ch R = 1 ,2821    ,1097,1097,1097
BEGIN DESCRIPTION:
Wet Lacy Fork 14
END DESCRIPTION:
XS GIS Cut Line= 3
      2736748.43      6872982.24        2736726.        6874061.
        2736726.        6875861.
#Sta/Elev= 30
  3920.6  437.83  4079.4  428.04  4379.5  414.39  4749.3  405.09  4979.6  405.42
  4997.1  396.68  5009.6  396.55  5039.6  403.86  5187.9  404.58  5239.6  401.73
  5279.6  405.11  5389.6     405  5409.6     403  5439.6  406.45  5562.8  406.11
  5619.6  405.86  5639.6  402.37  5659.6  405.26  5699.6  405.91  5709.6  404.88
  5717.1  395.99  5719.6  395.49  5742.1  395.99  5749.6  401.16  5769.6  405.53
  6004.8  406.01  6106.3  408.82  6496.5   413.2  6654.5  417.17  6799.6  424.07
#Mann= 10 ,-1 , 0
  3920.6     .05       0  4749.3      .1       0  5187.9     .12       0
  5562.8      .1       0  5717.1     .07       0  5742.1      .1       0
  6004.8     .12       0  6106.3     .05       0  6496.5     .12       0
  6654.5     .05       0
Bank Sta=5717.1,5742.1
XS Rating Curve= 0 ,0
Exp/Cntr=0.3,0.1

Type RM Length L Ch R = 1 ,1724    ,824,824,824
BEGIN DESCRIPTION:
Wet Lacy Fork 13
END DESCRIPTION:
XS GIS Cut Line= 3
      2735980.94      6872855.01        2735976.        6873661.
        2736092.      6875413.76
#Sta/Elev= 30
  4188.5  429.76  4564.5  405.97  4621.1  404.97  4964.5  403.63  4966.4  401.26
    4972  394.27  4974.5  393.77    4997  394.27  5004.5  403.29  5094.7  401.36
  5164.9  404.56  5375.1   403.6  5495.6  401.53  5655.9  404.64  5706.1  401.19
  5723.6  403.15  5736.1  404.27  5756.2  395.71  5766.2  395.28  5796.3  400.87
  5824.4  395.61  5829.4  402.86  5856.4  395.19  5876.4  404.39  5939.3  403.88
  5968.8  403.74    6192  405.23  6337.4  408.17    6585  420.07  6751.1  421.42
#Mann= 11 ,-1 , 0
  4188.5      .1       0  4621.1     .12       0  4966.4      .1       0
    4972     .07       0    4997      .1       0  5375.1     .12       0
  5723.6      .1       0  5939.3     .12       0  5968.8      .1       0
    6192     .12       0    6585      .1       0
Bank Sta=4972,4997
XS Rating Curve= 0 ,0
Exp/Cntr=0.3,0.1

Type RM Length L Ch R = 1 ,900     ,258,258,258
BEGIN DESCRIPTION:
Wet Lacy Fork 1971
END DESCRIPTION:
XS GIS Cut Line= 3
       2735339.7      6872044.86      2735254.92      6873393.68
      2735179.65      6875457.82
#Sta/Elev= 30
  3681.8  430.54  3868.5  420.05  4088.7  410.44  4359.3  404.23  4409.4  408.14
  4439.4  403.95  4529.6  403.43  4549.7  406.44  4679.9  402.04  4990.5   403.2
  4998.1  391.87  5000.6  391.37  5023.1  391.87  5029.4     403  5040.6  403.45
  5100.6  402.33  5110.7  393.39  5120.7  393.79  5138.3  401.89  5180.7  402.98
  5986.7  403.53  6001.2  403.25  6021.3   395.3  6051.3   403.2  6117.2  402.27
  6321.5  402.65  6447.6  408.37  6691.7  416.54  6787.1  423.71  7098.8  425.05
#Mann= 7 ,-1 , 0
  3681.8      .1       0  3868.5     .05       0  4998.1     .04       0
  5023.1     .05       0  5986.7     .12       0  6117.2      .1       0
  6447.6     .05       0
Bank Sta=4998.1,5023.1
XS Rating Curve= 0 ,0
Exp/Cntr=0.3,0.1

Type RM Length L Ch R = 1 ,642     ,641,641,641
BEGIN DESCRIPTION:
Wet Lacy Fork 1970
END DESCRIPTION:
XS GIS Cut Line= 3
      2735107.36      6871815.95      2735055.06      6873466.88
      2735009.85      6875190.63
#Sta/Elev= 30
  3354.6  434.84  3528.8  424.51  3839.9   410.1    4040  404.59  4460.2   402.2
  4520.2  404.83  4540.2  402.37  4640.3  402.34  4710.3  405.37  4750.3  402.22
  4860.4  402.37  4900.4   399.6  4950.4  402.54  4960.5  401.21    4968  391.88
  4970.5  391.38    4993  391.88  5000.5  401.41  5005.9  402.41  5240.6  402.88
  5900.8  402.92    5925  399.92  5930.8  394.73  5950.8  393.58  5960.8  393.97
  5970.8   401.6  5980.8  402.73  6050.8  401.99    6421  423.16  6730.7  423.59
#Mann= 4 ,-1 , 0
  3354.6      .1       0  3528.8     .05       0    4968     .04       0
    4993     .05       0
Bank Sta=4968,4993
XS Rating Curve= 0 ,0
Exp/Cntr=0.3,0.1

Type RM Length L Ch R = 1 ,1       ,0,0,0
BEGIN DESCRIPTION:
Wet Lacy Fork 1800
END DESCRIPTION:
XS GIS Cut Line= 3
      2734963.72      6871626.45      2734477.09      6873410.99
      2733994.07      6874694.73
#Sta/Elev= 30
  3150.3  446.48  3206.8   442.3  3238.8  441.56  3314.2  437.28  3380.2  431.01
  3502.5  421.99  3673.3  412.28  3958.6  403.66  4072.6  401.63  4300.7  402.77
  4813.4  401.13  4927.5  402.33  4945.1     402  4950.2  398.92  4958.5  399.28
  4968.9  396.95  4974.8   390.9  4977.7   390.4  5005.2   390.9  5010.7  396.02
    5022  398.88  5046.9  398.87  5053.4  400.47  5077.1  401.56  5443.3  400.91
  5662.4  404.55  5822.7  413.03  5985.5  423.75  6196.7  425.32  6371.6  422.23
#Mann= 5 ,-1 , 0
  3150.3     .12       0  3238.8      .1       0  3380.2     .05       0
  4974.8     .04       0  5005.2     .05       0
Bank Sta=4974.8,5005.2
XS Rating Curve= 0 ,0
Exp/Cntr=0.3,0.1

Chan Stop Cuts=-1
Use User Specified Reach Order=0
Composite Channel Slope=5