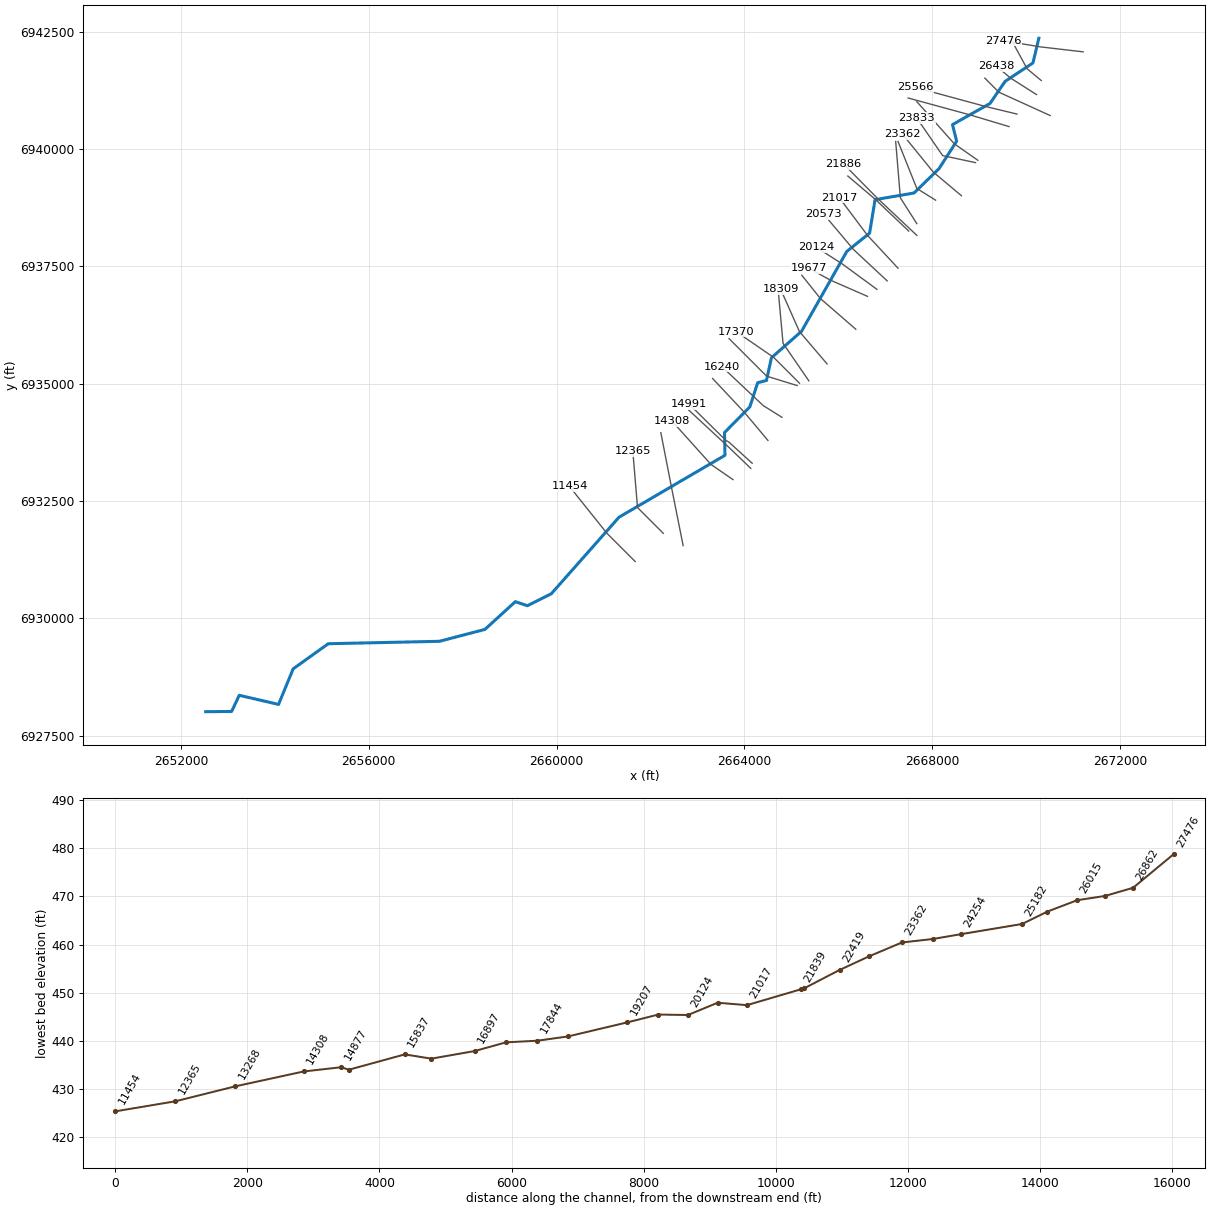
--- Anthony Branch.prj (project) ---

Proj Title=Anthony Branch Base Level Engineering
Current Plan=p01
Default Exp/Contr=0.3,0.1
English Units
Geom File=g01
Flow File=f01
Plan File=p01
Y Axis Title=Elevation
X Axis Title(PF)=Main Channel Distance
X Axis Title(XS)=Station
BEGIN DESCRIPTION:
Anthony Branch
END DESCRIPTION:
DSS Export Rating Curves= 0
DSS Export Rating Curve Sorted= 0
DSS Export Volume Flow Curves= 0
DXF OffsetX= 0
DXF OffsetY= 0
DXF ScaleX= 1
DXF ScaleY= 10

--- Anthony Branch.p01 (plan) ---

Plan Title=Multiple Run
Short Identifier=Multiple
Geom File=g01
Flow File=f01
Subcritical Flow
K Sum by GR= 0
Std Step Tol= 0.01
Critical Tol= 0.01
Num of Std Step Trials= 20
Max Error Tol= 0.3
Flow Tol Ratio= 0.001
Split Flow NTrial= 30
Split Flow Tol= 0.02
Split Flow Ratio= 0.02
Log Output Level= 0
Friction Slope Method= 1
Unsteady Friction Slope Method= 2
Unsteady Bridges Friction Slope Method= 1
Parabolic Critical Depth
Global Vel Dist=  1 , 1 , 1
Global Log Level= 0
CheckData=True
Encroach Param= -1, 0, 0, 0
BEGIN DESCRIPTION:
Multiple Run
END DESCRIPTION:

--- Anthony Branch.f01 (steady flow) ---

Flow Title=Multiple
Program Version=4.10
Number of Profiles= 7
Profile Names=10-year,25-year,50-year,1pct_min,100-year,1pct_plu,500-year
River Rch & RM=Anthony Branch,Reach-1         ,27476
     630     848    1026     615    1228    2450    1758
River Rch & RM=Anthony Branch,Reach-1         ,26862
     727     987    1199     723    1442    2878    2085
River Rch & RM=Anthony Branch,Reach-1         ,25182
     801    1090    1328     801    1599    3190    2318
River Rch & RM=Anthony Branch,Reach-1         ,21886
    1166    1622    2004    1226    2445    4879    3642
River Rch & RM=Anthony Branch,Reach-1         ,21017
    1389    1946    2413    1480    2953    5892    4427
River Rch & RM=Anthony Branch,Reach-1         ,13268
    1409    1974    2449    1502    2997    5979    4492
River Rch & RM=Anthony Branch,Reach-1         ,12365
    2109    3012    3785    2350    4688    9354    7199
River Rch & RM=Anthony Branch,Reach-1         ,11454
    2221    3168    3978    2466    4920    9817    7535
River Rch & RM=Anthony Branch,Reach-1         ,6122
    2265    3224    4042    2501    4990    9957    7615
Boundary for River Rch & Prof#=Anthony Branch,Reach-1         , 1
Up Type= 0
Dn Type= 3
Dn Slope=0.00024
Boundary for River Rch & Prof#=Anthony Branch,Reach-1         , 2
Up Type= 0
Dn Type= 3
Dn Slope=0.00024
Boundary for River Rch & Prof#=Anthony Branch,Reach-1         , 3
Up Type= 0
Dn Type= 3
Dn Slope=0.00024
Boundary for River Rch & Prof#=Anthony Branch,Reach-1         , 4
Up Type= 0
Dn Type= 3
Dn Slope=0.00024
Boundary for River Rch & Prof#=Anthony Branch,Reach-1         , 5
Up Type= 0
Dn Type= 3
Dn Slope=0.00024
Boundary for River Rch & Prof#=Anthony Branch,Reach-1         , 6
Up Type= 0
Dn Type= 3
Dn Slope=0.00024
Boundary for River Rch & Prof#=Anthony Branch,Reach-1         , 7
Up Type= 0
Dn Type= 3
Dn Slope=0.00024
DSS Import GetInterval= 0
DSS Import GetPeak= 0
DSS Import FillOption= 0

--- Anthony Branch.g01 (geometry) ---

Geom Title=Existing Conditions
Program Version=4.10

River Reach=Anthony Branch  ,Reach-1
Reach XY= 30
        2670276.        6942361.      2670149.83      6941834.13
      2669555.91      6941441.21      2669235.68      6940971.76
      2668436.28      6940521.16      2668524.04      6940166.65
      2668150.01      6939583.68       2667617.7      6939064.07
      2666786.05      6938920.98      2666670.17       6938208.7
      2666183.73       6937817.5      2665220.41      6936116.61
      2664579.35       6935552.9        2664473.      6935068.95
      2664286.05      6935021.05      2664118.14      6934504.83
      2663579.46       6933959.5      2663589.24      6933474.62
      2661331.61      6932155.41       2659889.3       6930524.4
      2659379.29      6930269.05      2659123.33       6930355.7
      2658474.37      6929764.13       2657505.8      6929511.06
      2655137.83      6929459.36      2654389.61      6928924.24
      2654078.47      6928166.45      2653241.15      6928360.64
      2653078.57        6928016.        2652526.        6928011.

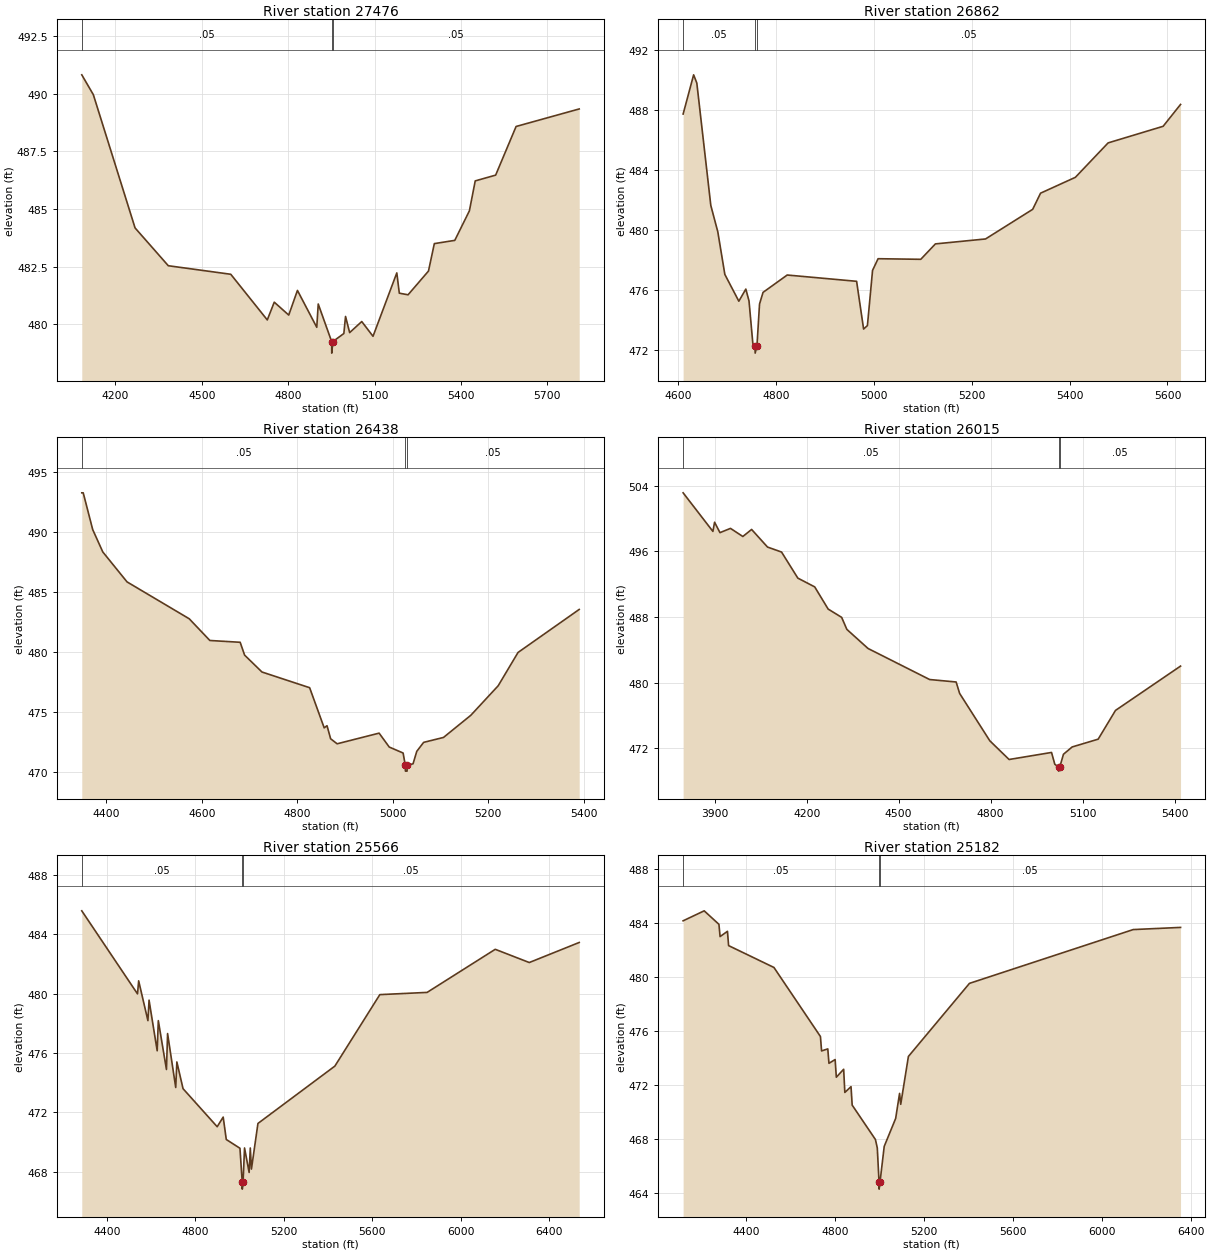
Type RM Length L Ch R = 1 ,27476   ,614,614,614
BEGIN DESCRIPTION:
Anthony Branch 51.0
END DESCRIPTION:
XS GIS Cut Line= 3
      2671219.77      6942071.24      2670309.34      6942177.47
      2669509.86      6942310.65
#Sta/Elev= 30
  4083.4  490.82  4123.5  489.96  4268.4  484.18  4383.8  482.54  4600.7  482.17
  4727.5  480.19  4751.7  480.96    4802   480.4  4832.2  481.47  4899.3  479.87
  4904.4  480.88    4951  479.25  4951.3  478.75    4955  479.25  4993.3   479.6
  4999.2  480.34  5013.5  479.64  5055.5  480.12  5094.6  479.48  5177.2  482.23
  5185.9  481.35  5216.3  481.28  5287.2  482.31  5307.5   483.5  5378.5  483.64
  5429.2  484.92  5449.5  486.22  5520.4  486.47  5591.4  488.58  5810.5  489.34
#Mann= 3 ,-1 , 0
  4083.4     .05       0    4951     .04       0    4955     .05       0
Bank Sta=4951,4955
XS Rating Curve= 0 ,0
Exp/Cntr=0.3,0.1

Type RM Length L Ch R = 1 ,26862   ,424,424,424
BEGIN DESCRIPTION:
Anthony Branch 50.0
END DESCRIPTION:
XS GIS Cut Line= 3
        2670326.        6941461.        2670026.        6941711.
      2669726.01      6942260.99
#Sta/Elev= 30
  4609.7  487.75  4631.2  490.37  4637.7  489.82  4666.3  481.64  4680.6  479.88
    4695  477.03  4723.6  475.24  4737.9  476.05  4744.4  475.26  4752.2  472.43
  4756.7  472.27    4757  471.77  4760.7  472.27  4765.9  475.05  4773.1  475.83
  4822.5  476.99  4964.4  476.57  4978.7  473.38  4986.5  473.61    4997   477.3
  5008.3  478.08  5095.6  478.04  5125.5  479.07    5228   479.4  5324.4  481.38
  5340.5  482.46  5411.7  483.52  5478.6  485.82  5591.1  486.93  5626.7  488.39
#Mann= 3 ,-1 , 0
  4609.7     .05       0  4756.7     .04       0  4760.7     .05       0
Bank Sta=4756.7,4760.7
XS Rating Curve= 0 ,0
Exp/Cntr=0.3,0.1

Type RM Length L Ch R = 1 ,26438   ,423,423,423
BEGIN DESCRIPTION:
Anthony Branch 49.0
END DESCRIPTION:
XS GIS Cut Line= 3
        2670226.        6941161.        2669676.        6941511.
      2669376.02      6941760.98
#Sta/Elev= 30
  4348.3   493.3  4351.3   493.3  4371.2  490.23  4392.3  488.37  4443.1  485.87
  4573.5  482.79  4616.7  480.98  4680.2  480.83  4689.5  479.76  4725.9  478.35
  4825.8  477.04  4856.3  473.69  4862.2  473.87  4869.8  472.78  4883.4  472.36
  4971.4  473.25  4992.6  472.09  5021.7  471.59  5026.2  470.58  5026.5  470.08
    5030  470.08  5030.2  470.58  5042.5  470.69  5050.3  471.73  5064.7  472.48
  5106.3  472.89  5163.6  474.74  5220.9   477.2  5262.5  479.98  5390.7  483.57
#Mann= 3 ,-1 , 0
  4348.3     .05       0  5026.2     .03       0  5030.2     .05       0
Bank Sta=5026.2,5030.2
XS Rating Curve= 0 ,0
Exp/Cntr=0.3,0.1

Type RM Length L Ch R = 1 ,26015   ,449,449,449
BEGIN DESCRIPTION:
Anthony Branch 48.0
END DESCRIPTION:
XS GIS Cut Line= 3
      2670516.59      6940714.49        2669426.        6941211.
      2669125.97      6941511.03
#Sta/Elev= 30
  3797.1  503.16  3894.2  498.45  3899.7  499.57  3917.3   498.3  3951.6  498.82
  3991.9  497.83  4020.5  498.69  4072.4  496.54  4118.2  495.93  4171.3  492.75
  4226.3  491.68  4270.2  488.97  4314.2  487.96  4331.2  486.49  4400.3  484.16
  4601.3  480.37  4687.7  480.07    4699  478.68  4797.6  472.89  4860.4  470.61
  4998.9  471.47  5009.5  470.03  5021.7  469.69  5021.9  469.19  5025.7  469.69
  5037.8  471.25  5066.1  472.14    5151  473.09  5207.5   476.6  5419.7  482.01
#Mann= 3 ,-1 , 0
  3797.1     .05       0  5021.7     .04       0  5025.7     .05       0
Bank Sta=5021.7,5025.7
XS Rating Curve= 0 ,0
Exp/Cntr=0.3,0.1

Type RM Length L Ch R = 1 ,25566   ,384,384,384
BEGIN DESCRIPTION:
Anthony Branch 47.0
END DESCRIPTION:
XS GIS Cut Line= 3
      2669810.89      6940745.72        2669126.        6940911.
      2667636.44      6941316.03
#Sta/Elev= 30
  4286.9  485.57  4538.8  479.98  4543.9  480.86  4585.8  478.18  4590.9  479.56
  4627.7  476.15  4632.8  478.18  4669.6  474.89  4674.7  477.31  4711.5  473.68
  4716.6   475.4  4744.6   473.6  4898.9  471.04    4926  471.69    4940  470.18
  5001.8  469.59  5011.9  467.34  5012.2  466.84  5015.9  467.34  5022.5  469.61
  5043.3  467.96  5048.5  469.61  5053.7  468.19  5083.1  471.26  5430.8  475.12
    5634  479.93  5847.7  480.08  6155.6  482.98  6309.5  482.09  6535.1  483.44
#Mann= 3 ,-1 , 0
  4286.9     .05       0  5011.9     .05       0  5015.9     .05       0
Bank Sta=5011.9,5015.9
XS Rating Curve= 0 ,0
Exp/Cntr=0.3,0.1

Type RM Length L Ch R = 1 ,25182   ,928,928,928
BEGIN DESCRIPTION:
Anthony Branch 46.0
END DESCRIPTION:
XS GIS Cut Line= 3
      2669641.62      6940478.79      2668810.19      6940727.82
      2667490.82       6941088.1
#Sta/Elev= 30
  4117.6  484.16  4212.3   484.9  4278.5   483.9  4283.7  482.99  4316.8  483.38
    4322  482.32  4525.7   480.7  4734.7  475.58  4739.9  474.51  4767.8  474.66
    4773  473.59  4800.8  473.87  4806.1  472.56  4839.1  473.15  4844.4  471.43
  4872.2  471.86  4877.4  470.49  4981.9  467.94  4990.3  467.31  4998.2  464.76
  4998.5  464.26  5002.3  464.76  5021.4  467.43  5072.8   469.5  5090.4  471.36
  5095.6  470.55  5130.1   474.1  5404.5  479.52  6140.5  483.51  6353.2  483.67
#Mann= 3 ,-1 , 0
  4117.6     .05       0  4998.2     .03       0  5002.3     .05       0
Bank Sta=4998.2,5002.3
XS Rating Curve= 0 ,0
Exp/Cntr=0.3,0.1

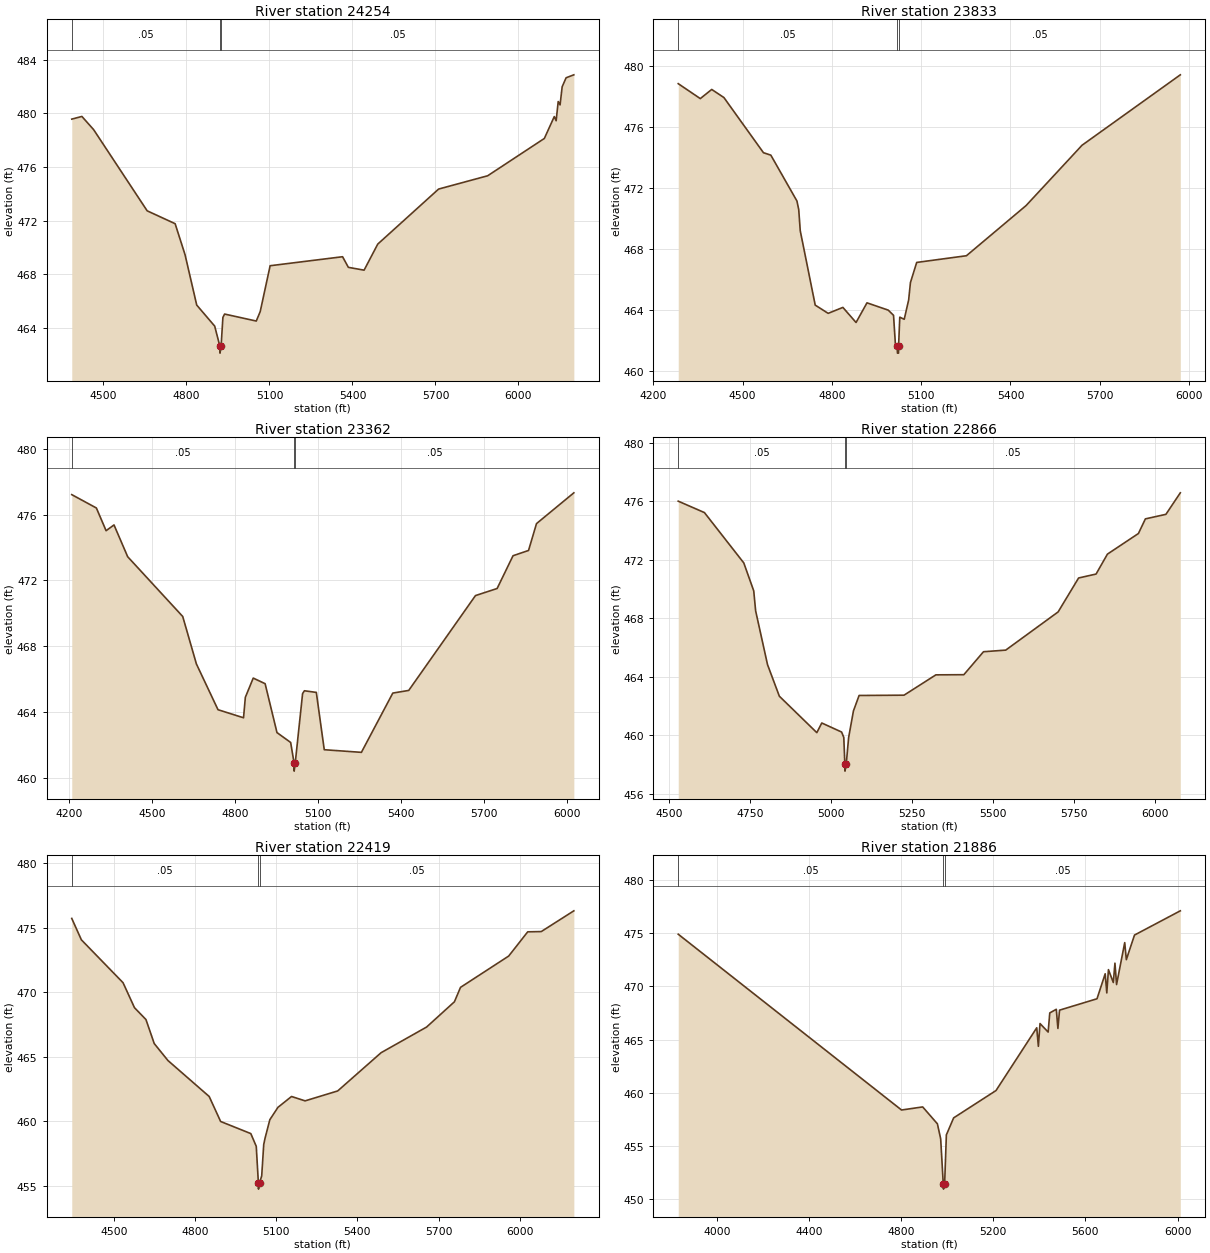
Type RM Length L Ch R = 1 ,24254   ,421,421,421
BEGIN DESCRIPTION:
Anthony Branch 44.0
END DESCRIPTION:
XS GIS Cut Line= 3
        2668976.        6939761.        2668476.        6940111.
      2667675.99      6941011.01
#Sta/Elev= 30
  4385.6  479.57  4422.2  479.77  4464.5  478.79  4658.1  472.74  4759.2  471.78
    4795  469.47  4837.2  465.72  4902.2  464.15    4921  462.64  4921.3  462.14
  4925.2  462.64  4931.8   464.8  4937.9  465.05  5052.4  464.53  5066.6  465.23
  5102.5  468.65  5364.3  469.32  5385.2  468.53  5442.1  468.32  5491.4  470.26
  5711.3  474.36  5888.6  475.35  6093.5  478.13  6129.4  479.76  6136.1  479.45
  6143.6  480.88  6150.3  480.63  6157.9  481.98  6172.1  482.65  6200.1  482.87
#Mann= 3 ,-1 , 0
  4385.6     .05       0    4921     .04       0  4925.2     .05       0
Bank Sta=4921,4925.2
XS Rating Curve= 0 ,0
Exp/Cntr=0.3,0.1

Type RM Length L Ch R = 1 ,23833   ,471,471,471
BEGIN DESCRIPTION:
Anthony Branch 43.0
END DESCRIPTION:
XS GIS Cut Line= 3
      2668925.98        6939711.        2668226.        6939861.
        2667676.        6940661.
#Sta/Elev= 30
  4283.8  478.83  4357.9  477.85  4396.3  478.45  4437.2  477.92  4570.1   474.3
  4594.9  474.14  4682.6  471.13  4688.6  470.57  4693.7  469.18    4744   464.3
  4787.5  463.76  4836.9  464.15  4881.2  463.16  4917.9  464.45  4989.4  463.97
  5007.1  463.63  5013.2  461.78  5019.9  461.65  5020.2  461.15  5023.8  461.15
  5024.1  461.65  5028.1  463.51    5043  463.37  5057.9  464.64  5063.9  465.78
  5084.9   467.1    5252  467.54  5452.3  470.83  5640.4  474.79  5970.5  479.41
#Mann= 3 ,-1 , 0
  4283.8     .05       0  5019.9     .03       0  5024.1     .05       0
Bank Sta=5019.9,5024.1
XS Rating Curve= 0 ,0
Exp/Cntr=0.3,0.1

Type RM Length L Ch R = 1 ,23362   ,496,496,496
BEGIN DESCRIPTION:
Anthony Branch 42.0
END DESCRIPTION:
XS GIS Cut Line= 3
      2668625.98      6939006.15        2668026.        6939511.
        2667376.        6940311.
#Sta/Elev= 30
  4210.4  477.21  4299.3   476.4  4334.5  475.02  4363.1  475.37  4412.5  473.44
  4611.5  469.81  4660.9  466.93    4739  464.15  4831.3  463.66  4837.8   464.9
  4866.4  466.07  4909.3  465.73  4952.2  462.76  5001.7  462.16  5013.9  460.92
  5014.3  460.42  5018.2  460.92  5044.8  465.13  5051.3   465.3  5094.4   465.2
  5123.1  461.72  5257.4  461.56  5370.9  465.16  5428.4  465.32  5669.7  471.08
    5748  471.51  5805.5   473.5  5861.5  473.82  5890.3  475.45  6025.3  477.32
#Mann= 3 ,-1 , 0
  4210.4     .05       0  5013.9     .03       0  5018.2     .05       0
Bank Sta=5013.9,5018.2
XS Rating Curve= 0 ,0
Exp/Cntr=0.3,0.1

Type RM Length L Ch R = 1 ,22866   ,447,447,447
BEGIN DESCRIPTION:
Anthony Branch 41.0
END DESCRIPTION:
XS GIS Cut Line= 3
        2668076.        6938911.        2667676.        6939161.
      2667276.01      6940160.97
#Sta/Elev= 30
  4528.1     476  4608.9  475.22  4730.3  471.78    4761  469.87  4766.9   468.5
  4803.5  464.83    4840  462.67  4955.6  460.18  4970.9  460.84  5032.1  460.22
  5038.8  459.85    5042  458.05  5042.4  457.55  5046.4  458.05  5053.7  459.84
  5068.5  461.66    5086  462.72  5224.6  462.74  5322.9  464.13  5409.1  464.14
  5469.7  465.71  5538.3  465.82  5699.9  468.43  5763.1  470.75    5817  471.02
    5852  472.38  5947.6  473.79  5969.1  474.79  6032.4   475.1  6076.8  476.57
#Mann= 3 ,-1 , 0
  4528.1     .05       0    5042     .03       0  5046.4     .05       0
Bank Sta=5042,5046.4
XS Rating Curve= 0 ,0
Exp/Cntr=0.3,0.1

Type RM Length L Ch R = 1 ,22419   ,533,533,533
BEGIN DESCRIPTION:
Anthony Branch 40.0
END DESCRIPTION:
XS GIS Cut Line= 3
      2667675.98      6938411.03        2667326.        6938961.
        2667226.      6940160.96
#Sta/Elev= 30
    4344  475.73  4379.5  474.07  4533.6  470.74  4575.9   468.8  4618.3  467.88
  4648.8  466.02  4699.6   464.7    4852  461.91  4894.3  459.97  5005.9  459.03
    5026  458.04  5033.8  455.22  5034.2  454.72  5038.3  455.22  5046.1  455.74
  5053.6  458.18  5058.6  458.68  5076.2  460.11  5106.3  461.07  5156.4  461.91
  5206.6  461.57    5327  462.34  5487.6  465.31  5655.7   467.3  5758.5  469.26
  5781.1  470.38  5959.2  472.81  6029.5  474.69  6079.6  474.71    6200  476.32
#Mann= 3 ,-1 , 0
    4344     .05       0  5033.8     .03       0  5038.3     .05       0
Bank Sta=5033.8,5038.3
XS Rating Curve= 0 ,0
Exp/Cntr=0.3,0.1

Type RM Length L Ch R = 1 ,21886   ,47,47,47
BEGIN DESCRIPTION:
Anthony Branch 39.0
END DESCRIPTION:
XS GIS Cut Line= 3
      2667676.03      6938160.97        2666826.        6938961.
      2666116.04      6939682.32
#Sta/Elev= 30
  3832.7   474.9    4802  458.37  4893.8  458.66  4957.7  457.07  4971.9  455.66
  4983.1  451.43  4984.1  450.93  4989.1  451.43  4996.6  456.03  5028.2  457.63
  5212.1   460.2  5388.9   466.1    5396  464.36  5403.1   466.5  5438.4   465.7
  5445.5   467.5  5473.8  467.84  5480.8  466.04  5487.9  467.76  5650.5  468.83
    5686  471.18    5693  469.38  5700.1  471.57  5721.3  470.36  5728.4  472.18
  5735.4  470.17  5770.8  474.11  5777.8  472.51  5813.2  474.82  6012.1   477.1
#Mann= 3 ,-1 , 0
  3832.7     .05       0  4983.1     .03       0  4989.1     .05       0
Bank Sta=4983.1,4989.1
XS Rating Curve= 0 ,0
Exp/Cntr=0.3,0.1

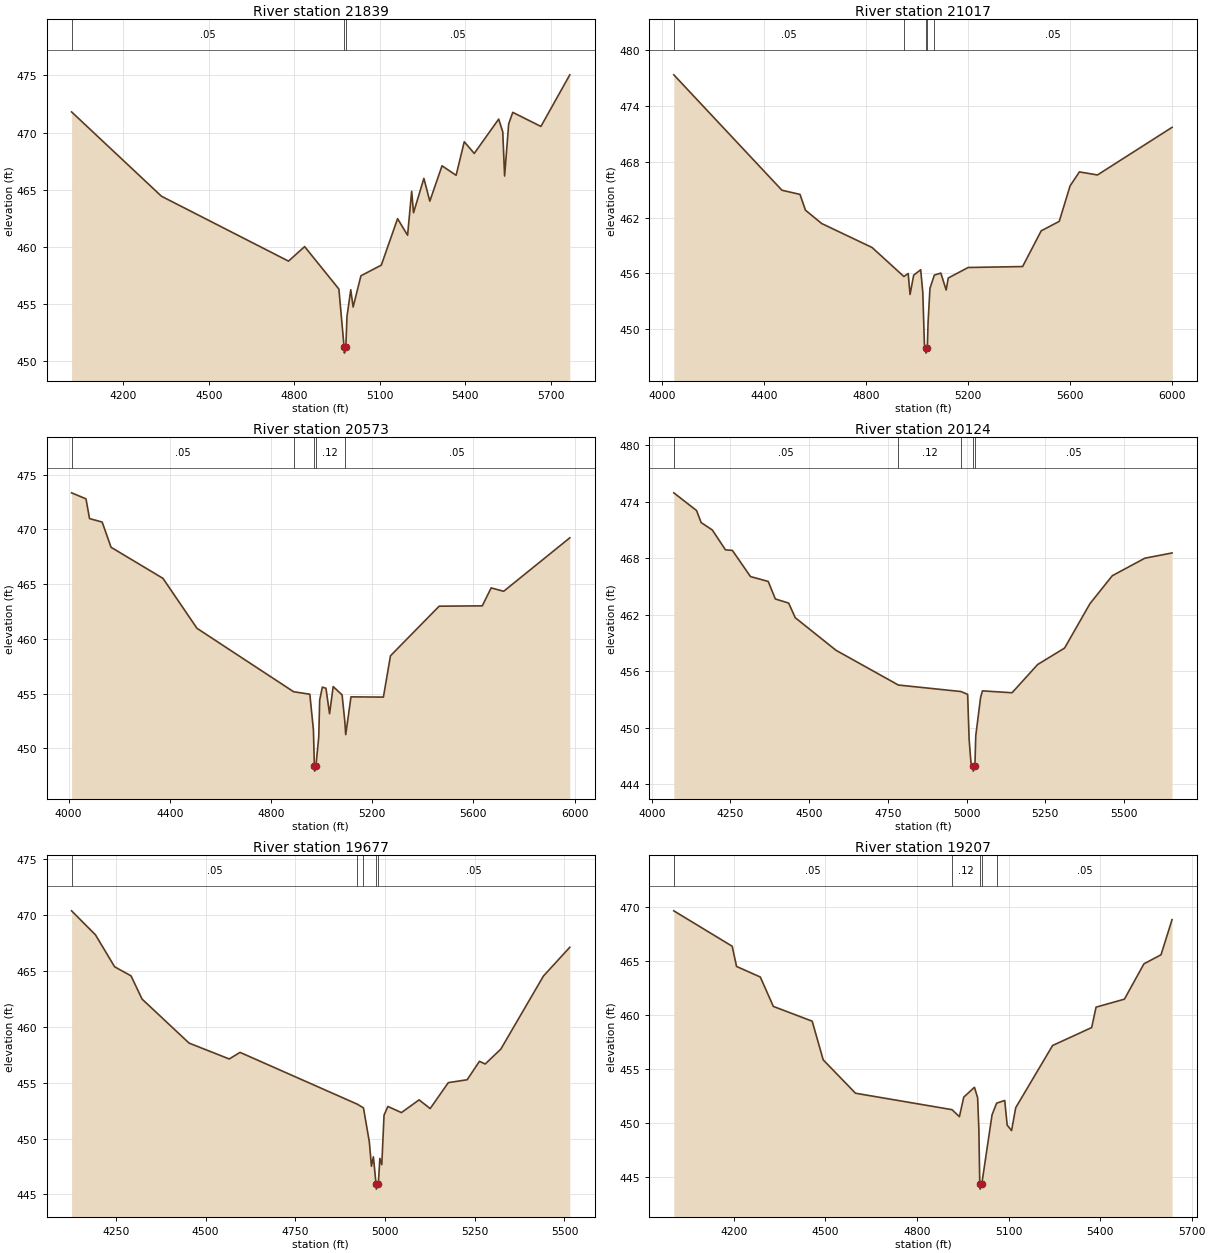
Type RM Length L Ch R = 1 ,21839   ,822,822,822
BEGIN DESCRIPTION:
Anthony Branch 38.0
END DESCRIPTION:
XS GIS Cut Line= 3
        2667504.       6938252.7      2666792.08      6938928.06
      2666207.17      6939424.53
#Sta/Elev= 30
  4018.7  471.81  4334.2  464.44    4780  458.77  4836.6  460.04  4956.8  456.33
  4975.2  451.23  4976.2  450.73  4981.2  451.23  4985.1  453.91  4998.5  456.27
  5006.8  454.76  5034.2  457.49  5105.7  458.42  5162.8  462.48  5197.9  461.03
  5212.2  464.87  5218.8     463  5255.1     466  5275.9  464.01  5318.8   467.1
  5368.2  466.27  5396.8   469.2  5431.9  468.18  5517.6  471.18  5531.9  470.07
  5538.4  466.21  5552.7  470.76    5567  471.77  5665.8  470.54  5767.2  475.05
#Mann= 3 ,-1 , 0
  4018.7     .05       0  4975.2     .03       0  4981.2     .05       0
Bank Sta=4975.2,4981.2
XS Rating Curve= 0 ,0
Exp/Cntr=0.3,0.1

Type RM Length L Ch R = 1 ,21017   ,444,444,444
BEGIN DESCRIPTION:
Anthony Branch 37.0
END DESCRIPTION:
XS GIS Cut Line= 3
      2667275.99      6937461.01        2666626.        6938161.
      2666026.02      6938960.98
#Sta/Elev= 30
    4045  477.35  4469.3  464.94  4540.2  464.49  4561.7  462.79  4625.2  461.36
  4823.1  458.78  4947.9  455.66  4964.8  455.98  4972.1  453.73  4986.3   455.8
  5013.8  456.39  5022.1  453.96  5028.4  448.36  5033.6  447.92  5034.6  447.42
  5039.7  447.92  5042.9  450.76  5050.2  454.39  5067.4  455.81  5092.9  456.03
  5113.8  454.21  5122.1   455.5  5200.2  456.63  5413.8  456.73  5486.7  460.57
  5557.5  461.59  5600.2  465.41  5636.7  466.91  5707.5  466.58  6000.2   471.7
#Mann= 5 ,-1 , 0
    4045     .05       0  4947.9     .12       0  5033.6     .07       0
  5039.7     .12       0  5067.4     .05       0
Bank Sta=5033.6,5039.7
XS Rating Curve= 0 ,0
Exp/Cntr=0.3,0.1

Type RM Length L Ch R = 1 ,20573   ,449,449,449
BEGIN DESCRIPTION:
Anthony Branch 36.0
END DESCRIPTION:
XS GIS Cut Line= 3
      2667045.72      6937190.15        2666326.        6937861.
      2665691.56      6938614.62
#Sta/Elev= 30
  4011.9  473.33  4068.8  472.78  4082.9  470.98  4132.8  470.66  4167.9  468.36
  4373.1  465.52  4507.5  460.96  4889.3  455.17  4953.5  454.94  4967.7  451.69
  4971.4  448.42  4972.4  447.92  4977.6  448.42  4988.7  451.04  4992.4   454.4
  5002.9  455.59  5017.2  455.49  5031.5  453.16  5045.8  455.64    5081  454.88
  5091.6   452.5  5095.3  451.25  5116.1   454.7  5244.2  454.68  5272.2  458.45
  5464.6  462.98    5635  463.01  5670.1  464.65  5719.5  464.34  5980.9  469.22
#Mann= 5 ,-1 , 0
  4011.9     .05       0  4889.3     .12       0  4971.4     .07       0
  4977.6     .12       0  5091.6     .05       0
Bank Sta=4971.4,4977.6
XS Rating Curve= 0 ,0
Exp/Cntr=0.3,0.1

Type RM Length L Ch R = 1 ,20124   ,447,447,447
BEGIN DESCRIPTION:
Anthony Branch 35.0
END DESCRIPTION:
XS GIS Cut Line= 3
      2666825.98      6937011.01        2666076.        6937561.
      2665525.96      6937911.03
#Sta/Elev= 30
  4070.2  474.95  4142.3  473.07    4157  471.79  4192.5     471  4234.2  468.89
  4256.2  468.83  4313.7  466.05    4370  465.53  4392.6  463.67  4434.9  463.23
  4455.7  461.68  4585.4  458.21  4783.3  454.52  4981.8  453.83  5003.2  453.53
  5007.9  448.76  5013.8  446.25  5019.9  445.87    5021  445.37  5026.2  445.87
    5029  449.14  5044.3  453.19  5050.2   453.9  5144.2   453.7  5225.4   456.7
    5311  458.45  5391.4  463.16  5462.5  466.14  5565.8     468  5652.2  468.56
#Mann= 5 ,-1 , 0
  4070.2     .05       0  4783.3     .12       0  4981.8     .05       0
  5019.9     .03       0  5026.2     .05       0
Bank Sta=5019.9,5026.2
XS Rating Curve= 0 ,0
Exp/Cntr=0.3,0.1

Type RM Length L Ch R = 1 ,19677   ,470,470,470
BEGIN DESCRIPTION:
Anthony Branch 34.0
END DESCRIPTION:
XS GIS Cut Line= 3
      2666625.97      6936861.01        2665826.        6937211.
      2665375.97      6937461.02
#Sta/Elev= 30
  4126.8  470.38  4193.4  468.23  4246.8  465.37  4292.4  464.56  4323.2  462.48
  4454.2  458.54  4566.1  457.12  4596.1  457.71    4923  453.07    4940  452.74
  4956.3   449.7  4962.2  447.52  4967.6  448.36  4974.9  445.97  4975.9  445.47
  4981.5  445.97  4985.6  448.22    4991  447.66  4997.3  452.09    5008  452.87
  5045.7  452.32  5094.9  453.46  5125.8  452.68  5176.2     455  5228.8  455.26
  5263.1  456.91  5279.1  456.67  5322.6     458  5441.5  464.55  5514.8  467.12
#Mann= 5 ,-1 , 0
  4126.8     .05       0    4923     .12       0    4940     .05       0
  4974.9     .03       0  4981.5     .05       0
Bank Sta=4974.9,4981.5
XS Rating Curve= 0 ,0
Exp/Cntr=0.3,0.1

Type RM Length L Ch R = 1 ,19207   ,898,898,898
BEGIN DESCRIPTION:
Anthony Branch 33.0
END DESCRIPTION:
XS GIS Cut Line= 3
      2666375.98      6936161.01        2665626.        6936811.
      2665225.98      6937311.03
#Sta/Elev= 30
  4002.9  469.62  4194.2  466.34  4208.5  464.47  4286.4  463.49  4329.1  460.77
  4456.4   459.4  4492.5  455.82  4598.4  452.73  4914.4  451.21  4938.9  450.56
  4953.1  452.37  4988.2  453.28  4998.6  452.31  5002.6  449.42  5005.6  444.35
  5006.7  443.85  5012.3  444.35  5045.8  450.72  5060.8  451.81  5087.4  452.06
  5095.4  449.78  5109.8  449.27  5123.4  451.39  5244.3  457.15  5372.3  458.81
  5386.7   460.7  5479.6  461.44  5543.6  464.71  5599.6  465.55  5635.7   468.8
#Mann= 5 ,-1 , 0
  4002.9     .05       0  4914.4     .12       0  5005.6     .07       0
  5012.3     .12       0  5060.8     .05       0
Bank Sta=5005.6,5012.3
XS Rating Curve= 0 ,0
Exp/Cntr=0.3,0.1

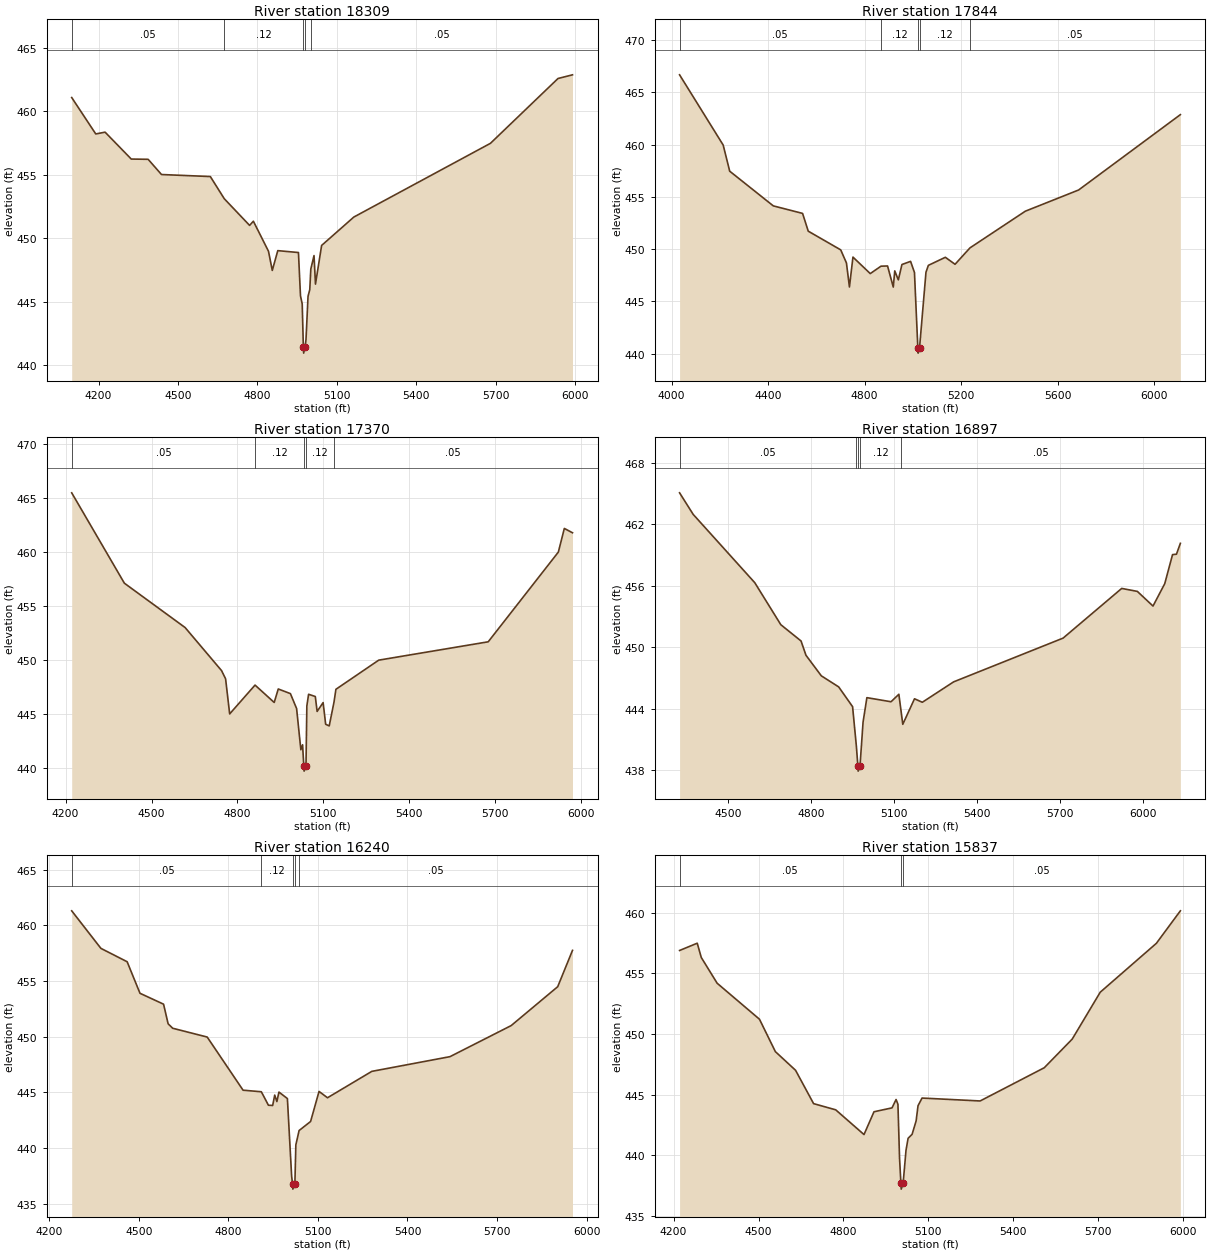
Type RM Length L Ch R = 1 ,18309   ,465,465,465
BEGIN DESCRIPTION:
Anthony Branch 31.0
END DESCRIPTION:
XS GIS Cut Line= 3
      2665764.44      6935421.95        2665176.        6936111.
        2664776.      6937010.99
#Sta/Elev= 30
  4098.8  461.08  4189.6  458.21  4224.9  458.35  4323.7  456.23  4387.4  456.21
  4437.9  455.01  4622.3  454.85    4675   453.1  4770.5     451  4784.8  451.33
  4841.9  448.96  4856.2  447.45    4877  449.01    4955  448.86  4962.7  445.44
  4969.2  444.81  4973.5  441.43  4974.6  440.93  4980.4  441.43  4983.5  442.01
  4991.2  445.41  4997.8  445.94  5001.7  447.56  5013.8  448.62  5019.3  446.37
  5042.5  449.42  5164.3  451.66    5680  457.47  5935.1  462.58  5989.8  462.87
#Mann= 5 ,-1 , 0
  4098.8     .05       0    4675     .12       0  4973.5     .07       0
  4980.4     .12       0  5001.7     .05       0
Bank Sta=4973.5,4980.4
XS Rating Curve= 0 ,0
Exp/Cntr=0.3,0.1

Type RM Length L Ch R = 1 ,17844   ,474,474,474
BEGIN DESCRIPTION:
Anthony Branch 30.0
END DESCRIPTION:
XS GIS Cut Line= 3
      2665376.02      6935060.97        2664826.        6935861.
        2664726.        6936961.
#Sta/Elev= 30
  4033.4  466.67  4214.1  459.95  4241.1  457.45  4421.8  454.13  4543.1  453.41
  4566.6  451.71  4701.2  449.92  4724.9  448.67  4737.3  446.37  4751.9  449.23
  4823.6  447.65  4868.1  448.36  4895.3  448.38    4919  446.36  4925.1  447.91
    4940  447.05  4954.9  448.52  4990.7  448.82  5006.8  447.76  5020.8  440.54
  5021.9  440.04  5027.8  440.54  5054.5  447.78  5064.5  448.44  5134.8  449.21
    5175  448.54  5236.8  450.11  5466.2  453.62  5687.1  455.65  6108.8  462.86
#Mann= 5 ,-1 , 0
  4033.4     .05       0  4868.1     .12       0  5020.8     .07       0
  5027.8     .12       0  5236.8     .05       0
Bank Sta=5020.8,5027.8
XS Rating Curve= 0 ,0
Exp/Cntr=0.3,0.1

Type RM Length L Ch R = 1 ,17370   ,473,473,473
BEGIN DESCRIPTION:
Anthony Branch 29.0
END DESCRIPTION:
XS GIS Cut Line= 3
      2665176.01      6935010.99        2664626.        6935561.
      2663825.96      6936111.03
#Sta/Elev= 30
  4221.3  465.48  4405.2  457.11  4617.3     453  4744.6  449.01  4758.7  448.25
  4772.9     445  4861.5  447.67  4928.4  446.06  4942.6  447.31    4985  446.88
  5006.6   445.5  5021.5  441.68  5027.5  442.14  5031.7   440.2  5032.8   439.7
  5039.4   440.2  5042.4  445.74  5048.5  446.82  5071.9  446.61  5078.3  445.23
  5099.2  446.05  5108.1  444.04  5120.5  443.89  5137.4  446.12  5143.9  447.28
  5293.4  449.98  5675.7  451.68  5920.6  459.99  5941.5  462.18    5970  461.78
#Mann= 5 ,-1 , 0
  4221.3     .05       0  4861.5     .12       0  5031.7     .07       0
  5039.4     .12       0  5137.4     .05       0
Bank Sta=5031.7,5039.4
XS Rating Curve= 0 ,0
Exp/Cntr=0.3,0.1

Type RM Length L Ch R = 1 ,16897   ,657,657,657
BEGIN DESCRIPTION:
Anthony Branch 28.0
END DESCRIPTION:
XS GIS Cut Line= 3
      2665126.01        6934961.        2664476.        6935161.
      2663675.97      6935961.03
#Sta/Elev= 30
  4324.2  465.06  4373.3  462.96  4596.2  456.29  4690.4  452.19  4763.6   450.6
  4781.3  449.21  4836.9   447.2  4899.7  446.12    4950  444.19  4963.8   440.3
  4969.1   438.4  4970.2   437.9  4976.8   438.4  4987.9  442.68  5001.7  445.07
  5089.1  444.67  5117.4   445.4  5125.9  443.65  5131.6  442.47    5174  444.96
  5202.3  444.62  5315.4  446.61  5711.4  450.88  5923.5  455.73  5980.1  455.44
  6036.7  454.01  6079.1  456.19  6107.4  459.03  6121.5  459.07  6135.7  460.13
#Mann= 5 ,-1 , 0
  4324.2     .05       0  4963.8     .12       0  4969.1     .07       0
  4976.8     .12       0  5125.9     .05       0
Bank Sta=4969.1,4976.8
XS Rating Curve= 0 ,0
Exp/Cntr=0.3,0.1

Type RM Length L Ch R = 1 ,16240   ,403,403,403
BEGIN DESCRIPTION:
Anthony Branch 27.0
END DESCRIPTION:
XS GIS Cut Line= 3
      2664803.49      6934283.93      2664403.51      6934533.91
      2663526.03      6935360.98
#Sta/Elev= 30
  4275.3   461.3  4373.1  457.93    4461  456.73    4504   453.9    4583  452.92
  4598.3  451.16  4613.6  450.76  4729.2  449.97  4849.3   445.2  4910.5  445.06
  4934.3  443.85  4948.5  443.83  4955.3  444.76  4962.6  444.18  4969.5  445.03
  4997.8  444.45    5012  437.48  5014.9  436.82  5016.1  436.32  5022.9  436.82
  5026.1  440.29    5037  441.58  5075.5  442.39  5103.8  445.09  5132.1  444.52
  5280.6  446.89  5542.4  448.21  5747.5     451  5903.3  454.49  5952.8  457.75
#Mann= 5 ,-1 , 0
  4275.3     .05       0  4910.5     .12       0  5014.9     .07       0
  5022.9     .12       0    5037     .05       0
Bank Sta=5014.9,5022.9
XS Rating Curve= 0 ,0
Exp/Cntr=0.3,0.1

Type RM Length L Ch R = 1 ,15837   ,846,846,846
BEGIN DESCRIPTION:
Anthony Branch 26.0
END DESCRIPTION:
XS GIS Cut Line= 3
      2664504.05      6933791.72      2664003.57      6934388.55
      2663325.98      6935111.02
#Sta/Elev= 30
  4221.1  456.88  4283.5  457.48  4297.8   456.3  4353.8  454.18  4503.4  451.21
  4559.5  448.54  4630.9     447  4694.6  444.25  4772.7  443.74  4872.7   441.7
    4908  443.58  4971.7   443.9    4986  444.59  4992.6   444.2  4998.3  439.74
    5003   437.7  5004.2   437.2    5011   437.7  5021.1   440.4  5028.5  441.39
  5042.6  441.72  5056.8  442.82  5063.6  444.08  5077.8  444.71    5283  444.47
  5509.6  447.21  5608.3  449.57  5707.4  453.44  5905.7  457.47  5990.5  460.15
#Mann= 3 ,-1 , 0
  4221.1     .05       0    5003     .03       0    5011     .05       0
Bank Sta=5003,5011
XS Rating Curve= 0 ,0
Exp/Cntr=0.3,0.1

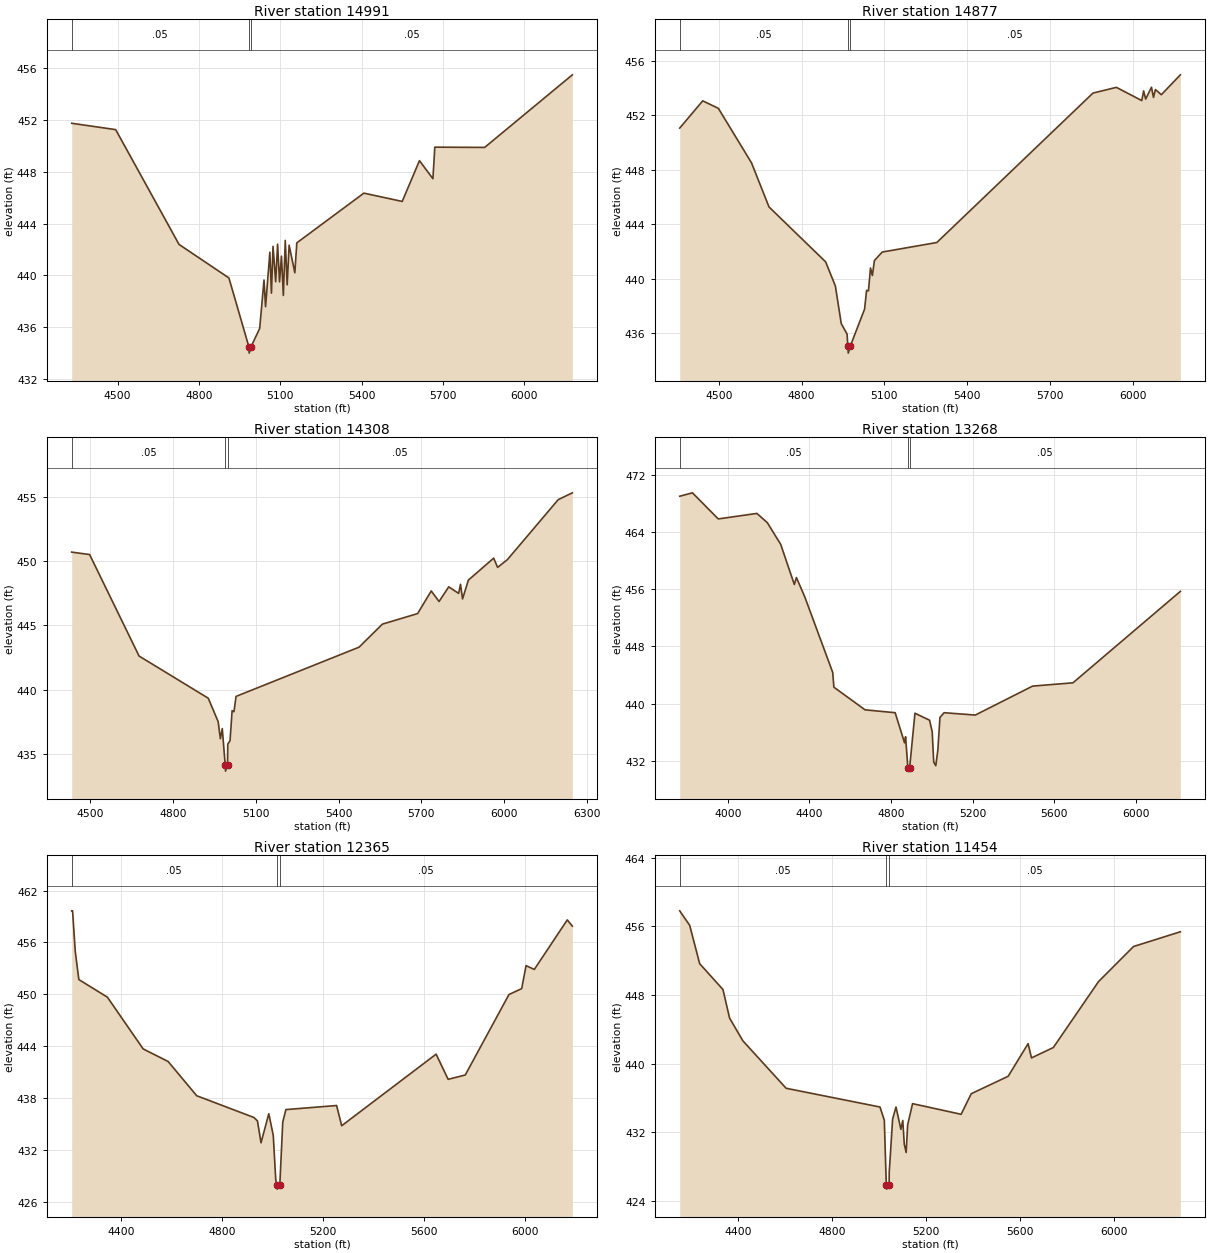
Type RM Length L Ch R = 1 ,14991   ,114,114,114
BEGIN DESCRIPTION:
Anthony Branch 25.0
END DESCRIPTION:
XS GIS Cut Line= 4
      2664168.75      6933304.75      2663673.94      6933755.14
      2663608.85      6933791.73      2662823.91      6934566.26
#Sta/Elev= 30
  4330.9  451.72  4493.1  451.23  4726.8  442.39  4910.7  439.81  4984.2  434.52
  4985.5  434.02  4992.6  434.52  5024.2  435.92  5040.2  439.65  5045.9   437.6
  5061.8  441.79  5067.6  438.64  5073.4  442.24  5083.2  439.52  5090.3  442.41
  5097.4  439.51  5104.5  441.49  5111.5  438.46  5118.6   442.7  5125.6  439.28
  5132.8  442.33  5153.9  440.21  5161.1  442.51  5408.5  446.34  5549.9   445.7
  5613.5  448.84  5663.1  447.45  5670.1  449.88    5854  449.86  6177.4  455.45
#Mann= 3 ,-1 , 0
  4330.9     .05       0  4984.2     .05       0  4992.6     .05       0
Bank Sta=4984.2,4992.6
XS Rating Curve= 0 ,0
Exp/Cntr=0.3,0.1

Type RM Length L Ch R = 1 ,14877   ,569,569,569
BEGIN DESCRIPTION:
Anthony Branch 24.0
END DESCRIPTION:
XS GIS Cut Line= 3
      2664138.82      6933195.79      2663676.21      6933640.94
      2662815.88      6934438.87
#Sta/Elev= 30
    4358  451.06  4441.5  453.06  4498.1  452.51  4618.3  448.51  4681.8  445.27
  4887.1  441.24  4922.4  439.47  4943.7  436.71  4964.8  435.94  4967.8  435.04
  4969.1  434.54  4976.2  435.04  5028.3  437.77  5035.6  439.15  5042.4  439.11
  5049.8  440.79  5056.6  440.24    5064  441.34  5092.3  441.96  5290.2  442.66
  5856.5  453.63  5941.4  454.05  6033.4  453.08  6040.2  453.79  6047.6  453.19
  6068.6  454.06  6075.9  453.31  6082.8  453.89  6104.3  453.51  6173.4  454.97
#Mann= 3 ,-1 , 0
    4358     .05       0  4967.8     .05       0  4976.2     .05       0
Bank Sta=4967.8,4976.2
XS Rating Curve= 0 ,0
Exp/Cntr=0.3,0.1

Type RM Length L Ch R = 1 ,14308   ,1040,1040,1040
BEGIN DESCRIPTION:
Anthony Branch 23.0
END DESCRIPTION:
XS GIS Cut Line= 3
       2663760.3      6932956.25      2663292.55      6933277.95
      2662458.38      6934206.08
#Sta/Elev= 30
  4432.3  450.69  4497.3   450.5  4676.6  442.61  4927.5  439.33  4963.4  437.51
  4971.5  436.18  4978.3  436.97  4988.9  434.16  4990.1  433.66  4997.4  434.16
  4998.3  435.76  5006.6  436.03    5014  438.36  5020.8  438.28  5028.3  439.47
  5474.5   443.3    5559  445.09  5686.8  445.91  5736.1  447.67  5764.5  446.85
  5799.6  447.99  5835.5  447.48  5842.2  448.19  5849.7  447.05  5870.7  448.51
  5962.6  450.22  5976.8   449.5  6012.5  450.11  6196.6  454.77  6247.9   455.3
#Mann= 3 ,-1 , 0
  4432.3     .05       0  4988.9     .04       0  4997.4     .05       0
Bank Sta=4988.9,4997.4
XS Rating Curve= 0 ,0
Exp/Cntr=0.3,0.1

Type RM Length L Ch R = 1 ,13268   ,903,903,903
BEGIN DESCRIPTION:
Anthony Branch 22.0
END DESCRIPTION:
XS GIS Cut Line= 3
      2662697.83      6931549.95      2662455.87      6932761.32
      2662222.49      6933957.87
#Sta/Elev= 30
  3764.7     469    3827  469.48  3953.6  465.83  4143.1   466.6  4194.1  465.31
  4259.7  462.28  4326.6  456.66  4336.8  457.63  4377.6  454.94  4514.8  444.36
  4520.4   442.3  4673.4  439.13  4820.9  438.73  4866.9  434.52    4872  435.37
  4883.1  431.06  4884.4  430.56  4891.9  431.06  4917.9  438.66  4989.5  437.68
  5002.4  436.07  5009.9  431.83  5020.1  431.32  5030.4  433.59  5040.4  438.06
  5060.8  438.73  5213.6   438.4  5494.7  442.45  5692.5  442.91  6219.1   455.7
#Mann= 3 ,-1 , 0
  3764.7     .05       0  4883.1     .04       0  4891.9     .05       0
Bank Sta=4883.1,4891.9
XS Rating Curve= 0 ,0
Exp/Cntr=0.3,0.1

Type RM Length L Ch R = 1 ,12365   ,911,911,911
BEGIN DESCRIPTION:
Anthony Branch 20.0
END DESCRIPTION:
XS GIS Cut Line= 3
      2662275.99      6931811.01        2661726.        6932361.
        2661626.      6933561.04
#Sta/Elev= 30
    4206  459.66  4209.5  459.66  4220.1  454.96  4234.3  451.71  4347.4  449.67
  4488.8  443.69  4587.8  442.23    4701  438.27  4927.2  435.76  4941.4  435.36
  4955.5  432.83  4986.3  436.19  5003.9  433.69  5013.9  428.52  5017.9  427.97
  5019.6  427.47  5029.9  427.97  5041.5  435.22    5054  436.67  5254.7  437.14
  5274.8   434.8  5648.6  443.08  5696.3  440.17    5764  440.67  5937.1  449.98
  5987.3  450.66  6004.8  453.32  6037.4  452.88  6167.9  458.61    6188  457.89
#Mann= 3 ,-1 , 0
    4206     .05       0  5017.9     .04       0  5029.9     .05       0
Bank Sta=5017.9,5029.9
XS Rating Curve= 0 ,0
Exp/Cntr=0.3,0.1

Type RM Length L Ch R = 1 ,11454   ,862,862,862
BEGIN DESCRIPTION:
Anthony Branch 18.0
END DESCRIPTION:
XS GIS Cut Line= 3
        2661676.        6931211.        2661076.        6931811.
      2660275.97      6932811.03
#Sta/Elev= 30
  4151.5  457.81  4193.9  456.12  4236.4  451.65  4335.4  448.64  4363.6  445.31
  4420.2  442.66  4604.1  437.13  5003.2  434.95  5021.6  433.41    5030  425.88
  5031.7  425.38  5042.1  425.88  5042.5  427.33  5056.9  433.53  5071.3  434.95
  5092.1  432.35  5100.1  433.38  5106.5  430.62  5114.5  429.65  5120.9  432.87
  5141.7  435.34  5348.2   434.1  5391.4   436.5  5548.3  438.53  5633.1  442.33
  5647.5  440.67  5740.4  441.88  5932.5  449.56  6081.4  453.65  6280.7  455.37
#Mann= 3 ,-1 , 0
  4151.5     .05       0    5030     .04       0  5042.1     .05       0
Bank Sta=5030,5042.1
XS Rating Curve= 0 ,0
Exp/Cntr=0.3,0.1