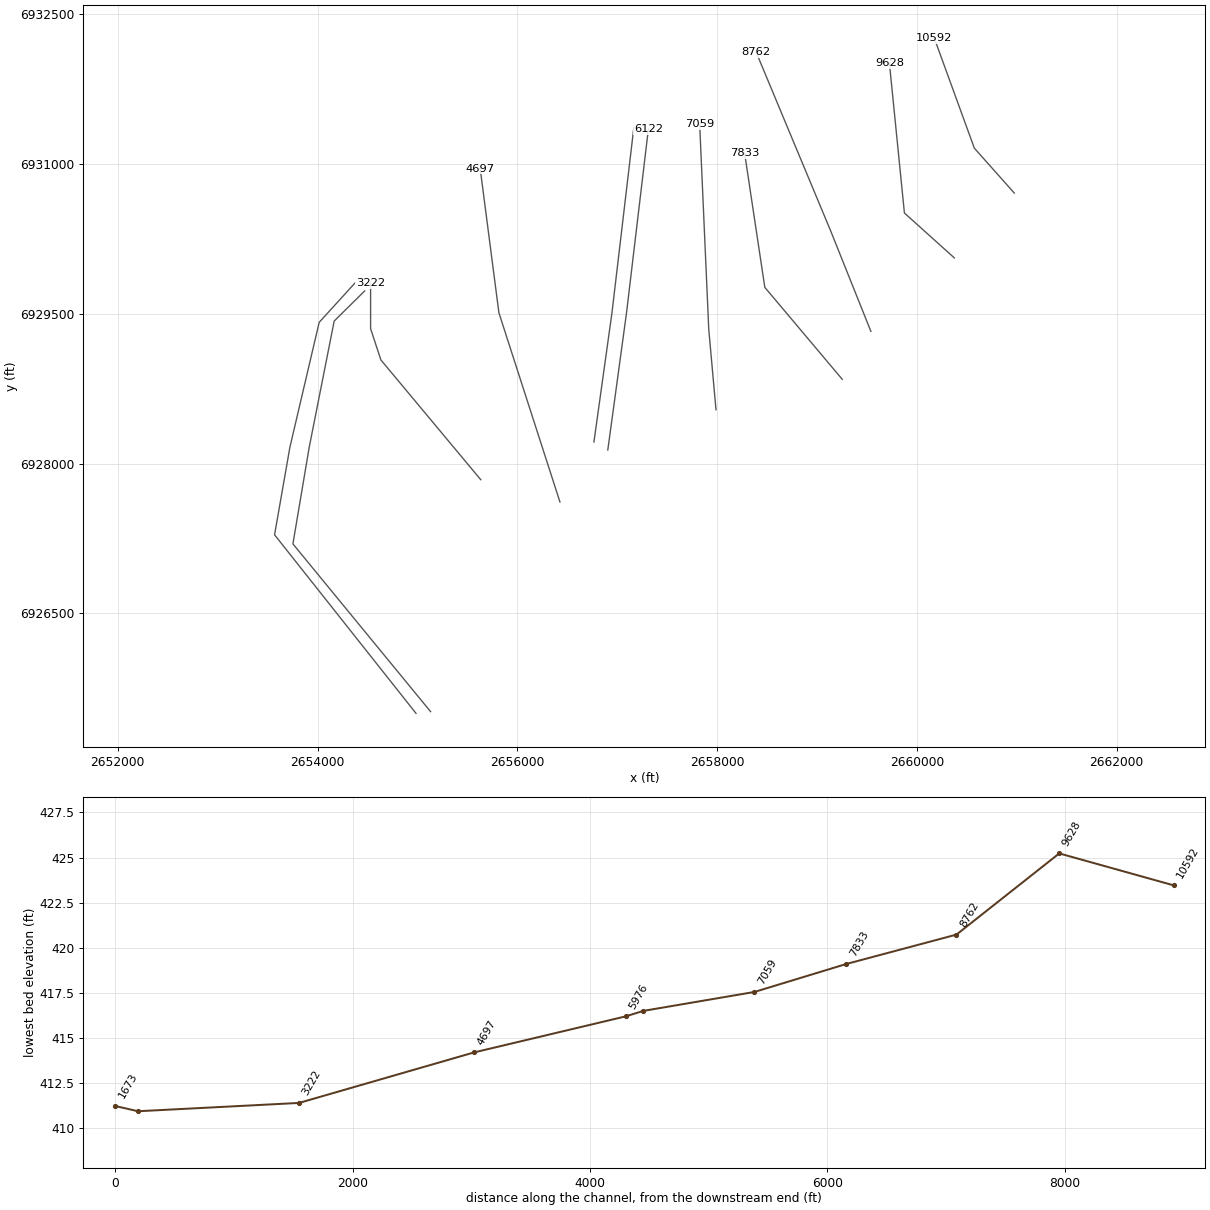
HEC-RAS study Anthony Branch.prj: Anthony Branch Base Level Engineering

--- Anthony Branch.g01 (geometry) --- (continued)

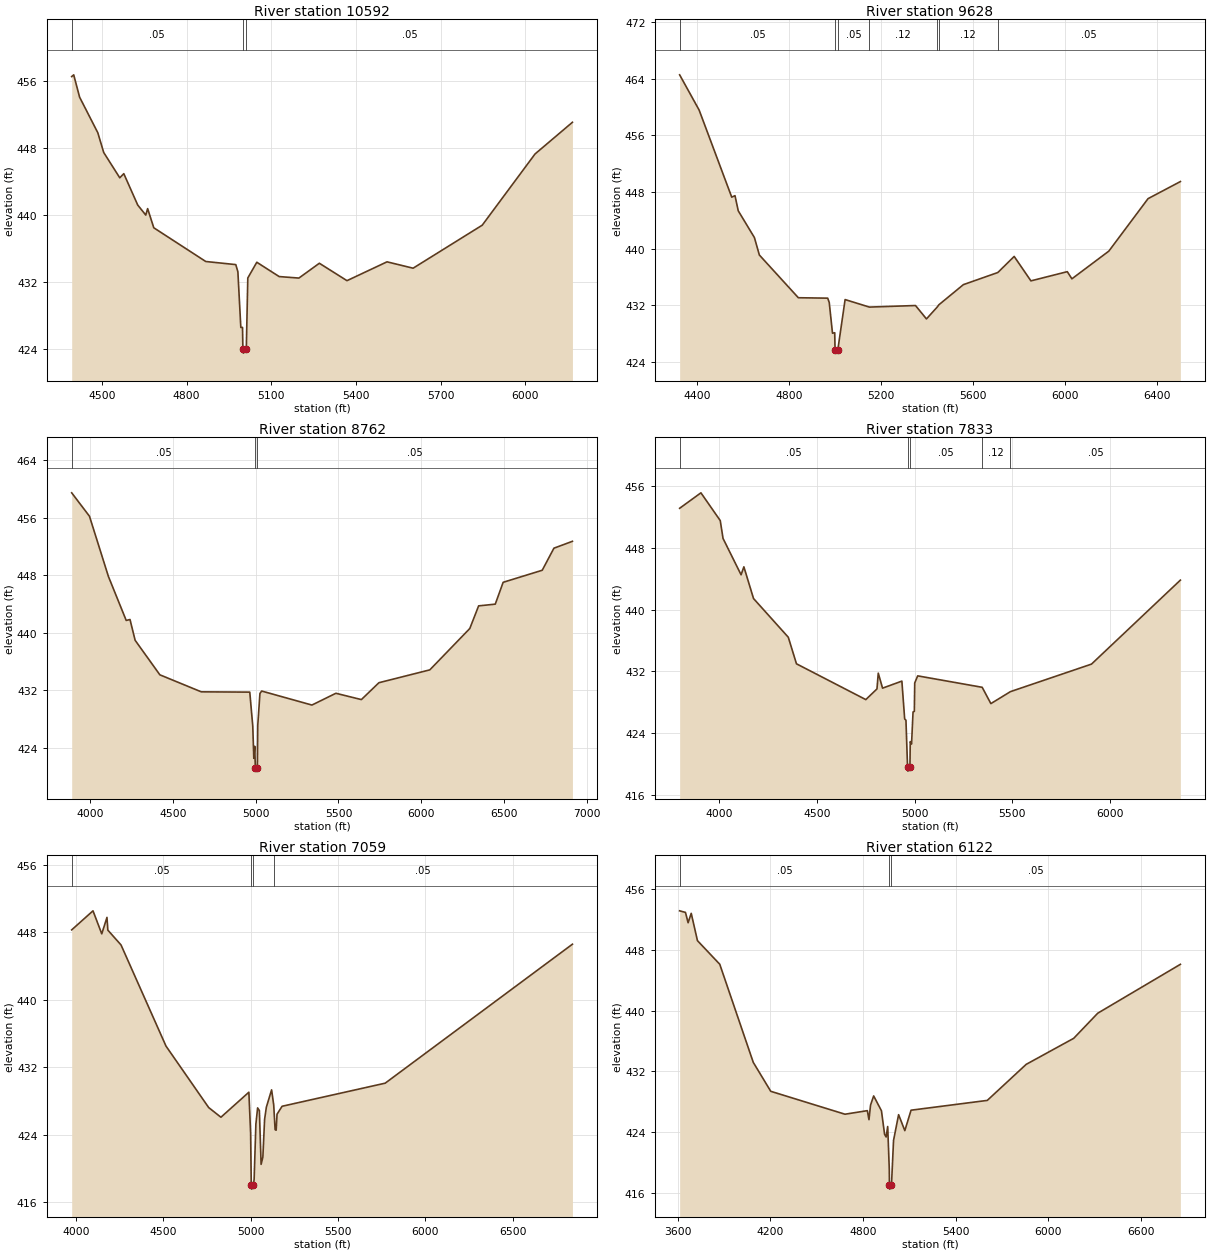
Type RM Length L Ch R = 1 ,10592   ,964,964,964
BEGIN DESCRIPTION:
Anthony Branch 16.0
END DESCRIPTION:
XS GIS Cut Line= 3
        2660976.        6930711.        2660576.        6931161.
      2660175.98      6932261.04
#Sta/Elev= 30
  4393.6  456.51  4400.7  456.72  4421.6  454.05    4486   449.8  4506.9  447.44
  4563.8  444.41    4578  444.91  4627.3  441.16  4655.8  439.96  4662.4  440.73
  4684.2  438.44  4868.2  434.41  4974.4  434.04  4981.9  433.18  4992.3  426.53
  4998.3  426.53  4999.6  423.96  5001.3  423.46  5011.7  423.96    5017  432.44
  5048.9  434.32    5128  432.61  5197.9  432.43  5270.3   434.2  5368.1  432.12
  5509.8  434.37  5602.2  433.61  5846.9  438.75  6033.8  447.26  6166.2  451.05
#Mann= 3 ,-1 , 0
  4393.6     .05       0  4999.6     .03       0  5011.7     .05       0
Bank Sta=4999.6,5011.7
XS Rating Curve= 0 ,0
Exp/Cntr=0.3,0.1

Type RM Length L Ch R = 1 ,9628    ,866,866,866
BEGIN DESCRIPTION:
Anthony Branch 14.0
END DESCRIPTION:
XS GIS Cut Line= 3
      2660375.97      6930061.03        2659876.        6930511.
        2659726.      6932010.98
#Sta/Elev= 30
  4323.2  464.52    4408  459.55    4550  447.25  4564.2  447.46  4578.4  445.32
  4648.7  441.55  4670.3  439.08    4840  433.05  4967.8  432.99  4974.5  432.38
  4988.7  428.04  4998.4  428.11  4999.8  425.73  5001.5  425.23    5012  425.73
  5043.6  432.79  5149.4  431.73  5350.1  431.95  5397.8  430.06  5444.5  431.73
  5451.7  432.05  5558.6   434.9  5708.5  436.61  5779.7  438.88  5852.6  435.43
  6010.9  436.73    6031  435.72  6191.8  439.63  6362.6  447.04  6503.3  449.45
#Mann= 7 ,-1 , 0
  4323.2     .05       0  4999.8     .03       0    5012     .05       0
  5149.4     .12       0  5444.5     .05       0  5451.7     .12       0
  5708.5     .05       0
Bank Sta=4999.8,5012
XS Rating Curve= 0 ,0
Exp/Cntr=0.3,0.1

Type RM Length L Ch R = 1 ,8762    ,929,929,929
BEGIN DESCRIPTION:
Anthony Branch 12.0
END DESCRIPTION:
XS GIS Cut Line= 3
      2659540.38      6929325.07      2659140.39      6930325.06
       2658390.7       6932124.3
#Sta/Elev= 30
  3887.9  459.48  3995.3  456.22  4109.7  447.84  4217.4  441.71  4240.3  441.84
  4271.2  438.95  4420.7  434.14  4671.1  431.77  4964.1  431.73  4982.2     427
  4988.5  422.51  4993.9  424.19  4997.8  421.23  4999.5  420.73    5010  421.23
  5012.3  427.09  5025.5  431.54  5036.1  431.88  5339.7  429.93  5484.6  431.57
  5638.5  430.69  5744.6  433.04  6052.3  434.83  6293.9  440.59  6347.2  443.74
  6447.7  443.98  6495.4  447.02  6731.6   448.7  6802.2  451.77  6914.1  452.73
#Mann= 3 ,-1 , 0
  3887.9     .05       0  4997.8     .03       0    5010     .05       0
Bank Sta=4997.8,5010
XS Rating Curve= 0 ,0
Exp/Cntr=0.3,0.1

Type RM Length L Ch R = 1 ,7833    ,774,774,774
BEGIN DESCRIPTION:
Anthony Branch 10.0
END DESCRIPTION:
XS GIS Cut Line= 3
      2659253.37      6928845.13      2658478.31      6929766.09
      2658276.01      6931110.96
#Sta/Elev= 30
  3796.3  453.09  3905.3  455.09  4004.2   451.5  4018.5  449.19  4110.9  444.49
  4125.2  445.52  4174.6  441.42  4352.7  436.41  4394.4  432.98  4749.4  428.35
  4806.6  429.73  4813.2  431.77  4835.2  429.83  4934.1  430.74  4948.4  425.85
    4955  425.68  4963.2   419.6  4964.9   419.1  4975.4   419.6    4977  422.92
  4983.6   422.6  4991.3  426.75  4997.9  426.83  4999.9   430.5  5015.1  431.42
  5345.3  429.94  5389.8  427.83  5489.9  429.38    5905  432.94    6360   443.8
#Mann= 5 ,-1 , 0
  3796.3     .05       0  4963.2     .03       0  4975.4     .05       0
  5345.3     .12       0  5489.9     .05       0
Bank Sta=4963.2,4975.4
XS Rating Curve= 0 ,0
Exp/Cntr=0.3,0.1

Type RM Length L Ch R = 1 ,7059    ,937,937,937
BEGIN DESCRIPTION:
Anthony Branch 8.0
END DESCRIPTION:
XS GIS Cut Line= 3
       2657989.5      6928539.52      2657917.08      6929345.27
      2657825.94      6931402.56
#Sta/Elev= 30
    3975  448.31    4097  450.57  4147.2  447.84    4177  449.79    4182  448.28
  4257.6  446.52  4515.2  434.52  4759.6  427.23  4829.8  426.08  4989.9  429.05
  4999.9  424.19  5003.6  418.05  5005.4  417.55  5016.2  418.05    5020  418.73
    5030  425.27    5040  427.19    5050  426.87    5060  420.49    5070  421.35
    5080  425.83    5090  427.27  5120.1  429.33  5132.2  427.53  5140.1  424.61
  5146.2  424.54  5151.2  426.44  5180.1  427.38  5770.7  430.12  6843.3  446.61
#Mann= 4 ,-1 , 0
    3975     .05       0  5003.6     .03       0  5016.2     .05       0
  5132.2     .05       0
Bank Sta=5003.6,5016.2
XS Rating Curve= 0 ,0
Exp/Cntr=0.3,0.1

Type RM Length L Ch R = 1 ,6122    ,146,146,146
BEGIN DESCRIPTION:
Anthony Branch 7.0
END DESCRIPTION:
XS GIS Cut Line= 3
      2656906.16      6928136.74      2657093.66        6929511.
      2657312.41      6931352.05
#Sta/Elev= 30
    3613  453.17  3650.7  452.96  3667.8   451.6    3688  452.84  3728.3  449.24
  3872.7  446.13  4089.6   433.2  4202.7  429.39  4683.2  426.37  4827.9  426.84
  4838.5  425.65  4848.6  427.57  4868.8  428.78  4919.3  426.82  4939.4  423.73
  4949.5  423.37  4959.6  424.75  4969.7  419.26  4971.1     417  4972.9   416.5
    4984     417  4997.5  422.92  5030.2  426.31  5070.5  424.21  5110.8   426.9
  5604.2  428.19    5856  432.94  6163.6  436.37  6319.2  439.68    6854  446.12
#Mann= 3 ,-1 , 0
    3613     .05       0  4971.1     .07       0    4984     .05       0
Bank Sta=4971.1,4984
XS Rating Curve= 0 ,0
Exp/Cntr=0.3,0.1

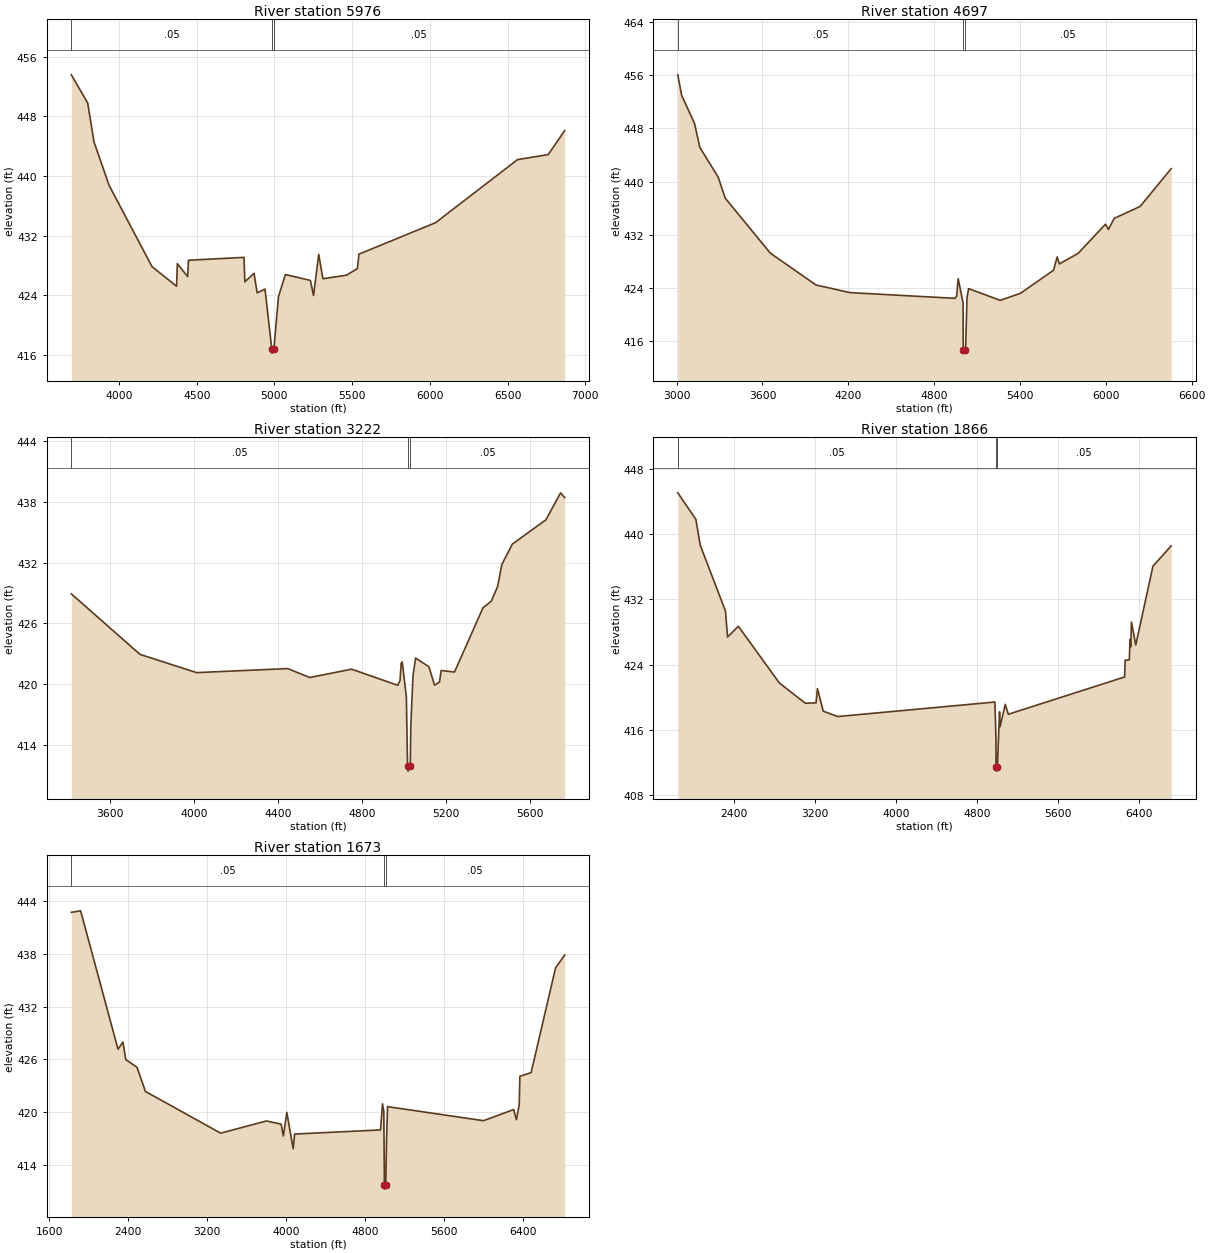
Type RM Length L Ch R = 1 ,5976    ,1279,1279,1279
BEGIN DESCRIPTION:
Anthony Branch 6.0
END DESCRIPTION:
XS GIS Cut Line= 3
      2656767.27      6928216.65      2656947.83      6929511.01
      2657166.58      6931365.96
#Sta/Elev= 30
  3693.1   453.6  3798.5  449.81  3838.9   444.6    3936  438.75  4212.4  427.82
  4370.2  425.19  4375.3  428.22  4441.8  426.49  4446.8  428.68  4804.4  429.07
  4809.5  425.78  4868.7  426.93  4888.9   424.3  4939.4  424.81  4983.4   416.7
  4985.3   416.2  4996.3   416.7  5026.1  423.79  5070.5  426.76  5231.6  425.97
  5251.7  423.94  5285.1  429.48  5312.1   426.2  5463.2  426.67  5533.7  427.56
  5544.1   429.5  6037.1  433.73  6564.9  442.21  6762.1  442.88  6867.8   446.1
#Mann= 3 ,-1 , 0
  3693.1     .05       0  4983.4     .03       0  4996.3     .05       0
Bank Sta=4983.4,4996.3
XS Rating Curve= 0 ,0
Exp/Cntr=0.3,0.1

Type RM Length L Ch R = 1 ,4697    ,1475,1475,1475
BEGIN DESCRIPTION:
Anthony Branch 5.0
END DESCRIPTION:
XS GIS Cut Line= 3
      2656427.01      6927615.91       2655815.8      6929511.41
       2655628.4       6930956.1
#Sta/Elev= 30
  3008.4  456.05  3034.8  452.98  3124.9  448.75  3162.2  445.14  3290.4  440.67
  3339.5  437.51  3654.7  429.24    3974  424.45  4211.5   423.3  4946.1  422.44
  4957.5  422.77  4968.1  425.39  5002.3  421.75  5003.2   414.7  5005.1   414.2
  5016.1   414.7  5019.8  414.85  5029.8  422.54  5041.1   423.9  5261.8  422.14
  5402.9  423.19  5634.9  426.67  5659.6  428.66  5675.2  427.62  5806.3   429.2
  5997.9  433.59    6018   432.8  6058.4  434.46  6239.9  436.26  6456.8  441.94
#Mann= 3 ,-1 , 0
  3008.4     .05       0  5003.2     .03       0  5016.1     .05       0
Bank Sta=5003.2,5016.1
XS Rating Curve= 0 ,0
Exp/Cntr=0.3,0.1

Type RM Length L Ch R = 1 ,3222    ,1356,1356,1356
BEGIN DESCRIPTION:
Anthony Branch 4.0
END DESCRIPTION:
XS GIS Cut Line= 4
      2655634.34      6927838.77      2654634.33      6929038.78
      2654531.16      6929352.06      2654531.16      6929810.37
#Sta/Elev= 30
  3414.3  428.93  3741.8  422.94  4011.3  421.14  4444.8  421.54  4550.2  420.66
  4749.4  421.48  4969.3  419.89  4980.2  420.37  4985.5  422.04  4990.7   422.2
  5010.3  418.77    5016   411.9  5017.9   411.4    5029   411.9  5031.3  415.79
  5041.9  420.82  5054.3  422.58  5117.9  421.72  5144.4  419.91  5168.2   420.2
  5176.1  421.35  5239.7   421.2  5375.1  427.54  5415.1  428.21  5445.1  429.66
  5465.1  431.83  5515.1  433.85  5675.1  436.25  5745.1  438.92  5764.5  438.45
#Mann= 3 ,-1 , 0
  3414.3     .05       0    5016     .03       0    5029     .05       0
Bank Sta=5016,5029
XS Rating Curve= 0 ,0
Exp/Cntr=0.3,0.1

Type RM Length L Ch R = 1 ,1866    ,193,193,193
BEGIN DESCRIPTION:
Anthony Branch 3.0
END DESCRIPTION:
XS GIS Cut Line= 5
      2655131.88      6925515.23      2653753.38      6927195.81
        2653916.      6928160.99      2654166.58      6929428.45
       2654471.6        6929730.
#Sta/Elev= 30
  1847.6  445.05    2026  441.79  2069.1  438.63  2318.1  430.56  2338.9  427.38
  2445.9  428.69    2851  421.74  3106.8  419.26  3213.1  419.31  3226.7  421.06
  3284.1  418.29  3426.1  417.63  4979.7  419.41  4989.9  415.08    4991  411.44
  4992.8  410.94    5004  411.44  5025.5  418.22  5030.7  416.39    5082  419.12
  5112.1  417.91  6261.1  422.48  6266.2  424.52  6307.5  424.59  6314.6  427.07
  6321.6  426.18  6328.8  429.21  6371.2   426.4  6540.9  436.06  6720.9  438.55
#Mann= 3 ,-1 , 0
  1847.6     .05       0    4991     .03       0    5004     .05       0
Bank Sta=4991,5004
XS Rating Curve= 0 ,0
Exp/Cntr=0.3,0.1

Type RM Length L Ch R = 1 ,1673    ,0,0,0
BEGIN DESCRIPTION:
Anthony Branch 2.0
END DESCRIPTION:
XS GIS Cut Line= 5
      2654986.03      6925497.89      2653569.59      6927287.13
      2653723.65      6928166.71      2654016.43      6929415.56
      2654376.01      6929811.01
#Sta/Elev= 30
    1825  442.74  1919.1  442.91  2297.4  427.15  2347.1  427.97  2375.9  425.98
  2489.7   425.1  2574.6  422.35  3335.9   417.6  3799.1  418.99  3948.1  418.63
  3970.6  417.28  4005.8  419.96  4069.9  415.82  4084.4   417.5  4953.6  417.97
  4973.9  420.94  4986.9  420.08  4993.1  411.73  4994.9  411.23  5006.1  411.73
  5014.7  416.92    5025  420.62  5995.8  419.02  6300.6  420.29    6329  419.13
  6357.4  420.86  6364.1  424.08  6477.6  424.49    6725  436.42  6817.2  437.88
#Mann= 3 ,-1 , 0
    1825     .05       0  4993.1     .03       0  5006.1     .05       0
Bank Sta=4993.1,5006.1
XS Rating Curve= 0 ,0
Exp/Cntr=0.3,0.1

Chan Stop Cuts=-1
Use User Specified Reach Order=0
Composite Channel Slope=5