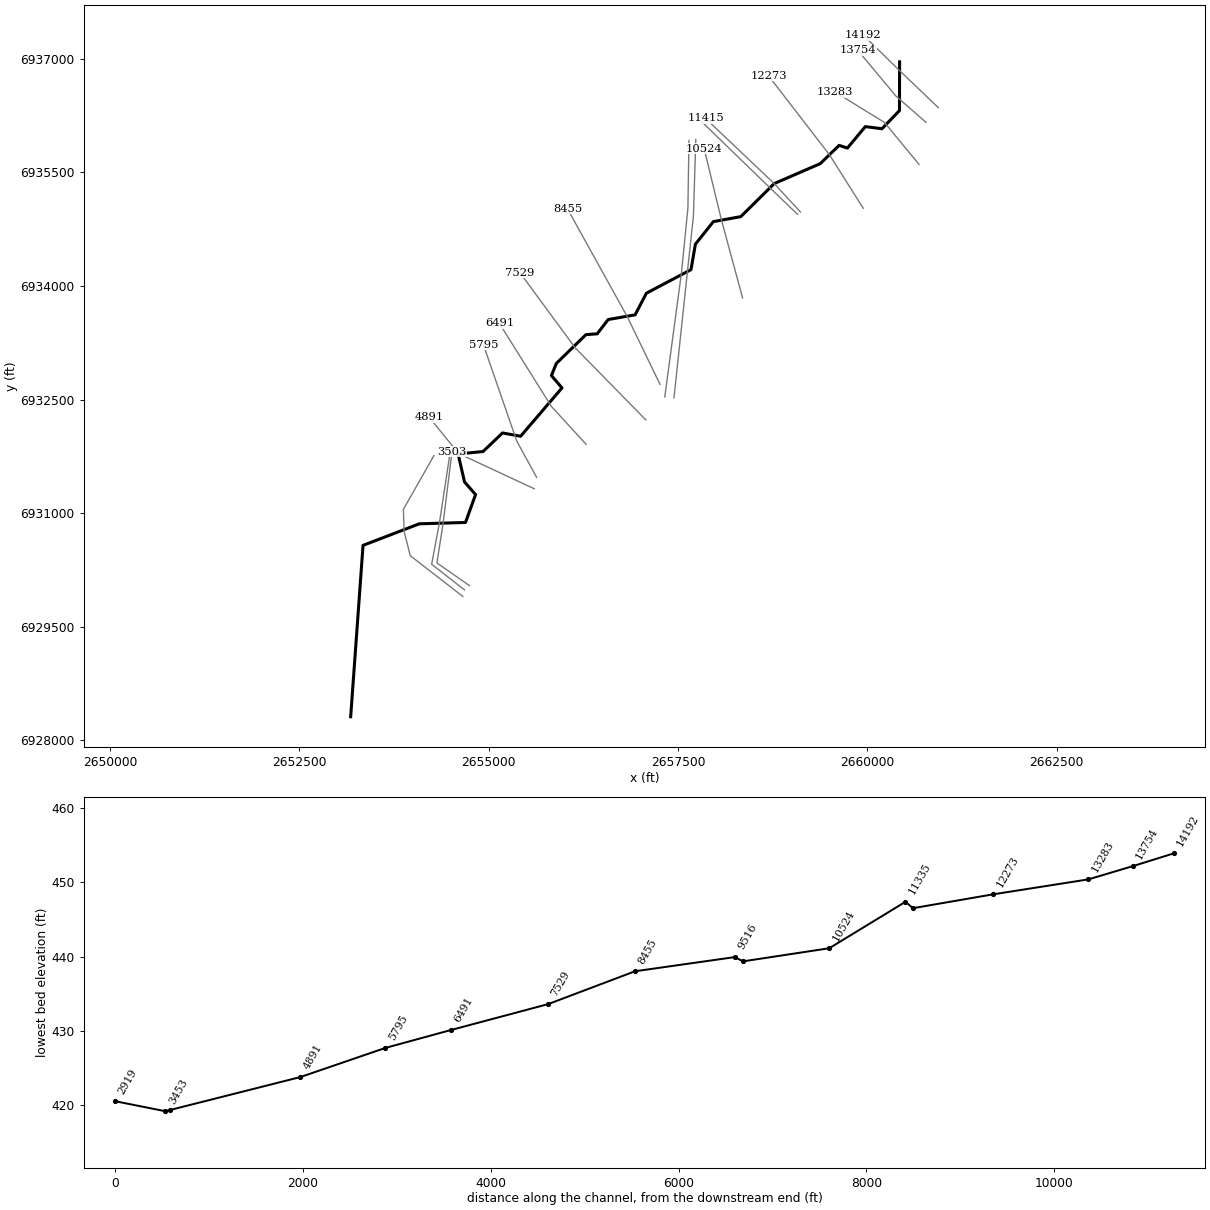
--- Anthony Branch Trib 1.prj (project) ---

Proj Title=Anthony Branch Trib 1 Base Level Engineering
Current Plan=p01
Default Exp/Contr=0.3,0.1
English Units
Geom File=g01
Flow File=f01
Plan File=p01
BEGIN DESCRIPTION:
Anthony Branch Trib 1
END DESCRIPTION:

--- Anthony Branch Trib 1.p01 (plan) ---

Plan Title=Multiple Run
Short Identifier=Multiple
Geom File=g01
Flow File=f01
Subcritical Flow
K Sum by GR= 0
Std Step Tol= 0.01
Critical Tol= 0.01
Num of Std Step Trials= 20
Max Error Tol= 0.3
Flow Tol Ratio= 0.001
Split Flow NTrial= 30
Split Flow Tol= 0.02
Split Flow Ratio= 0.02
Log Output Level= 0
Friction Slope Method= 1
Unsteady Friction Slope Method= 2
Unsteady Bridges Friction Slope Method= 1
Parabolic Critical Depth
Global Vel Dist=  1 , 1 , 1
Global Log Level= 0
CheckData=True
Encroach Param= -1, 0, 0, 0
BEGIN DESCRIPTION:
Multiple Run
END DESCRIPTION:

--- Anthony Branch Trib 1.f01 (steady flow) ---

Flow Title=Multiple
Number of Profiles=7
Profile Names=10-year,25-year,50-year,1pct_min,100-year,1pct_plu,500-year
River Rch & RM= Anthony Branch T,Reach-1,14192
     394     511     602     352     702    1401     954
River Rch & RM= Anthony Branch T,Reach-1,12273
     552     731     874     518    1033    2061    1442
River Rch & RM= Anthony Branch T,Reach-1,8455
     699     937    1128     673    1342    2678    1900
Boundary for River Rch & Prof#=Anthony Branch T,Reach-1,1
Up Type=0
Dn Type=3
Dn Slope=0.005
Boundary for River Rch & Prof#=Anthony Branch T,Reach-1,2
Up Type=0
Dn Type=3
Dn Slope=0.005
Boundary for River Rch & Prof#=Anthony Branch T,Reach-1,3
Up Type=0
Dn Type=3
Dn Slope=0.005
Boundary for River Rch & Prof#=Anthony Branch T,Reach-1,4
Up Type=0
Dn Type=3
Dn Slope=0.005
Boundary for River Rch & Prof#=Anthony Branch T,Reach-1,5
Up Type=0
Dn Type=3
Dn Slope=0.005
Boundary for River Rch & Prof#=Anthony Branch T,Reach-1,6
Up Type=0
Dn Type=3
Dn Slope=0.005
Boundary for River Rch & Prof#=Anthony Branch T,Reach-1,7
Up Type=0
Dn Type=3
Dn Slope=0.005

--- Anthony Branch Trib 1.g01 (geometry) ---

Geom Title=Existing Conditions

River Reach=Anthony Branch T,Reach-1
Reach XY= 30
      2660426.00      6936961.00      2660424.46      6936316.85
      2660193.08      6936077.14      2659973.55      6936105.55
      2659736.37      6935821.98      2659627.65      6935857.84
      2659378.43      6935616.52      2658769.94      6935352.86
      2658328.45      6934916.47      2657966.18      6934850.53
      2657729.10      6934552.69      2657670.96      6934216.08
      2657081.77      6933905.02      2656932.70      6933619.13
      2656577.25      6933557.55      2656432.20      6933368.81
      2656283.98      6933358.05      2655892.48      6932978.05
      2655827.61      6932817.04      2655967.03      6932654.34
      2655420.56      6932016.17      2655182.03      6932059.38
      2654924.37      6931814.13      2654595.09      6931781.52
      2654679.54      6931412.47      2654825.63      6931245.84
      2654692.71      6930877.20      2654082.04      6930859.37
      2653339.26      6930574.66      2653176.00      6928311.00

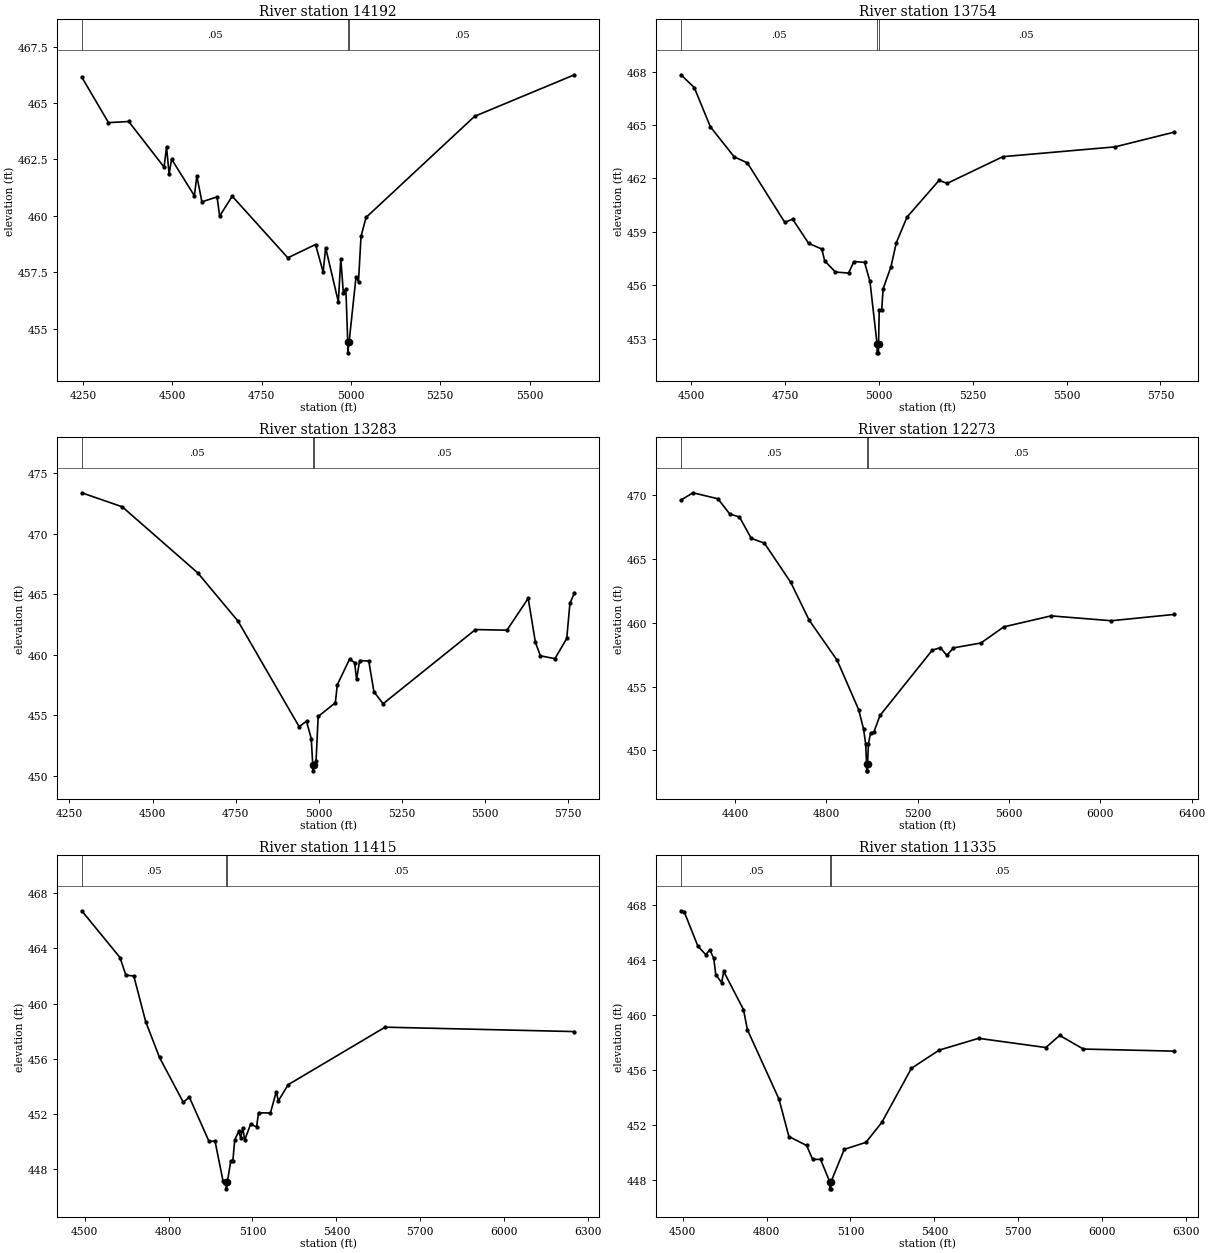
Type RM Length L Ch R = 1,14192,438,438,438
BEGIN DESCRIPTION:
Anthony Branch Trib 1 25.0
END DESCRIPTION:
XS GIS Cut Line= 3
      2660937.06      6936356.06      2660392.24      6936877.59
      2659945.78      6937316.11
#Sta/Elev= 30
  4245.8  466.15  4320.7  464.13  4377.3  464.18  4476.4  462.16  4483.3  463.05
  4490.5  461.85  4497.5  462.51  4561.3  460.89  4568.2  461.76  4582.4  460.62
  4624.8  460.84  4632.1  459.99  4667.3  460.87  4823.0  458.14  4900.6  458.73
  4922.0  457.51  4928.9  458.59  4964.5  456.19  4971.4  458.10  4978.6  456.58
  4985.6  456.76  4990.8  454.43  4991.0  453.93  4994.8  454.43  5013.9  457.28
  5021.0  457.09  5028.0  459.09  5042.2  459.93  5346.2  464.41  5625.8  466.25
#Mann=3,-1,0
  4245.8    0.05       0  4990.8    0.05       0  4994.8    0.05       0
Bank Sta=4990.8,4994.8
Exp/Cntr=0.3,0.1

Type RM Length L Ch R = 1,13754,471,471,471
BEGIN DESCRIPTION:
Anthony Branch Trib 1 24.0
END DESCRIPTION:
XS GIS Cut Line= 3
      2660775.98      6936161.02      2660376.00      6936511.00
      2659876.00      6937111.00
#Sta/Elev= 30
  4472.6  467.82  4508.2  467.10  4550.9  464.90  4614.5  463.21  4649.6  462.87
  4749.2  459.53  4770.1  459.71  4812.8  458.35  4847.9  458.03  4855.5  457.37
  4884.0  456.74  4919.1  456.68  4933.4  457.33  4961.8  457.28  4976.1  456.21
  4995.0  452.70  4995.2  452.20  4998.7  452.20  4999.0  452.70  5000.8  454.58
  5007.3  454.58  5011.2  455.80  5032.1  457.04  5046.4  458.39  5075.0  459.83
  5160.3  461.89  5181.8  461.72  5330.2  463.22  5628.9  463.77  5785.1  464.59
#Mann=3,-1,0
  4472.6    0.05       0  4995.0    0.04       0  4999.0    0.05       0
Bank Sta=4995,4999
Exp/Cntr=0.3,0.1

Type RM Length L Ch R = 1,13283,1010,1010,1010
BEGIN DESCRIPTION:
Anthony Branch Trib 1 23.0
END DESCRIPTION:
XS GIS Cut Line= 3
      2660682.27      6935606.61      2660226.00      6936161.00
      2659576.02      6936560.99
#Sta/Elev= 30
  4287.1  473.39  4408.9  472.23  4635.6  466.78  4756.9  462.79  4940.6  454.07
  4962.8  454.52  4977.1  453.08  4981.6  450.92  4981.8  450.42  4985.6  450.92
  4991.5  451.21  4997.9  454.91  5049.5  456.04  5055.4  457.53  5092.1  459.64
  5107.5  459.36  5113.3  457.97  5122.5  459.53  5150.0  459.49  5165.5  456.95
  5193.0  455.96  5470.7  462.09  5565.4  462.04  5629.3  464.67  5650.9  461.04
  5665.9  459.92  5709.6  459.69  5745.2  461.36  5754.7  464.25  5768.3  465.13
#Mann=3,-1,0
  4287.1    0.05       0  4981.6    0.03       0  4985.6    0.05       0
Bank Sta=4981.6,4985.6
Exp/Cntr=0.3,0.1

Type RM Length L Ch R = 1,12273,858,858,858
BEGIN DESCRIPTION:
Anthony Branch Trib 1 21.0
END DESCRIPTION:
XS GIS Cut Line= 3
      2659946.16      6935026.74      2659499.17      6935734.16
      2658692.66      6936780.25
#Sta/Elev= 30
  4163.2  469.57  4215.9  470.14  4325.3  469.67  4377.0  468.48  4419.4  468.25
  4471.1  466.58  4528.8  466.20  4644.1  463.14  4724.2  460.20  4847.6  457.04
  4941.7  453.18  4962.9  451.68  4972.3  450.50  4976.2  448.91  4976.4  448.41
  4979.9  448.41  4980.2  448.91  4984.4  450.53  4993.5  451.36  5007.9  451.43
  5035.0  452.74  5263.3  457.83  5299.1  458.04  5327.6  457.43  5356.6  458.02
  5477.1  458.40  5576.9  459.66  5784.2  460.52  6047.8  460.14  6320.9  460.63
#Mann=3,-1,0
  4163.2    0.05       0  4976.2    0.04       0  4980.2    0.05       0
Bank Sta=4976.2,4980.2
Exp/Cntr=0.3,0.1

Type RM Length L Ch R = 1,11415,80,80,80
BEGIN DESCRIPTION:
Anthony Branch Trib 1 20.0
END DESCRIPTION:
XS GIS Cut Line= 3
      2659116.25      6934978.19      2658769.94      6935352.86
      2657862.79      6936214.29
#Sta/Elev= 30
  4489.8  466.74  4626.6  463.34  4647.5  462.06  4675.9  462.00  4718.4  458.68
  4767.8  456.08  4852.8  452.82  4874.3  453.20  4944.7  449.98  4966.2  450.00
  4994.6  447.13  5006.4  447.03  5006.7  446.53  5010.4  447.03  5022.6  448.57
  5029.9  448.56  5036.8  450.10  5050.9  450.70  5058.2  450.25  5065.1  450.97
  5072.3  450.08  5093.4  451.23  5114.8  451.03  5121.7  452.06  5164.2  452.04
  5185.2  453.59  5192.5  452.92  5227.7  454.10  5574.3  458.28  6251.0  457.96
#Mann=3,-1,0
  4489.8    0.05       0  5006.4    0.04       0  5010.4    0.05       0
Bank Sta=5006.4,5010.4
Exp/Cntr=0.3,0.1

Type RM Length L Ch R = 1,11335,811,811,811
BEGIN DESCRIPTION:
Anthony Branch Trib 1 19.0
END DESCRIPTION:
XS GIS Cut Line= 3
      2659078.07      6934946.93      2658712.62      6935297.77
      2657810.86      6936172.48
#Sta/Elev= 30
  4493.4  467.60  4504.8  467.54  4554.2  465.02  4582.5  464.41  4596.7  464.76
  4610.8  464.14  4618.1  462.95  4639.1  462.38  4646.4  463.19  4717.1  460.42
  4731.3  458.95  4844.2  453.91  4879.7  451.19  4943.2  450.54  4964.6  449.53
  4992.9  449.53  5026.1  447.89  5026.4  447.39  5029.9  447.39  5030.1  447.89
  5077.8  450.26  5155.5  450.77  5212.1  452.22  5318.1  456.15  5417.1  457.47
  5558.6  458.33  5799.1  457.66  5848.5  458.54  5933.3  457.55  6256.3  457.40
#Mann=3,-1,0
  4493.4    0.05       0  5026.1    0.03       0  5030.1    0.05       0
Bank Sta=5026.1,5030.1
Exp/Cntr=0.3,0.1

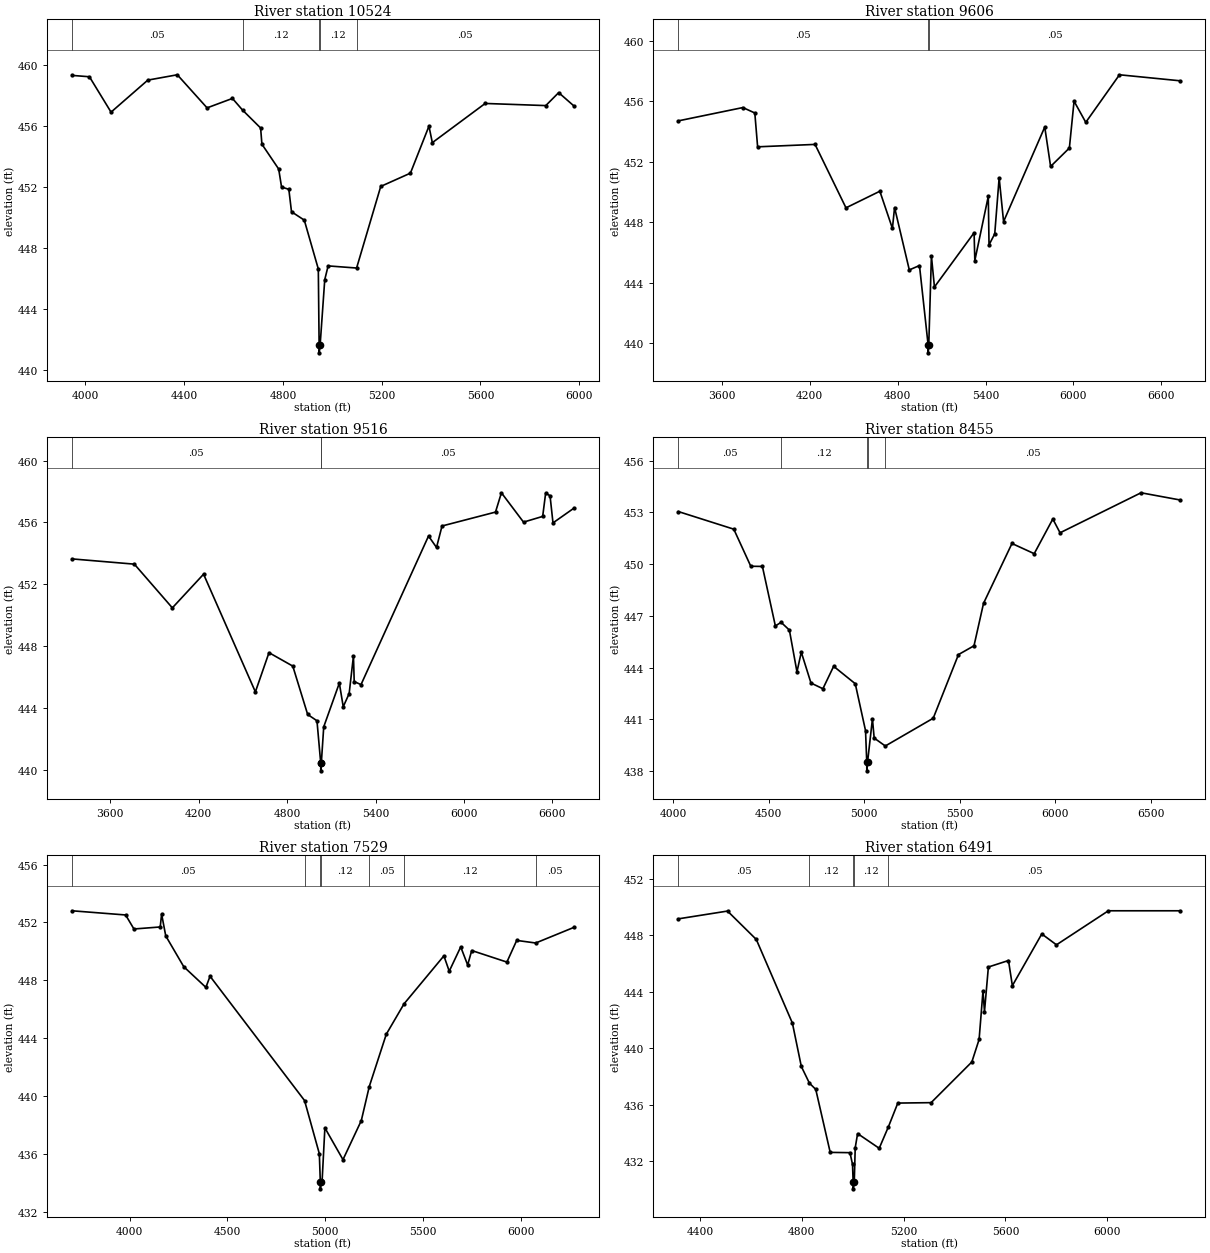
Type RM Length L Ch R = 1,10524,918,918,918
BEGIN DESCRIPTION:
Anthony Branch Trib 1 17.0
END DESCRIPTION:
XS GIS Cut Line= 3
      2658352.40      6933842.71      2658076.00      6934861.00
      2657845.45      6935811.50
#Sta/Elev= 30
  3945.2  459.31  4016.0  459.22  4103.6  456.90  4252.5  459.00  4372.0  459.35
  4492.6  457.18  4595.3  457.80  4636.6  457.03  4709.5  455.86  4714.7  454.80
  4782.7  453.17  4794.3  451.99  4823.8  451.84  4834.6  450.37  4886.4  449.82
  4943.2  446.62  4946.5  441.62  4946.8  441.12  4950.5  441.62  4969.3  445.92
  4983.0  446.82  5098.3  446.68  5196.1  452.03  5316.3  452.90  5391.4  455.98
  5405.1  454.90  5619.2  457.47  5864.7  457.33  5916.9  458.18  5978.4  457.31
#Mann=5,-1,0
  3945.2    0.05       0  4636.6    0.12       0  4946.5    0.07       0
  4950.5    0.12       0  5098.3    0.05       0
Bank Sta=4946.5,4950.5
Exp/Cntr=0.3,0.1

Type RM Length L Ch R = 1,9606,90,90,90
BEGIN DESCRIPTION:
Anthony Branch Trib 1 15.0
END DESCRIPTION:
XS GIS Cut Line= 4
      2657446.14      6932523.26      2657626.00      6934211.00
      2657703.08      6934926.08      2657734.33      6935936.28
#Sta/Elev= 30
  3302.9  454.71  3743.1  455.59  3824.6  455.23  3843.7  452.99  4235.9  453.15
  4447.1  448.95  4678.4  450.05  4764.1  447.59  4778.9  448.97  4879.5  444.84
  4948.9  445.13  5008.3  439.85  5008.5  439.35  5012.3  439.85  5030.4  445.76
  5051.2  443.71  5321.9  447.30  5326.9  445.46  5418.8  449.71  5423.9  446.50
  5462.9  447.23  5493.0  450.94  5523.2  448.04  5804.4  454.30  5844.4  451.69
  5972.5  452.91  6004.5  456.01  6084.5  454.61  6314.6  457.76  6730.1  457.36
#Mann=3,-1,0
  3302.9    0.05       0  5008.3    0.03       0  5012.3    0.05       0
Bank Sta=5008.3,5012.3
Exp/Cntr=0.3,0.1

Type RM Length L Ch R = 1,9516,1061,1061,1061
BEGIN DESCRIPTION:
Anthony Branch Trib 1 14.0
END DESCRIPTION:
XS GIS Cut Line= 4
      2657324.61      6932535.78      2657545.90      6934181.27
      2657630.17      6935030.25      2657644.06      6935922.59
#Sta/Elev= 30
  3339.7  453.64  3763.2  453.30  4021.0  450.47  4232.9  452.65  4584.5  445.03
  4676.8  447.57  4838.3  446.70  4939.2  443.57  5002.4  443.16  5027.9  440.42
  5028.1  439.92  5031.9  440.42  5048.3  442.77  5154.2  445.60  5180.6  444.07
  5220.8  444.92  5250.0  447.36  5255.1  445.70  5301.2  445.50  5759.4  455.12
  5813.7  454.38  5851.0  455.77  6213.9  456.67  6254.0  457.92  6404.0  456.02
  6534.0  456.39  6554.1  457.89  6584.0  457.73  6604.0  455.97  6745.6  456.92
#Mann=3,-1,0
  3339.7    0.05       0  5027.9    0.04       0  5031.9    0.05       0
Bank Sta=5027.9,5031.9
Exp/Cntr=0.3,0.1

Type RM Length L Ch R = 1,8455,926,926,926
BEGIN DESCRIPTION:
Anthony Branch Trib 1 11.0
END DESCRIPTION:
XS GIS Cut Line= 3
      2657262.10      6932700.41      2656828.73      6933596.06
      2656038.80      6935020.85
#Sta/Elev= 30
  4028.8  453.04  4318.3  452.02  4407.2  449.87  4467.9  449.86  4535.7  446.41
  4565.6  446.62  4609.0  446.17  4648.6  443.75  4671.2  444.89  4721.9  443.10
  4784.2  442.77  4840.4  444.07  4953.4  443.06  5007.1  440.34  5013.5  438.51
  5013.8  438.01  5017.6  438.51  5043.2  441.02  5052.3  439.91  5110.5  439.45
  5361.0  441.06  5493.0  444.75  5574.2  445.26  5624.0  447.72  5772.7  451.19
  5889.0  450.60  5986.3  452.61  6024.1  451.81  6447.6  454.13  6652.9  453.71
#Mann=5,-1,0
  4028.8    0.05       0  4565.6    0.12       0  5013.5    0.07       0
  5017.6    0.12       0  5110.5    0.05       0
Bank Sta=5013.5,5017.6
Exp/Cntr=0.3,0.1

Type RM Length L Ch R = 1,7529,1038,1038,1038
BEGIN DESCRIPTION:
Anthony Branch Trib 1 10.0
END DESCRIPTION:
XS GIS Cut Line= 3
      2657074.59      6932231.66      2656142.33      6933182.60
      2655411.46      6934176.02
#Sta/Elev= 30
  3705.6  452.81  3979.9  452.52  4022.4  451.55  4156.7  451.69  4163.8  452.58
  4185.0  451.07  4277.0  448.94  4390.1  447.51  4411.3  448.28  4894.3  439.68
  4969.9  436.00  4974.8  434.07  4975.2  433.57  4979.2  434.07  4984.0  434.10
  4998.2  437.79  5090.7  435.59  5184.3  438.29  5225.1  440.65  5312.1  444.27
  5402.7  446.37  5606.4  449.69  5633.8  448.63  5692.4  450.31  5727.9  449.06
  5748.7  450.06  5928.4  449.26  5978.6  450.76  6075.6  450.58  6270.6  451.66
#Mann=7,-1,0
  3705.6    0.05       0  4894.3    0.12       0  4974.8    0.07       0
  4979.2    0.12       0  5225.1    0.05       0  5402.7    0.12       0
  6075.6    0.05       0
Bank Sta=4974.8,4979.2
Exp/Cntr=0.3,0.1

Type RM Length L Ch R = 1,6491,696,696,696
BEGIN DESCRIPTION:
Anthony Branch Trib 1 8.0
END DESCRIPTION:
XS GIS Cut Line= 3
      2656286.41      6931908.73      2655826.00      6932411.00
      2655140.81      6933505.57
#Sta/Elev= 30
  4314.8  449.17  4507.8  449.72  4620.9  447.71  4762.8  441.79  4797.9  438.72
  4829.7  437.54  4854.6  437.10  4911.4  432.64  4989.1  432.62  4999.1  431.79
  5001.6  430.56  5002.0  430.06  5006.0  430.56  5009.7  432.97  5019.1  433.97
  5104.0  432.93  5140.4  434.46  5177.1  436.13  5308.0  436.16  5468.1  439.04
  5496.6  440.63  5511.9  444.06  5517.8  442.61  5533.1  445.76  5612.1  446.22
  5627.4  444.44  5743.0  448.10  5800.7  447.33  6004.7  449.74  6287.5  449.74
#Mann=5,-1,0
  4314.8    0.05       0  4829.7    0.12       0  5001.6    0.07       0
  5006.0    0.12       0  5140.4    0.05       0
Bank Sta=5001.6,5006
Exp/Cntr=0.3,0.1

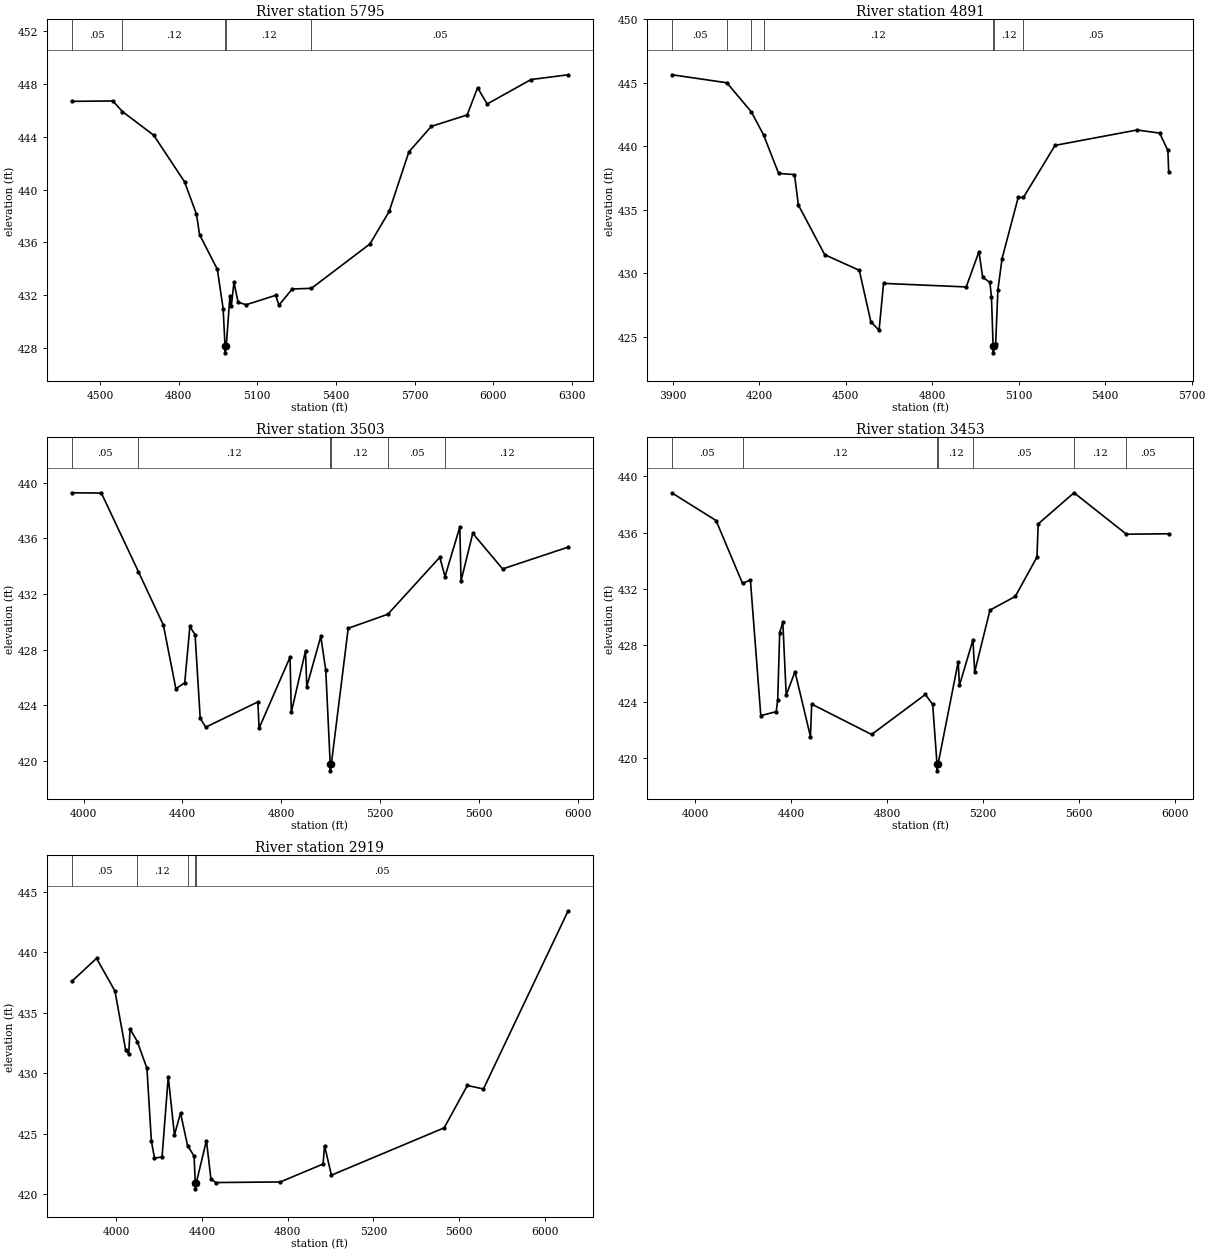
Type RM Length L Ch R = 1,5795,904,904,904
BEGIN DESCRIPTION:
Anthony Branch Trib 1 7.0
END DESCRIPTION:
XS GIS Cut Line= 3
      2655631.91      6931473.29      2655369.75      6931952.67
      2654928.77      6933224.72
#Sta/Elev= 30
  4392.4  446.67  4549.4  446.70  4585.7  445.90  4705.1  444.11  4822.9  440.58
  4868.2  438.13  4879.9  436.59  4947.6  433.97  4969.8  430.99  4977.1  428.15
  4977.5  427.65  4981.6  428.15  4995.6  431.94  5000.9  431.16  5011.1  432.98
  5026.8  431.47  5057.9  431.29  5169.9  432.00  5182.5  431.26  5233.4  432.48
  5306.5  432.53  5529.7  435.89  5602.6  438.34  5677.9  442.85  5763.6  444.78
  5900.1  445.64  5939.8  447.70  5976.3  446.47  6143.6  448.32  6285.1  448.68
#Mann=5,-1,0
  4392.4    0.05       0  4585.7    0.12       0  4977.1    0.07       0
  4981.6    0.12       0  5306.5    0.05       0
Bank Sta=4977.1,4981.6
Exp/Cntr=0.3,0.1

Type RM Length L Ch R = 1,4891,1388,1388,1388
BEGIN DESCRIPTION:
Anthony Branch Trib 1 6.0
END DESCRIPTION:
XS GIS Cut Line= 3
      2655600.65      6931322.26      2654601.53      6931788.15
      2654210.53      6932269.57
#Sta/Elev= 30
  3897.6  445.62  4087.3  444.99  4172.2  442.70  4214.8  440.88  4266.9  437.85
  4322.0  437.76  4335.5  435.36  4426.9  431.45  4546.8  430.22  4586.8  426.18
  4615.4  425.49  4631.0  429.19  4917.8  428.91  4962.0  431.69  4974.9  429.67
  5000.0  429.27  5005.5  428.08  5011.1  424.22  5011.6  423.72  5015.7  424.22
  5019.9  424.42  5027.8  428.70  5042.2  431.15  5098.2  435.96  5116.4  435.96
  5226.0  440.06  5510.5  441.27  5588.8  441.03  5617.5  439.66  5620.2  438.00
#Mann=7,-1,0
  3897.6    0.05       0  4087.3    0.12       0  4172.2    0.05       0
  4214.8    0.12       0  5011.1    0.07       0  5015.7    0.12       0
  5116.4    0.05       0
Bank Sta=5011.1,5015.7
Exp/Cntr=0.3,0.1

Type RM Length L Ch R = 1,3503,50,50,50
BEGIN DESCRIPTION:
Mapping XS 71d94042
END DESCRIPTION:
XS GIS Cut Line= 4
      2654744.54      6930043.25      2654314.86      6930342.72
      2654397.32      6930867.90      2654514.51      6931814.11
#Sta/Elev= 30
  3951.7  439.28  4071.8  439.26  4221.5  433.61  4322.7  429.76  4373.3  425.18
  4409.1  425.61  4430.0  429.66  4451.0  429.06  4471.7  423.06  4493.9  422.41
  4705.0  424.23  4710.0  422.34  4835.2  427.45  4840.3  423.48  4897.8  427.90
  4902.9  425.33  4959.6  428.94  4979.8  426.50  4997.7  419.77  4998.2  419.27
  5002.4  419.77  5070.6  429.53  5231.1  430.54  5441.1  434.64  5462.2  433.25
  5522.1  436.81  5527.1  432.94  5574.5  436.36  5695.4  433.80  5960.5  435.37
#Mann=6,-1,0
  3951.7    0.05       0  4221.5    0.12       0  4997.7    0.07       0
  5002.4    0.12       0  5231.1    0.05       0  5462.2    0.12       0
Bank Sta=4997.7,5002.4
Exp/Cntr=0.3,0.1

Type RM Length L Ch R = 1,3453,534,534,534
BEGIN DESCRIPTION:
Mapping XS 4c48ab06
END DESCRIPTION:
XS GIS Cut Line= 4
      2654679.40      6929986.85      2654245.41      6930325.36
      2654349.58      6930880.92      2654492.81      6931822.75
#Sta/Elev= 30
  3904.9  438.82  4087.7  436.87  4197.9  432.41  4230.7  432.65  4274.1  423.02
  4338.3  423.30  4344.6  424.16  4352.8  428.92  4365.8  429.66  4379.9  424.47
  4416.5  426.14  4481.0  421.53  4486.0  423.84  4735.7  421.68  4959.6  424.52
  4990.1  423.82  5008.1  419.60  5008.6  419.10  5012.8  419.60  5096.5  426.84
  5101.6  425.16  5157.9  428.40  5165.2  426.13  5228.8  430.51  5334.2  431.48
  5424.6  434.28  5429.7  436.63  5578.9  438.84  5797.2  435.90  5973.2  435.93
#Mann=7,-1,0
  3904.9    0.05       0  4197.9    0.12       0  5008.1    0.07       0
  5012.8    0.12       0  5157.9    0.05       0  5578.9    0.12       0
  5797.2    0.05       0
Bank Sta=5008.1,5012.8
Exp/Cntr=0.3,0.1

Type RM Length L Ch R = 1,2919,0,0,0
BEGIN DESCRIPTION:
Anthony Branch Trib 1 5.0
END DESCRIPTION:
XS GIS Cut Line= 5
      2654657.76      6929900.00      2653963.29      6930438.21
      2653881.98      6930758.64      2653872.15      6931050.19
      2654275.98      6931760.97
#Sta/Elev= 30
  3790.8  437.58  3906.9  439.49  3992.8  436.79  4042.6  431.94  4057.1  431.56
  4063.4  433.66  4097.3  432.62  4142.2  430.41  4163.0  424.40  4177.5  422.99
  4212.8  423.08  4241.8  429.71  4270.7  424.90  4299.1  426.71  4331.9  424.02
  4362.3  423.16  4368.0  420.95  4368.5  420.45  4372.7  420.95  4420.1  424.44
  4440.9  421.27  4463.6  420.97  4765.2  421.02  4964.8  422.50  4971.5  424.02
  5003.7  421.58  5530.4  425.49  5638.5  428.99  5713.5  428.70  6109.2  443.42
#Mann=5,-1,0
  3790.8    0.05       0  4097.3    0.12       0  4331.9    0.05       0
  4368.0    0.03       0  4372.7    0.05       0
Bank Sta=4368,4372.7
Exp/Cntr=0.3,0.1

Chan Stop Cuts=-1