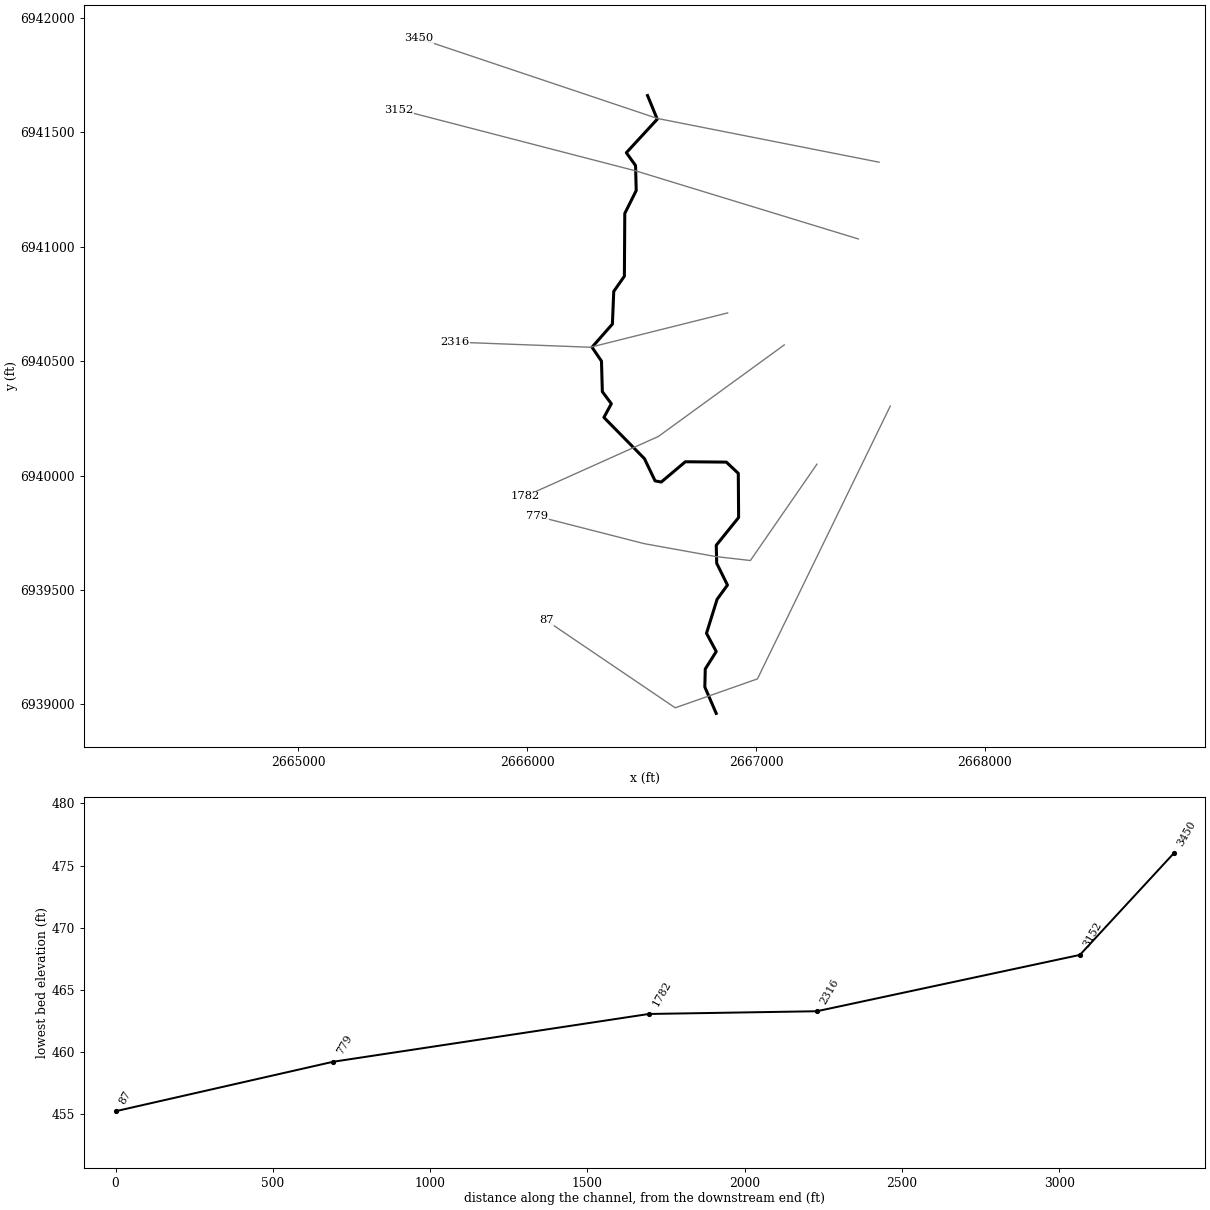
--- Anthony Branch Trib 2.prj (project) ---

Proj Title=Anthony Branch Trib 2 Base Level Engineering
Current Plan=p01
Default Exp/Contr=0.3,0.1
English Units
Geom File=g01
Flow File=f01
Plan File=p01
BEGIN DESCRIPTION:
Anthony Branch Trib 2
END DESCRIPTION:

--- Anthony Branch Trib 2.p01 (plan) ---

Plan Title=Multiple Run
Short Identifier=Multiple
Geom File=g01
Flow File=f01
Subcritical Flow
K Sum by GR= 0
Std Step Tol= 0.01
Critical Tol= 0.01
Num of Std Step Trials= 20
Max Error Tol= 0.3
Flow Tol Ratio= 0.001
Split Flow NTrial= 30
Split Flow Tol= 0.02
Split Flow Ratio= 0.02
Log Output Level= 0
Friction Slope Method= 1
Unsteady Friction Slope Method= 2
Unsteady Bridges Friction Slope Method= 1
Parabolic Critical Depth
Global Vel Dist=  1 , 1 , 1
Global Log Level= 0
CheckData=True
Encroach Param= -1, 0, 0, 0
BEGIN DESCRIPTION:
Multiple Run
END DESCRIPTION:

--- Anthony Branch Trib 2.f01 (steady flow) ---

Flow Title=Multiple
Number of Profiles=7
Profile Names=10-year,25-year,50-year,1pct_min,100-year,1pct_plu,500-year
River Rch & RM= Anthony Branch T,Reach-1,3450
     494     652     777     460     918    1832    1280
River Rch & RM= Anthony Branch T,Reach-1,87
    1166    1622    2004    1226    2445    4879    3642
Boundary for River Rch & Prof#=Anthony Branch T,Reach-1,1
Up Type=0
Dn Type=3
Dn Slope=0.005
Boundary for River Rch & Prof#=Anthony Branch T,Reach-1,2
Up Type=0
Dn Type=3
Dn Slope=0.005
Boundary for River Rch & Prof#=Anthony Branch T,Reach-1,3
Up Type=0
Dn Type=3
Dn Slope=0.005
Boundary for River Rch & Prof#=Anthony Branch T,Reach-1,4
Up Type=0
Dn Type=3
Dn Slope=0.005
Boundary for River Rch & Prof#=Anthony Branch T,Reach-1,5
Up Type=0
Dn Type=3
Dn Slope=0.005
Boundary for River Rch & Prof#=Anthony Branch T,Reach-1,6
Up Type=0
Dn Type=3
Dn Slope=0.005
Boundary for River Rch & Prof#=Anthony Branch T,Reach-1,7
Up Type=0
Dn Type=3
Dn Slope=0.005

--- Anthony Branch Trib 2.g01 (geometry) ---

Geom Title=Existing Conditions

River Reach=Anthony Branch T,Reach-1
Reach XY= 30
      2666526.00      6941661.00      2666568.41      6941557.61
      2666433.32      6941411.10      2666473.54      6941355.14
      2666476.47      6941245.84      2666426.52      6941145.78
      2666424.78      6940871.50      2666378.27      6940805.06
      2666372.43      6940662.47      2666283.33      6940561.10
      2666324.60      6940500.56      2666328.46      6940366.86
      2666367.71      6940314.21      2666335.30      6940254.33
      2666512.37      6940074.18      2666558.96      6939977.04
      2666585.86      6939971.92      2666691.16      6940060.61
      2666870.35      6940059.03      2666922.57      6940009.78
      2666923.94      6939816.86      2666826.25      6939695.78
      2666828.19      6939616.97      2666875.23      6939521.69
      2666829.88      6939459.41      2666783.59      6939310.99
      2666826.21      6939231.21      2666778.19      6939155.04
      2666776.30      6939076.25      2666826.00      6938961.00

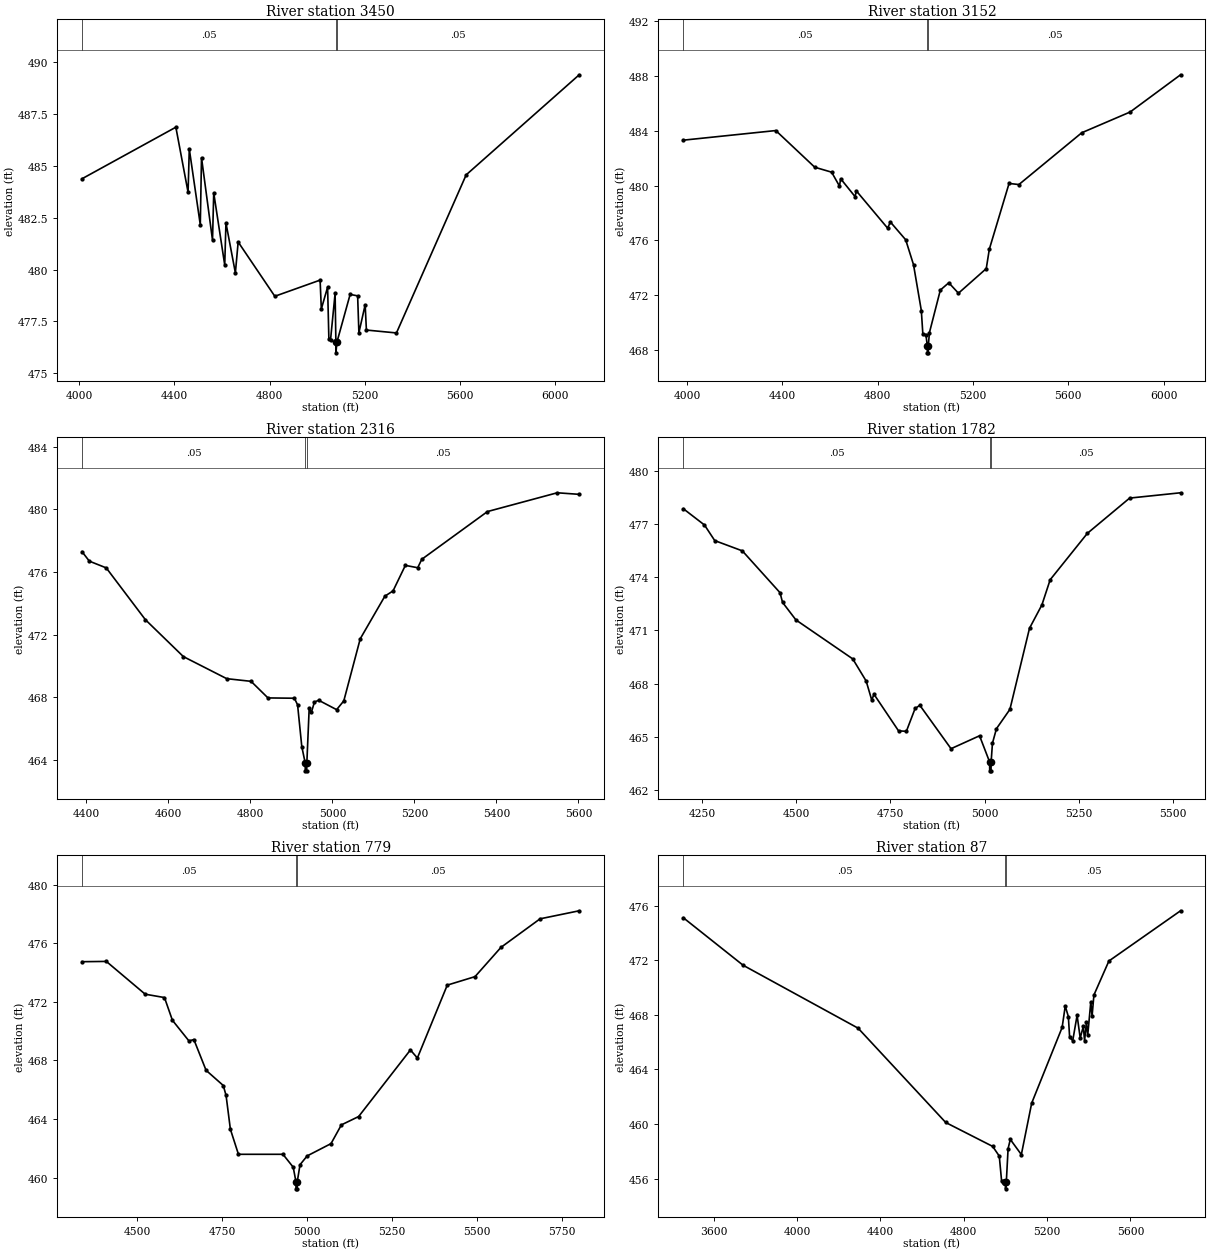
Type RM Length L Ch R = 1,3450,298,298,298
BEGIN DESCRIPTION:
Anthony Branch Trib 2 5.0
END DESCRIPTION:
XS GIS Cut Line= 3
      2667537.86      6941369.72      2666568.95      6941560.93
      2665526.03      6941910.99
#Sta/Elev= 30
  4012.4  484.38  4406.6  486.87  4457.9  483.73  4463.0  485.82  4509.2  482.16
  4514.3  485.40  4560.5  481.42  4565.6  483.70  4611.8  480.22  4616.9  482.25
  4656.5  479.84  4668.2  481.33  4822.1  478.71  5012.2  479.49  5017.4  478.10
  5043.7  479.15  5049.0  476.67  5055.9  476.59  5075.2  478.85  5078.5  476.48
  5078.8  475.98  5082.5  476.48  5138.3  478.80  5169.8  478.73  5175.1  476.95
  5201.4  478.30  5206.6  477.08  5332.8  476.94  5625.5  484.57  6100.1  489.40
#Mann=3,-1,0
  4012.4    0.05       0  5078.5    0.05       0  5082.5    0.05       0
Bank Sta=5078.5,5082.5
Exp/Cntr=0.3,0.1

Type RM Length L Ch R = 1,3152,836,836,836
BEGIN DESCRIPTION:
Anthony Branch Trib 2 4.0
END DESCRIPTION:
XS GIS Cut Line= 3
      2667447.02      6941034.28      2666476.31      6941331.17
      2665439.48      6941599.92
#Sta/Elev= 30
  3984.9  483.30  4372.9  484.00  4536.4  481.33  4607.2  480.97  4640.0  479.96
  4645.2  480.49  4705.6  479.19  4710.8  479.61  4841.9  476.90  4853.9  477.34
  4917.9  476.05  4950.7  474.24  4983.5  470.90  4989.9  469.19  5002.7  469.15
  5008.7  468.32  5008.9  467.82  5012.4  467.82  5012.7  468.32  5017.5  469.29
  5063.3  472.39  5098.7  472.92  5139.3  472.16  5255.9  473.95  5268.9  475.37
  5351.6  480.15  5392.9  480.07  5656.6  483.84  5859.6  485.35  6071.1  488.06
#Mann=3,-1,0
  3984.9    0.05       0  5008.7    0.03       0  5012.7    0.05       0
Bank Sta=5008.7,5012.7
Exp/Cntr=0.3,0.1

Type RM Length L Ch R = 1,2316,534,534,534
BEGIN DESCRIPTION:
Anthony Branch Trib 2 3.0
END DESCRIPTION:
XS GIS Cut Line= 3
      2666875.96      6940710.99      2666276.00      6940561.00
      2665682.45      6940583.54
#Sta/Elev= 30
  4389.4  477.30  4407.4  476.69  4448.6  476.26  4544.0  472.95  4636.7  470.59
  4742.4  469.18  4801.7  469.01  4842.9  467.95  4907.3  467.93  4915.1  467.51
  4925.4  464.84  4933.7  463.79  4933.9  463.29  4937.4  463.29  4937.7  463.79
  4943.4  467.28  4948.6  467.02  4956.3  467.69  4966.6  467.80  5010.3  467.20
  5027.8  467.76  5067.9  471.73  5127.9  474.45  5147.9  474.79  5177.9  476.42
  5208.0  476.27  5218.0  476.81  5378.1  479.86  5548.2  481.06  5601.8  480.96
#Mann=3,-1,0
  4389.4    0.05       0  4933.7    0.04       0  4937.7    0.05       0
Bank Sta=4933.7,4937.7
Exp/Cntr=0.3,0.1

Type RM Length L Ch R = 1,1782,1003,1003,1003
BEGIN DESCRIPTION:
Anthony Branch Trib 2 2.0
END DESCRIPTION:
XS GIS Cut Line= 3
      2667123.44      6940571.21      2666573.48      6940171.24
      2665990.50      6939909.42
#Sta/Elev= 30
  4200.8  477.87  4257.0  476.95  4284.2  476.07  4357.4  475.49  4457.3  473.13
  4464.1  472.58  4499.6  471.59  4650.3  469.39  4685.9  468.14  4700.6  467.07
  4706.7  467.39  4771.7  465.33  4792.5  465.30  4815.7  466.59  4828.3  466.77
  4911.0  464.32  4986.7  465.05  5013.4  463.57  5013.6  463.07  5017.1  463.07
  5017.4  463.57  5020.9  464.63  5031.5  465.45  5067.2  466.54  5119.2  471.12
  5152.1  472.44  5174.0  473.86  5272.7  476.48  5384.8  478.47  5519.9  478.77
#Mann=3,-1,0
  4200.8    0.05       0  5013.4    0.04       0  5017.4    0.05       0
Bank Sta=5013.4,5017.4
Exp/Cntr=0.3,0.1

Type RM Length L Ch R = 1,779,692,692,692
BEGIN DESCRIPTION:
Mapping XS 743c1fb5
END DESCRIPTION:
XS GIS Cut Line= 5
      2667266.18      6940050.02      2666975.39      6939629.02
      2666823.48      6939646.39      2666510.98      6939702.81
      2666044.41      6939822.16
#Sta/Elev= 30
  4337.3  474.75  4409.0  474.77  4523.4  472.53  4580.2  472.30  4603.5  470.75
  4652.1  469.34  4666.7  469.43  4702.6  467.33  4753.3  466.29  4761.5  465.61
  4774.2  463.30  4797.9  461.59  4928.9  461.59  4959.1  460.71  4967.1  459.73
  4967.4  459.23  4970.9  459.23  4971.1  459.73  4979.2  460.88  5000.2  461.48
  5070.4  462.32  5100.9  463.60  5151.7  464.17  5304.1  468.72  5324.6  468.17
  5412.6  473.15  5494.3  473.73  5570.7  475.73  5685.8  477.68  5801.0  478.23
#Mann=3,-1,0
  4337.3    0.05       0  4967.1    0.04       0  4971.1    0.05       0
Bank Sta=4967.1,4971.1
Exp/Cntr=0.3,0.1

Type RM Length L Ch R = 1,87,0,0,0
BEGIN DESCRIPTION:
Anthony Branch Trib 2 1.0
END DESCRIPTION:
XS GIS Cut Line= 4
      2667586.76      6940303.98      2667006.21      6939111.66
      2666646.83      6938985.36      2666083.32      6939367.09
#Sta/Elev= 30
  3453.2  475.11  3740.3  471.63  4292.5  467.02  4713.3  460.11  4938.6  458.36
  4970.4  457.65  4981.8  455.79  5000.2  455.75  5000.4  455.25  5004.2  455.75
  5012.8  458.20  5023.4  458.87  5076.4  457.76  5126.1  461.53  5272.2  467.07
  5287.2  468.64  5302.1  467.87  5308.2  466.38  5323.1  466.10  5344.1  467.96
  5359.1  466.30  5374.0  467.15  5380.0  466.10  5389.0  467.44  5395.0  466.49
  5410.0  468.95  5416.0  467.90  5424.9  469.45  5496.8  471.94  5840.9  475.62
#Mann=3,-1,0
  3453.2    0.05       0  5000.2    0.04       0  5004.2    0.05       0
Bank Sta=5000.2,5004.2
Exp/Cntr=0.3,0.1

Chan Stop Cuts=-1