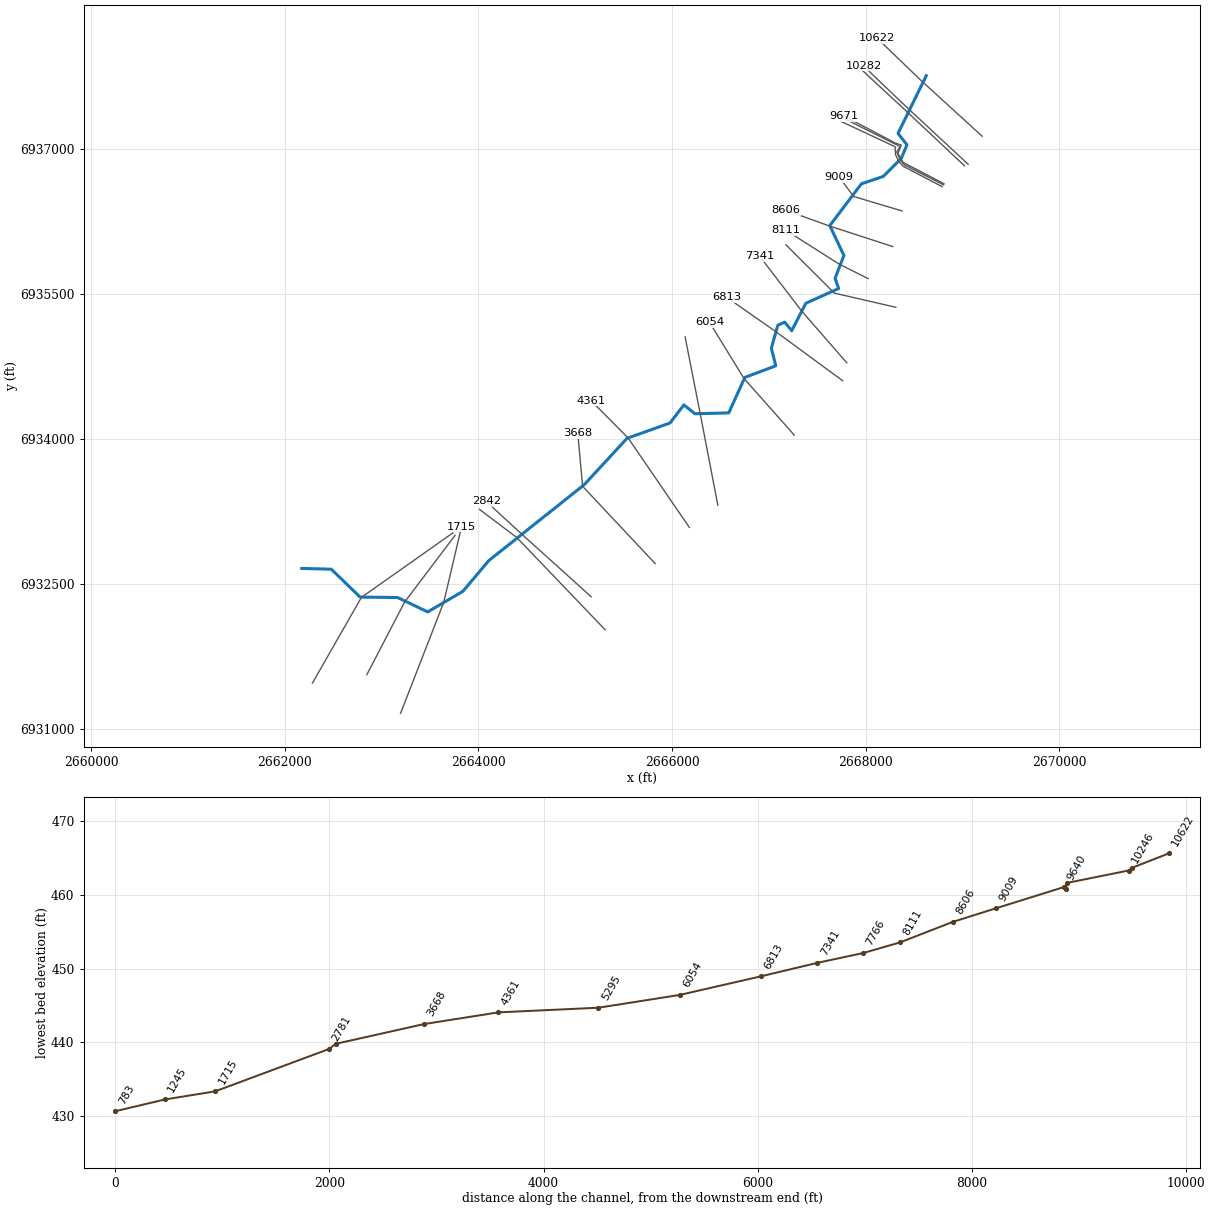
--- Anthony Branch Trib 3.prj (project) ---

Proj Title=Anthony Branch Trib 3 Base Level Engineering
Current Plan=p01
Default Exp/Contr=0.3,0.1
English Units
Geom File=g01
Flow File=f01
Plan File=p01
Y Axis Title=Elevation
X Axis Title(PF)=Main Channel Distance
X Axis Title(XS)=Station
BEGIN DESCRIPTION:
Anthony Branch Trib 3
END DESCRIPTION:
DSS Export Rating Curves= 0
DSS Export Rating Curve Sorted= 0
DSS Export Volume Flow Curves= 0
DXF OffsetX= 0
DXF OffsetY= 0
DXF ScaleX= 1
DXF ScaleY= 10

--- Anthony Branch Trib 3.p01 (plan) ---

Plan Title=Multiple Run
Short Identifier=Multiple
Geom File=g01
Flow File=f01
Subcritical Flow
K Sum by GR= 0
Std Step Tol= 0.01
Critical Tol= 0.01
Num of Std Step Trials= 20
Max Error Tol= 0.3
Flow Tol Ratio= 0.001
Split Flow NTrial= 30
Split Flow Tol= 0.02
Split Flow Ratio= 0.02
Log Output Level= 0
Friction Slope Method= 1
Unsteady Friction Slope Method= 2
Unsteady Bridges Friction Slope Method= 1
Parabolic Critical Depth
Global Vel Dist=  1 , 1 , 1
Global Log Level= 0
CheckData=True
Encroach Param= -1, 0, 0, 0
BEGIN DESCRIPTION:
Multiple Run
END DESCRIPTION:

--- Anthony Branch Trib 3.f01 (steady flow) ---

Flow Title=Multiple
Program Version=4.10
Number of Profiles= 7
Profile Names=10-year,25-year,50-year,1pct_min,100-year,1pct_plu,500-year
River Rch & RM=Anthony Branch T,Reach-1         ,10622
     476     628     748     443     883    1762    1229
River Rch & RM=Anthony Branch T,Reach-1         ,9671
     679     914    1104     662    1320    2635    1887
River Rch & RM=Anthony Branch T,Reach-1         ,7341
     739    1003    1218     733    1463    2920    2112
River Rch & RM=Anthony Branch T,Reach-1         ,5295
     748    1015    1232     741    1479    2951    2132
River Rch & RM=Anthony Branch T,Reach-1         ,3668
     810    1103    1343     809    1615    3222    2337
River Rch & RM=Anthony Branch T,Reach-1         ,1715
    1091    1509    1857    1131    2257    4503    3335
River Rch & RM=Anthony Branch T,Reach-1         ,783
    1082    1496    1839    1119    2232    4454    3293
Boundary for River Rch & Prof#=Anthony Branch T,Reach-1         , 1
Up Type= 0
Dn Type= 3
Dn Slope=0.005
Boundary for River Rch & Prof#=Anthony Branch T,Reach-1         , 2
Up Type= 0
Dn Type= 3
Dn Slope=0.005
Boundary for River Rch & Prof#=Anthony Branch T,Reach-1         , 3
Up Type= 0
Dn Type= 3
Dn Slope=0.005
Boundary for River Rch & Prof#=Anthony Branch T,Reach-1         , 4
Up Type= 0
Dn Type= 3
Dn Slope=0.005
Boundary for River Rch & Prof#=Anthony Branch T,Reach-1         , 5
Up Type= 0
Dn Type= 3
Dn Slope=0.005
Boundary for River Rch & Prof#=Anthony Branch T,Reach-1         , 6
Up Type= 0
Dn Type= 3
Dn Slope=0.005
Boundary for River Rch & Prof#=Anthony Branch T,Reach-1         , 7
Up Type= 0
Dn Type= 3
Dn Slope=0.005
DSS Import GetInterval= 0
DSS Import GetPeak= 0
DSS Import FillOption= 0

--- Anthony Branch Trib 3.g01 (geometry) ---

Geom Title=Existing Conditions
Program Version=4.10

River Reach=Anthony Branch T,Reach-1
Reach XY= 30
        2668626.        6937761.      2668333.88      6937164.22
      2668426.04      6937045.66      2668367.86      6936904.94
      2668182.06      6936719.14      2667955.46      6936641.53
      2667629.11      6936209.35      2667775.39      6935900.38
       2667684.1      6935664.29      2667720.89       6935558.7
      2667381.61      6935405.41      2667236.25      6935121.76
      2667163.92      6935209.86      2667092.36      6935178.35
      2667025.72      6934940.82      2667070.72      6934758.29
      2666751.99      6934638.31      2666585.71      6934271.18
      2666236.48      6934261.95      2666122.42      6934353.51
      2665978.44      6934166.52      2665534.48      6934007.49
      2665092.68      6933527.64      2664105.91      6932741.21
      2663839.62      6932424.27        2663476.        6932211.
       2663165.5       6932359.8      2662777.55      6932364.75
      2662479.43      6932653.21        2662176.        6932661.

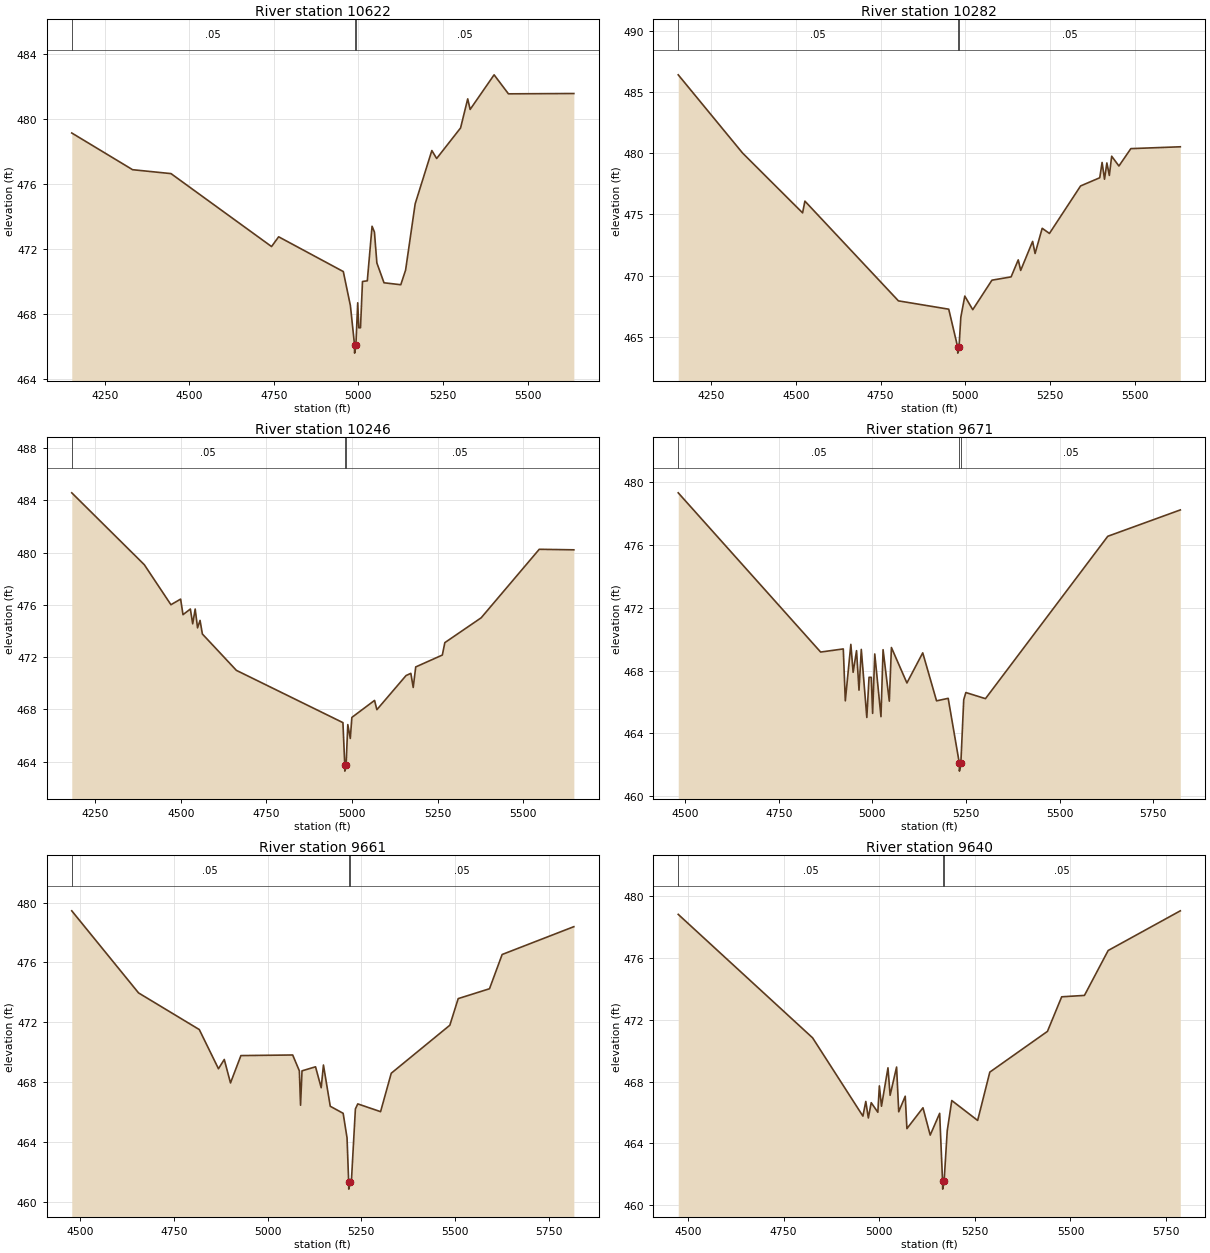
Type RM Length L Ch R = 1 ,10622   ,340,340,340
BEGIN DESCRIPTION:
Anthony Branch Trib 3 18.0
END DESCRIPTION:
XS GIS Cut Line= 3
      2669203.35      6937134.35      2668576.35      6937707.82
      2668119.57      6938147.92
#Sta/Elev= 30
  4152.8  479.15  4332.6  476.89  4446.1  476.65  4743.3  472.16  4764.3  472.76
  4955.4  470.62  4976.4  468.52  4988.6   466.1  4988.8   465.6  4992.6   466.1
    4998   468.7  5001.2  467.16  5006.2  467.16  5012.1  470.01  5026.3  470.05
  5040.4  473.41  5047.4  473.05  5054.6  471.15  5075.7  469.93  5125.3  469.81
  5139.5  470.71  5167.8  474.79  5217.1  478.07  5231.3  477.58    5302  479.46
  5323.1  481.25  5330.3   480.6  5401.1  482.73  5443.5  481.56  5636.8  481.58
#Mann= 3 ,-1 , 0
  4152.8     .05       0  4988.6     .04       0  4992.6     .05       0
Bank Sta=4988.6,4992.6
XS Rating Curve= 0 ,0
Exp/Cntr=0.3,0.1

Type RM Length L Ch R = 1 ,10282   ,36,36,36
BEGIN DESCRIPTION:
Mapping XS 68d797c4
END DESCRIPTION:
XS GIS Cut Line= 4
      2669058.28      6936844.54      2668437.21      6937422.64
      2668066.12      6937776.81      2667981.47      6937862.76
#Sta/Elev= 30
  4152.4  486.41  4342.6  480.01  4519.5  475.13  4526.3  476.09  4802.4  467.94
  4950.9  467.26  4977.3  464.17  4977.5  463.67  4981.3  464.17  4986.6   466.6
  4998.3  468.33  5021.8  467.22  5078.4  469.63    5135   469.9  5156.1  471.29
  5163.3  470.43  5198.5   472.8  5205.8  471.81  5226.8  473.87  5248.2  473.45
  5340.1  477.33  5396.7     478  5403.6  479.25  5410.8  477.88  5417.7  479.21
    5425  478.19  5431.9  479.76  5453.3  478.96  5488.5  480.38  5634.5  480.53
#Mann= 3 ,-1 , 0
  4152.4     .05       0  4977.3     .05       0  4981.3     .05       0
Bank Sta=4977.3,4981.3
XS Rating Curve= 0 ,0
Exp/Cntr=0.3,0.1

Type RM Length L Ch R = 1 ,10246   ,575,575,575
BEGIN DESCRIPTION:
Mapping XS 3adc0120
END DESCRIPTION:
XS GIS Cut Line= 3
      2669021.84       6936827.6      2668424.19      6937390.09
       2667951.5      6937828.92
#Sta/Elev= 30
  4181.9  484.57  4393.7  479.07  4471.4  476.01  4499.7  476.44  4506.6  475.25
  4528.1  475.68  4534.9  474.55  4542.2  475.68  4549.1  474.24  4556.4  474.81
  4563.2  473.77  4662.4  470.99  4973.5  466.99  4978.8  463.78    4979  463.28
  4982.8  463.78  4987.7  466.84    4995  465.78  4999.6  467.39  5065.8  468.69
  5072.6  467.98  5157.7  470.59  5171.8  470.76  5178.7  469.68    5186  471.25
  5263.7  472.16    5271  473.11  5377.1  475.01  5546.6  480.25  5647.6  480.21
#Mann= 3 ,-1 , 0
  4181.9     .05       0  4978.8     .05       0  4982.8     .05       0
Bank Sta=4978.8,4982.8
XS Rating Curve= 0 ,0
Exp/Cntr=0.3,0.1

Type RM Length L Ch R = 1 ,9671    ,10,10,10
BEGIN DESCRIPTION:
Mapping XS 5fa0be67
END DESCRIPTION:
XS GIS Cut Line= 6
      2668808.72      6936643.14      2668386.87      6936863.61
      2668333.05      6936957.36      2668367.23      6937042.96
      2668306.14      6937064.13      2667775.78      6937344.51
#Sta/Elev= 30
  4481.3  479.34  4861.8  469.19  4922.3  469.39  4927.7  466.08  4942.5  469.68
  4948.6   467.9  4957.7  469.28  4964.3  466.76  4970.4  469.36  4985.2  465.02
  4991.1  467.58    4997  467.58  5000.7  465.28  5006.4  469.07    5023  465.07
  5028.6  469.34  5045.3  466.06  5050.9  469.48  5092.3  467.22  5134.6  469.14
  5171.5  466.08  5202.6  466.24  5232.4   462.1  5232.6   461.6  5236.4   462.1
  5244.1  466.15  5249.8  466.61  5302.2  466.22    5629  476.57  5822.8  478.25
#Mann= 3 ,-1 , 0
  4481.3     .05       0  5232.4     .05       0  5236.4     .05       0
Bank Sta=5232.4,5236.4
XS Rating Curve= 0 ,0
Exp/Cntr=0.3,0.1

Type RM Length L Ch R = 1 ,9661    ,21,21,21
BEGIN DESCRIPTION:
Anthony Branch Trib 3 16.0
END DESCRIPTION:
XS GIS Cut Line= 6
      2668804.77      6936631.49      2668400.22       6936838.1
      2668356.22      6936890.91      2668320.36      6936971.78
      2668356.82      6937027.34       2667764.8      6937324.22
#Sta/Elev= 30
    4477  479.45  4655.3  473.96  4817.4  471.51  4868.6  468.89  4884.1  469.51
  4900.7  467.94  4928.5  469.77  5066.7  469.81  5084.5  468.75  5087.7  466.45
  5091.6  468.75  5127.7  469.02  5142.8  467.62  5148.8  469.14    5167  466.38
  5201.4  465.91  5211.8  464.27  5216.1  461.34  5216.4  460.84  5220.1  461.34
  5223.7  461.49  5234.1   466.2  5240.4  466.54  5301.3  466.02  5329.8  468.59
  5486.2   471.8  5508.5  473.58  5592.1  474.24  5625.8  476.53  5817.2  478.39
#Mann= 3 ,-1 , 0
    4477     .05       0  5216.1     .05       0  5220.1     .05       0
Bank Sta=5216.1,5220.1
XS Rating Curve= 0 ,0
Exp/Cntr=0.3,0.1

Type RM Length L Ch R = 1 ,9640    ,631,631,631
BEGIN DESCRIPTION:
Mapping XS aca0191a
END DESCRIPTION:
XS GIS Cut Line= 6
      2668790.88      6936612.39      2668386.33      6936824.21
      2668342.93      6936872.83      2668308.21      6936944.01
      2668304.73       6937025.6      2667735.26      6937292.98
#Sta/Elev= 30
  4474.7  478.83    4826  470.83  4957.5  465.76    4965  466.71  4971.7  465.64
  4979.2  466.63  4996.5  466.01  5000.5  467.72    5006   466.4    5023  468.89
  5028.6  467.11  5045.5  468.94  5051.1  466.04  5068.1  467.05  5072.5  464.95
  5114.5   466.3  5133.4  464.53  5158.1  465.94  5165.7  461.53    5166  461.03
  5169.7  461.53  5177.9  464.81  5189.8  466.77  5257.4  465.48  5289.2  468.61
  5439.9  471.25  5477.1  473.49  5536.6  473.58  5598.6  476.49  5787.2  479.06
#Mann= 3 ,-1 , 0
  4474.7     .05       0  5165.7     .03       0  5169.7     .05       0
Bank Sta=5165.7,5169.7
XS Rating Curve= 0 ,0
Exp/Cntr=0.3,0.1

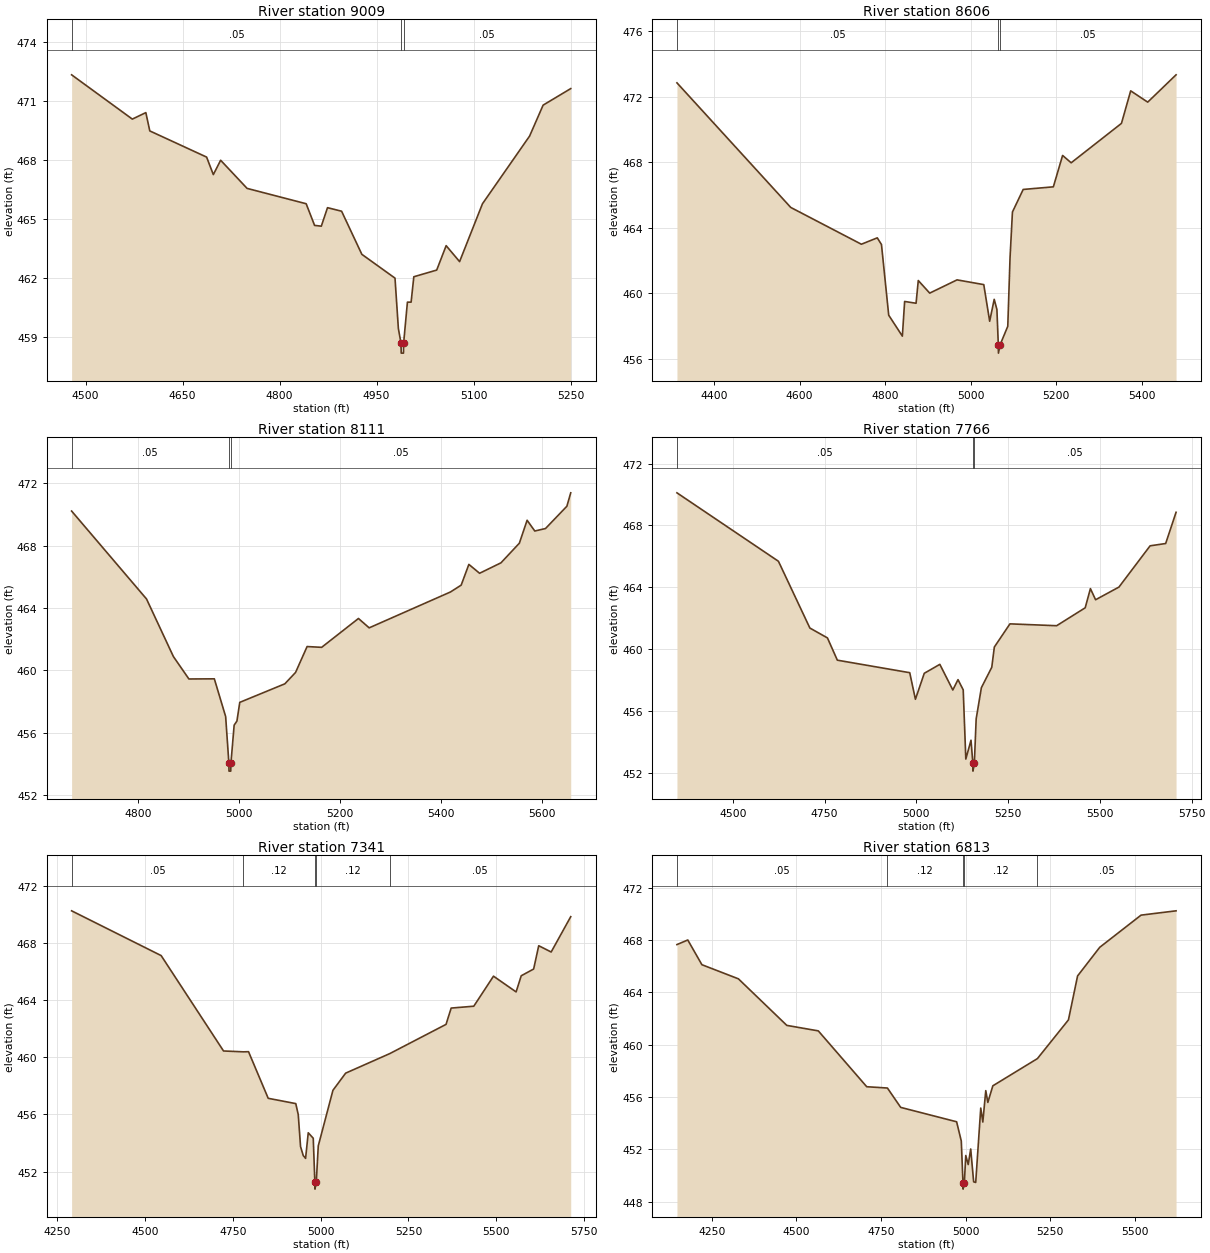
Type RM Length L Ch R = 1 ,9009    ,403,403,403
BEGIN DESCRIPTION:
Anthony Branch Trib 3 15.0
END DESCRIPTION:
XS GIS Cut Line= 3
      2668375.95      6936361.01        2667876.        6936511.
      2667725.98      6936711.03
#Sta/Elev= 30
  4478.3  472.31  4572.2  470.06  4593.1  470.39  4599.2  469.46  4687.1  468.13
  4697.5  467.24  4708.8  467.97  4749.7  466.54  4841.1  465.76  4854.1  464.66
  4864.5  464.62  4874.1  465.56  4895.9  465.38  4927.2  463.19  4978.5  461.98
  4983.7  459.42  4987.8  458.67  4988.1  458.17  4991.6  458.17  4991.8  458.67
  4997.7  460.76  5003.4  460.76  5007.6  462.05    5043  462.39  5057.6  463.63
  5078.4  462.82  5113.8  465.76  5186.7   469.2  5207.6  470.77  5250.3  471.61
#Mann= 3 ,-1 , 0
  4478.3     .05       0  4987.8     .05       0  4991.8     .05       0
Bank Sta=4987.8,4991.8
XS Rating Curve= 0 ,0
Exp/Cntr=0.3,0.1

Type RM Length L Ch R = 1 ,8606    ,495,495,495
BEGIN DESCRIPTION:
Anthony Branch Trib 3 14.0
END DESCRIPTION:
XS GIS Cut Line= 3
      2668280.43      6935992.62      2667627.59      6936204.95
      2667176.31       6936367.6
#Sta/Elev= 30
  4313.5  472.86  4579.4  465.24  4744.4  462.99  4781.6  463.38  4791.4  462.97
  4808.3  458.65  4840.2  457.37  4845.5  459.49  4872.2  459.38  4877.4  460.77
  4904.1     460    4968  460.81  5030.4  460.52  5044.2  458.28  5054.8  459.62
  5061.1     459  5064.4  456.83  5064.7  456.33  5068.4  456.83  5086.5  457.97
  5091.8  462.17  5097.4  464.96  5122.5  466.34    5193   466.5  5214.6  468.42
  5234.6  467.97  5352.1  470.38  5373.7  472.37  5413.5  471.68  5479.7  473.35
#Mann= 3 ,-1 , 0
  4313.5     .05       0  5064.4     .03       0  5068.4     .05       0
Bank Sta=5064.4,5068.4
XS Rating Curve= 0 ,0
Exp/Cntr=0.3,0.1

Type RM Length L Ch R = 1 ,8111    ,345,345,345
BEGIN DESCRIPTION:
Anthony Branch Trib 3 13.0
END DESCRIPTION:
XS GIS Cut Line= 3
      2668026.01      6935660.99        2667726.        6935811.
      2667176.04      6936160.97
#Sta/Elev= 30
  4668.8  470.22    4817  464.58  4870.1  460.89  4900.8  459.45  4951.1  459.46
  4973.5  457.04  4979.9  454.04  4980.1  453.54  4983.6  453.54  4983.9  454.04
  4990.3  456.49  4995.8  456.75  5001.4  457.95  5090.6  459.14  5111.8  459.87
  5134.6  461.53  5163.4  461.48  5236.2  463.33  5257.4  462.73  5418.2  465.03
  5439.4  465.47  5454.6   466.8  5475.8  466.23  5518.1   466.9  5554.5  468.16
  5569.8  469.63    5585  468.94  5606.2   469.1  5648.5  470.53  5656.1  471.39
#Mann= 3 ,-1 , 0
  4668.8     .05       0  4979.9     .05       0  4983.9     .05       0
Bank Sta=4979.9,4983.9
XS Rating Curve= 0 ,0
Exp/Cntr=0.3,0.1

Type RM Length L Ch R = 1 ,7766    ,425,425,425
BEGIN DESCRIPTION:
Anthony Branch Trib 3 12.0
END DESCRIPTION:
XS GIS Cut Line= 3
       2668311.7      6935364.14      2667676.38      6935510.67
      2667176.01      6936010.99
#Sta/Elev= 30
    4348  470.11  4624.5  465.68  4710.1  461.36    4758  460.72  4784.9  459.28
  4982.1  458.47  4997.6  456.75  5021.7  458.43  5064.1  459.01  5099.5  457.35
  5113.6  458.02  5127.8  457.36  5134.9  452.88    5149   454.1  5154.1   452.6
  5154.3   452.1  5158.1   452.6  5163.1  455.48  5177.3   457.5  5205.6  458.82
  5212.6  460.13  5255.1  461.63  5382.3  461.51  5460.1  462.67  5474.3  463.91
  5488.4  463.19    5552  464.01  5636.9  466.68  5679.3  466.83  5707.6  468.85
#Mann= 3 ,-1 , 0
    4348     .05       0  5154.1     .05       0  5158.1     .05       0
Bank Sta=5154.1,5158.1
XS Rating Curve= 0 ,0
Exp/Cntr=0.3,0.1

Type RM Length L Ch R = 1 ,7341    ,528,528,528
BEGIN DESCRIPTION:
Anthony Branch Trib 3 11.0
END DESCRIPTION:
XS GIS Cut Line= 3
      2667804.72      6934789.51      2667339.54       6935324.3
      2666907.14      6935890.22
#Sta/Elev= 30
  4291.2  470.24  4546.1  467.11  4723.7  460.44  4780.1  460.38  4794.9  460.39
  4850.9  457.13  4929.4  456.76  4936.4  455.99    4943  453.75  4950.6  453.13
  4957.3  452.93  4964.9  454.72  4979.1  454.34  4983.7  451.28    4984  450.78
  4987.8  451.28  4993.4   453.8  5035.2  457.69  5071.4  458.89  5197.3  460.26
  5357.2   462.3  5371.8  463.44  5436.2  463.57  5492.3  465.67  5556.7  464.57
  5571.3   465.7  5606.6  466.17  5621.1   467.8  5656.5  467.36  5712.2  469.83
#Mann= 5 ,-1 , 0
  4291.2     .05       0  4780.1     .12       0  4983.7     .07       0
  4987.8     .12       0  5197.3     .05       0
Bank Sta=4983.7,4987.8
XS Rating Curve= 0 ,0
Exp/Cntr=0.3,0.1

Type RM Length L Ch R = 1 ,6813    ,759,759,759
BEGIN DESCRIPTION:
Anthony Branch Trib 3 10.0
END DESCRIPTION:
XS GIS Cut Line= 3
       2667762.2      6934603.72      2667067.93      6935114.63
      2666566.89      6935465.71
#Sta/Elev= 30
  4147.6  467.65  4179.6     468  4221.3  466.11  4329.1  465.03    4472  461.47
    4565  461.05    4708  456.78  4769.1  456.68  4808.3   455.2  4973.4   454.1
  4987.2  452.63  4992.2  449.45  4992.5  448.95  4996.3  449.45  5000.4  451.52
  5007.7  450.83    5015  452.02  5023.7  449.51  5029.8  449.46  5044.7  455.15
  5050.8  454.08  5059.5  456.48  5065.6  455.58  5080.4  456.85    5212  458.93
  5303.6  461.89  5330.6  465.25    5396  467.44    5518   469.9  5621.4  470.23
#Mann= 5 ,-1 , 0
  4147.6     .05       0  4769.1     .12       0  4992.2     .07       0
  4996.3     .12       0    5212     .05       0
Bank Sta=4992.2,4996.3
XS Rating Curve= 0 ,0
Exp/Cntr=0.3,0.1

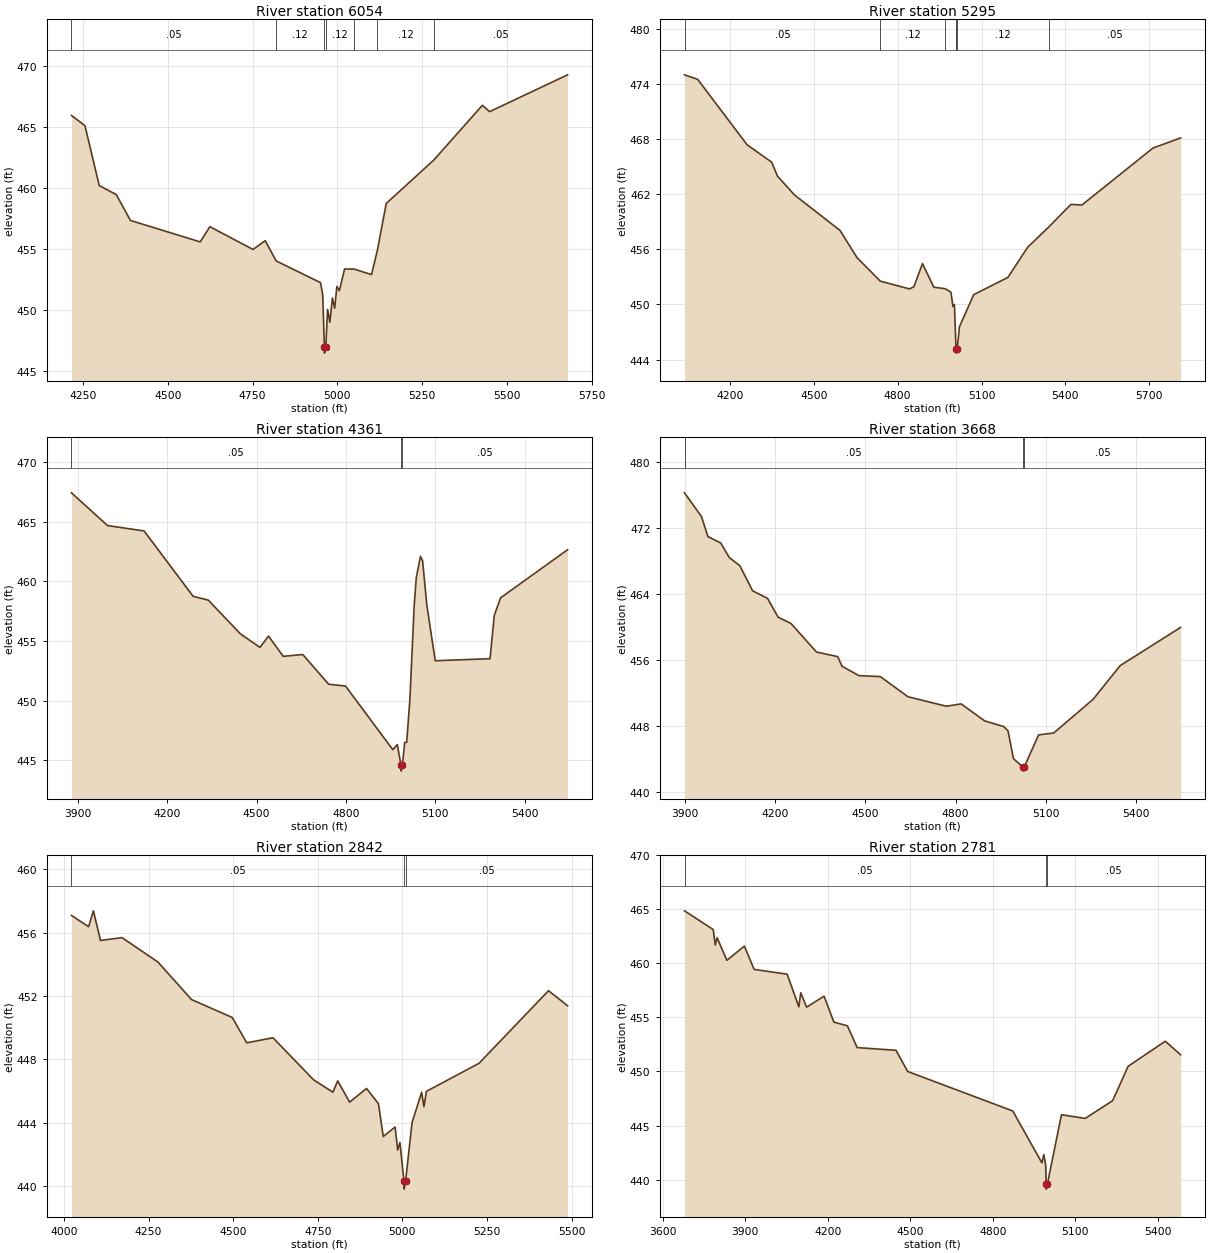
Type RM Length L Ch R = 1 ,6054    ,759,759,759
BEGIN DESCRIPTION:
Anthony Branch Trib 3 8.0
END DESCRIPTION:
XS GIS Cut Line= 3
      2667262.19      6934041.24      2666742.28      6934628.18
      2666387.78      6935206.95
#Sta/Elev= 30
  4215.9  465.92  4255.7  465.08  4297.8  460.17    4348  459.43  4389.8  457.31
  4595.5  455.55    4624   456.8  4751.1  454.93  4787.1  455.65  4819.5  453.99
  4950.2  452.21  4956.8  451.18  4961.6  446.93  4961.9  446.43  4965.8  446.93
  4971.1  450.02  4977.7  448.96  4985.3  450.95    4992  450.11  4998.5   451.9
  5005.8  451.55  5021.2  453.33  5049.4  453.32  5100.6  452.87  5117.8  454.85
    5144   458.7  5284.5  462.27  5427.5  466.75  5448.9  466.23  5678.7  469.25
#Mann= 7 ,-1 , 0
  4215.9     .05       0  4819.5     .12       0  4961.6     .07       0
  4965.8     .12       0  5049.4     .05       0  5117.8     .12       0
  5284.5     .05       0
Bank Sta=4961.6,4965.8
XS Rating Curve= 0 ,0
Exp/Cntr=0.3,0.1

Type RM Length L Ch R = 1 ,5295    ,934,934,934
BEGIN DESCRIPTION:
Anthony Branch Trib 3 7.0
END DESCRIPTION:
XS GIS Cut Line= 3
      2666473.14      6933314.65      2666291.06      6934260.28
      2666134.93      6935057.74
#Sta/Elev= 30
    4037  475.01  4084.2  474.52  4261.1  467.39    4349   465.5    4370  463.97
  4430.5  461.93  4593.4  458.07  4654.5   455.1  4737.8  452.54  4842.3  451.69
  4858.2  451.94  4888.7  454.45  4929.5  451.88  4970.5  451.71  4990.6  451.34
  4997.8  449.77  5003.1  449.99  5008.5  445.37  5008.7   445.2  5009.1   444.7
  5013.2   445.2  5021.1  447.57  5072.1  451.07  5194.3  452.94  5265.7  456.25
  5341.2  458.45  5420.1   460.9  5459.3  460.83    5714  467.04  5812.6  468.14
#Mann= 7 ,-1 , 0
    4037     .05       0  4737.8     .12       0  4970.5     .05       0
  5008.5     .12       0  5008.7     .03       0  5013.2     .12       0
  5341.2     .05       0
Bank Sta=5008.7,5013.2
XS Rating Curve= 0 ,0
Exp/Cntr=0.3,0.1

Type RM Length L Ch R = 1 ,4361    ,693,693,693
BEGIN DESCRIPTION:
Anthony Branch Trib 3 6.0
END DESCRIPTION:
XS GIS Cut Line= 3
      2666178.88      6933085.48      2665546.34       6934010.6
      2665164.25      6934396.98
#Sta/Elev= 30
  3879.3  467.44  4000.3  464.69  4122.9  464.24  4287.4  458.75  4338.2  458.43
  4445.9   455.6  4511.6  454.46  4540.2  455.41  4589.5  453.71  4655.2  453.86
  4741.9  451.37  4798.7  451.21  4957.2  445.87  4972.1   446.3  4984.7  444.57
  4985.2  444.07  4989.3  444.57  4997.2  446.49  5003.8  446.49  5014.6  450.15
  5028.8  457.92  5035.9  460.32    5050  462.11  5057.1  461.73  5071.2  458.02
  5099.5  453.34  5283.3  453.51  5297.5  457.14  5318.7  458.62  5543.4  462.66
#Mann= 3 ,-1 , 0
  3879.3     .05       0  4984.7     .05       0  4989.3     .05       0
Bank Sta=4984.7,4989.3
XS Rating Curve= 0 ,0
Exp/Cntr=0.3,0.1

Type RM Length L Ch R = 1 ,3668    ,826,826,826
BEGIN DESCRIPTION:
Anthony Branch Trib 3 3.0
END DESCRIPTION:
XS GIS Cut Line= 3
      2665825.97      6932711.03        2665076.        6933511.
        2665026.      6934060.98
#Sta/Elev= 30
  3898.9  476.28  3955.3   473.4  3976.8  470.97  4019.3  470.19  4047.6  468.43
  4082.8  467.43  4125.3  464.38  4174.6  463.48  4210.2  461.18  4252.7  460.42
  4337.5  456.95  4408.1  456.39  4422.3  455.23  4478.9  454.08  4549.7  453.97
  4641.6  451.52    4769  450.37  4818.4  450.65  4896.5  448.59    4960   447.9
  4974.2  447.38    4992  444.01  5023.3  442.99  5023.7  442.49  5027.9  442.99
  5075.8  446.89    5126  447.12  5256.5  451.19  5346.9   455.3  5547.7  459.94
#Mann= 3 ,-1 , 0
  3898.9     .05       0  5023.3     .03       0  5027.9     .05       0
Bank Sta=5023.3,5027.9
XS Rating Curve= 0 ,0
Exp/Cntr=0.3,0.1

Type RM Length L Ch R = 1 ,2842    ,61,61,61
BEGIN DESCRIPTION:
Anthony Branch Trib 3 5.0
END DESCRIPTION:
XS GIS Cut Line= 3
      2665164.12      6932368.04      2664438.86      6933023.86
      2664080.01      6933354.57
#Sta/Elev= 30
  4022.2  457.08  4072.8  456.37    4087  457.37    4108   455.5  4171.5  455.68
  4277.6  454.14    4377  451.77  4497.3  450.64  4539.9  449.04  4617.6  449.36
  4737.9   446.7  4794.7  445.93  4808.9  446.64    4844   445.3    4894  446.16
  4929.2   445.2  4943.4  443.13  4978.5  443.73    4986  442.28  4992.7  442.75
  5004.6  440.31  5005.1  439.81  5009.3  440.31  5028.5  444.01  5056.8  445.92
  5063.6  445.01    5071  445.98  5226.4  447.75  5431.7  452.33    5488  451.38
#Mann= 3 ,-1 , 0
  4022.2     .05       0  5004.6     .05       0  5009.3     .05       0
Bank Sta=5004.6,5009.3
XS Rating Curve= 0 ,0
Exp/Cntr=0.3,0.1

Type RM Length L Ch R = 1 ,2781    ,1066,1066,1066
BEGIN DESCRIPTION:
Anthony Branch Trib 3 4.0
END DESCRIPTION:
XS GIS Cut Line= 3
      2665309.06      6932026.06      2664395.89      6932980.89
      2664010.32      6933272.45
#Sta/Elev= 30
  3678.8  464.86  3783.3  463.13  3790.6   461.7  3797.5  462.37    3833  460.28
  3896.6   461.6  3932.1  459.44  4052.2     459  4094.7  455.98  4101.6  457.28
    4123  455.95  4186.5  456.97  4222.1  454.57  4271.5  454.22    4307  452.21
  4448.2  451.96  4490.7     450  4872.8  446.35  4978.8  441.55    4986  442.31
  4992.9  441.28  4994.2  439.62  4994.8  439.12    4999  439.62    5050     446
  5136.3  445.66  5236.2   447.3  5292.4  450.48  5427.7   452.8  5483.4  451.55
#Mann= 3 ,-1 , 0
  3678.8     .05       0  4994.2     .05       0    4999     .05       0
Bank Sta=4994.2,4999
XS Rating Curve= 0 ,0
Exp/Cntr=0.3,0.1

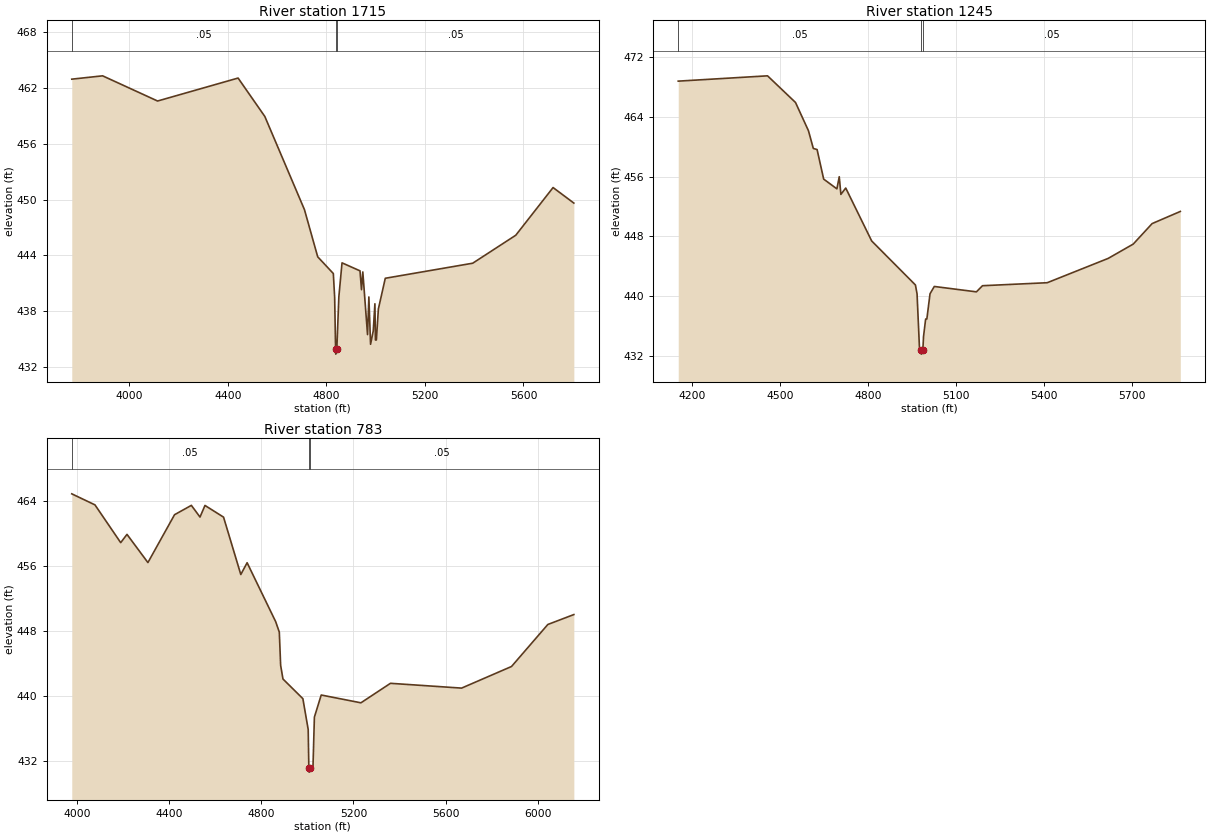
Type RM Length L Ch R = 1 ,1715    ,470,470,470
BEGIN DESCRIPTION:
Anthony Branch Trib 3 2.0
END DESCRIPTION:
XS GIS Cut Line= 3
       2663195.2      6931160.79      2663641.47      6932309.99
       2663825.4      6933093.07
#Sta/Elev= 30
  3767.2  462.95  3892.3  463.31  4115.4   460.6  4442.1  463.07  4550.5  458.94
  4711.4  448.91  4765.1  443.84  4828.5  442.04  4833.9  439.45  4837.7  433.87
  4838.3  433.37  4842.6  433.87  4850.9  439.54  4863.8  443.19  4936.7  442.33
  4942.8   440.3  4948.1  442.21  4967.3  435.47  4972.7  439.52  4979.6  434.43
  4990.4  435.85  4997.2  438.79  4999.4  434.89  5003.1  434.89  5011.3  438.23
  5039.3  441.53    5394  443.15  5568.8  446.16  5720.1  451.29  5804.4  449.62
#Mann= 3 ,-1 , 0
  3767.2     .05       0  4837.7     .03       0  4842.6     .05       0
Bank Sta=4837.7,4842.6
XS Rating Curve= 0 ,0
Exp/Cntr=0.3,0.1

Type RM Length L Ch R = 1 ,1245    ,462,462,462
BEGIN DESCRIPTION:
Mapping XS 6abe7e96
END DESCRIPTION:
XS GIS Cut Line= 3
      2662846.93      6931560.65      2663237.56      6932313.27
      2663758.37      6933003.34
#Sta/Elev= 30
  4152.8  468.74  4457.4  469.45  4552.8  465.89    4597  462.11  4613.5  459.75
  4626.4   459.6  4648.9  455.65    4694  454.35    4702  455.97  4707.6  453.61
  4724.1  454.46  4812.6  447.39  4961.8  441.51  4967.4  440.31  4975.7  433.02
  4980.7  432.77  4981.8  432.27  4987.1  432.77  4989.5  434.63  4996.7  436.96
  5000.8  436.96  5011.6  440.33  5026.2  441.31  5169.8  440.59  5190.6  441.41
  5411.4  441.81  5619.4  445.06  5704.7  446.97  5769.2  449.71  5865.3  451.33
#Mann= 3 ,-1 , 0
  4152.8     .05       0  4980.7     .04       0  4987.1     .05       0
Bank Sta=4980.7,4987.1
XS Rating Curve= 0 ,0
Exp/Cntr=0.3,0.1

Type RM Length L Ch R = 1 ,783     ,0,0,0
BEGIN DESCRIPTION:
Anthony Branch Trib 3 1.0
END DESCRIPTION:
XS GIS Cut Line= 3
      2662284.62      6931473.55      2662791.21      6932361.51
      2663736.03      6933029.14
#Sta/Elev= 30
  3977.7  464.93  4078.4  463.57  4190.1  458.92  4217.4  459.94  4308.2  456.47
  4423.8  462.36  4496.8  463.51  4534.3  462.07  4555.9   463.5  4636.5  462.06
  4711.4     455  4738.8  456.45  4862.7   449.2  4878.5  447.91  4884.3  443.82
  4894.4  442.14  4980.8  439.72  5003.9  435.92  5006.7  431.18  5007.7  430.68
  5013.1  431.18  5024.7  431.34  5030.8  437.45  5060.4  440.17  5232.7  439.21
    5361  441.61  5669.7  441.02  5886.4  443.68    6044  448.85  6156.9  450.07
#Mann= 3 ,-1 , 0
  3977.7     .05       0  5006.7     .03       0  5013.1     .05       0
Bank Sta=5006.7,5013.1
XS Rating Curve= 0 ,0
Exp/Cntr=0.3,0.1

Chan Stop Cuts=-1
Use User Specified Reach Order=0
Composite Channel Slope=5