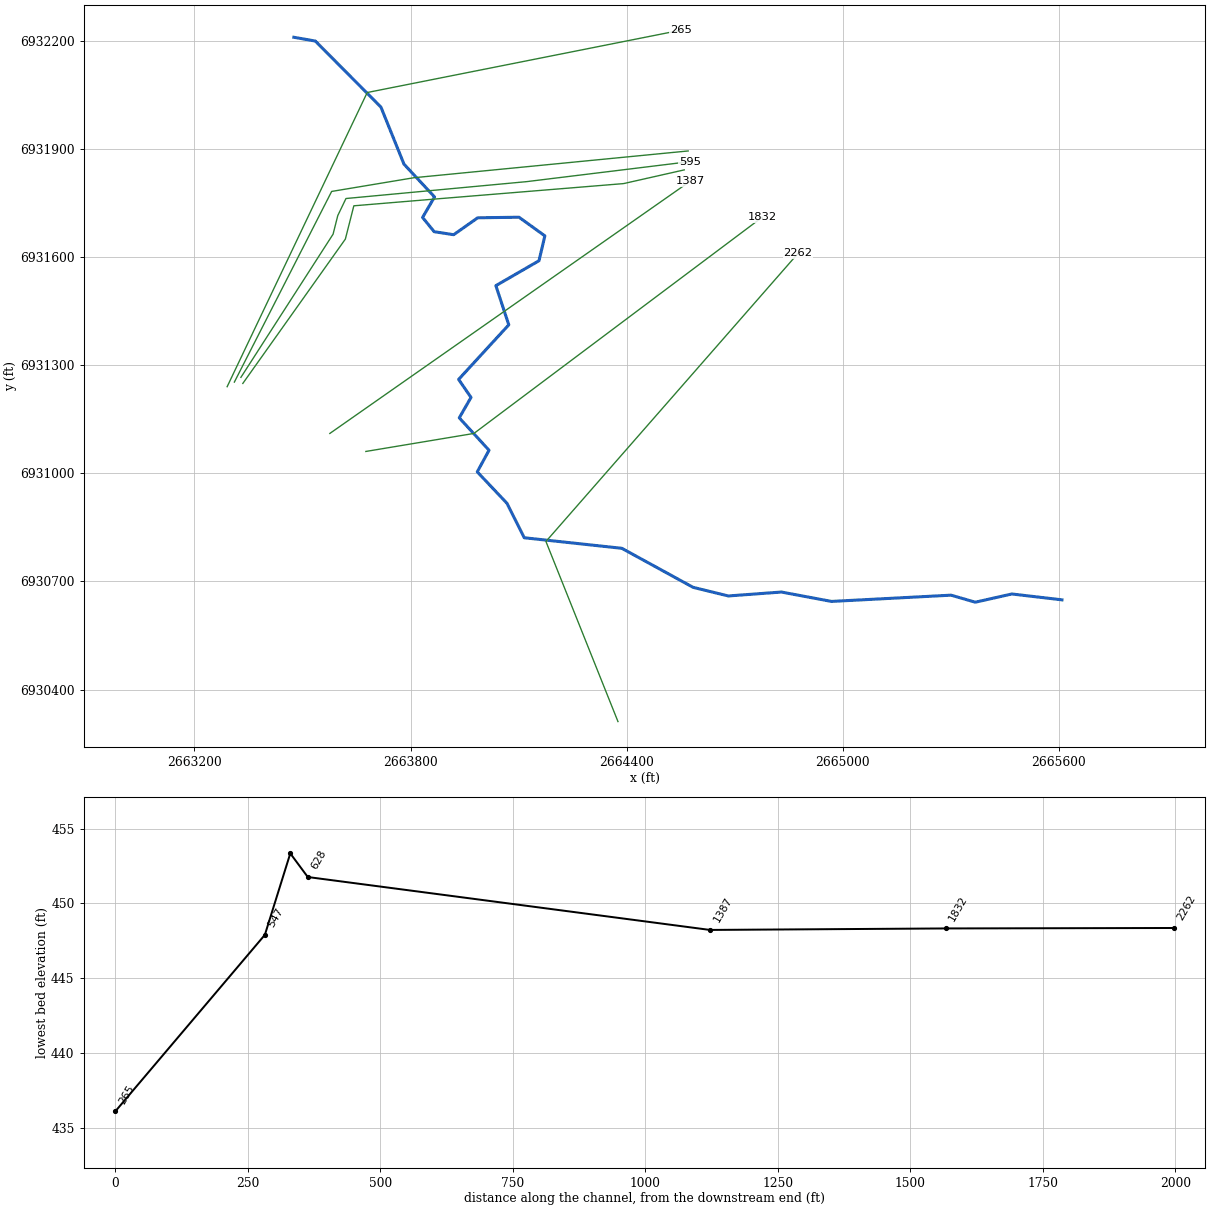
--- Anthony Branch Trib 3_1.prj (project) ---

Proj Title=Anthony Branch Trib 3_1 Base Level Engineering
Current Plan=p01
Default Exp/Contr=0.3,0.1
English Units
Geom File=g01
Flow File=f01
Plan File=p01
BEGIN DESCRIPTION:
Anthony Branch Trib 3_1
END DESCRIPTION:

--- Anthony Branch Trib 3_1.p01 (plan) ---

Plan Title=Multiple Run
Short Identifier=Multiple
Geom File=g01
Flow File=f01
Subcritical Flow
K Sum by GR= 0
Std Step Tol= 0.01
Critical Tol= 0.01
Num of Std Step Trials= 20
Max Error Tol= 0.3
Flow Tol Ratio= 0.001
Split Flow NTrial= 30
Split Flow Tol= 0.02
Split Flow Ratio= 0.02
Log Output Level= 0
Friction Slope Method= 1
Unsteady Friction Slope Method= 2
Unsteady Bridges Friction Slope Method= 1
Parabolic Critical Depth
Global Vel Dist=  1 , 1 , 1
Global Log Level= 0
CheckData=True
Encroach Param= -1, 0, 0, 0
BEGIN DESCRIPTION:
Multiple Run
END DESCRIPTION:

--- Anthony Branch Trib 3_1.f01 (steady flow) ---

Flow Title=Multiple
Number of Profiles=7
Profile Names=10-year,25-year,50-year,1pct_min,100-year,1pct_plu,500-year
River Rch & RM= Anthony Branch T,Reach-1,2262
     466     615     734     434     867    1730    1209
Boundary for River Rch & Prof#=Anthony Branch T,Reach-1,1
Up Type=0
Dn Type=3
Dn Slope=0.005
Boundary for River Rch & Prof#=Anthony Branch T,Reach-1,2
Up Type=0
Dn Type=3
Dn Slope=0.005
Boundary for River Rch & Prof#=Anthony Branch T,Reach-1,3
Up Type=0
Dn Type=3
Dn Slope=0.005
Boundary for River Rch & Prof#=Anthony Branch T,Reach-1,4
Up Type=0
Dn Type=3
Dn Slope=0.005
Boundary for River Rch & Prof#=Anthony Branch T,Reach-1,5
Up Type=0
Dn Type=3
Dn Slope=0.005
Boundary for River Rch & Prof#=Anthony Branch T,Reach-1,6
Up Type=0
Dn Type=3
Dn Slope=0.005
Boundary for River Rch & Prof#=Anthony Branch T,Reach-1,7
Up Type=0
Dn Type=3
Dn Slope=0.005

--- Anthony Branch Trib 3_1.g01 (geometry) ---

Geom Title=Existing Conditions

River Reach=Anthony Branch T,Reach-1
Reach XY= 30
      2665608.66      6930648.99      2665469.72      6930665.26
      2665368.10      6930642.42      2665300.82      6930661.95
      2664968.79      6930644.59      2664829.90      6930670.63
      2664682.33      6930659.78      2664584.68      6930683.65
      2664386.68      6930792.09      2664115.88      6930821.34
      2664067.79      6930917.03      2663985.32      6931004.34
      2664017.97      6931064.33      2663935.32      6931154.33
      2663967.95      6931211.00      2663933.54      6931261.00
      2664072.84      6931412.65      2664036.98      6931521.37
      2664156.74      6931590.54      2664173.02      6931659.57
      2664101.22      6931711.36      2663986.50      6931709.77
      2663919.79      6931662.78      2663865.61      6931671.19
      2663833.47      6931710.72      2663866.68      6931767.65
      2663781.86      6931858.70      2663717.86      6932017.06
      2663535.79      6932200.49      2663476.00      6932211.00

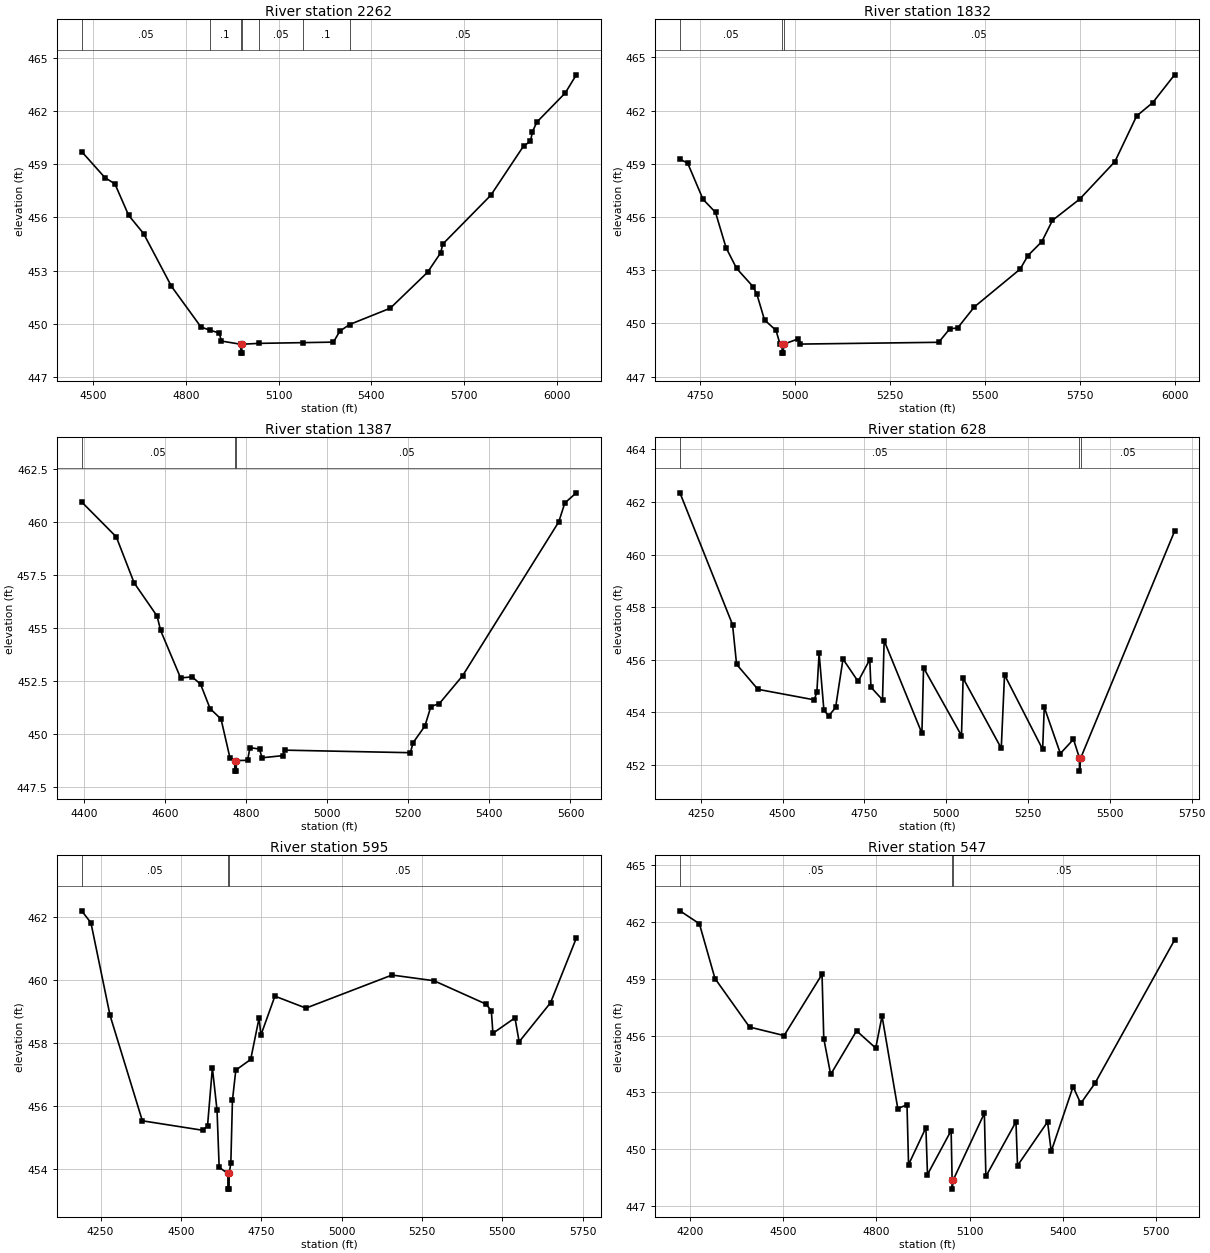
Type RM Length L Ch R = 1,2262,430,430,430
BEGIN DESCRIPTION:
Anthony Branch Trib 3_1 5.0
END DESCRIPTION:
XS GIS Cut Line= 3
      2664375.99      6930311.02      2664176.00      6930811.00
      2664875.99      6931610.99
#Sta/Elev= 30
  4462.0  459.71  4537.4  458.24  4569.7  457.89  4614.1  456.12  4662.6  455.09
  4752.8  452.12  4848.4  449.83  4876.1  449.66  4907.6  449.49  4914.3  449.04
  4977.0  448.86  4977.2  448.36  4980.7  448.36  4981.0  448.86  5036.8  448.91
  5177.1  448.95  5277.2  448.98  5298.0  449.60  5329.5  449.97  5461.3  450.89
  5581.8  452.91  5624.5  454.01  5631.2  454.50  5786.8  457.25  5893.1  460.03
  5915.0  460.28  5921.6  460.83  5935.9  461.37  6027.9  463.01  6063.5  464.03
#Mann=7,-1,0
  4462.0    0.05       0  4876.1     0.1       0  4977.0    0.07       0
  4981.0     0.1       0  5036.8    0.05       0  5177.1     0.1       0
  5329.5    0.05       0
Bank Sta=4977,4981
Exp/Cntr=0.3,0.1

Type RM Length L Ch R = 1,1832,445,445,445
BEGIN DESCRIPTION:
Anthony Branch Trib 3_1 4.0
END DESCRIPTION:
XS GIS Cut Line= 3
      2663676.02      6931061.00      2663976.00      6931111.00
      2664775.99      6931710.99
#Sta/Elev= 30
  4695.9  459.25  4716.2  459.04  4756.7  457.00  4789.7  456.26  4817.5  454.27
  4845.4  453.10  4888.5  452.08  4898.6  451.66  4918.9  450.20  4949.3  449.61
  4959.5  448.85  4965.1  448.83  4965.3  448.33  4968.8  448.33  4969.1  448.83
  5007.3  449.13  5013.6  448.84  5378.1  448.94  5407.3  449.70  5428.1  449.75
  5471.9  450.93  5592.7  453.06  5613.6  453.83  5650.0  454.61  5678.1  455.81
  5750.0  457.01  5842.7  459.12  5900.0  461.69  5942.7  462.45  6000.0  464.01
#Mann=3,-1,0
  4695.9    0.05       0  4965.1    0.03       0  4969.1    0.05       0
Bank Sta=4965.1,4969.1
Exp/Cntr=0.3,0.1

Type RM Length L Ch R = 1,1387,759,759,759
BEGIN DESCRIPTION:
Anthony Branch Trib 3_1 3.0
END DESCRIPTION:
XS GIS Cut Line= 3
      2663575.96      6931110.97      2664076.00      6931461.00
      2664576.00      6931811.00
#Sta/Elev= 30
  4393.7  460.94  4479.2  459.29  4523.2  457.12  4579.9  455.55  4588.6  454.87
  4637.9  452.63  4666.2  452.68  4687.1  452.34  4710.7  451.18  4737.7  450.69
  4759.9  448.84  4771.5  448.73  4771.7  448.23  4775.2  448.23  4775.5  448.73
  4803.1  448.74  4809.2  449.34  4832.7  449.27  4838.8  448.86  4889.4  448.96
  4895.5  449.22  5205.0  449.10  5211.6  449.57  5240.8  450.36  5255.6  451.28
  5276.5  451.42  5333.7  452.73  5571.2  460.00  5586.1  460.89  5614.4  461.37
#Mann=3,-1,0
  4393.7    0.05       0  4771.5    0.03       0  4775.5    0.05       0
Bank Sta=4771.5,4775.5
Exp/Cntr=0.3,0.1

Type RM Length L Ch R = 1,628,33,33,33
BEGIN DESCRIPTION:
Mapping XS f9434644
END DESCRIPTION:
XS GIS Cut Line= 6
      2663334.40      6931249.89      2663619.06      6931650.59
      2663642.63      6931743.06      2663860.21      6931761.19
      2664391.44      6931804.70      2664560.11      6931842.79
#Sta/Elev= 30
  4186.6  462.35  4347.3  457.34  4359.7  455.83  4424.8  454.88  4597.0  454.48
  4605.0  454.78  4611.8  456.25  4626.5  454.08  4641.3  453.87  4662.2  454.19
  4684.8  456.03  4730.9  455.18  4766.6  456.01  4770.2  454.96  4805.5  454.48
  4810.5  456.73  4925.9  453.21  4930.9  455.70  5046.8  453.12  5051.8  455.30
  5168.3  452.64  5178.3  455.43  5294.7  452.60  5299.7  454.20  5348.9  452.44
  5389.0  452.98  5407.1  452.27  5407.3  451.77  5411.1  452.27  5697.8  460.89
#Mann=3,-1,0
  4186.6    0.05       0  5407.1    0.03       0  5411.1    0.05       0
Bank Sta=5407.1,5411.1
Exp/Cntr=0.3,0.1

Type RM Length L Ch R = 1,595,48,48,48
BEGIN DESCRIPTION:
Mapping XS 54b31577
END DESCRIPTION:
XS GIS Cut Line= 6
      2663329.07      6931266.73      2663585.00      6931664.34
      2663598.02      6931715.90      2663620.76      6931763.30
      2664122.50      6931810.17      2664575.60      6931865.73
#Sta/Elev= 30
  4191.1  462.19  4220.0  461.81  4279.4  458.87  4380.0  455.52  4567.5  455.22
  4582.7  455.35  4597.9  457.20  4612.4  455.85  4619.0  454.04  4646.1  453.85
  4646.3  453.35  4649.8  453.35  4650.1  453.85  4655.3  454.17  4660.3  456.17
  4670.8  457.13  4717.1  457.47  4743.3  458.79  4748.8  458.24  4792.4  459.48
  4889.0  459.10  5156.8  460.15  5287.3  459.97  5448.7  459.23  5465.8  459.02
  5470.8  458.30  5539.4  458.79  5552.4  458.03  5650.1  459.27  5730.2  461.32
#Mann=3,-1,0
  4191.1    0.05       0  4646.1    0.04       0  4650.1    0.05       0
Bank Sta=4646.1,4650.1
Exp/Cntr=0.3,0.1

Type RM Length L Ch R = 1,547,282,282,282
BEGIN DESCRIPTION:
Mapping XS 9bc714ef
END DESCRIPTION:
XS GIS Cut Line= 4
      2663310.84      6931253.54      2663580.99      6931782.95
      2663809.44      6931821.02      2664570.97      6931895.36
#Sta/Elev= 30
  4168.2  462.58  4230.8  461.90  4280.9  459.01  4392.0  456.45  4503.2  456.00
  4625.3  459.23  4630.9  455.84  4653.1  453.95  4736.4  456.25  4798.0  455.34
  4818.3  457.03  4869.0  452.15  4898.6  452.35  4903.6  449.19  4959.4  451.14
  4964.5  448.67  5040.6  450.99  5043.7  448.40  5043.9  447.90  5047.7  448.40
  5147.4  451.90  5152.4  448.57  5249.1  451.45  5254.1  449.14  5350.8  451.45
  5362.5  449.89  5432.8  453.30  5457.5  452.42  5503.1  453.48  5759.3  461.04
#Mann=3,-1,0
  4168.2    0.05       0  5043.7    0.04       0  5047.7    0.05       0
Bank Sta=5043.7,5047.7
Exp/Cntr=0.3,0.1

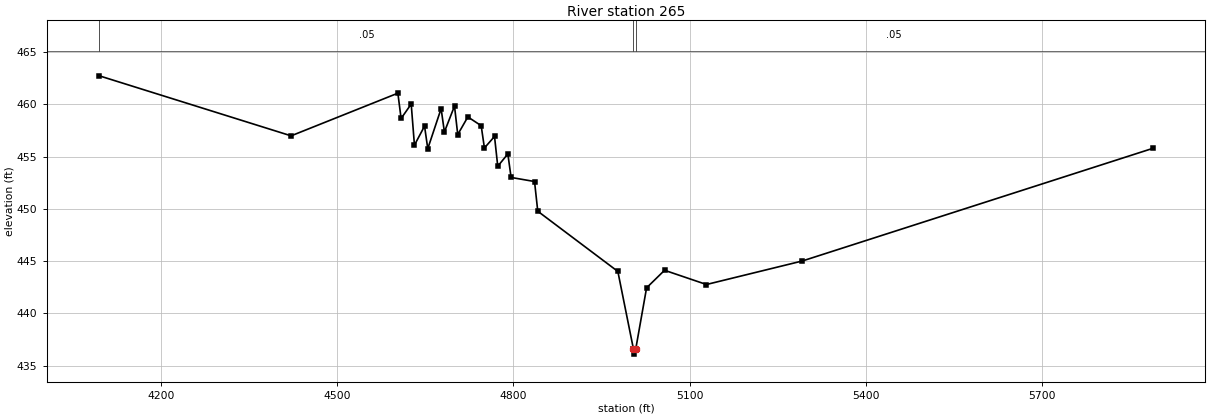
Type RM Length L Ch R = 1,265,0,0,0
BEGIN DESCRIPTION:
Anthony Branch Trib 3_1 1.0
END DESCRIPTION:
XS GIS Cut Line= 3
      2663290.89      6931240.83      2663679.75      6932057.59
      2664551.00      6932230.78
#Sta/Elev= 30
  4095.4  462.72  4421.8  456.98  4603.5  461.06  4609.0  458.64  4626.2  460.02
  4631.7  456.09  4648.9  457.91  4654.4  455.75  4677.1  459.58  4682.7  457.35
  4699.9  459.83  4705.4  457.10  4722.6  458.79  4745.3  457.95  4750.8  455.82
  4768.0  456.92  4773.5  454.07  4790.7  455.25  4796.2  453.00  4836.1  452.61
  4841.6  449.77  4977.9  444.01  5004.4  436.60  5004.6  436.10  5008.4  436.60
  5026.8  442.44  5057.4  444.12  5128.7  442.76  5291.9  445.01  5888.3  455.78
#Mann=3,-1,0
  4095.4    0.05       0  5004.4    0.04       0  5008.4    0.05       0
Bank Sta=5004.4,5008.4
Exp/Cntr=0.3,0.1

Chan Stop Cuts=-1