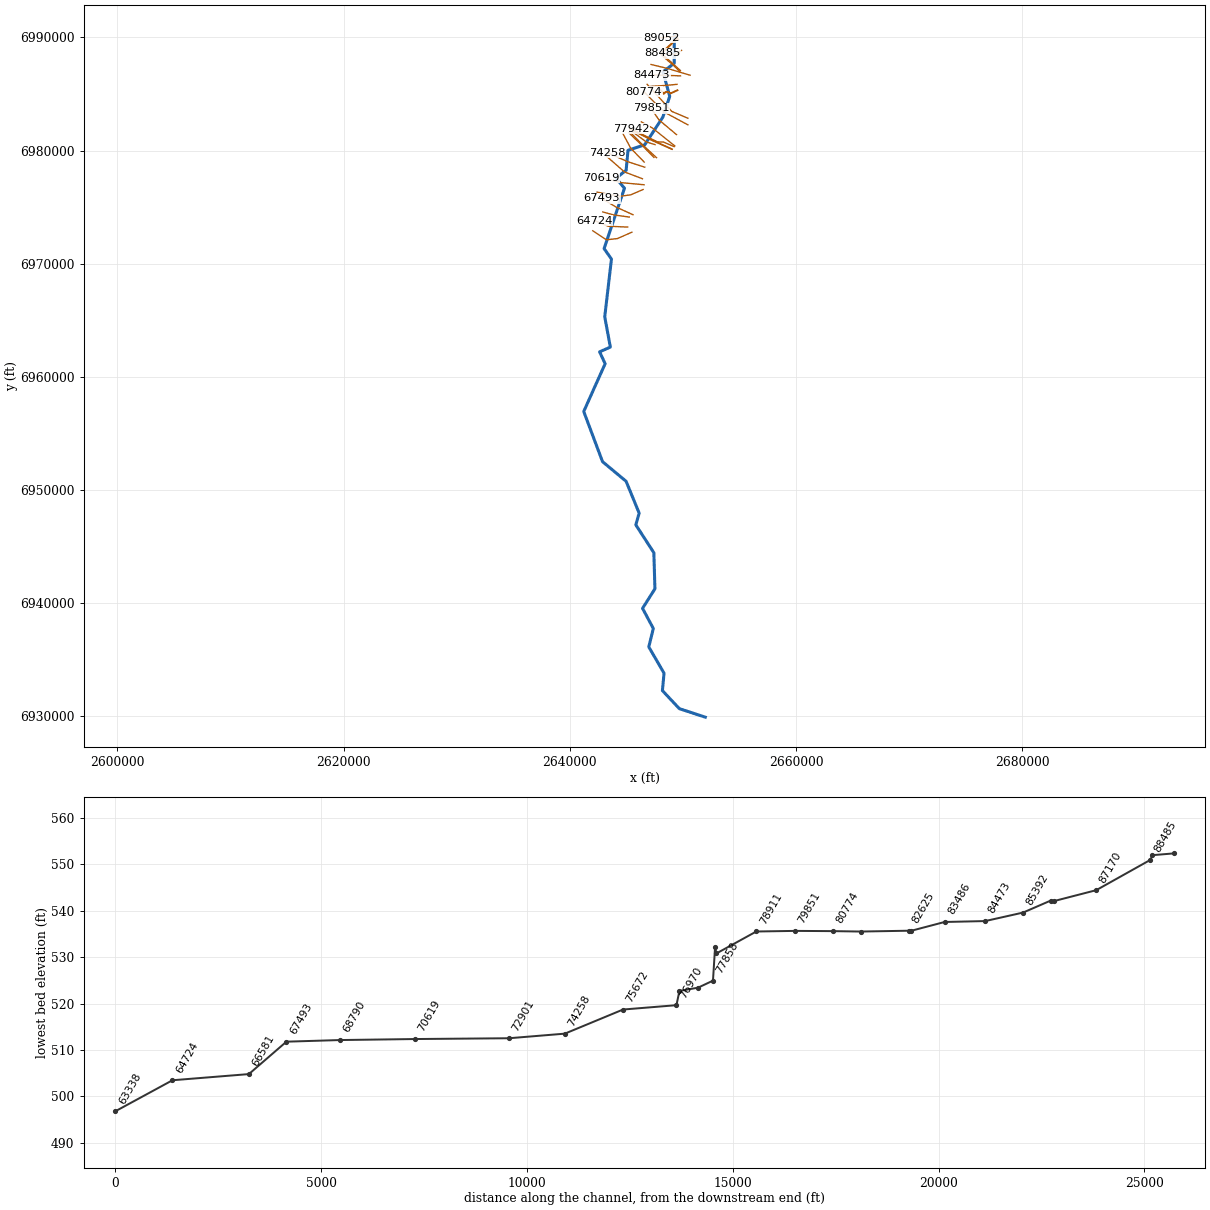
--- Bachelor Creek.prj (project) ---

Proj Title=Bachelor Creek Base Level Engineering
Current Plan=p01
Default Exp/Contr=0.3,0.1
English Units
Geom File=g01
Flow File=f01
Plan File=p01
Y Axis Title=Elevation
X Axis Title(PF)=Main Channel Distance
X Axis Title(XS)=Station
BEGIN DESCRIPTION:
Bachelor Creek
END DESCRIPTION:
DSS Export Rating Curves= 0
DSS Export Rating Curve Sorted= 0
DSS Export Volume Flow Curves= 0
DXF OffsetX= 0
DXF OffsetY= 0
DXF ScaleX= 1
DXF ScaleY= 10

--- Bachelor Creek.p01 (plan) ---

Plan Title=Multiple Run
Short Identifier=Multiple
Geom File=g01
Flow File=f01
Subcritical Flow
K Sum by GR= 0
Std Step Tol= 0.01
Critical Tol= 0.01
Num of Std Step Trials= 20
Max Error Tol= 0.3
Flow Tol Ratio= 0.001
Split Flow NTrial= 30
Split Flow Tol= 0.02
Split Flow Ratio= 0.02
Log Output Level= 0
Friction Slope Method= 1
Unsteady Friction Slope Method= 2
Unsteady Bridges Friction Slope Method= 1
Parabolic Critical Depth
Global Vel Dist=  1 , 1 , 1
Global Log Level= 0
CheckData=True
Encroach Param= -1, 0, 0, 0
BEGIN DESCRIPTION:
Multiple Run
END DESCRIPTION:

--- Bachelor Creek.f01 (steady flow) ---

Flow Title=Multiple
Program Version=4.10
Number of Profiles= 7
Profile Names=10-year,25-year,50-year,1pct_min,100-year,1pct_plu,500-year
River Rch & RM=Bachelor Creek,Reach-1         ,89052
     505     669     799     474     945    1885    1321
River Rch & RM=Bachelor Creek,Reach-1         ,87170
     627     838    1008     601    1199    2392    1696
River Rch & RM=Bachelor Creek,Reach-1         ,85392
     686     917    1103     657    1312    2617    1854
River Rch & RM=Bachelor Creek,Reach-1         ,81448
    1036    1417    1729    1044    2083    4156    3024
River Rch & RM=Bachelor Creek,Reach-1         ,79851
    1357    1880    2315    1409    2812    5611    4151
River Rch & RM=Bachelor Creek,Reach-1         ,72901
    1393    1924    2363    1434    2861    5708    4196
River Rch & RM=Bachelor Creek,Reach-1         ,67493
    1790    2500    3094    1890    3771    7524    5607
River Rch & RM=Bachelor Creek,Reach-1         ,61464
    2016    2830    3513    2153    4295    8570    6425
River Rch & RM=Bachelor Creek,Reach-1         ,59940
    2051    2879    3575    2190    4371    8720    6537
River Rch & RM=Bachelor Creek,Reach-1         ,58414
    2208    3108    3866    2372    4733    9445    7102
River Rch & RM=Bachelor Creek,Reach-1         ,56500
    2323    3270    4069    2497    4982    9941    7475
River Rch & RM=Bachelor Creek,Reach-1         ,51257
    2489    3511    4374    2687    5361   10696    8058
River Rch & RM=Bachelor Creek,Reach-1         ,47485
    2591    3655    4553    2795    5578   11129    8379
River Rch & RM=Bachelor Creek,Reach-1         ,40718
    2661    3750    4670    2866    5718   11408    8579
River Rch & RM=Bachelor Creek,Reach-1         ,35711
    2857    4039    5039    3097    6180   12330    9304
River Rch & RM=Bachelor Creek,Reach-1         ,32794
    2884    4074    5081    3122    6229   12428    9368
River Rch & RM=Bachelor Creek,Reach-1         ,31293
    2963    4194    5236    3221    6428   12825    9693
River Rch & RM=Bachelor Creek,Reach-1         ,29582
    2961    4188    5226    3213    6411   12791    9654
River Rch & RM=Bachelor Creek,Reach-1         ,26475
    2882    4083    5101    3139    6263   12496    9454
River Rch & RM=Bachelor Creek,Reach-1         ,26326
    2912    4122    5145    3164    6314   12598    9518
River Rch & RM=Bachelor Creek,Reach-1         ,16643
    3043    4314    5392    3319    6622   13213   10001
River Rch & RM=Bachelor Creek,Reach-1         ,14851
    3113    4415    5520    3398    6780   13529   10244
River Rch & RM=Bachelor Creek,Reach-1         ,9507
    3250    4615    5775    3558    7100   14166   10744
River Rch & RM=Bachelor Creek,Reach-1         ,7297
    3346    4752    5945    3663    7309   14583   11057
River Rch & RM=Bachelor Creek,Reach-1         ,172
    3390    4816    6028    3715    7412   14789   11218
Boundary for River Rch & Prof#=Bachelor Creek,Reach-1         , 1
Up Type= 0
Dn Type= 3
Dn Slope=0.00146
Boundary for River Rch & Prof#=Bachelor Creek,Reach-1         , 2
Up Type= 0
Dn Type= 3
Dn Slope=0.00146
Boundary for River Rch & Prof#=Bachelor Creek,Reach-1         , 3
Up Type= 0
Dn Type= 3
Dn Slope=0.00146
Boundary for River Rch & Prof#=Bachelor Creek,Reach-1         , 4
Up Type= 0
Dn Type= 3
Dn Slope=0.00146
Boundary for River Rch & Prof#=Bachelor Creek,Reach-1         , 5
Up Type= 0
Dn Type= 3
Dn Slope=0.00146
Boundary for River Rch & Prof#=Bachelor Creek,Reach-1         , 6
Up Type= 0
Dn Type= 3
Dn Slope=0.00146
Boundary for River Rch & Prof#=Bachelor Creek,Reach-1         , 7
Up Type= 0
Dn Type= 3
Dn Slope=0.00146
DSS Import GetInterval= 0
DSS Import GetPeak= 0
DSS Import FillOption= 0

--- Bachelor Creek.g01 (geometry) ---

Geom Title=Existing Conditions
Program Version=4.10

River Reach=Bachelor Creek  ,Reach-1
Reach XY= 30
        2649226.        6990211.      2649224.38      6987717.03
      2648233.21      6986961.35      2648826.49       6984795.8
      2648222.46      6982962.47      2646620.39      6980516.59
      2645136.48       6980020.8       2644972.9      6978262.65
      2644083.67      6977564.66      2644825.47      6976671.69
      2643025.58      6971336.01        2643676.        6970411.
      2643083.28       6965310.9      2643576.11      6962626.36
      2642629.02      6962209.61       2643118.5      6961157.83
      2641225.67      6956935.79      2642887.08      6952500.95
      2644970.54      6950764.02      2646125.24      6947950.31
      2645829.45      6946912.19      2647424.53      6944448.87
      2647518.52      6941257.38      2646425.45      6939531.11
      2647374.46       6937755.2      2646977.03      6936121.43
      2648324.95      6933799.28      2648179.82      6932262.58
      2649673.53      6930666.45        2651976.        6929911.

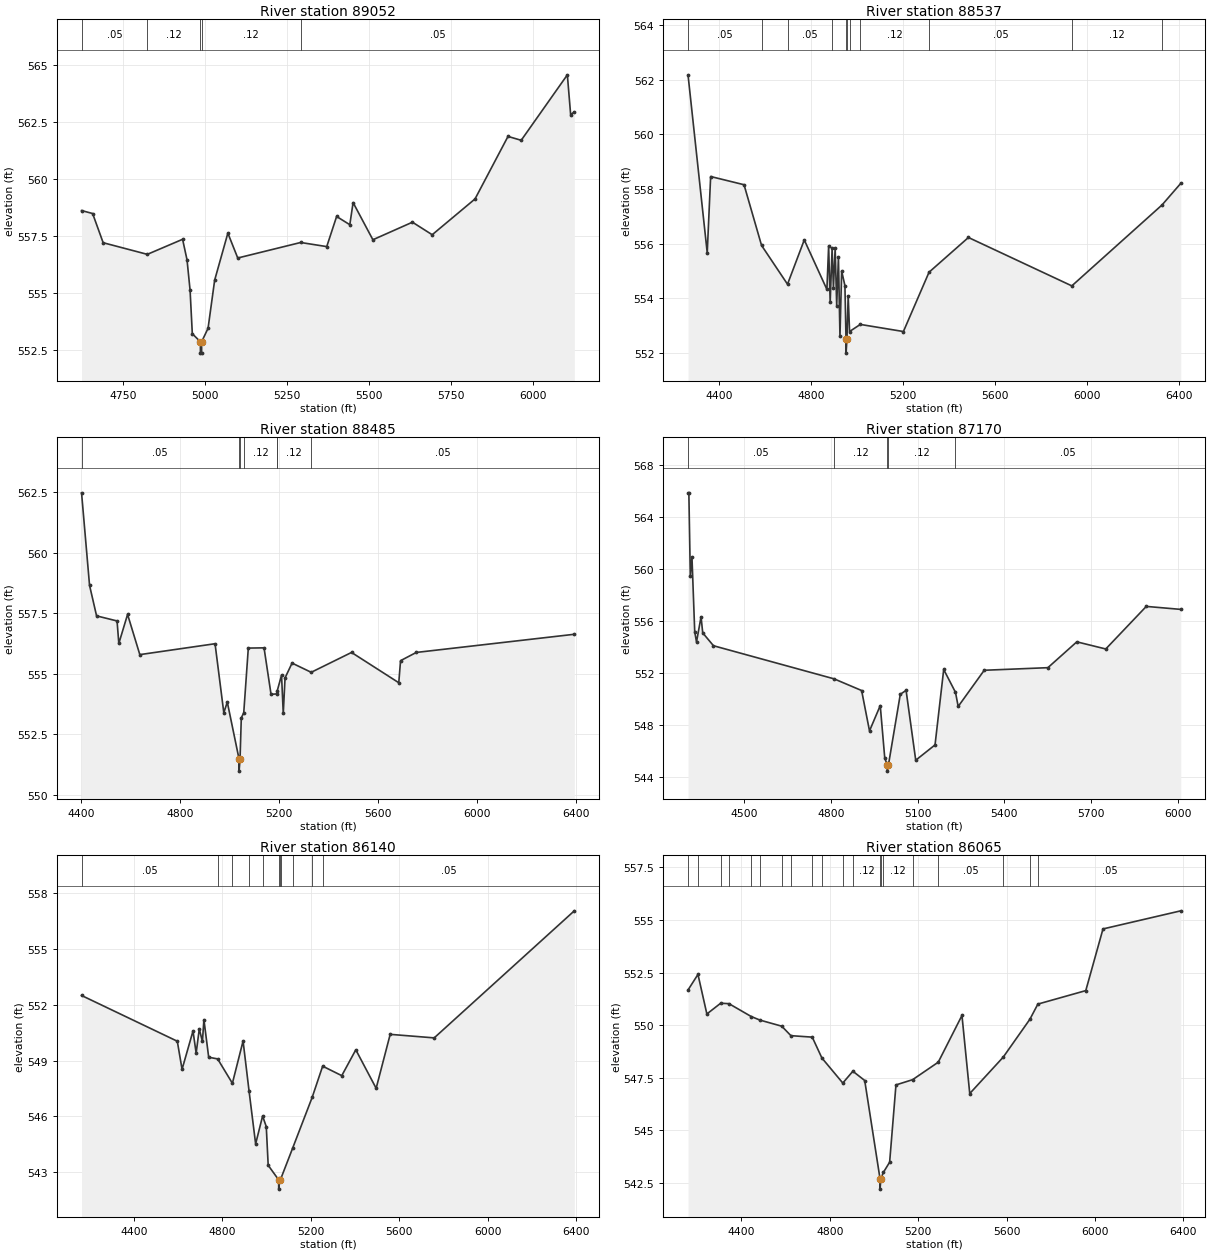
Type RM Length L Ch R = 1 ,89052   ,515,515,515
BEGIN DESCRIPTION:
Bachelor Creek 143.0
END DESCRIPTION:
XS GIS Cut Line= 3
      2649505.54      6990259.43      2649182.73      6990081.42
      2648054.86      6989979.51
#Sta/Elev= 30
  4624.2  558.63  4657.9   558.5    4690  557.22  4824.6  556.71    4932  557.37
  4945.5  556.47  4954.8  555.14  4961.6  553.23  4986.1  552.88  4986.4  552.38
  4989.9  552.38  4990.1  552.88  5009.6  553.47  5029.7  555.58  5069.9  557.64
    5100  556.55  5291.7  557.23  5371.1  557.05  5401.2  558.37  5441.4  558.01
  5451.4  558.98  5511.7  557.35  5632.2  558.12  5692.4  557.57  5822.9  559.14
  5923.3  561.88  5963.5  561.71  6104.1  564.58  6114.1  562.84  6125.3  562.95
#Mann= 5 ,-1 , 0
  4624.2     .05       0  4824.6     .12       0  4986.1     .08       0
  4990.1     .12       0  5291.7     .05       0
Bank Sta=4986.1,4990.1
XS Rating Curve= 0 ,0
Exp/Cntr=0.3,0.1

Type RM Length L Ch R = 1 ,88537   ,52,52,52
BEGIN DESCRIPTION:
Bachelor Creek 142.0
END DESCRIPTION:
XS GIS Cut Line= 4
      2649599.97      6989809.17      2649472.37      6989993.02
        2649126.        6989611.      2648093.57      6988657.26
#Sta/Elev= 30
  4264.8  562.18  4348.4  555.67  4363.3  558.46  4508.6  558.16  4584.9  555.94
  4697.9  554.52  4770.8  556.14  4869.4  554.33  4876.9  555.92  4883.6  553.86
    4892  555.83  4897.8   554.4  4905.3  555.83    4912  553.74  4919.5  555.52
  4926.2  552.62  4933.6     555  4947.8  554.47  4952.6   552.5  4952.8     552
  4956.6   552.5    4962   554.1    4968  552.79  5014.8  553.05  5202.4  552.79
    5314  554.96  5485.4  556.23  5935.5  554.46  6328.2  557.42  6409.8  558.21
#Mann= 11 ,-1 , 0
  4264.8     .05       0  4584.9     .12       0  4697.9     .05       0
    4892     .12       0  4952.6     .03       0  4956.6     .12       0
    4968     .05       0  5014.8     .12       0    5314     .05       0
  5935.5     .12       0  6328.2     .05       0
Bank Sta=4952.6,4956.6
XS Rating Curve= 0 ,0
Exp/Cntr=0.3,0.1

Type RM Length L Ch R = 1 ,88485   ,1315,1315,1315
BEGIN DESCRIPTION:
Bachelor Creek 141.0
END DESCRIPTION:
XS GIS Cut Line= 4
      2649578.28      6989797.21      2649488.17      6989899.27
       2649162.1      6989574.16      2648163.89      6988599.97
#Sta/Elev= 30
  4403.4  562.47  4435.7  558.65  4464.1  557.39  4546.9  557.18    4554  556.25
  4589.4  557.45  4638.9  555.79  4942.9  556.24  4978.3  553.39  4992.4  553.83
  5039.9  551.48  5040.1  550.98  5043.9  551.48    5049  553.18  5058.9  553.39
  5077.3  556.06  5140.9  556.07  5169.2  554.15  5193.3  554.17  5194.1  554.29
  5211.6  554.94  5218.6  553.36  5225.8  554.83  5254.1  555.44  5331.5  555.06
  5494.5  555.88  5685.4  554.63  5692.6  555.54  5756.1  555.88  6394.8  556.63
#Mann= 7 ,-1 , 0
  4403.4     .05       0  5039.9     .03       0  5043.9     .05       0
  5058.9     .12       0  5193.3     .05       0  5194.1     .12       0
  5331.5     .05       0
Bank Sta=5039.9,5043.9
XS Rating Curve= 0 ,0
Exp/Cntr=0.3,0.1

Type RM Length L Ch R = 1 ,87170   ,1030,1030,1030
BEGIN DESCRIPTION:
Bachelor Creek 139.0
END DESCRIPTION:
XS GIS Cut Line= 3
      2649876.02      6988861.01        2649276.        6988511.
      2648266.75      6988566.07
#Sta/Elev= 30
  4305.2  565.89  4308.1  565.89  4313.1  559.51  4318.9  560.91  4328.4  555.18
  4334.6   554.4  4350.3  556.34  4356.1   555.1  4393.3  554.11  4810.6  551.56
    4906  550.66  4933.3  547.55  4970.5   549.5  4986.2  545.43    4995  544.95
  4995.2  544.45    4999  544.95  5039.9  550.37  5059.9  550.67  5093.3  545.29
  5160.1  546.47  5190.1  552.28  5230.9  550.52  5240.2  549.43  5330.3  552.22
  5550.7  552.42  5650.8  554.41    5751  553.86  5891.2  557.14  6010.6  556.91
#Mann= 5 ,-1 , 0
  4305.2     .05       0  4810.6     .12       0    4995     .07       0
    4999     .12       0  5230.9     .05       0
Bank Sta=4995,4999
XS Rating Curve= 0 ,0
Exp/Cntr=0.3,0.1

Type RM Length L Ch R = 1 ,86140   ,75,75,75
BEGIN DESCRIPTION:
Bachelor Creek 137.0
END DESCRIPTION:
XS GIS Cut Line= 3
      2649773.03      6987076.35      2649152.76      6987637.59
      2648115.03      6988565.08
#Sta/Elev= 30
  4163.5   552.5  4596.5  550.04    4618  548.53  4667.5  550.59  4681.7   549.4
  4695.9   550.7  4710.1  550.03  4716.8   551.2  4738.4  549.18  4778.8  549.09
  4845.6  547.78  4893.9  550.05  4920.8  547.38  4950.7  544.52  4982.2  546.02
  4998.8  545.45  5007.5  543.37  5054.8  542.59  5055.1  542.09  5058.8  542.59
  5063.3  542.61    5118  544.29  5206.3  547.02  5253.8   548.7  5340.2  548.19
  5403.7  549.58  5495.7  547.51  5559.2  550.41  5758.2  550.22  6391.8  557.05
#Mann= 11 ,-1 , 0
  4163.5     .05       0  4778.8     .12       0  4845.6     .05       0
  4920.8     .12       0  4982.2     .05       0  5054.8     .03       0
  5058.8     .05       0  5063.3     .12       0    5118     .05       0
  5206.3     .12       0  5253.8     .05       0
Bank Sta=5054.8,5058.8
XS Rating Curve= 0 ,0
Exp/Cntr=0.3,0.1

Type RM Length L Ch R = 1 ,86065   ,673,673,673
BEGIN DESCRIPTION:
Bachelor Creek 136.0
END DESCRIPTION:
XS GIS Cut Line= 3
      2649707.96      6987002.53      2649099.33      6987584.07
      2648041.27      6988482.59
#Sta/Elev= 30
  4158.2  551.67  4203.2  552.41  4243.5  550.53  4305.9  551.04  4343.4  551.02
  4444.1  550.41  4483.6  550.24  4582.3  549.95  4623.8   549.5  4720.4  549.43
    4764  548.44  4858.6  547.25  4904.2  547.81  4957.8  547.37    5027  542.71
  5027.2  542.21    5031  542.71    5042     543  5070.6  543.49  5099.2  547.16
  5174.7  547.41  5290.6  548.24  5397.9  550.46  5433.1  546.75  5584.6  548.48
  5705.3  550.28  5741.4     551  5958.2  551.64  6036.1  554.57  6388.1  555.43
#Mann= 20 ,-1 , 0
  4158.2     .12       0  4203.2     .12       0  4305.9     .05       0
  4343.4     .12       0  4444.1     .05       0  4483.6     .12       0
  4582.3     .05       0  4623.8     .12       0  4720.4     .05       0
    4764     .12       0  4858.6     .05       0  4904.2     .12       0
    5027     .03       0    5031     .05       0    5042     .12       0
  5174.7     .12       0  5290.6     .05       0  5584.6     .05       0
  5705.3     .12       0  5741.4     .05       0
Bank Sta=5027,5031
XS Rating Curve= 0 ,0
Exp/Cntr=0.3,0.1

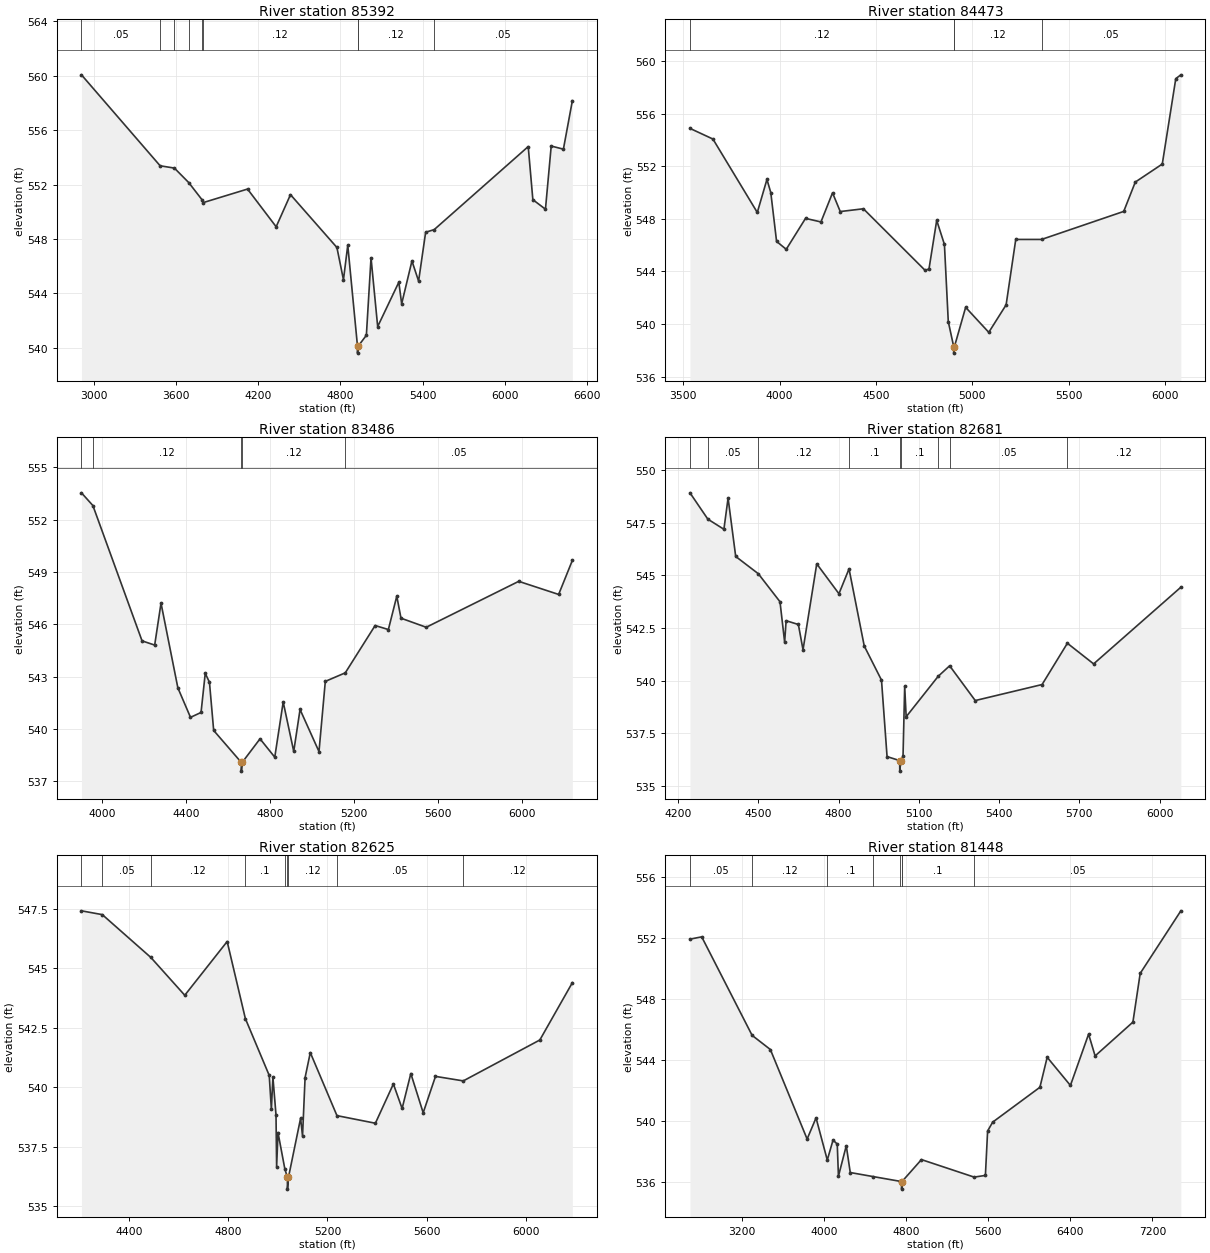
Type RM Length L Ch R = 1 ,85392   ,919,919,919
BEGIN DESCRIPTION:
Bachelor Creek 135.0
END DESCRIPTION:
XS GIS Cut Line= 3
      2650625.97      6986661.01        2648626.        6987261.
      2647175.97      6987611.01
#Sta/Elev= 30
    2912  560.06  3485.6  553.38  3589.7  553.21  3693.9  552.15    3790   550.9
    3798  550.67    4123  551.67  4331.8   548.9  4436.2  551.26  4774.7  547.38
  4822.5  545.01  4853.9  547.55  4924.9  540.12  4925.2  539.62  4928.9  540.12
  4989.6  540.93  5023.5  546.62    5072  541.57  5226.3  544.83  5246.9  543.24
  5321.9  546.39  5370.4  544.91  5421.8   548.5    5484  548.69  6169.8  554.79
  6203.6  550.89  6295.5  550.19  6337.4  554.83  6426.3   554.6  6491.7  558.16
#Mann= 9 ,-1 , 0
    2912     .05       0  3485.6     .12       0  3589.7     .05       0
  3693.9     .12       0    3790     .05       0    3798     .12       0
  4924.9     .07       0  4928.9     .12       0    5484     .05       0
Bank Sta=4924.9,4928.9
XS Rating Curve= 0 ,0
Exp/Cntr=0.3,0.1

Type RM Length L Ch R = 1 ,84473   ,987,987,987
BEGIN DESCRIPTION:
Bachelor Creek 133.0
END DESCRIPTION:
XS GIS Cut Line= 3
      2649784.98      6986602.99        2648326.        6986661.
      2647239.58      6986670.68
#Sta/Elev= 30
  3534.8  554.87  3653.9  554.06  3884.1  548.48  3934.1  550.99  3954.1  549.99
  3984.1  546.28  4034.2  545.68  4134.3  548.03  4214.3  547.76  4274.4  549.97
  4314.4  548.55  4434.5  548.76  4754.7  544.08  4774.8  544.19  4814.8  547.88
  4854.8  546.05  4874.8  540.19  4902.8  538.29  4903.1  537.79  4906.9  538.29
  4964.9  541.27  5084.9  539.37  5174.9  541.46  5224.9  546.43  5358.7  546.43
    5785  548.56    5845  550.79    5985  552.16    6055  558.65  6081.4  558.94
#Mann= 4 ,-1 , 0
  3534.8     .12       0  4902.8     .07       0  4906.9     .12       0
  5358.7     .05       0
Bank Sta=4902.8,4906.9
XS Rating Curve= 0 ,0
Exp/Cntr=0.3,0.1

Type RM Length L Ch R = 1 ,83486   ,805,805,805
BEGIN DESCRIPTION:
Bachelor Creek 132.0
END DESCRIPTION:
XS GIS Cut Line= 3
      2649473.61      6985855.02      2648373.64      6985755.02
      2647140.78      6985676.01
#Sta/Elev= 30
  3900.2  553.53  3954.7   552.8    4189  545.05  4249.2  544.81  4279.4  547.21
  4359.7  542.36  4419.9  540.67  4470.2  540.95  4490.2  543.19  4510.3  542.68
  4530.4  539.92  4662.1  538.09  4662.5  537.59  4666.4  538.09  4751.3  539.44
  4821.6  538.39  4861.8  541.55    4912  538.72  4942.1  541.12  5032.4  538.71
  5062.5  542.73  5157.7  543.22    5300  545.93  5363.1   545.7  5403.2  547.61
  5423.2  546.35  5543.5  545.83  5984.4  548.46  6174.7  547.71  6240.1  549.66
#Mann= 5 ,-1 , 0
  3900.2     .05       0  3954.7     .12       0  4662.1     .07       0
  4666.4     .12       0  5157.7     .05       0
Bank Sta=4662.1,4666.4
XS Rating Curve= 0 ,0
Exp/Cntr=0.3,0.1

Type RM Length L Ch R = 1 ,82681   ,56,56,56
BEGIN DESCRIPTION:
Mapping XS 36a9a1a6
END DESCRIPTION:
XS GIS Cut Line= 6
      2649501.12      6985355.59      2648914.33      6985083.02
       2648686.9      6985197.61      2648495.92       6985216.7
      2648289.33      6985084.76      2647945.59      6985431.97
#Sta/Elev= 30
  4244.4  548.92  4311.3  547.67  4371.3  547.19  4386.9  548.67  4415.4   545.9
  4499.9  545.08    4581  543.75  4598.4  541.83  4603.9  542.85  4649.7  542.67
  4667.1  541.47  4718.4  545.55  4801.4  544.13  4839.1  545.31    4896  541.65
  4960.5  540.03  4981.3   536.4  5028.4  536.21  5028.9  535.71  5032.9  536.21
    5041  536.42  5047.2  539.74  5052.7  538.29  5172.4  540.21  5215.3  540.71
    5311  539.06  5560.9  539.82  5655.5  541.78  5753.6   540.8  6079.8  544.44
#Mann= 9 ,-1 , 0
  4244.4     .12       0  4311.3     .05       0  4499.9     .12       0
  4839.1      .1       0  5028.4     .07       0  5032.9      .1       0
  5172.4     .12       0  5215.3     .05       0  5655.5     .12       0
Bank Sta=5028.4,5032.9
XS Rating Curve= 0 ,0
Exp/Cntr=0.3,0.1

Type RM Length L Ch R = 1 ,82625   ,1177,1177,1177
BEGIN DESCRIPTION:
Mapping XS 85082b11
END DESCRIPTION:
XS GIS Cut Line= 6
      2649534.11      6985324.34      2648907.38      6985030.94
      2648740.72      6985128.16      2648525.44      6985171.56
      2648284.12       6984985.8      2647933.44      6985423.27
#Sta/Elev= 30
  4208.8  547.41  4292.8  547.25  4488.4  545.45  4625.1  543.86    4796  546.12
  4869.3  542.88  4965.5  540.49  4974.1  539.07  4980.3  540.42  4992.8  538.83
  4995.3  536.65  5000.8  538.09  5028.4  536.56  5038.6  536.21    5039  535.71
  5043.1  536.21  5091.9  538.69  5099.7  537.94    5110   540.4    5131  541.45
  5238.4   538.8  5393.3  538.48  5465.8  540.13    5501   539.1  5536.1  540.57
  5585.9  538.92  5635.5  540.45  5747.5  540.26    6056  541.98  6187.1  544.39
#Mann= 9 ,-1 , 0
  4208.8     .12       0  4292.8     .05       0  4488.4     .12       0
  4869.3      .1       0  5028.4     .12       0  5038.6     .07       0
  5043.1     .12       0  5238.4     .05       0  5747.5     .12       0
Bank Sta=5038.6,5043.1
XS Rating Curve= 0 ,0
Exp/Cntr=0.3,0.1

Type RM Length L Ch R = 1 ,81448   ,674,674,674
BEGIN DESCRIPTION:
Bachelor Creek 129.0
END DESCRIPTION:
XS GIS Cut Line= 4
      2650426.01        6982861.      2649005.93      6983465.87
      2648496.12      6984030.95      2646825.98      6985861.02
#Sta/Elev= 30
  2695.4  551.95  2809.9   552.1  3300.9  545.63  3478.6   544.7  3836.7  538.82
  3923.6  540.21  4033.1  537.44  4089.1  538.75  4130.2  538.49  4141.8  536.38
  4218.1  538.38  4256.9  536.62  4483.2  536.35  4736.9  536.05  4756.8  536.03
  4757.3  535.53  4761.4  536.03  4950.4  537.47  5463.4  536.32  5573.4  536.43
    5595  539.35  5644.3  539.93  6104.4  542.22  6175.3  544.19  6401.7  542.34
  6578.7  545.71  6642.2  544.28  7010.4   546.5  7081.3   549.7  7477.6  553.81
#Mann= 8 ,-1 , 0
  2695.4     .05       0  3300.9     .12       0  4033.1      .1       0
  4483.2     .05       0  4736.9      .1       0  4756.8     .07       0
  4761.4      .1       0  5463.4     .05       0
Bank Sta=4756.8,4761.4
XS Rating Curve= 0 ,0
Exp/Cntr=0.3,0.1

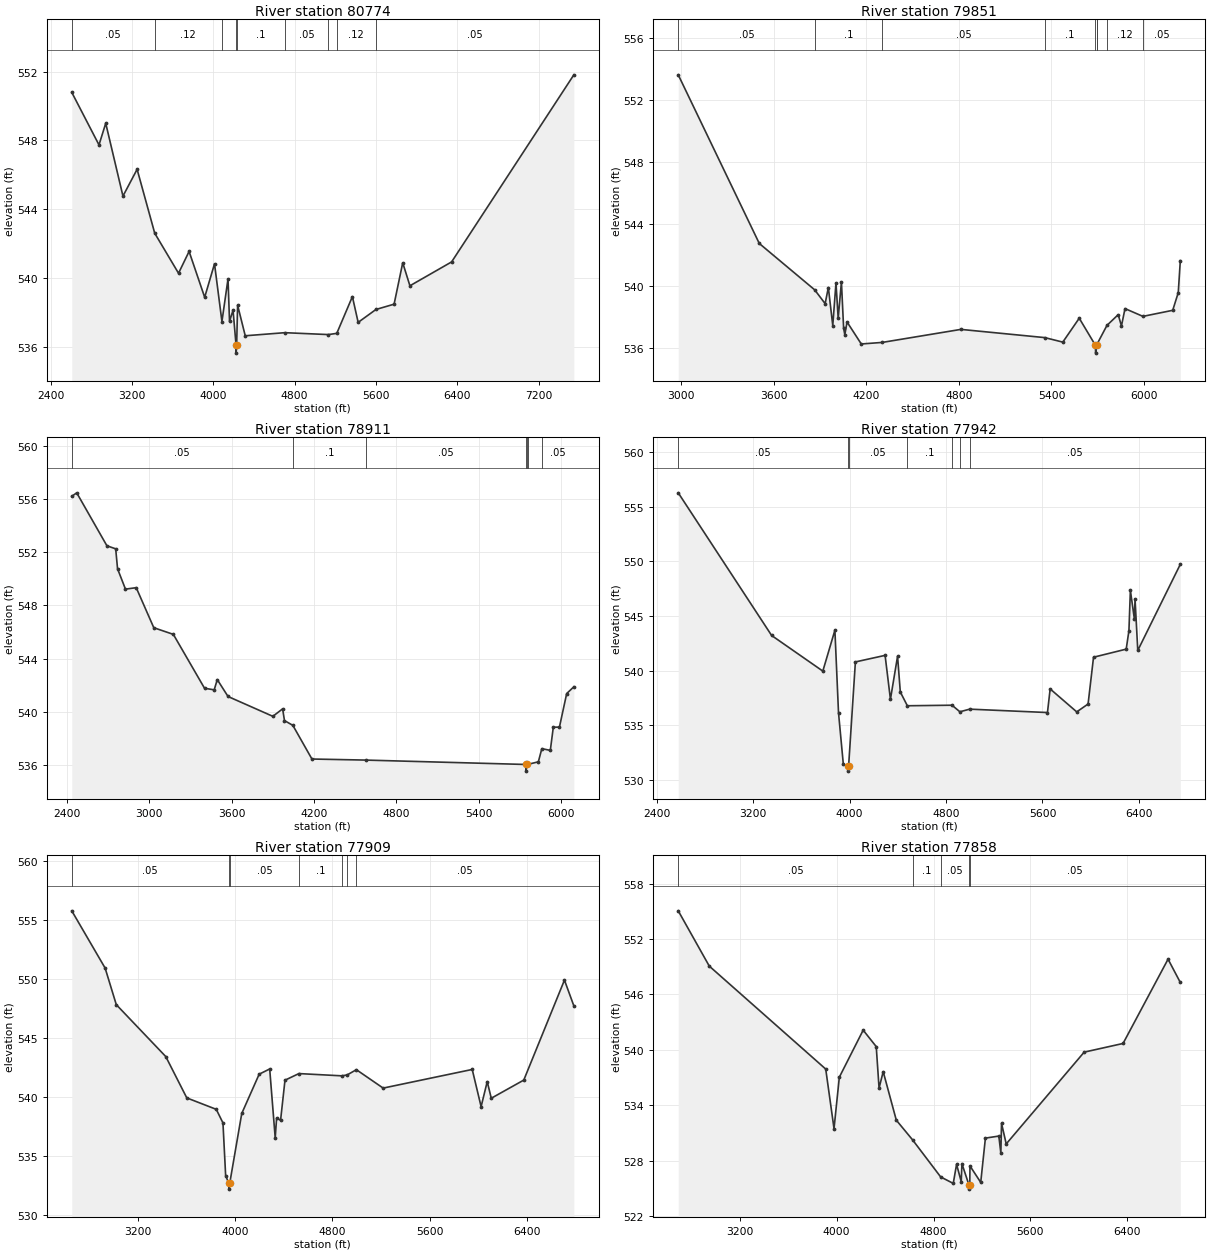
Type RM Length L Ch R = 1 ,80774   ,923,923,923
BEGIN DESCRIPTION:
Bachelor Creek 128.0
END DESCRIPTION:
XS GIS Cut Line= 3
      2650431.66      6982275.74        2648326.        6983411.
      2646525.99      6985211.01
#Sta/Elev= 30
  2607.8   550.8  2875.5  547.74  2941.8     549  3111.2  544.76  3250.4  546.32
  3423.7   542.6  3657.8  540.27  3761.6  541.54  3914.9  538.87  4011.6  540.82
  4084.6  537.46  4144.4  539.94  4159.3  537.47  4193.9  538.12  4223.1  536.12
  4224.2  535.62  4229.5  536.12  4238.8  538.41  4313.9  536.63  4702.8  536.81
  5130.7   536.7  5214.1  536.77  5367.7  538.91  5424.3  537.41  5599.1  538.16
  5777.8  538.47  5862.7  540.88  5933.4  539.54  6343.5  540.93  7545.6  551.82
#Mann= 9 ,-1 , 0
  2607.8     .05       0  3423.7     .12       0  4084.6      .1       0
  4223.1     .03       0  4229.5      .1       0  4702.8     .05       0
  5130.7      .1       0  5214.1     .12       0  5599.1     .05       0
Bank Sta=4223.1,4229.5
XS Rating Curve= 0 ,0
Exp/Cntr=0.3,0.1

Type RM Length L Ch R = 1 ,79851   ,940,940,940
BEGIN DESCRIPTION:
Bachelor Creek 126.0
END DESCRIPTION:
XS GIS Cut Line= 3
      2649426.01      6981410.99        2647876.        6982711.
      2647183.58      6983727.09
#Sta/Elev= 30
    2982  553.61    3507  542.74  3865.9  539.75  3933.7  538.86  3954.5   539.9
  3983.1  537.45  4003.9   540.2  4018.2  537.92  4039.2  540.26  4053.4  537.28
  4061.2  536.85  4075.5  537.68  4167.8  536.26  4303.3  536.36  4813.1   537.2
  5356.9  536.67  5473.3  536.38  5579.8  537.92  5684.8  536.17    5686  535.67
  5692.6  536.17  5693.7  536.22  5759.5  537.46  5832.3  538.15  5853.3  537.42
  5876.3  538.54  5992.5  538.04  6185.4  538.43  6221.3  539.57  6234.6  541.63
#Mann= 9 ,-1 , 0
    2982     .05       0  3865.9      .1       0  4303.3     .05       0
  5356.9      .1       0  5684.8     .03       0  5692.6      .1       0
  5693.7     .05       0  5759.5     .12       0  5992.5     .05       0
Bank Sta=5684.8,5692.6
XS Rating Curve= 0 ,0
Exp/Cntr=0.3,0.1

Type RM Length L Ch R = 1 ,78911   ,969,969,969
BEGIN DESCRIPTION:
Bachelor Creek 124.0
END DESCRIPTION:
XS GIS Cut Line= 3
      2649275.96      6980411.03        2647276.        6982011.
      2646313.97      6982540.44
#Sta/Elev= 30
  2434.2   556.2  2470.2  556.46  2690.3  552.48  2754.3  552.25  2767.9  550.75
  2825.5  549.22    2904  549.33    3032  546.32  3174.5  545.82  3401.8  541.77
  3472.3  541.65  3494.7  542.42  3573.1  541.15  3899.7  539.66  3970.9  540.22
  3984.5  539.34  4045.5  538.98  4184.6  536.45  4576.3  536.37  5743.8  536.04
    5745  535.54  5751.6  536.04  5762.7  536.06  5834.9  536.24  5860.1  537.23
    5922   537.1  5943.8  538.84  5988.5  538.85  6041.3  541.37  6093.5  541.88
#Mann= 7 ,-1 , 0
  2434.2     .05       0  4045.5      .1       0  4576.3     .05       0
  5743.8     .03       0  5751.6     .05       0  5762.7      .1       0
  5860.1     .05       0
Bank Sta=5743.8,5751.6
XS Rating Curve= 0 ,0
Exp/Cntr=0.3,0.1

Type RM Length L Ch R = 1 ,77942   ,33,33,33
BEGIN DESCRIPTION:
Bachelor Creek 123.0
END DESCRIPTION:
XS GIS Cut Line= 6
      2649211.88      6980350.78       2648263.5      6980756.61
      2647748.11      6980770.26      2646958.98      6981144.48
      2646093.87      6981595.33      2645403.29      6981929.61
#Sta/Elev= 30
  2579.5  556.27    3354  543.22  3778.6  539.96  3878.7   543.7  3908.7  536.15
  3948.7  531.43  3984.6  531.31  3985.8  530.81  3992.7  531.31  4048.7   540.8
    4295   541.4  4339.3  537.38  4398.4  541.32  4421.2  538.05  4479.6  536.79
  4850.2  536.84  4915.1  536.24  4996.9  536.48  5641.6  536.17  5663.9  538.33
  5884.3  536.23  5978.4  536.95  6023.6  541.23  6294.6  541.97  6317.2  543.66
  6329.2  547.34  6362.4  544.73  6367.9  546.55  6390.5  541.85  6743.3  549.73
#Mann= 7 ,-1 , 0
  2579.5     .05       0  3984.6     .03       0  3992.7     .05       0
  4479.6      .1       0  4850.2     .05       0  4915.1      .1       0
  4996.9     .05       0
Bank Sta=3984.6,3992.7
XS Rating Curve= 0 ,0
Exp/Cntr=0.3,0.1

Type RM Length L Ch R = 1 ,77909   ,51,51,51
BEGIN DESCRIPTION:
Mapping XS 2cd28059
END DESCRIPTION:
XS GIS Cut Line= 6
      2649054.55      6980123.43       2647468.3      6980854.45
      2647409.62      6980890.21      2647267.95      6980956.01
       2646744.6      6981213.74      2645340.96      6981920.33
#Sta/Elev= 30
  2658.8  555.76  2932.9  550.91  3024.7  547.81  3431.5  543.41  3604.1  539.91
  3846.4  538.94  3901.4  537.79  3923.5  533.33    3949  532.68  3950.2  532.18
  3957.1  532.68  4055.9  538.59  4199.1  541.92  4285.5  542.36  4330.9  536.52
  4342.4  538.21  4374.9  538.01  4411.2  541.41  4525.5  541.97  4876.8  541.78
  4921.4  541.85  4997.9   542.3  5218.1  540.74  5950.1  542.32  6023.1  539.17
  6073.4  541.29  6106.6  539.88  6373.9  541.42  6708.1  549.89  6785.3  547.71
#Mann= 7 ,-1 , 0
  2658.8     .05       0    3949     .03       0  3957.1     .05       0
  4525.5      .1       0  4876.8     .05       0  4921.4      .1       0
  4997.9     .05       0
Bank Sta=3949,3957.1
XS Rating Curve= 0 ,0
Exp/Cntr=0.3,0.1

Type RM Length L Ch R = 1 ,77858   ,365,365,365
BEGIN DESCRIPTION:
Bachelor Creek 122.0
END DESCRIPTION:
XS GIS Cut Line= 4
      2649021.34      6980110.17      2647203.89      6980918.25
      2646924.33      6981071.69      2645289.83      6981911.67
#Sta/Elev= 30
  2692.1  555.05  2948.4  549.07  3909.9  537.93  3978.4  531.49  4022.2  537.05
  4219.1  542.14    4327  540.36  4350.3  535.87  4384.5  537.65  4492.7   532.4
  4626.4  530.28    4859  526.26  4962.8  525.56  4990.3  527.62  5028.8  525.75
  5034.4   527.7  5091.3  525.44  5092.5  524.94  5099.4  525.44  5100.9  527.45
  5189.7  525.67  5228.4  530.46  5339.3  530.68  5355.9  528.83  5361.5  532.06
  5400.2  529.83  6043.7  539.76    6365   540.7  6736.5  549.82  6837.7   547.3
#Mann= 5 ,-1 , 0
  2692.1     .05       0  4626.4      .1       0    4859     .05       0
  5091.3     .03       0  5099.4     .05       0
Bank Sta=5091.3,5099.4
XS Rating Curve= 0 ,0
Exp/Cntr=0.3,0.1

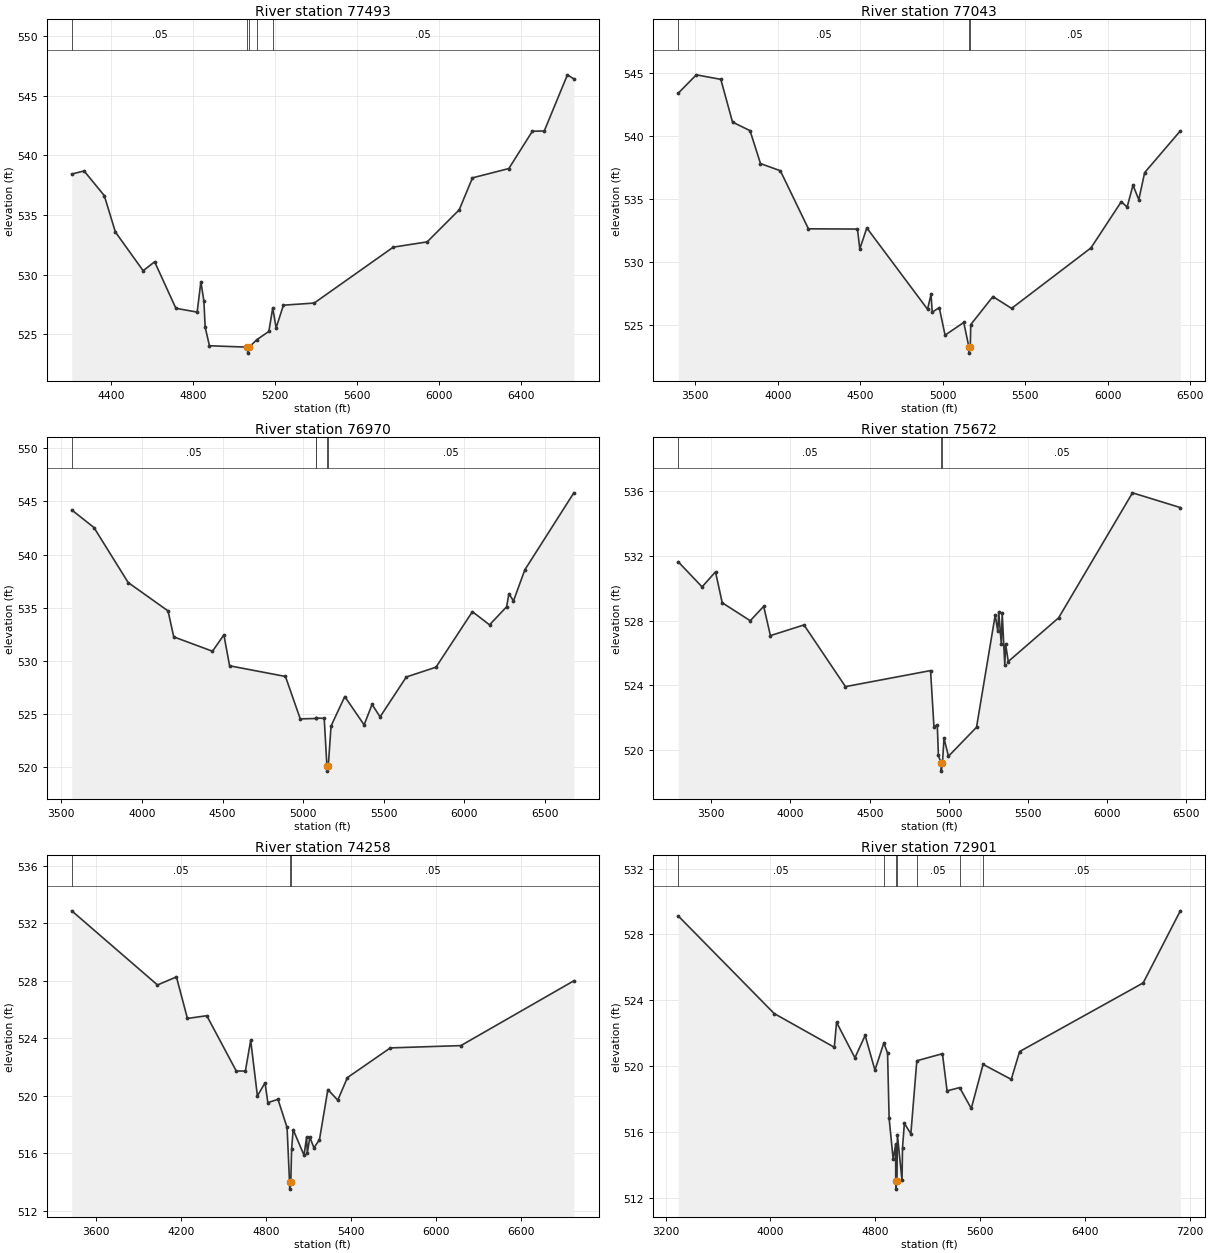
Type RM Length L Ch R = 1 ,77493   ,450,450,450
BEGIN DESCRIPTION:
Mapping XS c2936524
END DESCRIPTION:
XS GIS Cut Line= 3
      2647529.98      6980528.93      2646762.63      6980761.56
      2645429.33      6981737.24
#Sta/Elev= 30
    4206  538.44  4266.2   538.7    4365  536.63  4419.1  533.58    4555  530.33
    4611  531.08  4714.9  527.18  4818.9  526.86  4837.1  529.41  4851.8  527.79
    4858   525.6  4878.9  524.04  5064.9  523.92  5066.1  523.42  5073.1  523.92
  5109.1  524.53  5169.3  525.24  5188.2   527.2  5204.9  525.54  5240.4  527.44
  5390.9  527.62  5777.7  532.31    5943  532.75  6099.7  535.44  6164.5  538.12
  6342.2   538.9  6457.2  542.03  6515.4  542.05  6628.6  546.76    6660  546.42
#Mann= 5 ,-1 , 0
    4206     .05       0  5064.9     .03       0  5073.1     .05       0
  5109.1     .12       0  5188.2     .05       0
Bank Sta=5064.9,5073.1
XS Rating Curve= 0 ,0
Exp/Cntr=0.3,0.1

Type RM Length L Ch R = 1 ,77043   ,73,73,73
BEGIN DESCRIPTION:
Bachelor Creek 121.0
END DESCRIPTION:
XS GIS Cut Line= 3
      2647660.19      6979370.61      2646482.12      6980458.29
      2645470.15      6981480.78
#Sta/Elev= 30
  3396.6  543.41  3506.1  544.87  3654.6  544.51  3725.5  541.11  3831.5  540.43
    3895  537.81  4015.3  537.24  4185.4  532.62  4482.5   532.6  4496.7  531.02
  4539.2  532.69  4907.2  526.22  4928.2   527.4  4935.6  525.99  4978.1  526.35
  5013.3  524.16  5126.5  525.17  5157.5  523.23  5158.7  522.73  5166.1  523.23
  5168.9     525  5303.2  527.23  5416.4  526.29  5897.2   531.1  6081.1  534.78
  6116.4  534.35  6151.8  536.09  6187.1  534.94  6222.5  537.09  6438.6  540.41
#Mann= 3 ,-1 , 0
  3396.6     .05       0  5157.5     .03       0  5166.1     .05       0
Bank Sta=5157.5,5166.1
XS Rating Curve= 0 ,0
Exp/Cntr=0.3,0.1

Type RM Length L Ch R = 1 ,76970   ,1298,1298,1298
BEGIN DESCRIPTION:
Bachelor Creek 120.0
END DESCRIPTION:
XS GIS Cut Line= 3
      2647434.52      6979394.89      2646424.45      6980414.75
      2645209.88      6981574.44
#Sta/Elev= 30
  3564.6   544.2  3702.2  542.55  3914.3  537.38  4161.9  534.71  4197.2  532.27
  4437.6  530.92  4508.3  532.46  4543.7  529.55  4890.2  528.55  4982.1  524.56
  5079.5   524.6  5081.7  524.64  5130.7  524.61  5147.4  520.15  5148.7  519.65
    5156  520.15  5173.1  523.89  5258.1  526.66  5378.2     524  5427.6  525.92
  5477.3  524.75  5639.9   528.5  5823.9  529.42    6050  534.64  6156.3   533.4
  6262.3   535.1  6276.4  536.33  6304.8  535.65  6375.5  538.58  6679.3  545.81
#Mann= 5 ,-1 , 0
  3564.6     .05       0  5079.5     .12       0  5081.7     .05       0
  5147.4     .04       0    5156     .05       0
Bank Sta=5147.4,5156
XS Rating Curve= 0 ,0
Exp/Cntr=0.3,0.1

Type RM Length L Ch R = 1 ,75672   ,1414,1414,1414
BEGIN DESCRIPTION:
Bachelor Creek 119.0
END DESCRIPTION:
XS GIS Cut Line= 3
      2646570.61      6978982.76        2645376.        6980211.
      2644691.32      6981496.68
#Sta/Elev= 30
  3291.2  531.64  3441.8  530.09  3526.5  531.02  3568.9  529.11  3745.9     528
  3830.7  528.89  3873.2  527.08  4085.2  527.74    4347  523.93  4884.3  524.92
  4905.7  521.46  4926.8  521.56  4933.9  519.68  4950.7  519.21    4952  518.71
  4959.4  519.21  4969.2  520.74  4997.5  519.63  5174.5  521.42  5292.6  528.35
  5308.9  527.34  5314.6  528.54  5330.9  526.58  5336.6  528.46  5352.9  525.29
  5358.5  526.54  5374.8  525.48    5693  528.18  6159.3   535.9  6461.2  534.99
#Mann= 3 ,-1 , 0
  3291.2     .05       0  4950.7     .03       0  4959.4     .05       0
Bank Sta=4950.7,4959.4
XS Rating Curve= 0 ,0
Exp/Cntr=0.3,0.1

Type RM Length L Ch R = 1 ,74258   ,1357,1357,1357
BEGIN DESCRIPTION:
Bachelor Creek 116.0
END DESCRIPTION:
XS GIS Cut Line= 3
      2646622.74      6978529.62        2645126.        6979011.
      2643326.01      6979810.99
#Sta/Elev= 30
  3431.9  532.88  4036.6  527.72  4170.2  528.28  4247.8  525.39  4384.4  525.58
  4592.5  521.73  4656.7  521.73  4694.1  523.87  4741.5     520  4795.6  520.91
  4815.1  519.53  4886.6  519.76  4950.8   517.8  4968.1  514.01  4969.4  513.51
  4977.2  514.01  4982.8  516.29  4993.6  517.65  5070.5  515.87  5088.3  517.13
  5093.7  516.04  5111.5  517.12  5140.2  516.39  5179.2  516.95  5238.7  520.44
  5308.5   519.7  5376.2  521.27  5679.2  523.34  6177.1   523.5  6973.9  528.01
#Mann= 3 ,-1 , 0
  3431.9     .05       0  4968.1     .03       0  4977.2     .05       0
Bank Sta=4968.1,4977.2
XS Rating Curve= 0 ,0
Exp/Cntr=0.3,0.1

Type RM Length L Ch R = 1 ,72901   ,2282,2282,2282
BEGIN DESCRIPTION:
Bachelor Creek 114.0
END DESCRIPTION:
XS GIS Cut Line= 3
      2646419.56       6977508.8        2644826.        6978111.
      2643225.98      6979511.01
#Sta/Elev= 30
  3296.5  529.12  4028.3  523.19  4486.9  521.14    4504  522.66  4644.2   520.5
  4722.1  521.86  4796.9  519.75  4864.5   521.4  4893.1  520.79  4905.1  516.82
  4935.9  514.33  4954.8  515.24  4955.5  513.02  4956.8  512.52  4964.8  513.02
    4968  515.83  5003.4  513.05  5007.2  515.04  5021.4  516.52  5070.8  515.88
  5116.3  520.32  5311.8  520.75    5347  518.49  5443.2  518.69  5531.6  517.42
  5621.7   520.1  5836.7  519.19  5900.3  520.88  6842.8  525.05  7126.1  529.43
#Mann= 7 ,-1 , 0
  3296.5     .05       0  4864.5     .12       0  4955.5     .07       0
  4964.8     .12       0  5116.3     .05       0  5443.2     .12       0
  5621.7     .05       0
Bank Sta=4955.5,4964.8
XS Rating Curve= 0 ,0
Exp/Cntr=0.3,0.1

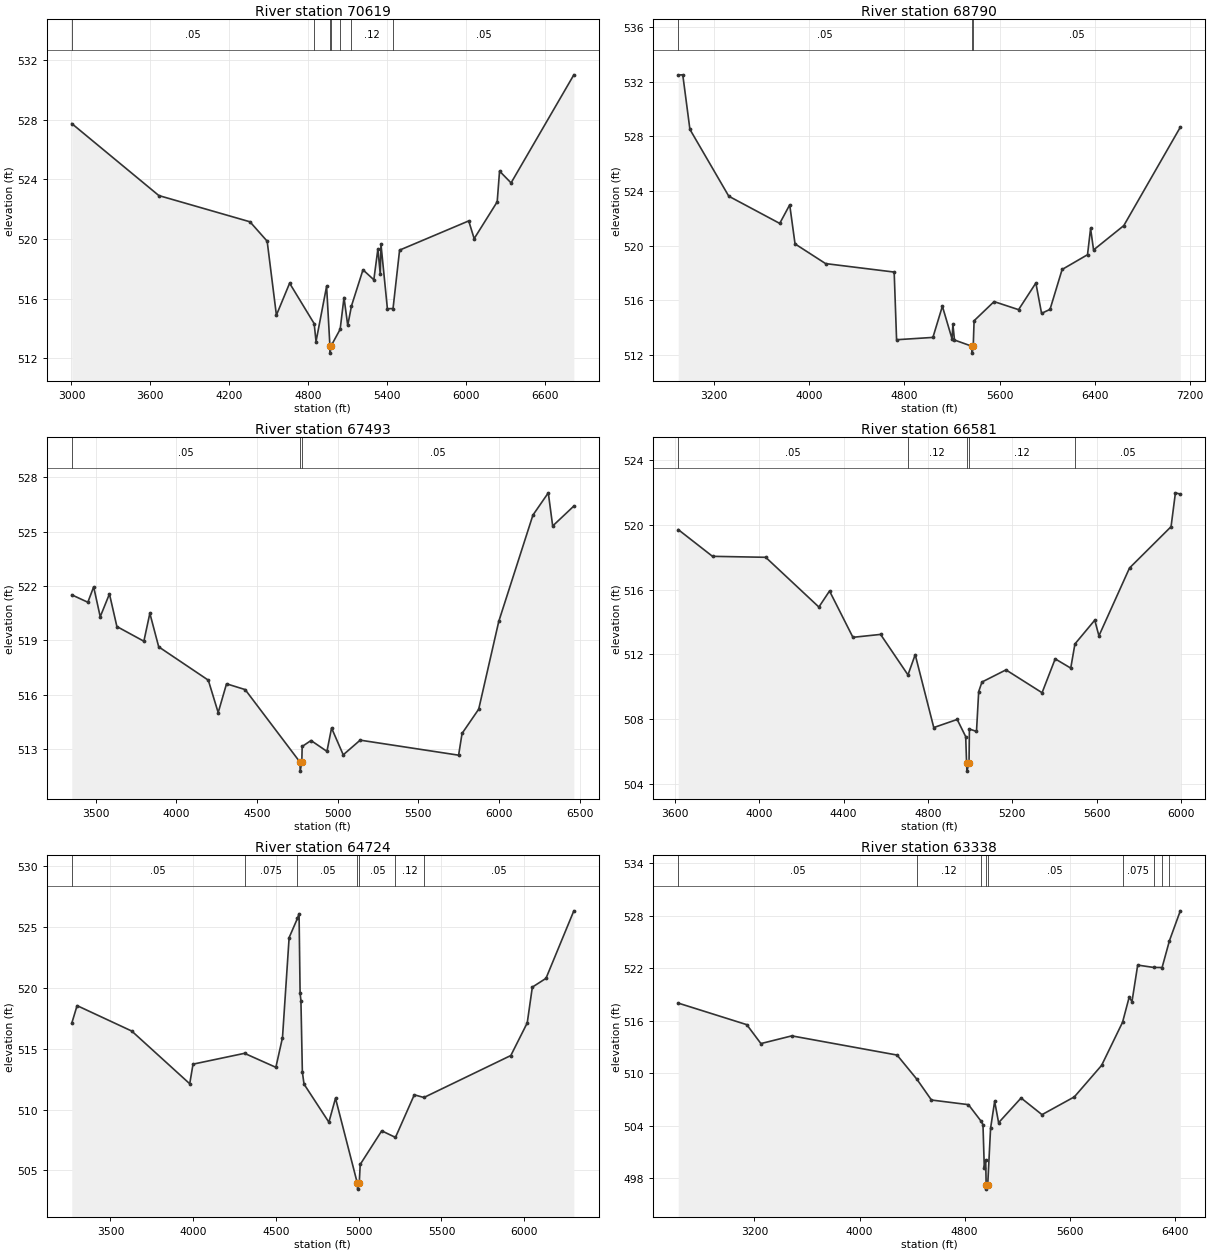
Type RM Length L Ch R = 1 ,70619   ,1829,1829,1829
BEGIN DESCRIPTION:
Bachelor Creek 111.0
END DESCRIPTION:
XS GIS Cut Line= 3
      2646565.41      6976977.54        2644576.        6977161.
       2642810.6      6977602.44
#Sta/Elev= 30
  3002.2  527.75  3664.4  522.92  4357.3  521.16  4487.9  519.86  4558.2   514.9
  4658.6  517.04  4845.3  514.33  4859.5  513.13  4939.8  516.83  4964.9  512.85
  4966.3  512.35  4974.9  512.85  5042.9  513.95  5072.2  516.08  5100.5  514.21
  5129.1  515.52  5216.5  517.94    5299  517.27  5329.9  519.34  5347.9  517.64
  5353.1  519.66  5402.1  515.33    5445  515.34  5494.8  519.26  6020.5  521.22
  6061.8  520.03    6237   522.5  6254.9  524.56  6342.5  523.77  6819.8  531.02
#Mann= 7 ,-1 , 0
  3002.2     .05       0  4845.3     .12       0  4964.9     .07       0
  4974.9     .12       0  5042.9     .05       0  5129.1     .12       0
    5445     .05       0
Bank Sta=4964.9,4974.9
XS Rating Curve= 0 ,0
Exp/Cntr=0.3,0.1

Type RM Length L Ch R = 1 ,68790   ,1297,1297,1297
BEGIN DESCRIPTION:
Bachelor Creek 108.0
END DESCRIPTION:
XS GIS Cut Line= 4
      2646476.02      6976561.01      2645383.12      6976092.13
        2644476.        6975961.      2642398.79      6976326.49
#Sta/Elev= 30
  2901.8  532.48  2939.9  532.49  2999.8   528.5  3326.2  523.61  3753.8  521.62
  3837.6  522.98  3882.4  520.12  4138.8  518.68  4714.6  518.06  4734.8  513.11
  5039.8  513.28  5119.3  515.56  5200.5  513.17  5207.6  514.24  5220.8  513.09
  5367.9  512.63  5369.4  512.13  5378.3  512.63  5385.5   514.5  5553.3   515.9
  5758.9  515.31  5904.1  517.26  5951.9  515.04  6022.9  515.33  6124.5  518.25
  6337.7  519.33  6363.4  521.25  6388.5  519.68  6642.3  521.46  7116.7  528.66
#Mann= 3 ,-1 , 0
  2901.8     .05       0  5367.9     .03       0  5378.3     .05       0
Bank Sta=5367.9,5378.3
XS Rating Curve= 0 ,0
Exp/Cntr=0.3,0.1

Type RM Length L Ch R = 1 ,67493   ,912,912,912
BEGIN DESCRIPTION:
Bachelor Creek 105.0
END DESCRIPTION:
XS GIS Cut Line= 3
      2645576.83      6974331.03        2644076.        6975011.
      2642820.44      6975764.73
#Sta/Elev= 30
  3352.7  521.51  3452.4   521.1  3488.4  521.95  3529.1   520.3  3586.2  521.56
  3632.4  519.76  3799.6  518.95  3836.7  520.49  3891.6  518.64    4199   516.8
  4260.3  515.01    4312   516.6  4427.5  516.28    4767  512.28  4768.6  511.78
  4778.6  512.28  4780.8  513.14  4835.7  513.47  4934.4  512.87    4963  514.16
  5035.4  512.68  5140.3  513.49  5750.5  512.66  5771.9  513.86  5875.1   515.2
  5999.3  520.04  6211.1  525.91  6306.4  527.14  6333.6  525.31  6464.8  526.41
#Mann= 3 ,-1 , 0
  3352.7     .05       0    4767     .03       0  4778.6     .05       0
Bank Sta=4767,4778.6
XS Rating Curve= 0 ,0
Exp/Cntr=0.3,0.1

Type RM Length L Ch R = 1 ,66581   ,1857,1857,1857
BEGIN DESCRIPTION:
Bachelor Creek 103.0
END DESCRIPTION:
XS GIS Cut Line= 3
      2645247.03      6974126.14        2643876.        6974311.
      2642913.65      6974574.07
#Sta/Elev= 30
  3616.1   519.7  3778.6  518.05  4030.9  517.99  4283.1  514.92  4333.6  515.91
  4444.6  513.05  4575.7  513.23  4705.6  510.73  4739.9  511.98    4828  507.48
    4939  507.98  4979.4  506.92  4983.6  505.29  4985.2  504.79  4995.2  505.29
    4997  507.39  5030.6  507.24    5041   509.7  5056.5  510.29  5170.4  511.04
  5341.6  509.63  5403.8  511.72  5477.6  511.15  5497.4  512.64  5591.5  514.11
  5611.2  513.14  5756.3  517.33  5953.3  519.88    5974  521.97  5997.2  521.89
#Mann= 5 ,-1 , 0
  3616.1     .05       0  4705.6     .12       0  4983.6     .07       0
  4995.2     .12       0  5497.4     .05       0
Bank Sta=4983.6,4995.2
XS Rating Curve= 0 ,0
Exp/Cntr=0.3,0.1

Type RM Length L Ch R = 1 ,64724   ,1386,1386,1386
BEGIN DESCRIPTION:
Bachelor Creek 101.0
END DESCRIPTION:
XS GIS Cut Line= 3
      2645108.07      6973237.26        2643376.        6973311.
      2642176.03      6973810.99
#Sta/Elev= 30
  3266.4  517.09  3298.5  518.54  3628.8  516.45  3979.1  512.12  3999.1  513.73
  4310.1  514.62  4499.6  513.47  4539.6  515.91  4579.7  524.13    4630  525.71
  4639.7   526.1    4646  519.57    4651  518.95  4659.7  513.08  4669.7  512.09
  4819.9  508.96  4859.9  510.93  4991.6  503.96  4993.3  503.46  5003.4  503.96
  5009.2  505.49  5139.2  508.25  5222.2  507.71  5335.9  511.21  5394.1  510.99
  5919.2  514.44  6018.4  517.12  6049.2  520.06  6131.6  520.78    6300  526.33
#Mann= 7 ,-1 , 0
  3266.4     .05       0  4310.1    .075       0    4630     .05       0
  4991.6     .03       0  5003.4     .05       0  5222.2     .12       0
  5394.1     .05       0
Bank Sta=4991.6,5003.4
XS Rating Curve= 0 ,0
Exp/Cntr=0.3,0.1

Type RM Length L Ch R = 1 ,63338   ,1287,1287,1287
BEGIN DESCRIPTION:
Bachelor Creek 98.0
END DESCRIPTION:
XS GIS Cut Line= 4
      2645482.09      6972784.84      2644206.04      6972222.34
        2643226.        6972111.      2642025.99      6972911.01
#Sta/Elev= 30
  2619.5  518.01  3141.2  515.55  3249.1  513.39  3484.2  514.27  4285.8  512.08
  4437.3  509.31  4547.5  506.95  4829.3  506.42  4924.8  504.55    4940  504.13
    4950  499.22  4960.6  500.08  4964.2  497.28  4965.9  496.78  4976.1  497.28
  4997.9  503.73  5028.9   506.8    5059  504.36  5230.2  507.18  5389.5  505.28
  5635.8  507.31  5843.2   510.9  6002.7  515.82  6053.5   518.7  6074.5  518.17
  6118.1  522.35    6239  522.08  6303.9  522.07    6360  525.14  6442.6  528.54
#Mann= 9 ,-1 , 0
  2619.5     .05       0  4437.3     .12       0  4924.8     .05       0
  4964.2     .03       0  4976.1     .05       0  6002.7    .075       0
    6239     .05       0  6303.9    .075       0    6360     .05       0
Bank Sta=4964.2,4976.1
XS Rating Curve= 0 ,0
Exp/Cntr=0.3,0.1