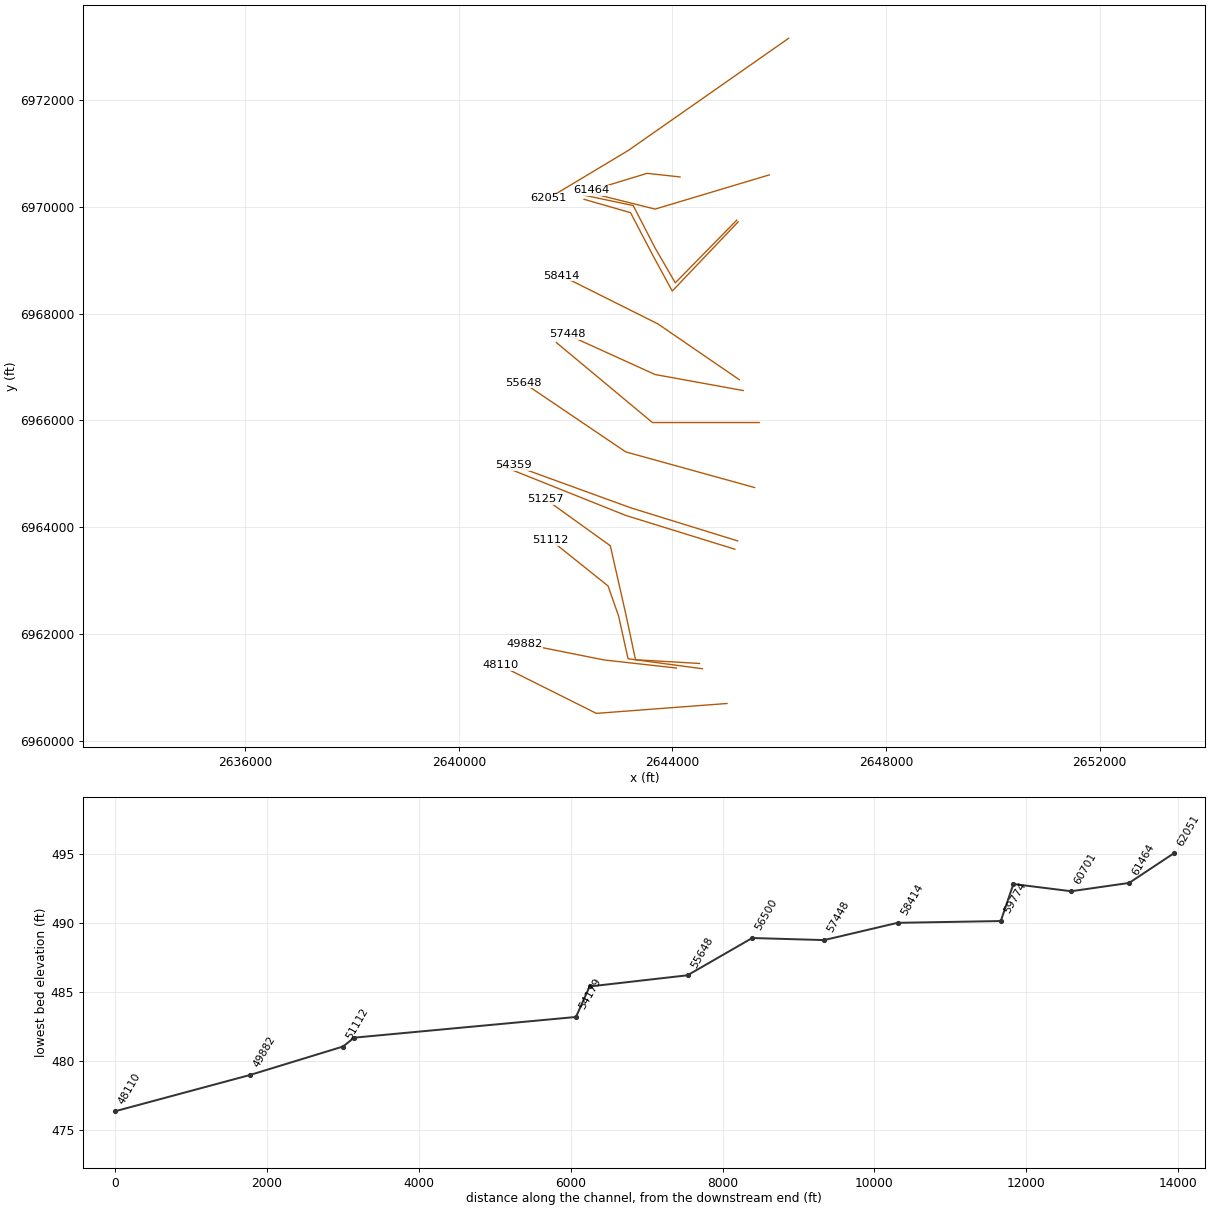
HEC-RAS study Bachelor Creek.prj: Bachelor Creek Base Level Engineering

--- Bachelor Creek.g01 (geometry) --- (continued)

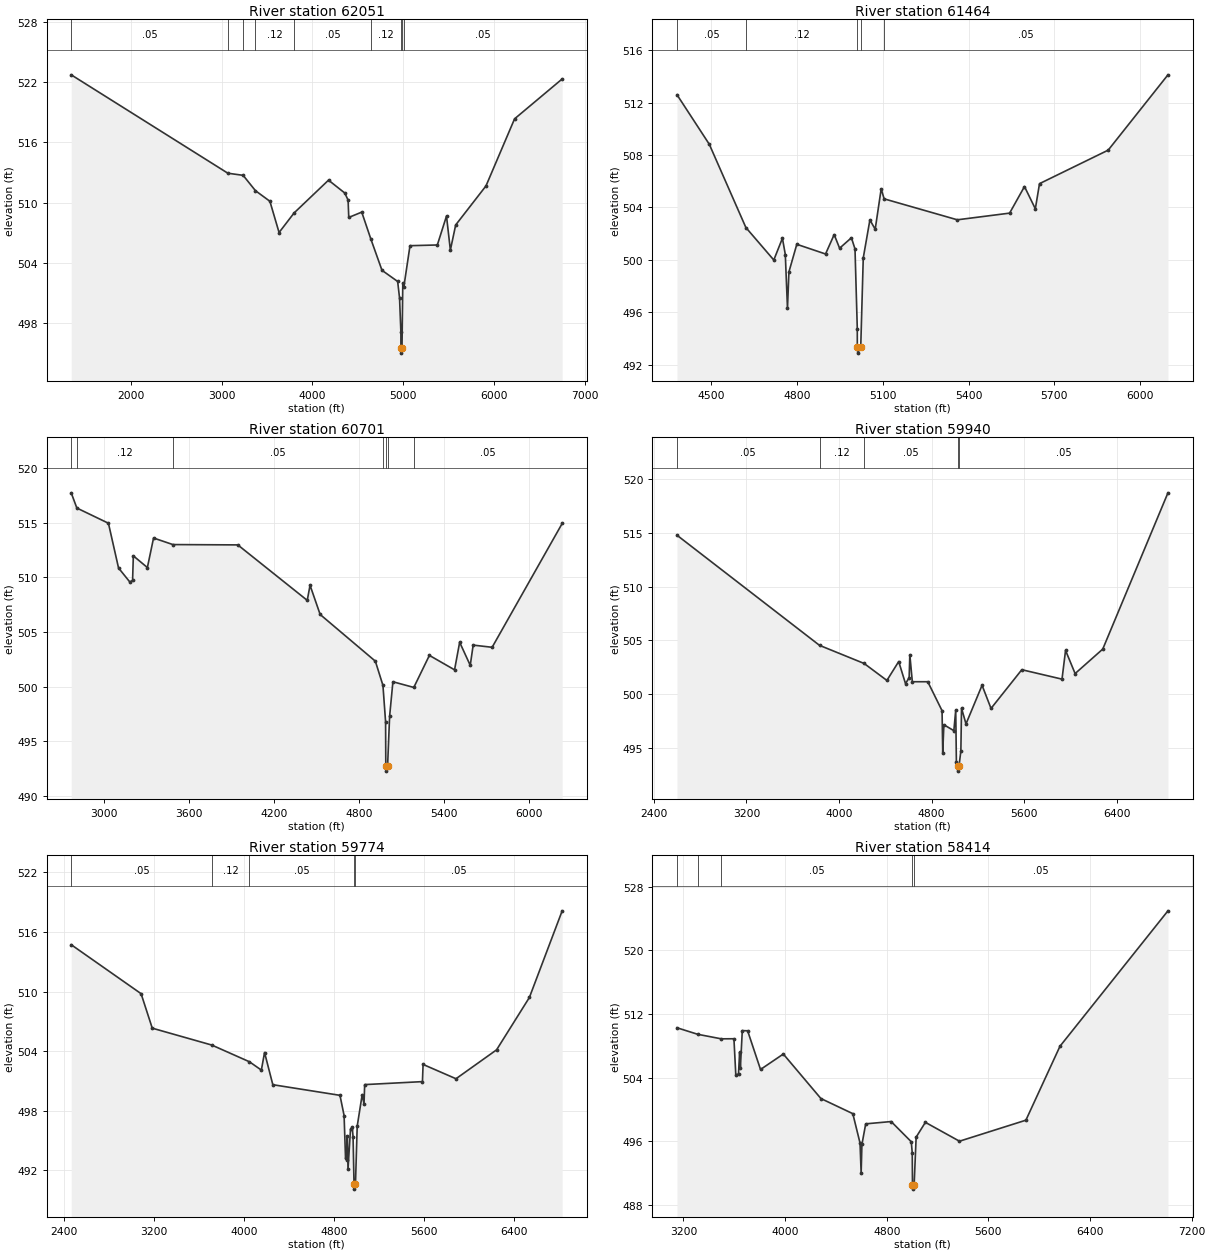
Type RM Length L Ch R = 1 ,62051   ,587,587,587
BEGIN DESCRIPTION:
Bachelor Creek 95.0
END DESCRIPTION:
XS GIS Cut Line= 3
      2646175.98      6973160.98        2643176.        6971061.
      2641676.02      6970161.01
#Sta/Elev= 30
  1342.8  522.71  3069.4  512.92  3237.5  512.71  3373.7  511.18  3532.5  510.13
  3633.7  507.02  3799.5  508.97  4178.6  512.23  4357.8  510.95  4394.4  510.25
  4401.8  508.52  4544.8  509.05  4646.1  506.35    4768  503.26  4940.7  502.15
  4961.6   500.5  4976.4   497.1  4976.5  495.52  4978.2  495.02  4988.5  495.52
  4997.3  501.99  5007.8  501.55  5076.7  505.71  5377.9  505.78    5479  508.66
  5521.7  505.27  5580.1  507.77  5914.4  511.66  6229.2  518.33    6754   522.3
#Mann= 9 ,-1 , 0
  1342.8     .05       0  3069.4     .12       0  3237.5     .05       0
  3373.7     .12       0  3799.5     .05       0  4646.1     .12       0
  4976.5     .07       0  4988.5     .12       0  5007.8     .05       0
Bank Sta=4976.5,4988.5
XS Rating Curve= 0 ,0
Exp/Cntr=0.3,0.1

Type RM Length L Ch R = 1 ,61464   ,763,763,763
BEGIN DESCRIPTION:
Bachelor Creek 93.0
END DESCRIPTION:
XS GIS Cut Line= 3
      2644142.83      6970563.65      2643526.21      6970631.14
      2642476.02      6970311.01
#Sta/Elev= 30
  4379.7  512.61  4492.7  508.83  4620.8  502.47  4718.5  499.99  4748.7  501.65
  4758.8  500.41  4766.4  496.29  4771.4  499.08    4799  501.19  4899.6  500.45
  4929.8  501.93  4948.8  500.89  4990.2  501.69  5002.7  500.83  5010.7  494.75
  5010.8  493.38  5012.4  492.88  5022.8  493.38  5031.6  500.15  5054.8  503.05
  5073.4  502.34  5094.3  505.42  5104.7  504.66  5360.7  503.06  5543.8  503.57
  5595.8   505.6  5633.8   503.9  5648.4  505.82  5888.8  508.38  6097.9  514.13
#Mann= 5 ,-1 , 0
  4379.7     .05       0  4620.8     .12       0  5010.8     .07       0
  5022.8     .12       0  5104.7     .05       0
Bank Sta=5010.8,5022.8
XS Rating Curve= 0 ,0
Exp/Cntr=0.3,0.1

Type RM Length L Ch R = 1 ,60701   ,761,761,761
BEGIN DESCRIPTION:
Bachelor Creek 92.0
END DESCRIPTION:
XS GIS Cut Line= 3
      2645813.14      6970601.39        2643676.        6969961.
      2642475.96      6970261.01
#Sta/Elev= 30
    2769  517.72  2808.8  516.33  3031.9  514.94  3103.3  510.85  3183.6  509.56
  3202.5  509.72  3207.8  511.96    3307  510.89  3350.6  513.59  3487.1  512.99
  3945.7  512.96  4436.3  507.89    4456  509.27  4527.4   506.6  4917.3  502.33
  4970.9  500.12  4989.6  496.79  4991.1  492.78  4992.9  492.28  5003.8  492.78
  5018.1   497.3  5041.3  500.45  5188.9  499.93    5299  502.86  5476.8  501.54
  5512.8  504.06  5587.6  501.95  5608.2   503.8  5742.2   503.6    6237  514.92
#Mann= 7 ,-1 , 0
    2769     .05       0  2808.8     .12       0  3487.1     .05       0
  4970.9     .12       0  4991.1     .07       0  5003.8     .12       0
  5188.9     .05       0
Bank Sta=4991.1,5003.8
XS Rating Curve= 0 ,0
Exp/Cntr=0.3,0.1

Type RM Length L Ch R = 1 ,59940   ,166,166,166
BEGIN DESCRIPTION:
Mapping XS 3c3451c4
END DESCRIPTION:
XS GIS Cut Line= 5
      2645205.57      6969753.64       2644054.3      6968579.27
      2643676.05      6969232.05       2643266.1      6970027.19
      2642340.97       6970222.4
#Sta/Elev= 30
    2601  514.78  3831.5  504.52    4217  502.83  4413.4  501.25  4515.3  503.01
  4574.1  500.95  4605.6  501.51  4611.4  503.65  4632.9  501.13  4766.3  501.13
  4889.7  498.43  4895.5  494.53  4905.4  497.12  4991.6  496.57  5007.7  498.48
  5013.4  493.67  5023.5   493.3  5025.3   492.8  5036.3   493.3  5052.1  494.69
  5057.7  498.66  5096.4   497.2  5235.1   500.8  5312.4  498.64  5578.3  502.25
  5925.4  501.37    5956  504.05  6038.5  501.89  6277.1  504.17  6840.1  518.73
#Mann= 5 ,-1 , 0
    2601     .05       0  3831.5     .12       0    4217     .05       0
  5023.5     .03       0  5036.3     .05       0
Bank Sta=5023.5,5036.3
XS Rating Curve= 0 ,0
Exp/Cntr=0.3,0.1

Type RM Length L Ch R = 1 ,59774   ,1360,1360,1360
BEGIN DESCRIPTION:
Mapping XS b40f130e
END DESCRIPTION:
XS GIS Cut Line= 5
      2645231.59      6969722.36      2643997.24      6968425.52
      2643642.69      6969077.48      2643215.99      6969894.27
      2642346.24      6970144.26
#Sta/Elev= 30
  2467.5  514.72  3087.9  509.79    3187  506.32  3715.6  504.62  4049.5  502.94
  4155.7   502.1    4184  503.87  4257.5  500.63  4853.7  499.56  4890.2  497.53
  4903.1  493.22  4912.9  493.06  4919.2  495.49  4924.9   492.1  4947.1  496.15
  4962.9  496.33  4969.9  495.37  4978.4  490.62  4980.2  490.12  4991.2  490.62
  5006.6  496.45  5050.8  499.63  5067.2   498.7  5072.9  500.64  5585.9  500.94
  5591.5  502.67  5883.7  501.23  6244.1  504.14  6535.4  509.41  6826.5  518.13
#Mann= 5 ,-1 , 0
  2467.5     .05       0  3715.6     .12       0  4049.5     .05       0
  4978.4     .03       0  4991.2     .05       0
Bank Sta=4978.4,4991.2
XS Rating Curve= 0 ,0
Exp/Cntr=0.3,0.1

Type RM Length L Ch R = 1 ,58414   ,966,966,966
BEGIN DESCRIPTION:
Bachelor Creek 87.0
END DESCRIPTION:
XS GIS Cut Line= 3
      2645252.88      6966764.02        2643726.        6967811.
      2641926.02      6968710.99
#Sta/Elev= 30
  3149.1  510.26  3312.2  509.44  3497.9  508.87  3597.3  508.88  3612.2  504.28
  3633.2  504.48  3642.1  507.19  3648.1  505.24    3663   509.9    3705  509.88
  3806.5  505.02  3985.9  506.96  4281.7  501.37  4532.8  499.47  4589.6  495.78
  4598.4  492.02  4604.5   495.6  4634.3  498.19  4834.6  498.48    4993  495.94
  5000.5  494.54  5002.4  490.49  5004.2  489.99  5015.3  490.49  5031.2  496.52
  5103.9  498.38  5372.2  496.01  5894.9  498.65  6163.2  507.94  7012.9  524.95
#Mann= 5 ,-1 , 0
  3149.1     .05       0  3312.2     .12       0  3497.9     .05       0
  5002.4     .04       0  5015.3     .05       0
Bank Sta=5002.4,5015.3
XS Rating Curve= 0 ,0
Exp/Cntr=0.3,0.1

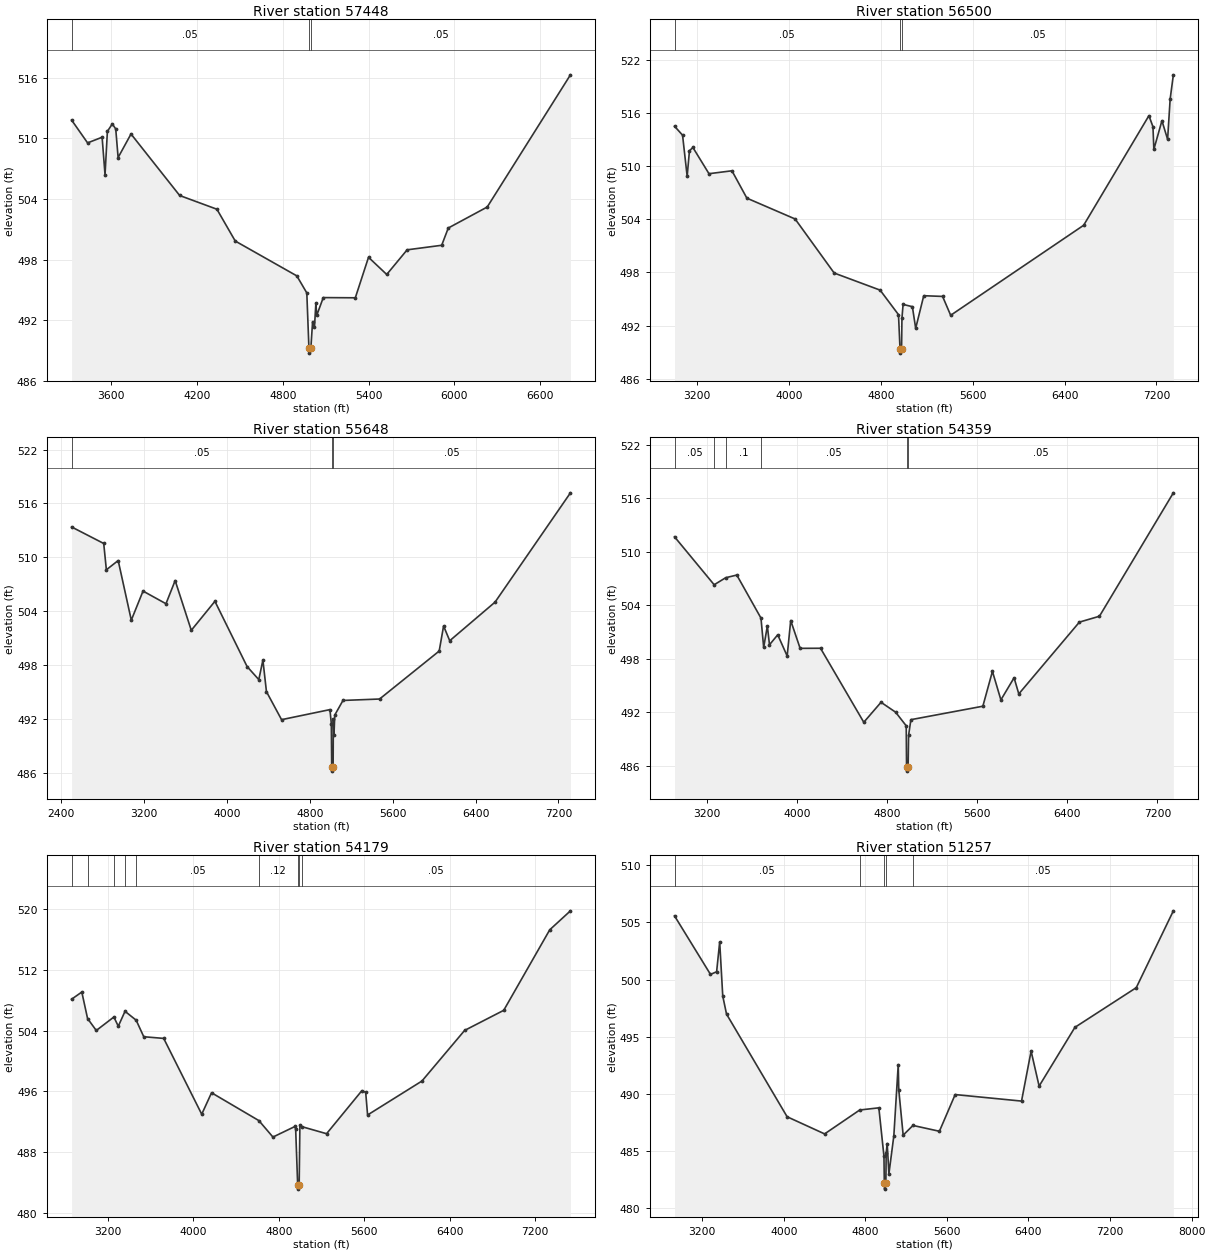
Type RM Length L Ch R = 1 ,57448   ,948,948,948
BEGIN DESCRIPTION:
Bachelor Creek 85.0
END DESCRIPTION:
XS GIS Cut Line= 3
        2645326.        6966561.        2643676.        6966861.
      2642026.01      6967610.99
#Sta/Elev= 30
  3322.6  511.82  3434.4  509.56    3536  510.12  3556.4   506.4  3572.9   510.7
  3607.2  511.44  3631.3  510.94  3647.9  508.11  3738.1  510.44  4078.5  504.35
    4339  502.99  4467.3  499.84    4898  496.39  4967.9   494.7  4982.7  489.24
  4984.6  488.74  4996.2  489.24  5008.4  491.86  5021.6  491.35  5031.5  493.72
    5037  492.47  5083.1  494.24  5307.2  494.22  5399.5  498.23  5526.9  496.53
  5669.7  498.97  5911.4  499.42  5957.5  501.13  6229.9  503.21  6812.1   516.3
#Mann= 3 ,-1 , 0
  3322.6     .05       0  4982.7     .04       0  4996.2     .05       0
Bank Sta=4982.7,4996.2
XS Rating Curve= 0 ,0
Exp/Cntr=0.3,0.1

Type RM Length L Ch R = 1 ,56500   ,852,852,852
BEGIN DESCRIPTION:
Bachelor Creek 83.0
END DESCRIPTION:
XS GIS Cut Line= 3
      2645625.97        6965961.        2643626.        6965961.
      2641826.04      6967460.97
#Sta/Elev= 30
  3004.6   514.5  3074.6  513.49  3114.6  508.85  3134.6  511.73  3164.6   512.1
  3304.6  509.14  3504.6  509.47  3634.6  506.38  4054.6  504.03  4394.6  497.93
  4794.6     496  4954.6  493.23  4967.8  489.39  4969.7  488.89  4981.4  489.39
  4984.6  492.83  4994.6  494.39  5075.5  494.13  5104.2  491.69  5174.4  495.37
  5338.5  495.29  5408.8  493.16  6566.6  503.32  7134.8  515.69    7170  514.44
  7177.8  511.89  7248.1  515.12  7297.5  513.02  7319.7  517.57  7347.6   520.3
#Mann= 3 ,-1 , 0
  3004.6     .05       0  4967.8     .04       0  4981.4     .05       0
Bank Sta=4967.8,4981.4
XS Rating Curve= 0 ,0
Exp/Cntr=0.3,0.1

Type RM Length L Ch R = 1 ,55648   ,1289,1289,1289
BEGIN DESCRIPTION:
Bachelor Creek 81.0
END DESCRIPTION:
XS GIS Cut Line= 3
      2645539.32      6964743.18        2643126.        6965411.
      2641211.81      6966706.33
#Sta/Elev= 30
  2500.3  513.38  2810.3  511.54  2835.8  508.61  2949.9  509.64  3076.5     503
  3189.8  506.24  3411.2  504.83  3499.8  507.41  3655.5  501.87  3883.7   505.1
    4194  497.84  4307.3  496.38  4346.8  498.55  4381.1  495.04    4527  491.92
  4993.9  493.04  5007.3  491.48    5011  486.69  5012.9  486.19  5024.7  486.69
  5026.8  491.96  5032.8  490.18  5040.5  492.43  5119.7  494.06  5473.2  494.22
  6048.5  499.56    6091  502.35  6150.3  500.71  6587.8  505.01  7315.6  517.18
#Mann= 3 ,-1 , 0
  2500.3     .05       0    5011     .04       0  5024.7     .05       0
Bank Sta=5011,5024.7
XS Rating Curve= 0 ,0
Exp/Cntr=0.3,0.1

Type RM Length L Ch R = 1 ,54359   ,180,180,180
BEGIN DESCRIPTION:
Bachelor Creek 79.0
END DESCRIPTION:
XS GIS Cut Line= 3
      2645221.64      6963743.18        2643226.        6964361.
      2641026.02      6965160.99
#Sta/Elev= 30
  2910.9  511.66  3262.9  506.28  3365.4  507.07  3463.9  507.37  3678.7  502.54
  3702.7  499.25  3735.3  501.66  3754.3  499.55  3827.5  500.67  3911.3  498.29
  3942.7  502.27  4026.4  499.15  4207.5  499.16  4591.7  490.86  4744.9   493.1
  4874.4  491.99  4968.6  490.46  4971.5  485.88  4973.5  485.38  4985.3  485.88
  4989.5  489.39    5010  491.15  5649.1  492.66  5734.2  496.57  5809.3  493.37
  5926.4  495.85  5968.3  494.04  6506.3  502.09  6684.5  502.75  7340.9  516.59
#Mann= 6 ,-1 , 0
  2910.9     .05       0  3262.9    .075       0  3365.4      .1       0
  3678.7     .05       0  4971.5     .03       0  4985.3     .05       0
Bank Sta=4971.5,4985.3
XS Rating Curve= 0 ,0
Exp/Cntr=0.3,0.1

Type RM Length L Ch R = 1 ,54179   ,2922,2922,2922
BEGIN DESCRIPTION:
Bachelor Creek 78.0
END DESCRIPTION:
XS GIS Cut Line= 3
      2645169.58      6963586.92      2643125.18      6964221.07
      2640776.03      6965160.99
#Sta/Elev= 30
  2859.5  508.12    2955  509.06    3009  505.58  3090.5  504.01  3255.2  505.78
  3296.5  504.57  3359.6  506.53  3464.1  505.36    3535  503.19  3721.8  502.97
  4077.8  493.01  4169.8  495.83  4613.2  492.17  4744.6  490.01  4950.6   491.4
  4957.3  491.07  4976.3  483.67  4978.2  483.17  4990.1  483.67    4997  491.56
  5014.5  491.38  5246.8  490.45    5577   496.1    5613  495.89  5630.8  492.91
  6139.7  497.37  6539.3  504.02  6905.5  506.66  7336.4  517.24  7530.2  519.73
#Mann= 9 ,-1 , 0
  2859.5     .12       0    3009     .05       0  3255.2    .075       0
  3359.6      .1       0  3464.1     .05       0  4613.2     .12       0
  4976.3     .07       0  4990.1     .12       0  5014.5     .05       0
Bank Sta=4976.3,4990.1
XS Rating Curve= 0 ,0
Exp/Cntr=0.3,0.1

Type RM Length L Ch R = 1 ,51257   ,145,145,145
BEGIN DESCRIPTION:
Bachelor Creek 75.0
END DESCRIPTION:
XS GIS Cut Line= 5
      2644508.12      6961446.29      2643309.36      6961515.99
      2643128.33      6962366.76      2642837.28      6963652.19
      2641617.46      6964529.65
#Sta/Elev= 30
  2929.4  505.57  3282.1  500.45  3342.2  500.68  3372.3  503.29  3402.3  498.56
  3439.3  496.98  4033.4     488  4401.1   486.5  4745.2  488.59  4932.8  488.78
    4983  484.55  4986.6  482.17  4988.6  481.67  5001.6  482.17  5004.7   484.8
  5014.6  485.66  5031.6  483.01  5079.9  486.34    5123  492.56  5128.1  490.37
  5171.3  486.39  5267.5  487.24  5526.7  486.73  5681.1  489.94  6331.9  489.37
  6425.7  493.74  6504.3  490.68  6855.4  495.82  7456.9  499.29  7820.6  506.01
#Mann= 5 ,-1 , 0
  2929.4     .05       0  4745.2     .12       0  4986.6     .07       0
  5001.6     .12       0  5267.5     .05       0
Bank Sta=4986.6,5001.6
XS Rating Curve= 0 ,0
Exp/Cntr=0.3,0.1

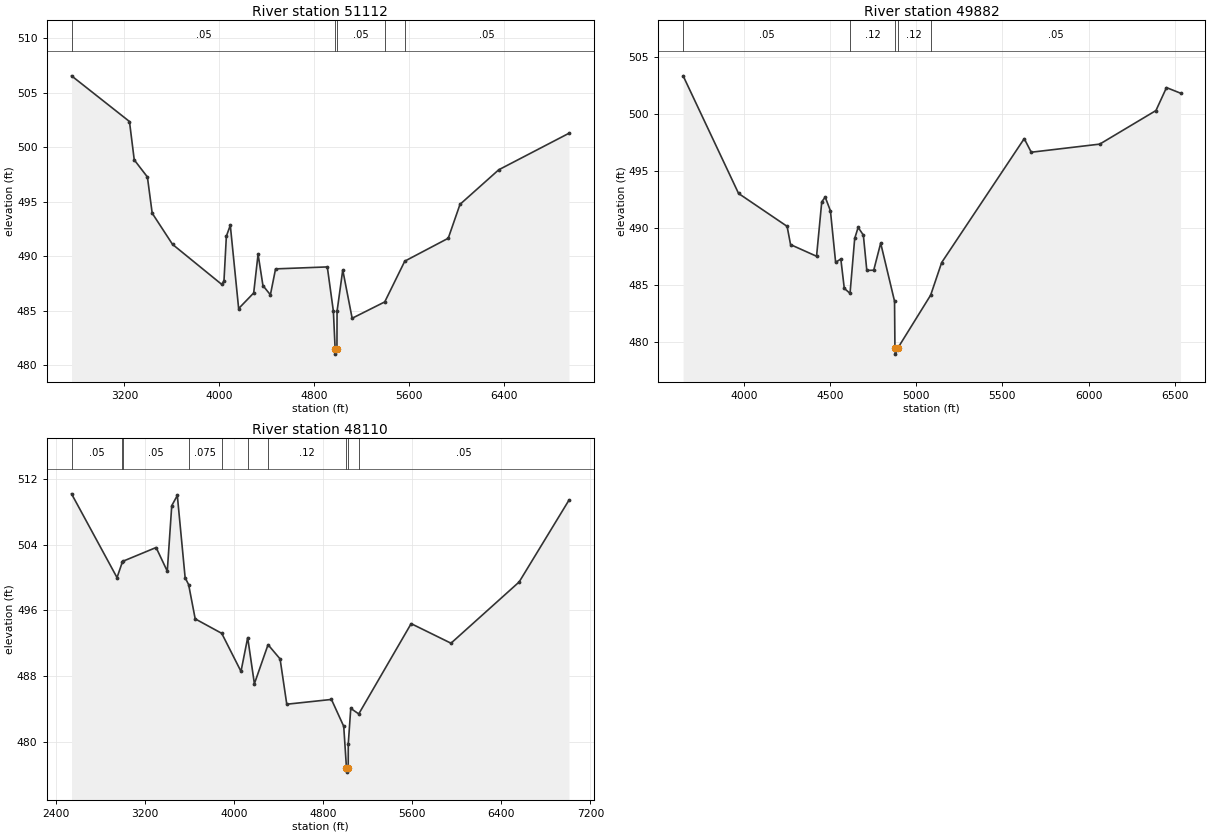
Type RM Length L Ch R = 1 ,51112   ,1230,1230,1230
BEGIN DESCRIPTION:
Bachelor Creek 74.0
END DESCRIPTION:
XS GIS Cut Line= 5
      2644560.19      6961347.34      2643169.58      6961534.84
      2642991.18      6962339.08      2642794.58      6962899.42
      2641721.64      6963758.81
#Sta/Elev= 30
  2753.3  506.56  3241.9  502.37  3282.2  498.85  3393.2  497.28  3433.6  493.96
  3605.1   491.1  4019.7  487.43    4039  487.74  4059.2  491.85  4092.4  492.85
  4162.8  485.21  4289.7  486.64  4326.7   490.2  4367.7  487.32  4430.6  486.47
  4474.2  488.85  4910.6  489.03  4961.8  484.97  4976.6  481.53  4978.6  481.03
  4991.9  481.53  4992.9  484.96  5040.9  488.75  5120.1  484.32    5395  485.82
  5564.1  489.56  5930.6  491.66  6029.8  494.77  6356.4  497.94  6948.8  501.29
#Mann= 5 ,-1 , 0
  2753.3     .05       0  4976.6     .03       0  4991.9     .05       0
    5395     .12       0  5564.1     .05       0
Bank Sta=4976.6,4991.9
XS Rating Curve= 0 ,0
Exp/Cntr=0.3,0.1

Type RM Length L Ch R = 1 ,49882   ,1772,1772,1772
BEGIN DESCRIPTION:
Bachelor Creek 72.0
END DESCRIPTION:
XS GIS Cut Line= 3
      2644075.98        6961361.        2642726.        6961511.
      2641225.99        6961811.
#Sta/Elev= 30
  3646.2  503.33  3968.1  493.03  4249.9  490.15    4270  488.55  4420.9  487.53
  4451.1   492.3  4471.2  492.71  4501.4  491.51  4531.6     487  4561.8  487.29
  4581.9  484.72  4615.3  484.28  4642.3  489.09  4662.4  490.06  4692.6  489.38
  4712.7  486.29  4752.9  486.31  4793.2  488.68  4873.7  483.59    4876  479.46
    4878  478.96  4891.5  479.46  5083.5  484.13  5147.3  486.98  5626.6  497.83
  5667.4  496.64  6065.1  497.35  6391.4  500.29  6452.6   502.3  6534.2  501.81
#Mann= 5 ,-1 , 0
  3646.2     .05       0  4615.3     .12       0    4876     .07       0
  4891.5     .12       0  5083.5     .05       0
Bank Sta=4876,4891.5
XS Rating Curve= 0 ,0
Exp/Cntr=0.3,0.1

Type RM Length L Ch R = 1 ,48110   ,625,625,625
BEGIN DESCRIPTION:
Bachelor Creek 69.0
END DESCRIPTION:
XS GIS Cut Line= 3
      2645023.33      6960696.35        2642576.        6960511.
        2640776.        6961411.
#Sta/Elev= 30
  2540.8  510.19  2949.3     500  2997.4  501.91  3000.7  501.98  3300.3  503.66
  3400.6  500.78  3440.7  508.75  3490.8  509.99    3561  499.98  3592.2  499.15
  3651.3  494.98  3889.6  493.22  4062.5  488.59  4122.7   492.7  4182.8  487.09
  4305.4  491.84  4413.5  490.11  4473.6   484.6  4874.8  485.18  4985.1  481.91
  5009.7  476.84  5011.7  476.34  5025.3  476.84  5025.9  479.78  5048.2  484.09
    5120  483.42  5590.5   494.4  5948.3  492.02  6560.4  499.47  7007.6  509.42
#Mann= 10 ,-1 , 0
  2540.8     .05       0  2997.4    .075       0  3000.7     .05       0
  3592.2    .075       0  3889.6     .05       0  4122.7    .075       0
  4305.4     .12       0  5009.7     .07       0  5025.3     .12       0
    5120     .05       0
Bank Sta=5009.7,5025.3
XS Rating Curve= 0 ,0
Exp/Cntr=0.3,0.1