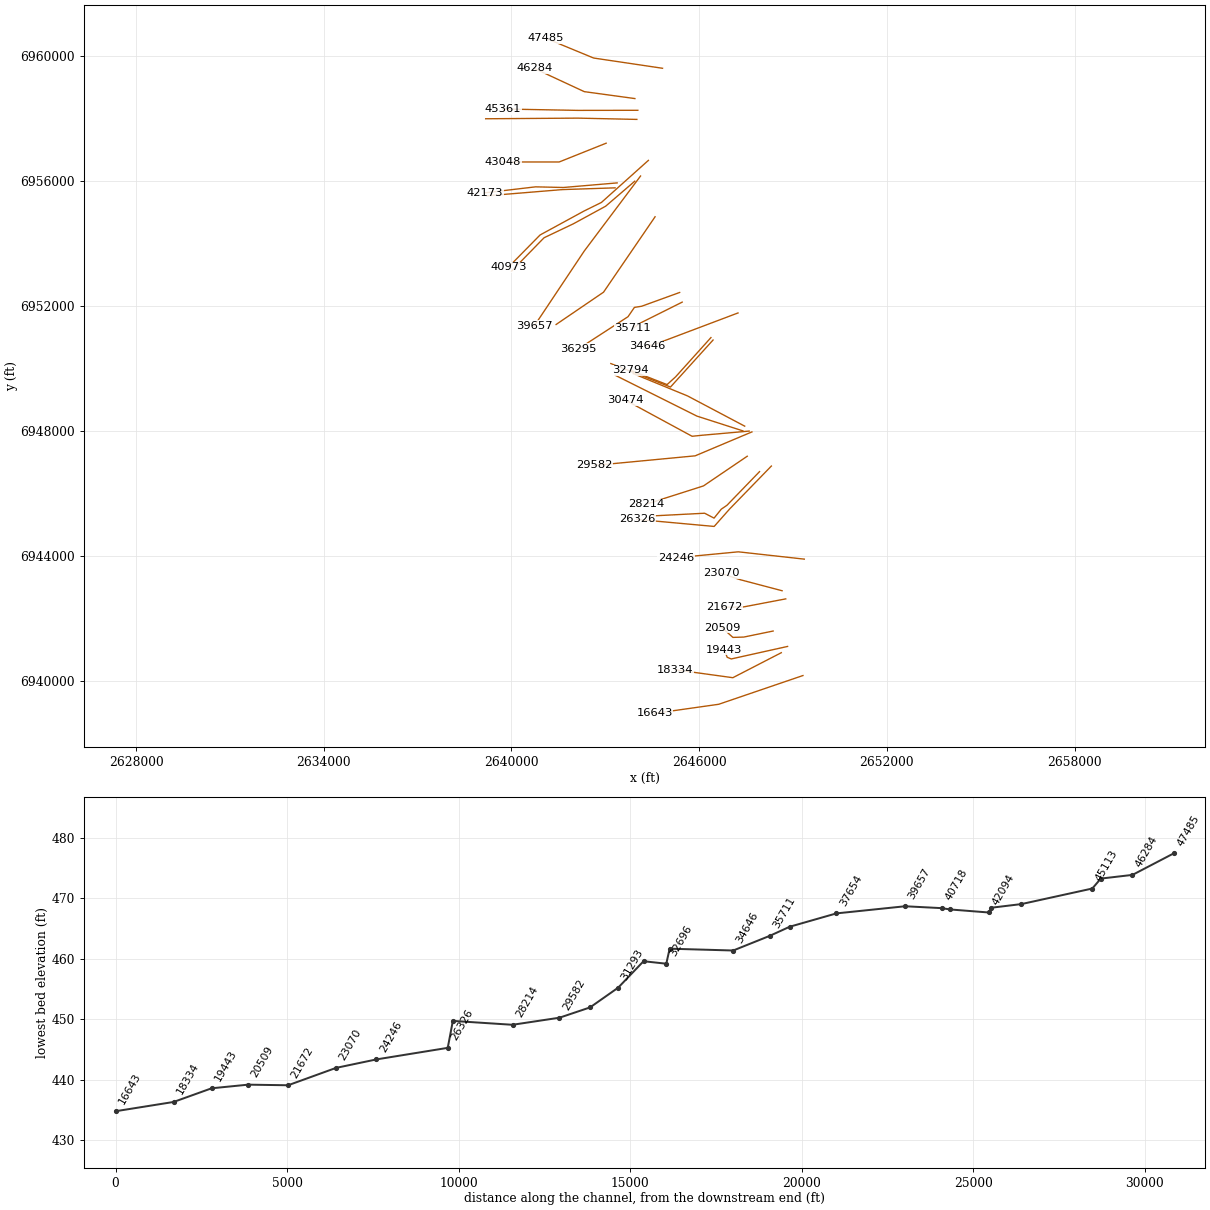
HEC-RAS study Bachelor Creek.prj: Bachelor Creek Base Level Engineering

--- Bachelor Creek.g01 (geometry) --- (continued)

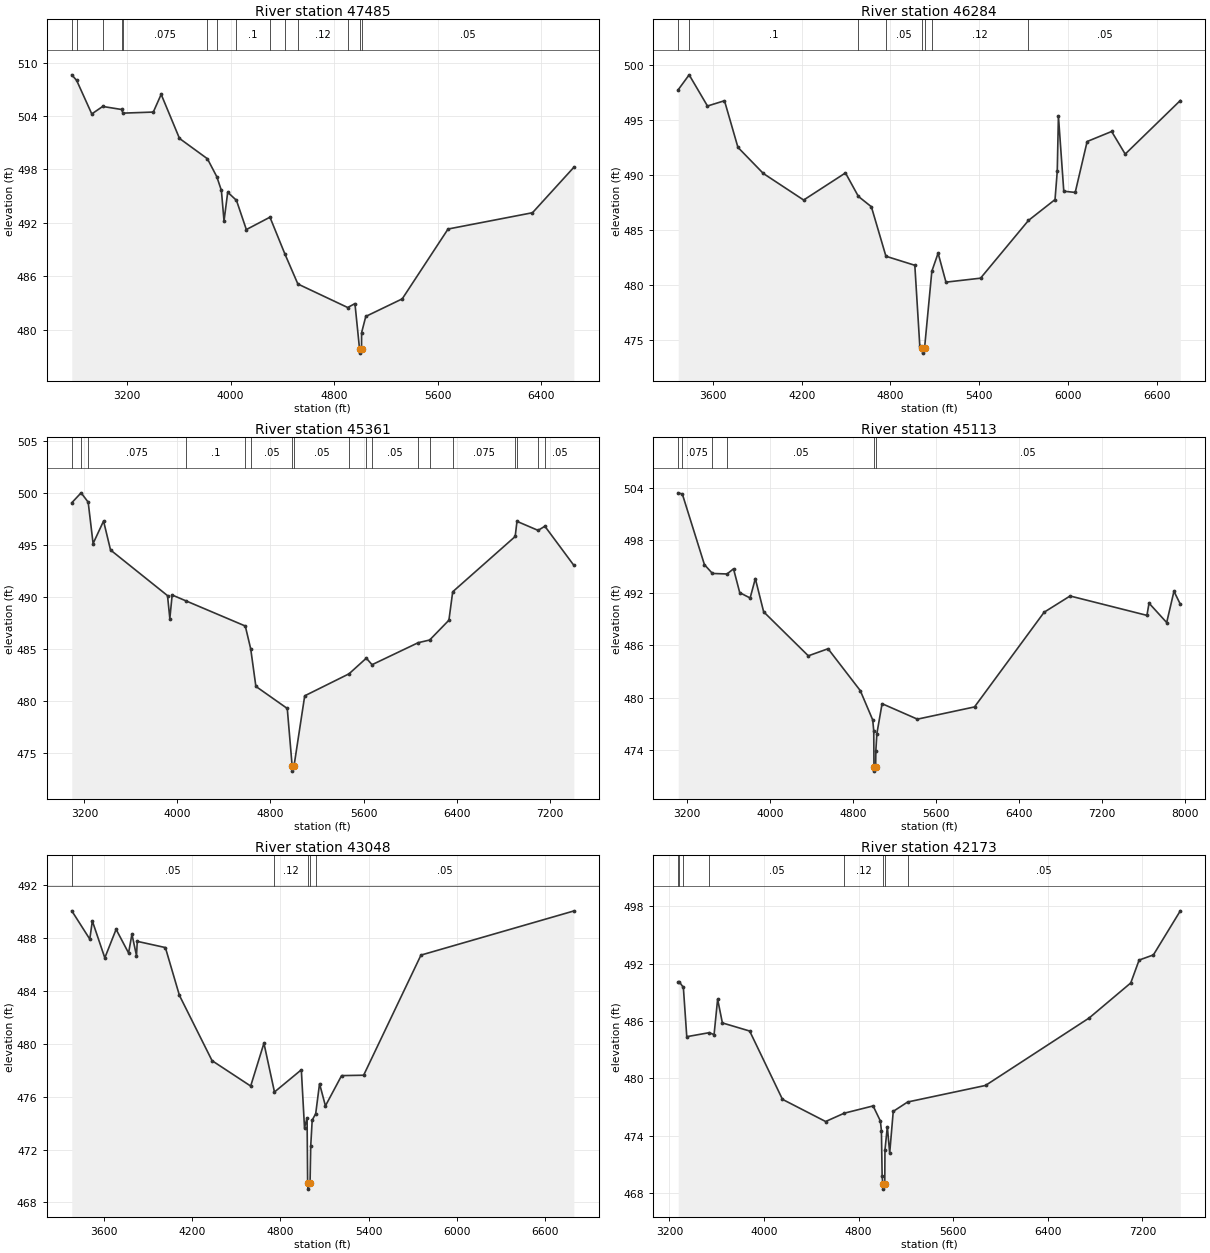
Type RM Length L Ch R = 1 ,47485   ,1201,1201,1201
BEGIN DESCRIPTION:
Bachelor Creek 67.0
END DESCRIPTION:
XS GIS Cut Line= 3
       2644828.8      6959608.43      2642626.21      6959935.91
      2641101.19      6960566.11
#Sta/Elev= 30
  2773.2  508.62    2811  507.99  2927.7  504.23    3012  505.07  3157.2  504.73
    3169  504.32  3402.8  504.44  3463.5  506.43    3605  501.48  3820.5   499.2
  3892.9  497.19  3928.6  495.64  3948.8  492.21  3977.3  495.44  4044.9  494.53
  4121.2  491.25  4303.5  492.64  4418.6  488.52  4519.1  485.14  4903.9   482.5
  4959.8  482.94  4995.1  477.88  4997.1  477.38  5010.8  477.88  5011.1  479.67
  5043.5   481.5  5324.8  483.47  5678.7  491.31  6330.7  493.14  6650.1  498.24
#Mann= 14 ,-1 , 0
  2773.2     .05       0    2811     .12       0    3012    .075       0
  3157.2     .12       0    3169    .075       0  3820.5      .1       0
  3892.9    .075       0  4044.9      .1       0  4303.5    .075       0
  4418.6     .05       0  4519.1     .12       0  4903.9     .05       0
  4995.1     .03       0  5010.8     .05       0
Bank Sta=4995.1,5010.8
XS Rating Curve= 0 ,0
Exp/Cntr=0.3,0.1

Type RM Length L Ch R = 1 ,46284   ,923,923,923
BEGIN DESCRIPTION:
Bachelor Creek 65.0
END DESCRIPTION:
XS GIS Cut Line= 3
      2643945.62        6958639.        2642326.        6958861.
      2640732.12      6959602.53
#Sta/Elev= 30
  3365.9  497.73  3439.6  499.08  3563.5  496.25  3678.4  496.73  3769.3   492.5
  3940.9  490.13  4213.4  487.72    4496  490.18  4583.2  488.05    4671  487.11
  4769.4  482.62  4964.6   481.8  4998.1   474.5  5014.8  474.33  5016.8  473.83
  5030.7  474.33  5079.6  481.26    5122   482.9    5175  480.27  5408.7  480.63
  5732.6  485.87    5912  487.76  5927.1  490.34  5934.9  495.35  5971.2  488.52
  6048.4  488.41    6129  493.03  6294.6  493.94  6386.2  491.89  6758.6  496.75
#Mann= 8 ,-1 , 0
  3365.9    .075       0  3439.6      .1       0  4583.2    .075       0
  4769.4     .05       0  5014.8     .03       0  5030.7     .05       0
  5079.6     .12       0  5732.6     .05       0
Bank Sta=5014.8,5030.7
XS Rating Curve= 0 ,0
Exp/Cntr=0.3,0.1

Type RM Length L Ch R = 1 ,45361   ,248,248,248
BEGIN DESCRIPTION:
Bachelor Creek 63.0
END DESCRIPTION:
XS GIS Cut Line= 3
      2644039.36        6958264.        2642126.        6958261.
      2639721.67      6958305.67
#Sta/Elev= 30
  3090.9  499.09  3171.2  500.05    3232  499.15  3274.3  495.16  3364.3  497.33
  3424.3  494.54  3914.3  490.14  3934.3  487.93  3954.3   490.2  4069.7  489.65
  4583.2  487.21    4630     485  4674.3  481.39  4944.3  479.26  4986.2  473.72
  4988.2  473.22  5002.4  473.72  5094.3  480.48  5475.3   482.6  5624.2  484.11
  5673.5  483.48  6069.8   485.6  6168.9  485.86  6334.5  487.77  6367.1  490.51
  6904.5  495.84  6919.9   497.3  7101.4  496.43  7159.8  496.83    7409  493.06
#Mann= 18 ,-1 , 0
  3090.9    .075       0  3171.2      .1       0    3232    .075       0
  4069.7      .1       0  4583.2    .075       0    4630     .05       0
  4986.2     .03       0  5002.4     .05       0  5475.3    .075       0
  5624.2      .1       0  5673.5     .05       0  6069.8    .075       0
  6168.9      .1       0  6367.1    .075       0  6904.5      .1       0
  6919.9    .075       0  7101.4      .1       0  7159.8     .05       0
Bank Sta=4986.2,5002.4
XS Rating Curve= 0 ,0
Exp/Cntr=0.3,0.1

Type RM Length L Ch R = 1 ,45113   ,2065,2065,2065
BEGIN DESCRIPTION:
Bachelor Creek 62.0
END DESCRIPTION:
XS GIS Cut Line= 3
      2644008.07      6957972.34      2642126.02      6958013.31
      2639174.79      6957993.17
#Sta/Elev= 30
  3117.5  503.44    3157   503.3  3369.6  495.22  3446.8  494.21  3587.5  494.15
  3649.7  494.74  3709.7  492.01  3809.7   491.4  3859.7  493.62  3939.8  489.82
  4369.9  484.78  4559.9  485.59    4870   480.8    4990  477.44    5000  476.15
  5001.9  472.08  5003.9  471.58  5018.2  472.08    5020  473.92    5030  475.88
    5080   479.3    5420  477.53    5970  478.93  6640.1  489.77  6890.1  491.63
  7630.1  489.41  7650.1  490.81  7820.1  488.59  7890.1  492.17  7951.3  490.69
#Mann= 6 ,-1 , 0
  3117.5      .1       0    3157    .075       0  3446.8      .1       0
  3587.5     .05       0  5001.9     .03       0  5018.2     .05       0
Bank Sta=5001.9,5018.2
XS Rating Curve= 0 ,0
Exp/Cntr=0.3,0.1

Type RM Length L Ch R = 1 ,43048   ,875,875,875
BEGIN DESCRIPTION:
Bachelor Creek 61.0
END DESCRIPTION:
XS GIS Cut Line= 3
      2643026.02      6957211.01        2641526.        6956611.
      2639725.97        6956611.
#Sta/Elev= 30
  3380.1  490.07  3502.6  487.93  3520.1   489.3  3604.9  486.51  3681.7  488.67
  3766.5  486.88  3789.4   488.3  3820.4  486.68  3825.7  487.76  4016.9  487.29
  4112.5  483.67  4334.6  478.73  4597.2  476.81  4687.4  480.05  4759.1  476.36
  4941.8  478.04  4963.4  473.65  4980.9  474.41  4984.7  469.51  4986.7  469.01
  5001.2  469.51  5005.7  472.27  5015.7  474.23  5039.6  474.72  5065.7  476.99
  5105.7  475.31  5215.7   477.6  5365.7  477.63  5755.7  486.72  6795.7  490.06
#Mann= 5 ,-1 , 0
  3380.1     .05       0  4759.1     .12       0  4984.7     .07       0
  5001.2     .12       0  5039.6     .05       0
Bank Sta=4984.7,5001.2
XS Rating Curve= 0 ,0
Exp/Cntr=0.3,0.1

Type RM Length L Ch R = 1 ,42173   ,79,79,79
BEGIN DESCRIPTION:
Bachelor Creek 60.0
END DESCRIPTION:
XS GIS Cut Line= 4
      2643377.93      6955941.09      2641658.98       6955794.3
      2640768.06      6955814.95      2639149.91      6955623.51
#Sta/Elev= 30
  3274.8  490.06    3284  490.08  3318.2   489.5    3347  484.35  3537.3  484.77
  3577.8  484.56  3607.9  488.27  3648.1  485.79  3878.9  484.94  4156.1   477.8
  4521.2  475.48  4678.6  476.35  4922.7  477.11    4984  475.54    4993  474.53
    4999  469.83  5004.6  468.91  5006.6  468.41  5021.3  468.91    5023   472.5
    5043  474.94    5063  472.18    5093  476.54  5214.7  477.52  5873.2  479.25
  6749.2   486.3  7101.6  489.97  7172.1  492.36  7292.9   492.9  7520.6  497.51
#Mann= 8 ,-1 , 0
  3274.8    .075       0    3284      .1       0  3318.2    .075       0
  3537.3     .05       0  4678.6     .12       0  5004.6     .07       0
  5021.3     .12       0  5214.7     .05       0
Bank Sta=5004.6,5021.3
XS Rating Curve= 0 ,0
Exp/Cntr=0.3,0.1

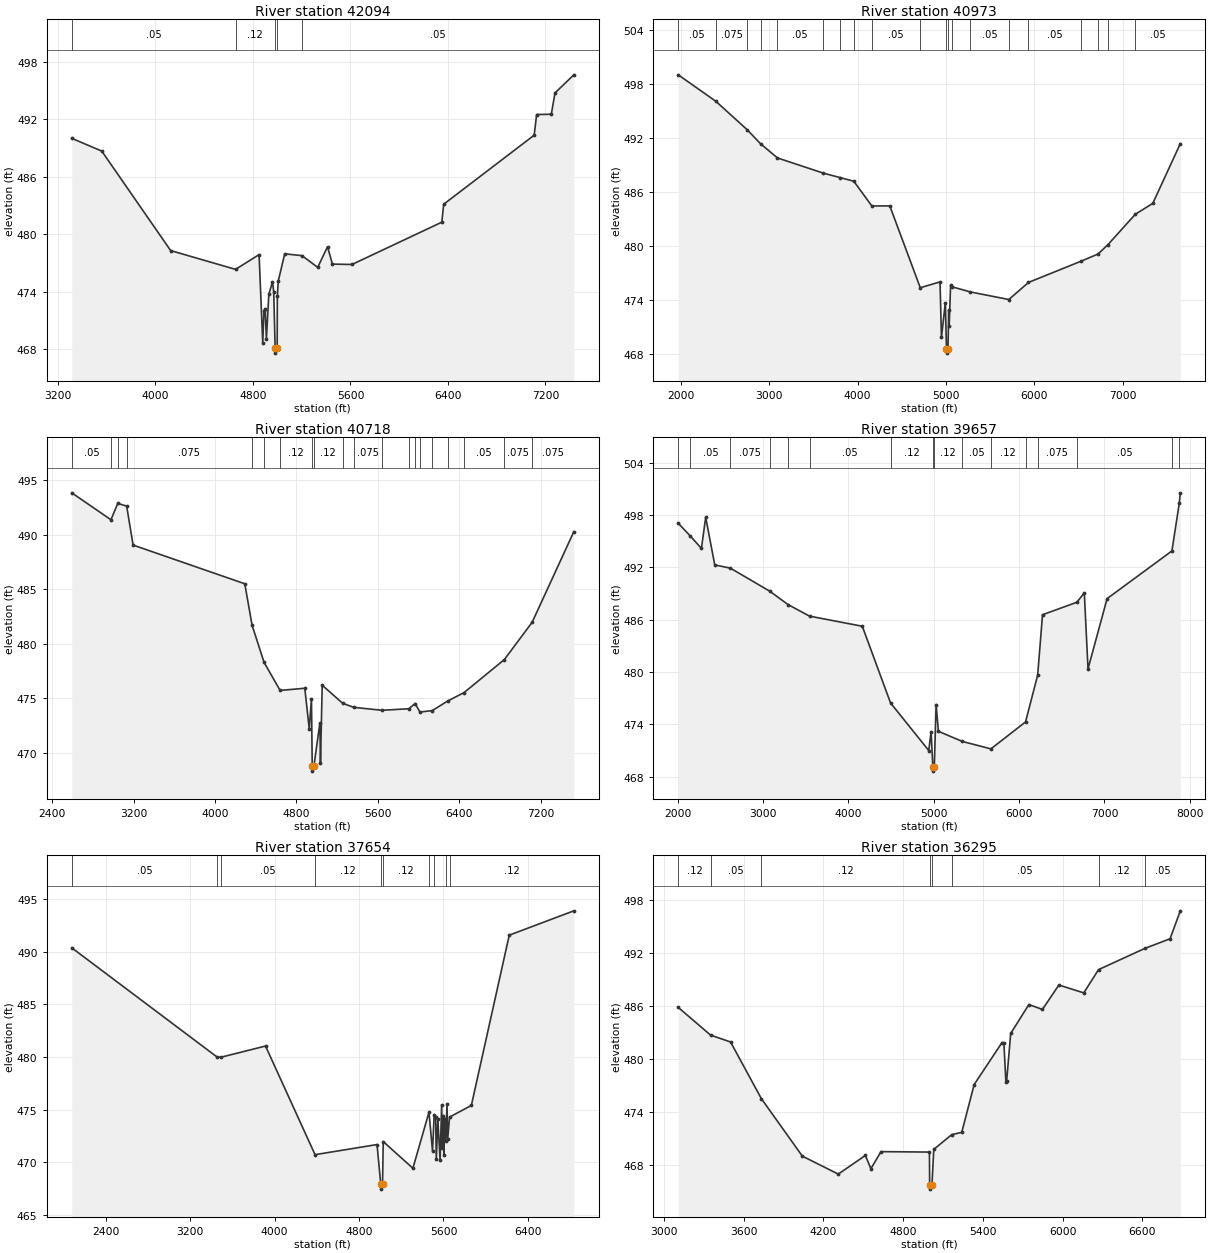
Type RM Length L Ch R = 1 ,42094   ,1121,1121,1121
BEGIN DESCRIPTION:
Bachelor Creek 59.0
END DESCRIPTION:
XS GIS Cut Line= 3
      2643311.99       6955783.1      2641626.13      6955726.76
      2639201.74      6955527.03
#Sta/Elev= 30
  3313.2  490.01  3559.3  488.68  4124.6  478.31  4657.1  476.35    4850  477.89
  4880.1   468.7  4890.1  472.04  4900.1  472.25  4910.1  469.09  4930.1  473.76
  4960.1  475.03  4970.1  474.04  4981.8  468.12  4983.8  467.62  4998.5  468.12
    5000  473.55  5007.2  475.12  5060.3  477.97  5202.3  477.78  5331.2  476.56
  5411.5  478.71  5451.7   476.9  5612.2  476.86  6349.3  481.27  6364.7  483.14
  7107.2  490.34  7127.3  492.49  7247.7  492.52  7277.8  494.74  7432.6  496.63
#Mann= 5 ,-1 , 0
  3313.2     .05       0  4657.1     .12       0  4981.8     .07       0
  4998.5     .12       0  5202.3     .05       0
Bank Sta=4981.8,4998.5
XS Rating Curve= 0 ,0
Exp/Cntr=0.3,0.1

Type RM Length L Ch R = 1 ,40973   ,255,255,255
BEGIN DESCRIPTION:
Bachelor Creek 56.0
END DESCRIPTION:
XS GIS Cut Line= 5
      2644375.99      6956660.99      2642873.57      6955314.35
      2642326.98      6955045.09      2640912.91      6954274.26
      2639901.71      6953245.29
#Sta/Elev= 30
  1970.9  499.06  2396.2  496.12  2751.8  492.95  2902.5  491.39  3093.7  489.82
  3609.5  488.14  3804.3  487.63  3957.2  487.23  4161.4  484.48  4364.3  484.49
    4709  475.39  4932.6  476.04  4948.7  469.86  4992.4  473.73  5005.7  468.62
  5007.7  468.12  5022.7  468.62  5030.3  472.88    5036  471.15  5052.2  475.66
  5063.2  475.51  5277.1  474.92  5710.9  474.08  5933.5  475.98  6525.8  478.33
  6720.8  479.14  6833.1  480.19  7142.5  483.56  7339.8  484.77    7651  491.41
#Mann= 20 ,-1 , 0
  1970.9     .05       0  2396.2    .075       0  2751.8     .05       0
  2902.5     .05       0  3093.7     .05       0  3609.5    .075       0
  3804.3     .05       0  3957.2    .075       0  4161.4     .05       0
    4709     .05       0  5005.7     .03       0  5022.7     .05       0
  5063.2     .05       0  5277.1     .05       0  5710.9     .05       0
  5933.5     .05       0  6525.8    .075       0  6720.8     .05       0
  6833.1    .075       0  7142.5     .05       0
Bank Sta=5005.7,5022.7
XS Rating Curve= 0 ,0
Exp/Cntr=0.3,0.1

Type RM Length L Ch R = 1 ,40718   ,1061,1061,1061
BEGIN DESCRIPTION:
Bachelor Creek 55.0
END DESCRIPTION:
XS GIS Cut Line= 5
      2643941.27      6955995.77      2643010.14      6955195.14
      2641975.43      6954631.05      2641040.52      6954185.72
      2640000.65      6953118.52
#Sta/Elev= 30
  2593.5  493.86  2978.4  491.39  3045.5  492.89  3132.9  492.64  3195.9  489.07
  4293.2  485.52    4365  481.71  4482.2  478.32  4640.2  475.74  4882.5  475.94
  4926.1  472.23    4948  474.98  4955.6  468.84  4957.6  468.34  4972.7  468.84
    5031  472.77  5036.6  469.07  5053.7  476.22  5254.6  474.56  5363.1  474.19
  5639.7  473.92  5905.2  474.06  5966.2  474.54  6013.7  473.76    6135  473.89
  6284.5  474.76  6448.2  475.55  6842.9  478.57  7116.1  481.99  7525.6   490.3
#Mann= 20 ,-1 , 0
  2593.5     .05       0  2978.4    .075       0  3045.5     .05       0
  3132.9    .075       0    4365     .05       0  4482.2    .075       0
  4640.2     .12       0  4955.6     .07       0  4972.7     .12       0
  5254.6     .05       0  5363.1    .075       0  5639.7     .05       0
  5905.2    .075       0  5966.2     .05       0  6013.7    .075       0
    6135     .05       0  6284.5    .075       0  6448.2     .05       0
  6842.9    .075       0  7116.1    .075       0
Bank Sta=4955.6,4972.7
XS Rating Curve= 0 ,0
Exp/Cntr=0.3,0.1

Type RM Length L Ch R = 1 ,39657   ,2003,2003,2003
BEGIN DESCRIPTION:
Bachelor Creek 54.0
END DESCRIPTION:
XS GIS Cut Line= 3
      2644125.98      6956160.97        2642326.        6953761.
        2640726.        6951361.
#Sta/Elev= 30
  2004.8  497.06  2146.2  495.59  2276.6  494.17  2326.6  497.74  2432.9  492.28
  2615.7  491.91    3077  489.27  3290.9  487.74  3543.6  486.41  4162.1  485.25
  4493.2  476.46  4941.2  471.01  4968.3  473.17  4988.9  469.15  4990.9  468.65
    5006  469.15  5027.3  476.28  5054.3  473.21  5334.7  472.05  5669.4   471.2
  6075.4  474.29  6217.6  479.66  6274.2  486.57  6677.3     488    6764  489.08
  6807.5  480.37  7031.4  488.42  7790.8  493.88  7877.7  499.39  7889.2  500.54
#Mann= 16 ,-1 , 0
  2004.8    .075       0  2146.2     .05       0  2615.7    .075       0
    3077     .05       0  3290.9    .075       0  3543.6     .05       0
  4493.2     .12       0  4988.9     .07       0    5006     .12       0
  5334.7     .05       0  5669.4     .12       0  6075.4     .05       0
  6217.6    .075       0  6677.3     .05       0  7790.8    .075       0
  7877.7     .05       0
Bank Sta=4988.9,5006
XS Rating Curve= 0 ,0
Exp/Cntr=0.3,0.1

Type RM Length L Ch R = 1 ,37654   ,1359,1359,1359
BEGIN DESCRIPTION:
Bachelor Creek 52.0
END DESCRIPTION:
XS GIS Cut Line= 3
      2644589.99      6954856.85      2642942.47      6952444.33
      2641425.97      6951410.98
#Sta/Elev= 30
  2078.6  490.37    3456     480  3493.7  479.99  3914.2  481.05  4383.3  470.74
  4970.5   471.7  5005.7  467.97  5007.7  467.47  5022.9  467.97  5029.3  471.98
  5310.4  469.45  5462.7  474.77  5496.1   471.1  5512.1  474.54    5526  474.32
    5532   470.3  5546.9  474.09  5567.9  470.22  5582.8  475.48  5588.9  471.33
  5597.8  474.45  5603.8  470.69  5612.7  474.14  5621.4     472  5633.7  475.54
  5639.7  472.21  5657.9  474.31  5864.1  475.41  6223.2  491.57  6835.1  493.88
#Mann= 10 ,-1 , 0
  2078.6     .05       0    3456     .12       0  3493.7     .05       0
  4383.3     .12       0  5005.7     .07       0  5022.9     .12       0
  5462.7     .05       0  5512.1     .12       0  5621.4     .05       0
  5657.9     .12       0
Bank Sta=5005.7,5022.9
XS Rating Curve= 0 ,0
Exp/Cntr=0.3,0.1

Type RM Length L Ch R = 1 ,36295   ,584,584,584
BEGIN DESCRIPTION:
Bachelor Creek 49.0
END DESCRIPTION:
XS GIS Cut Line= 5
      2645376.08      6952435.36      2644159.43      6951994.29
      2643930.28      6951958.45        2643726.        6951661.
      2642140.28      6950631.33
#Sta/Elev= 30
  3107.7  485.82  3350.7  482.69  3501.3  481.91  3732.7  475.51  4041.6     469
  4311.9  466.97  4515.9  469.08  4557.1  467.58  4633.4  469.51  4997.6  469.46
  4999.4  465.77  5001.4  465.27  5016.8  465.77  5030.4  469.77  5165.7  471.43
  5240.8  471.69  5334.4   477.1  5543.1  481.83  5557.8  481.82  5572.9  477.41
  5578.9  477.55  5609.2  482.87  5745.8  486.14  5847.8  485.59  5971.7  488.35
  6158.9  487.46    6270  490.09    6617  492.48  6808.1  493.58  6885.3  496.74
#Mann= 8 ,-1 , 0
  3107.7     .12       0  3350.7     .05       0  3732.7     .12       0
  4999.4     .07       0  5016.8     .12       0  5165.7     .05       0
    6270     .12       0    6617     .05       0
Bank Sta=4999.4,5016.8
XS Rating Curve= 0 ,0
Exp/Cntr=0.3,0.1

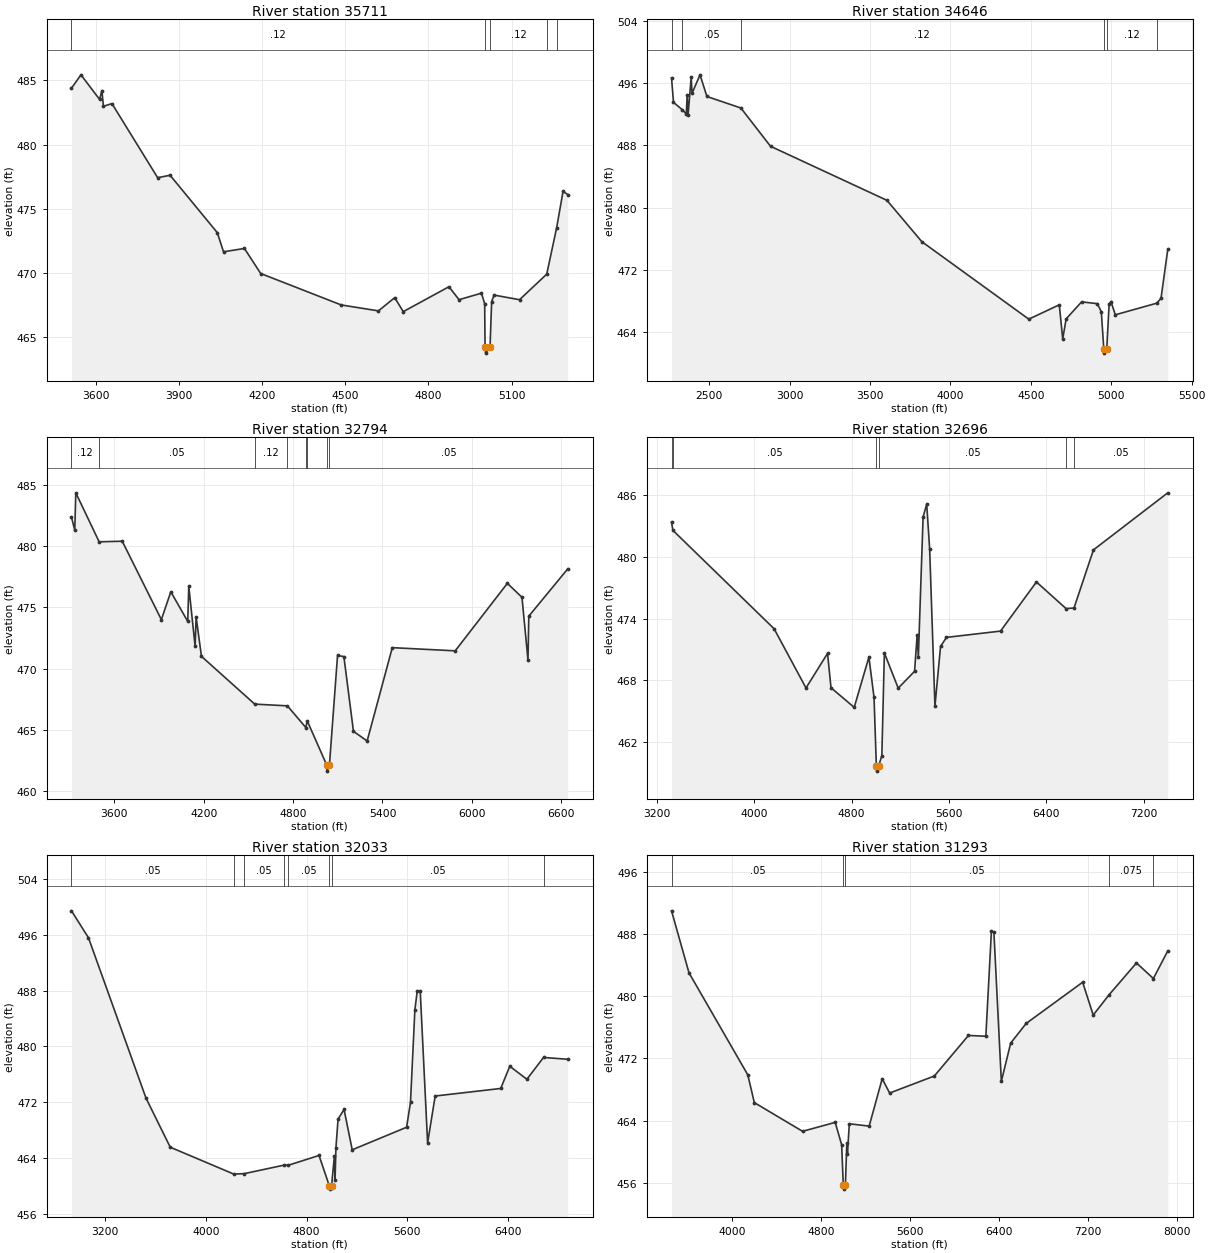
Type RM Length L Ch R = 1 ,35711   ,1065,1065,1065
BEGIN DESCRIPTION:
Bachelor Creek 48.0
END DESCRIPTION:
XS GIS Cut Line= 3
      2645456.62      6952126.31        2644126.        6951461.
      2643880.44      6951283.96
#Sta/Elev= 30
  3512.1  484.39  3546.3  485.43  3613.4  483.52  3621.8   484.2  3627.4  482.98
  3658.1  483.19    3823  477.42  3867.8  477.61  4038.3  473.14  4060.6  471.65
  4136.1  471.91  4194.8  469.96  4485.5  467.51  4619.6  467.05  4678.3  468.08
  4709.1  466.99    4874  468.93  4910.3  467.92  4991.4  468.43  5002.9   467.6
  5004.2  464.26  5006.2  463.76  5022.3  464.26    5028  467.76  5036.6  468.28
  5128.6  467.92  5226.8  469.91  5262.6  473.53  5285.7  476.36  5302.5  476.11
#Mann= 5 ,-1 , 0
  3512.1     .12       0  5004.2     .07       0  5022.3     .12       0
  5226.8     .05       0  5262.6    .075       0
Bank Sta=5004.2,5022.3
XS Rating Curve= 0 ,0
Exp/Cntr=0.3,0.1

Type RM Length L Ch R = 1 ,34646   ,1852,1852,1852
BEGIN DESCRIPTION:
Bachelor Creek 46.0
END DESCRIPTION:
XS GIS Cut Line= 3
      2647241.91      6951780.49        2644676.        6950811.
      2644345.51      6950717.94
#Sta/Elev= 30
  2265.1  496.67  2277.3  493.53  2333.1  492.56  2356.9  492.04  2362.5  494.51
  2367.8  491.86  2387.3  496.76  2392.7  494.69  2442.3  497.06  2485.2  494.28
  2696.5   492.8  2880.7  487.89  3604.9  480.95  3821.5  475.65  4487.1   465.7
  4676.7  467.54    4698  463.16  4719.4  465.74  4815.6  467.92  4913.1  467.69
    4938  466.66  4953.7  461.84  4955.7  461.34  4971.8  461.84  4986.7  467.64
  4998.3  467.96  5025.1  466.26  5282.8  467.75  5309.3  468.37  5351.4  474.65
#Mann= 6 ,-1 , 0
  2265.1     .12       0  2333.1     .05       0  2696.5     .12       0
  4953.7     .07       0  4971.8     .12       0  5282.8    .075       0
Bank Sta=4953.7,4971.8
XS Rating Curve= 0 ,0
Exp/Cntr=0.3,0.1

Type RM Length L Ch R = 1 ,32794   ,98,98,98
BEGIN DESCRIPTION:
Mapping XS 071f6141
END DESCRIPTION:
XS GIS Cut Line= 4
      2646376.29      6950992.06      2645249.98      6949739.89
      2644974.37      6949488.15      2643790.24      6949952.26
#Sta/Elev= 30
  3313.4  482.36  3335.6  481.33  3342.4  484.36  3499.1  480.36    3654  480.41
  3916.4  474.01  3979.9  476.28  4093.5  473.86  4100.3  476.74  4142.9  471.83
  4149.6  474.22  4185.5  471.01  4542.9  467.11  4761.8  466.97  4885.7   465.2
  4895.2  465.74  5025.7  462.14  5027.7  461.64  5044.1  462.14  5098.4  471.08
    5141  470.99  5205.2  464.89    5297   464.1  5465.8  471.72  5887.8  471.46
  6237.8  476.97  6335.8  475.83  6376.1   470.7  6381.5  474.29  6642.7  478.15
#Mann= 8 ,-1 , 0
  3313.4     .12       0  3499.1     .05       0  4542.9     .12       0
  4761.8     .05       0  4885.7     .12       0  4895.2     .05       0
  5025.7     .05       0  5044.1     .05       0
Bank Sta=5025.7,5044.1
XS Rating Curve= 0 ,0
Exp/Cntr=0.3,0.1

Type RM Length L Ch R = 1 ,32696   ,663,663,663
BEGIN DESCRIPTION:
Bachelor Creek 44.0
END DESCRIPTION:
XS GIS Cut Line= 3
      2646443.58      6950913.95      2645082.88      6949410.02
      2643175.96      6950161.02
#Sta/Elev= 30
  3320.2  483.37  3331.4  482.58  4162.9  473.01  4425.1  467.25  4602.2  470.61
  4630.6  467.27  4821.2  465.36  4942.2  470.25  4984.1  466.33  5003.3  459.66
  5005.3  459.16  5021.7  459.66  5048.3  460.66  5069.2  470.66  5182.8  467.23
  5317.3  468.87  5338.2  472.36  5348.3  470.26  5387.3  483.88    5417  485.14
  5441.4  480.72  5484.7  465.48  5530.7  471.29  5579.5  472.17  6023.5  472.78
  6318.7  477.56    6562  474.97  6627.5  475.03  6787.1  480.68  7397.8  486.23
#Mann= 6 ,-1 , 0
  3320.2     .12       0  3331.4     .05       0  5003.3     .05       0
  5021.7     .05       0    6562    .075       0  6627.5     .05       0
Bank Sta=5003.3,5021.7
XS Rating Curve= 0 ,0
Exp/Cntr=0.3,0.1

Type RM Length L Ch R = 1 ,32033   ,740,740,740
BEGIN DESCRIPTION:
Bachelor Creek 42.0
END DESCRIPTION:
XS GIS Cut Line= 3
       2647455.5      6948158.95      2645626.96       6949126.4
      2643891.43      6949839.73
#Sta/Elev= 30
  2931.3  499.41  3066.5  495.55  3524.2  472.58  3716.6  465.57  4222.1  461.72
  4305.7  461.79  4622.5  463.01  4655.6  462.99  4899.3  464.39  4980.6  460.07
  4982.6  459.57    4999  460.07  5021.3  464.27  5026.7  460.82  5033.5  465.44
  5050.6   469.6  5098.3  470.97  5163.2   465.2  5595.7  468.43  5626.5  472.02
  5661.3  485.24  5679.8  487.89  5703.8  487.97  5762.5  466.18  5822.7   472.9
  6343.8  473.98  6415.7  477.16  6551.7   475.3  6684.3  478.42  6876.4  478.16
#Mann= 8 ,-1 , 0
  2931.3     .05       0  4222.1     .12       0  4305.7     .05       0
  4622.5     .12       0  4655.6     .05       0  4980.6     .05       0
    4999     .05       0  6684.3    .075       0
Bank Sta=4980.6,4999
XS Rating Curve= 0 ,0
Exp/Cntr=0.3,0.1

Type RM Length L Ch R = 1 ,31293   ,819,819,819
BEGIN DESCRIPTION:
Bachelor Creek 41.0
END DESCRIPTION:
XS GIS Cut Line= 3
      2647399.46      6948007.49      2645926.02      6948480.83
      2643313.98       6949788.3
#Sta/Elev= 30
  3452.4  490.97  3609.7     483  4139.1  469.89    4198  466.32  4632.4  462.63
  4926.5  463.78  4984.2   460.9  4999.2   455.7  5001.2   455.2    5018   455.7
  5030.9  461.14  5036.5  459.68  5053.3   463.6  5232.1   463.3  5349.5  469.39
  5416.5  467.55  5818.9  469.74  6126.2  474.95  6282.7  474.85    6333  488.38
  6355.4   488.2  6422.4  469.05  6506.3  473.96    6646   476.5  7154.5  481.79
  7249.5  477.57  7393.6   480.2  7639.2  484.27  7791.2  482.27    7921  485.82
#Mann= 5 ,-1 , 0
  3452.4     .05       0  4999.2     .03       0    5018     .05       0
  7393.6    .075       0  7791.2     .05       0
Bank Sta=4999.2,5018
XS Rating Curve= 0 ,0
Exp/Cntr=0.3,0.1

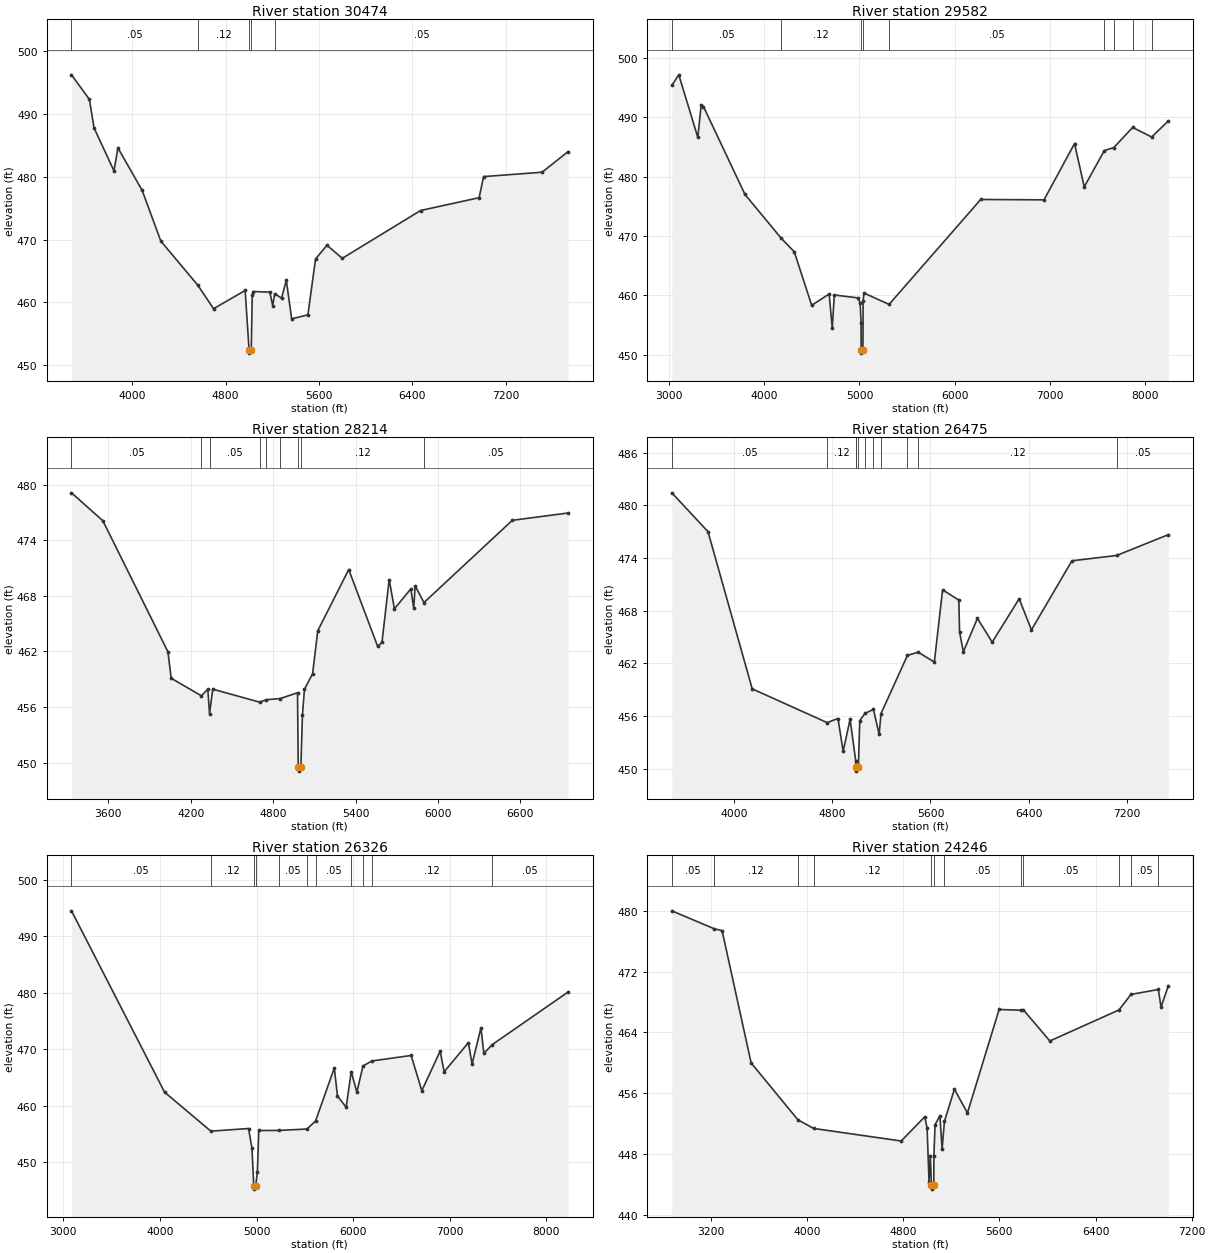
Type RM Length L Ch R = 1 ,30474   ,892,892,892
BEGIN DESCRIPTION:
Bachelor Creek 40.0
END DESCRIPTION:
XS GIS Cut Line= 4
      2647598.69      6948000.98      2646084.52      6947866.94
      2645774.07      6947834.98      2643644.14      6948990.55
#Sta/Elev= 30
  3479.9  496.18  3633.2  492.28  3673.3  487.74    3844  480.92  3877.9  484.56
    4085  477.83  4245.6  469.75  4563.4  462.72  4697.3     459  4968.4   461.9
    5002  452.44    5004  451.94  5020.8  452.44  5028.7   461.2  5038.7  461.73
  5179.5  461.64  5204.5  459.48  5221.4  461.39    5280  460.68  5321.3  463.51
  5366.8  457.39    5506  458.02  5571.6   466.9  5669.5  469.09  5800.7  467.01
  6471.8  474.61  6973.7  476.65  7011.8     480  7513.7   480.7  7735.3  483.97
#Mann= 5 ,-1 , 0
  3479.9     .05       0  4563.4     .12       0    5002     .07       0
  5020.8     .12       0  5221.4     .05       0
Bank Sta=5002,5020.8
XS Rating Curve= 0 ,0
Exp/Cntr=0.3,0.1

Type RM Length L Ch R = 1 ,29582   ,1368,1368,1368
BEGIN DESCRIPTION:
Bachelor Creek 39.0
END DESCRIPTION:
XS GIS Cut Line= 3
      2647687.18      6947974.92       2645872.6      6947209.28
      2642645.59      6946902.03
#Sta/Elev= 30
  3030.5  495.42  3103.6  497.19  3303.1  486.64  3338.8  492.14  3362.5  491.84
  3798.2  477.01  4176.5  469.66  4315.9  467.32  4498.2  458.31  4681.5  460.21
  4714.1  454.48  4735.8  460.05  4981.4  459.56  5006.6  458.77  5016.7  455.39
  5017.3  450.74  5019.3  450.24  5036.1  450.74  5038.2  459.02  5046.8  460.38
  5310.5  458.46  6272.3  476.16    6937   476.1  7256.8  485.59  7358.9  478.29
  7569.8  484.41  7669.1  484.92  7867.6  488.32    8066   486.7  8241.6  489.41
#Mann= 9 ,-1 , 0
  3030.5     .05       0  4176.5     .12       0  5017.3     .07       0
  5036.1     .12       0  5310.5     .05       0  7569.8     .12       0
  7669.1     .05       0  7867.6     .12       0    8066     .05       0
Bank Sta=5017.3,5036.1
XS Rating Curve= 0 ,0
Exp/Cntr=0.3,0.1

Type RM Length L Ch R = 1 ,28214   ,1739,1739,1739
BEGIN DESCRIPTION:
Bachelor Creek 37.0
END DESCRIPTION:
XS GIS Cut Line= 3
      2647536.79      6947196.43      2646136.76      6946246.42
      2644306.17      6945662.45
#Sta/Elev= 30
  3332.7  479.15  3561.1  476.13  4034.6  461.97  4058.2  459.11  4278.3  457.21
  4324.6  457.92  4337.3  455.28  4360.6  457.93    4703  456.52  4749.2  456.79
  4850.3  456.91  4977.6  457.54    4983  449.57    4985  449.07  5002.1  449.57
  5013.5  455.17  5028.3  457.92  5087.5  459.61  5124.9  464.24  5350.3  470.86
  5560.7  462.56  5592.2  462.98  5644.7  469.78  5682.8  466.61  5802.2  468.77
  5823.2  466.69  5833.7   469.1  5897.9  467.29  6540.9  476.18  6946.1  476.97
#Mann= 9 ,-1 , 0
  3332.7     .05       0  4278.3     .12       0  4337.3     .05       0
    4703     .12       0  4749.2     .05       0  4850.3     .12       0
    4983     .07       0  5002.1     .12       0  5897.9     .05       0
Bank Sta=4983,5002.1
XS Rating Curve= 0 ,0
Exp/Cntr=0.3,0.1

Type RM Length L Ch R = 1 ,26475   ,149,149,149
BEGIN DESCRIPTION:
Mapping XS dd9ad7f2
END DESCRIPTION:
XS GIS Cut Line= 6
      2647930.26      6946704.09      2646888.62      6945627.72
      2646706.32      6945501.85      2646476.11      6945216.59
      2646174.46      6945372.84      2644550.08      6945289.22
#Sta/Elev= 30
    3489  481.44  3784.2  477.01  4144.9  459.09  4756.9  455.24  4844.9  455.71
  4887.3  451.97  4943.9  455.63  4989.4   450.9  4992.2  450.21  4994.2  449.71
  5011.4  450.21  5022.8  455.48  5065.1  456.29  5134.4  456.75  5180.9   453.9
  5196.4  456.28  5411.7   462.9    5499  463.27  5631.4  462.15  5698.7  470.38
  5831.5  469.21  5837.2  465.59  5867.9  463.31  5983.2  467.13  6103.4  464.41
  6323.7  469.36  6423.8  465.81  6754.2  473.69  7119.8   474.3  7541.2  476.67
#Mann= 11 ,-1 , 0
    3489     .05       0  4756.9     .12       0  4989.4     .05       0
  4992.2     .03       0  5011.4     .05       0  5065.1     .12       0
  5134.4     .05       0  5196.4     .12       0  5411.7     .05       0
    5499     .12       0  7119.8     .05       0
Bank Sta=4992.2,5011.4
XS Rating Curve= 0 ,0
Exp/Cntr=0.3,0.1

Type RM Length L Ch R = 1 ,26326   ,2080,2080,2080
BEGIN DESCRIPTION:
Bachelor Creek 35.0
END DESCRIPTION:
XS GIS Cut Line= 4
      2648307.88      6946882.05        2646976.        6945511.
      2646479.36      6944950.21      2644008.42      6945176.17
#Sta/Elev= 30
  3083.6  494.52  4047.3  462.43  4526.9  455.52  4917.2  455.99  4952.7  452.47
  4971.3  445.76  4973.3  445.26  4990.7  445.76  5008.8  448.31  5023.1  455.64
  5231.2  455.65    5522   455.9  5611.2  457.32  5805.3  466.71  5837.9  461.74
  5928.3  459.76  5980.4  466.06  6038.7  462.42    6102  467.04  6192.7  467.94
  6601.1  468.92  6711.5  462.68  6901.6  469.69  6942.5  466.02  7193.5  471.18
    7232   467.4  7324.1  473.81  7354.2  469.28  7441.7  470.85  8225.4  480.14
#Mann= 11 ,-1 , 0
  3083.6     .05       0  4526.9     .12       0  4971.3     .07       0
  4990.7     .12       0  5231.2     .05       0    5522     .12       0
  5611.2     .05       0  5980.4     .12       0    6102     .05       0
  6192.7     .12       0  7441.7     .05       0
Bank Sta=4971.3,4990.7
XS Rating Curve= 0 ,0
Exp/Cntr=0.3,0.1

Type RM Length L Ch R = 1 ,24246   ,1176,1176,1176
BEGIN DESCRIPTION:
Bachelor Creek 33.0
END DESCRIPTION:
XS GIS Cut Line= 3
      2649361.28       6943904.2      2647251.92      6944138.14
      2645255.39       6943947.6
#Sta/Elev= 30
  2877.7     480  3229.9  477.64  3295.5  477.39    3537  459.97  3925.7  452.48
  4056.7  451.34  4784.6  449.69  4980.7  452.88    5000  451.39    5016   444.3
  5026.8  447.72  5036.4  443.85  5038.4  443.35  5055.8  443.85  5056.2  447.66
  5066.2  451.85  5106.4  452.99  5124.6  448.64  5144.1  452.28  5226.9  456.51
  5335.4  453.38  5598.6  467.01  5783.3  466.91  5799.7  466.97  6020.5  462.86
  6595.4  466.95  6694.6  468.99  6922.6  469.64  6944.7  467.32  7005.6  470.13
#Mann= 12 ,-1 , 0
  2877.7     .05       0  3229.9     .12       0  3925.7     .05       0
  4056.7     .12       0  5036.4     .07       0  5055.8     .12       0
  5144.1     .05       0  5783.3     .12       0  5799.7     .05       0
  6595.4     .12       0  6694.6     .05       0  6922.6     .12       0
Bank Sta=5036.4,5055.8
XS Rating Curve= 0 ,0
Exp/Cntr=0.3,0.1

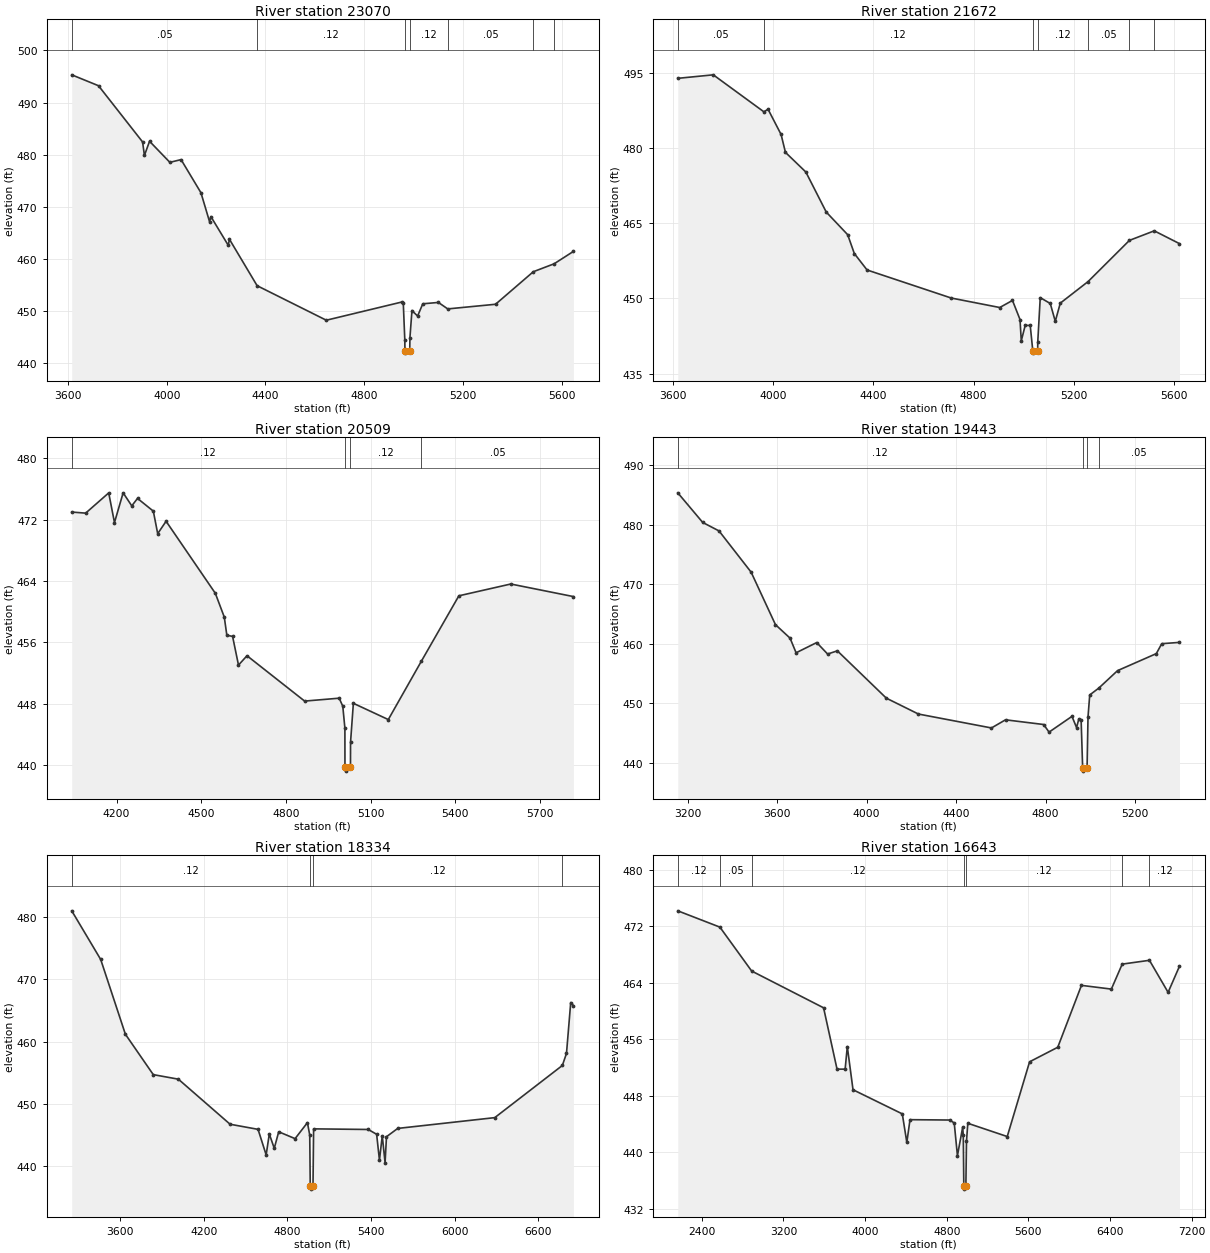
Type RM Length L Ch R = 1 ,23070   ,1398,1398,1398
BEGIN DESCRIPTION:
Bachelor Creek 32.0
END DESCRIPTION:
XS GIS Cut Line= 3
      2648650.79      6942893.34      2647306.38      6943248.25
      2646696.19       6943448.9
#Sta/Elev= 30
  3615.3  495.32  3723.7  493.23  3902.3  482.45  3909.8  479.86  3930.5  482.58
  4012.8  478.54  4058.3  479.06  4138.8  472.71  4173.9  467.12  4179.1  468.13
  4249.3  462.64  4254.4  463.77  4366.4  454.88  4646.8  448.26  4953.5  451.76
  4958.7  451.53  4964.8  444.51  4965.4  442.45  4967.4  441.95  4984.9  442.45
  4985.5  444.85  4993.8  450.12  5016.7  449.06  5037.7  451.41  5100.9  451.67
  5138.8  450.43  5332.5  451.32  5485.5  457.56  5569.8  459.08  5648.1  461.46
#Mann= 7 ,-1 , 0
  3615.3     .05       0  4366.4     .12       0  4965.4     .07       0
  4984.9     .12       0  5138.8     .05       0  5485.5     .12       0
  5569.8     .05       0
Bank Sta=4965.4,4984.9
XS Rating Curve= 0 ,0
Exp/Cntr=0.3,0.1

Type RM Length L Ch R = 1 ,21672   ,1163,1163,1163
BEGIN DESCRIPTION:
Bachelor Creek 30.0
END DESCRIPTION:
XS GIS Cut Line= 3
      2648767.99      6942632.93      2647411.88      6942374.06
      2646790.44      6942365.57
#Sta/Elev= 30
  3619.4  493.84    3761  494.54    3963  487.17  3979.6  487.68  4031.7  482.65
    4049  479.09  4130.5  475.17  4211.9  467.19  4297.4  462.68  4323.9  458.93
  4374.8  455.65  4710.7  450.06  4904.2  448.17  4955.1  449.58  4985.1  445.78
  4990.2  441.53  5005.9  444.61  5025.9  444.59  5036.1  439.58  5038.1  439.08
  5055.7  439.58  5055.9  441.23  5065.9  450.14  5105.9  448.97  5125.9  445.42
  5145.9  449.04  5256.8  453.34  5421.9  461.55  5520.9  463.45  5621.5   460.9
#Mann= 7 ,-1 , 0
  3619.4     .05       0    3963     .12       0  5036.1     .07       0
  5055.7     .12       0  5256.8     .05       0  5421.9     .12       0
  5520.9     .05       0
Bank Sta=5036.1,5055.7
XS Rating Curve= 0 ,0
Exp/Cntr=0.3,0.1

Type RM Length L Ch R = 1 ,20509   ,1066,1066,1066
BEGIN DESCRIPTION:
Bachelor Creek 28.0
END DESCRIPTION:
XS GIS Cut Line= 4
      2648364.32      6941604.28        2647426.        6941411.
      2647078.15      6941400.29      2646727.59      6941716.14
#Sta/Elev= 30
  4041.1  472.99  4090.4  472.85  4172.1  475.49  4192.5  471.62  4223.2   475.5
  4253.8   473.8  4274.2  474.77  4330.2  473.11  4345.7  470.17  4375.4  471.79
  4549.9  462.39  4581.7  459.28  4590.7  456.92  4611.1  456.76    4632  453.02
  4662.2  454.24  4866.4  448.32  4988.9   448.7  5001.6  447.65  5009.1  444.79
  5009.3  439.68  5011.3  439.18  5028.9  439.68  5029.1  442.94  5039.1  448.03
  5162.9  445.91  5279.7   453.5    5413  462.06  5596.9   463.6    5819  461.96
#Mann= 4 ,-1 , 0
  4041.1     .12       0  5009.3     .07       0  5028.9     .12       0
  5279.7     .05       0
Bank Sta=5009.3,5028.9
XS Rating Curve= 0 ,0
Exp/Cntr=0.3,0.1

Type RM Length L Ch R = 1 ,19443   ,1109,1109,1109
BEGIN DESCRIPTION:
Bachelor Creek 26.0
END DESCRIPTION:
XS GIS Cut Line= 4
      2648825.97      6941110.99        2647026.        6940711.
      2646894.63      6940764.37      2646806.14      6941005.36
#Sta/Elev= 30
  3155.7  485.38  3267.1   480.4  3340.1  478.97  3483.5  472.04  3592.3  463.21
  3657.6  460.94  3684.5  458.48  3776.7   460.2  3825.4  458.27  3868.9  458.81
  4087.9  450.85  4231.3  448.18  4557.8  445.84  4620.6  447.21  4790.9  446.42
  4815.2  445.14  4917.6  447.79  4938.1  445.91  4948.4  447.36  4958.6  447.11
  4965.4  439.08  4967.4  438.58  4985.1  439.08  4989.3   447.7    4997  451.39
  5037.1  452.53  5121.4  455.48  5294.6  458.34  5318.9  460.01  5398.1  460.23
#Mann= 4 ,-1 , 0
  3155.7     .12       0  4965.4     .07       0  4985.1     .12       0
  5037.1     .05       0
Bank Sta=4965.4,4985.1
XS Rating Curve= 0 ,0
Exp/Cntr=0.3,0.1

Type RM Length L Ch R = 1 ,18334   ,1691,1691,1691
BEGIN DESCRIPTION:
Bachelor Creek 25.0
END DESCRIPTION:
XS GIS Cut Line= 3
      2648626.04      6940911.02        2647076.        6940111.
      2645236.64       6940364.7
#Sta/Elev= 30
  3251.4  480.97  3459.1  473.17  3636.4  461.17  3836.6  454.69  4016.7  453.96
    4388  446.73  4588.7  445.91  4646.9  441.81  4669.4  445.17  4705.1  442.87
  4736.9  445.52  4854.5  444.42  4943.2  446.99  4959.7  444.98  4963.4  436.82
  4965.4  436.32  4983.1  436.82  4987.5  445.99  5379.3  445.89  5439.9  445.12
  5460.1  440.97  5480.3  444.88  5500.5  440.56  5510.6  444.73  5591.3  446.06
  6287.8  447.79    6773  456.16  6802.7   458.1    6833  466.26  6852.5  465.77
#Mann= 4 ,-1 , 0
  3251.4     .12       0  4963.4     .07       0  4983.1     .12       0
    6773     .05       0
Bank Sta=4963.4,4983.1
XS Rating Curve= 0 ,0
Exp/Cntr=0.3,0.1

Type RM Length L Ch R = 1 ,16643   ,1792,1792,1792
BEGIN DESCRIPTION:
Bachelor Creek 24.0
END DESCRIPTION:
XS GIS Cut Line= 3
      2649317.91      6940180.24        2646626.        6939261.
      2644575.22      6938969.73
#Sta/Elev= 30
  2164.3  474.22  2576.9  471.91  2888.2  465.69  3592.9  460.48  3724.8  451.79
  3804.2  451.79  3825.3  454.99  3881.4  448.87  4364.3  445.45  4408.6  441.41
  4439.9  444.63  4829.2  444.58  4873.2  444.16  4904.5  439.53    4956  443.57
  4961.9  442.39    4967  435.29  4969.1  434.79  4987.2  435.29  4993.2  441.55
  5006.2  444.12  5392.6  442.24  5611.6  452.83  5887.6  454.89  6119.9  463.66
  6412.8  463.13  6519.2  466.67    6786  467.21  6968.9  462.67  7080.2  466.37
#Mann= 7 ,-1 , 0
  2164.3     .12       0  2576.9     .05       0  2888.2     .12       0
    4967     .07       0  4987.2     .12       0  6519.2     .05       0
    6786     .12       0
Bank Sta=4967,4987.2
XS Rating Curve= 0 ,0
Exp/Cntr=0.3,0.1