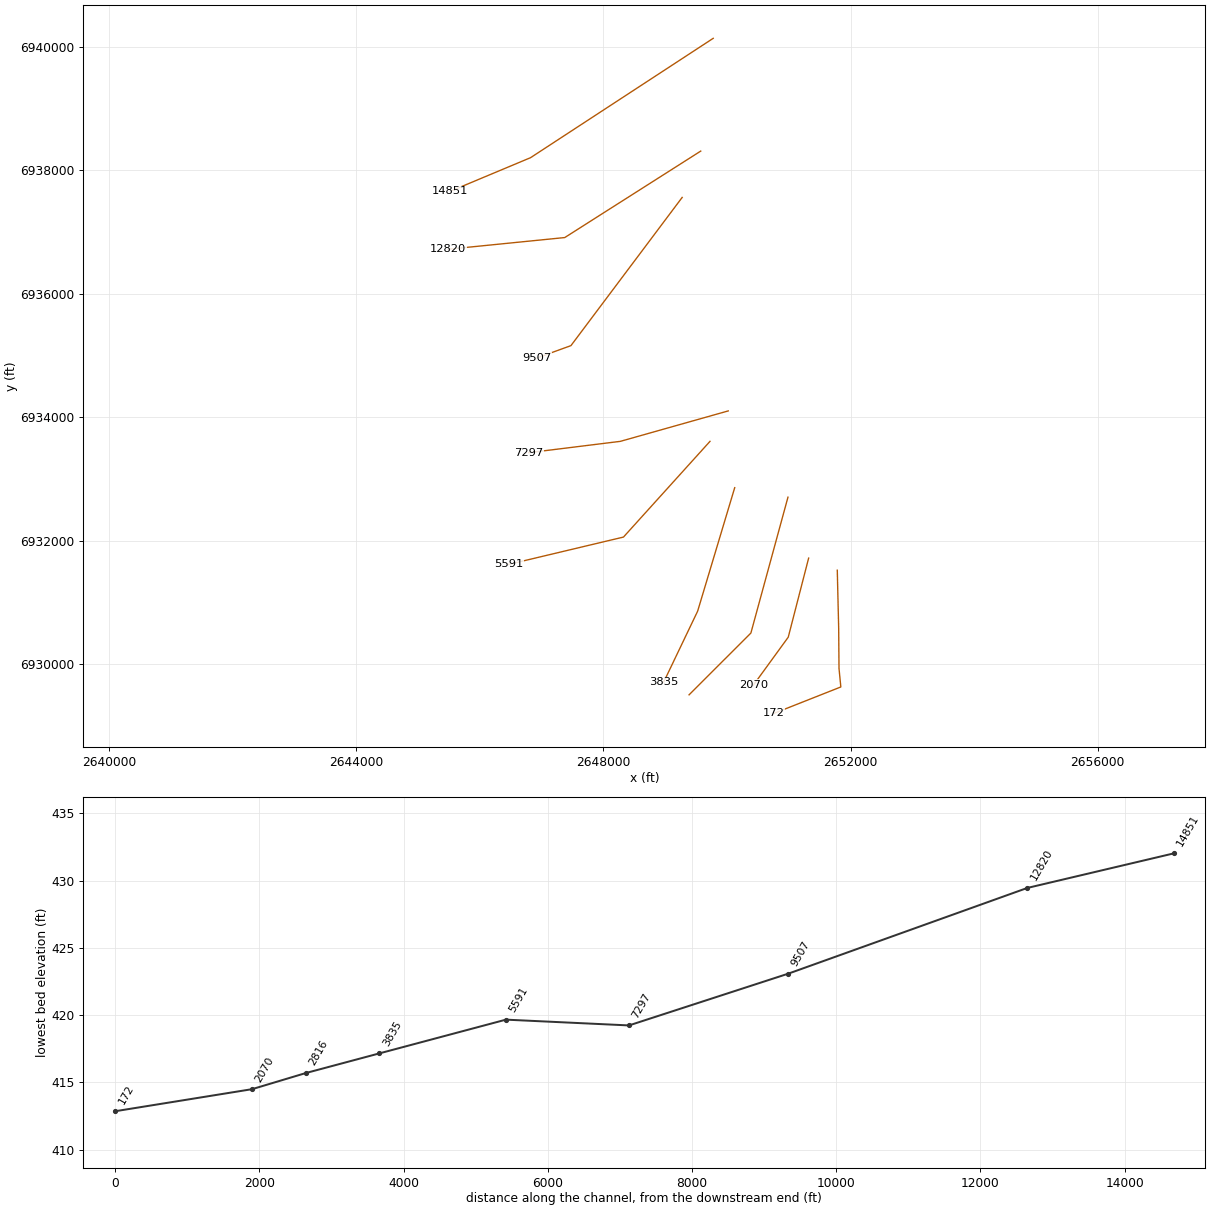
HEC-RAS study Bachelor Creek.prj: Bachelor Creek Base Level Engineering

--- Bachelor Creek.g01 (geometry) --- (continued)

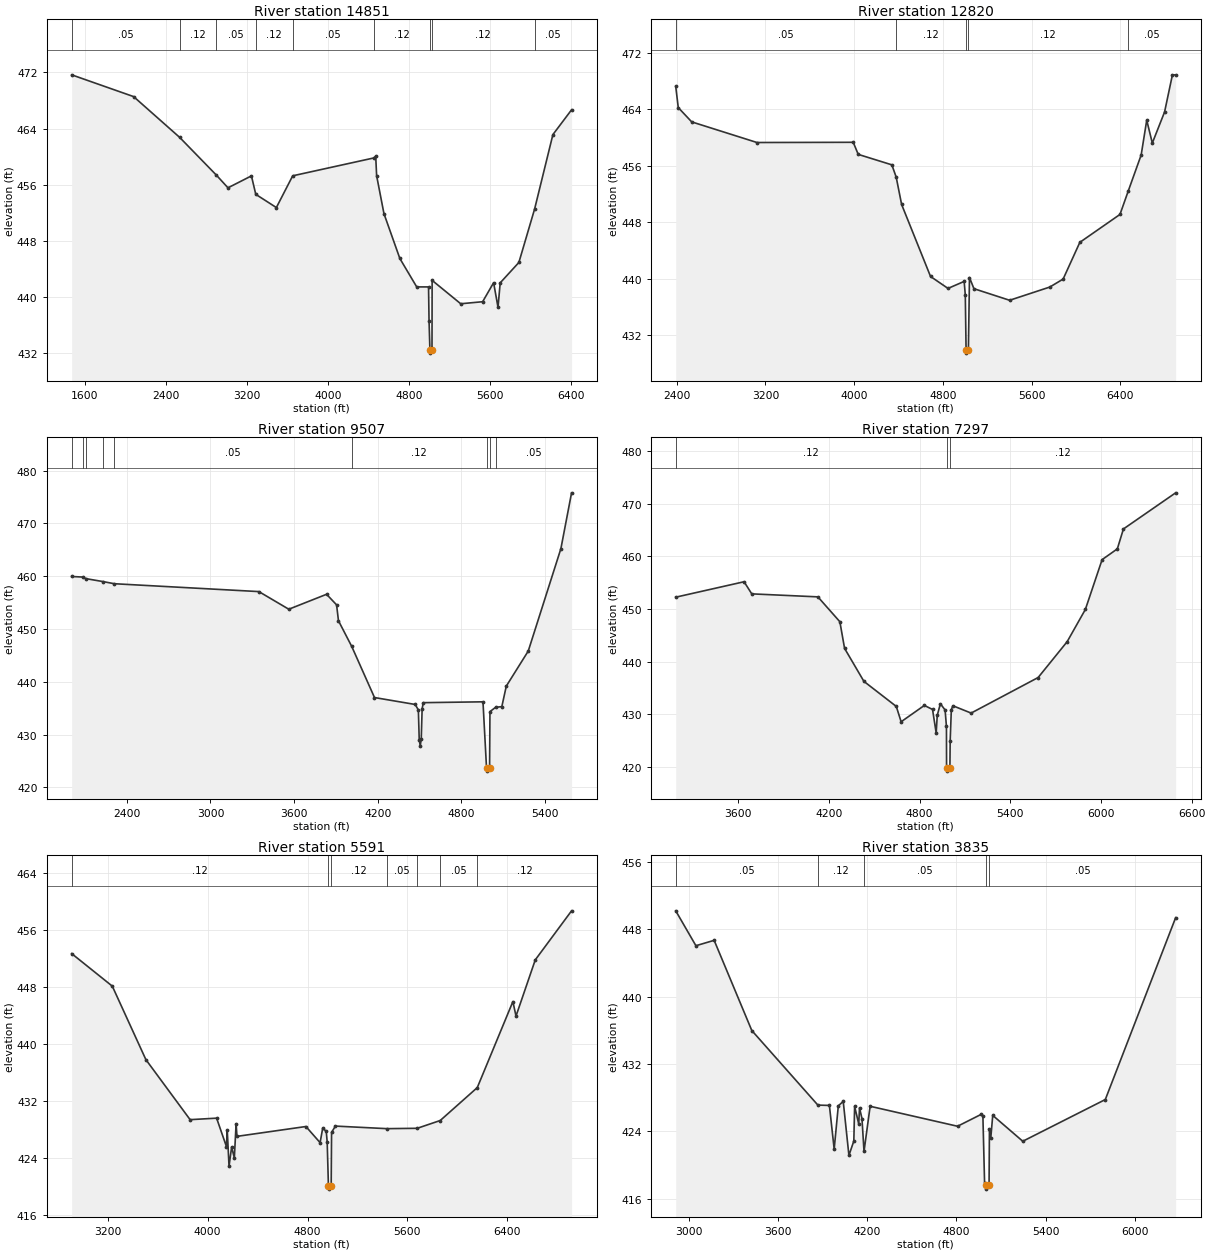
Type RM Length L Ch R = 1 ,14851   ,2031,2031,2031
BEGIN DESCRIPTION:
Bachelor Creek 22.0
END DESCRIPTION:
XS GIS Cut Line= 3
      2649777.95      6940136.83      2646822.86      6938204.47
      2645526.03      6937661.01
#Sta/Elev= 30
  1469.2  471.66  2080.9  468.56  2535.2  462.76  2898.9  457.37  3012.9  455.57
  3244.5  457.27  3287.5  454.64  3490.8  452.76  3652.1  457.28  4452.2  459.82
  4471.9  460.07    4481  457.29  4553.4  451.89  4710.2  445.51  4876.8  441.46
  4993.7  441.46  4998.6  436.65  5007.1  432.53  5009.1  432.03  5027.7  432.53
  5029.1  442.39  5311.5  439.06  5527.9  439.35  5636.3  442.06  5679.7  438.56
  5701.4  442.04  5885.7  444.94  6041.5  452.57  6221.8  463.15  6406.1  466.68
#Mann= 9 ,-1 , 0
  1469.2     .05       0  2535.2     .12       0  2898.9     .05       0
  3287.5     .12       0  3652.1     .05       0  4452.2     .12       0
  5007.1     .07       0  5027.7     .12       0  6041.5     .05       0
Bank Sta=5007.1,5027.7
XS Rating Curve= 0 ,0
Exp/Cntr=0.3,0.1

Type RM Length L Ch R = 1 ,12820   ,3313,3313,3313
BEGIN DESCRIPTION:
Bachelor Creek 19.0
END DESCRIPTION:
XS GIS Cut Line= 3
      2649575.98      6938310.99        2647376.        6936911.
      2645486.74      6936721.47
#Sta/Elev= 30
    2392   467.2  2414.8  464.21  2535.9  462.19  3124.3  459.27  3992.1   459.3
    4037  457.59  4340.1  456.11  4379.3  454.37  4428.2   450.5  4688.9  440.31
  4846.4  438.62    4992  439.61  5002.2  437.69  5009.3  429.96  5011.4  429.46
  5030.2  429.96  5039.9  440.16  5080.1  438.58  5401.7  436.94  5763.5  438.81
  5884.1  439.94  6034.8  445.14  6396.6  449.09  6471.1   452.4  6587.6   457.5
  6637.8  462.43  6688.1  459.19  6798.6  463.59    6869  468.82  6898.4  468.85
#Mann= 5 ,-1 , 0
    2392     .05       0  4379.3     .12       0  5009.3     .07       0
  5030.2     .12       0  6471.1     .05       0
Bank Sta=5009.3,5030.2
XS Rating Curve= 0 ,0
Exp/Cntr=0.3,0.1

Type RM Length L Ch R = 1 ,9507    ,2210,2210,2210
BEGIN DESCRIPTION:
Bachelor Creek 16.0
END DESCRIPTION:
XS GIS Cut Line= 3
      2649276.02      6937561.02        2647476.        6935161.
      2646925.96      6934960.99
#Sta/Elev= 30
  2004.6  459.96  2086.6  459.85  2105.7  459.56    2231  458.99  2310.7  458.59
  3347.3   457.1  3561.9  453.76  3832.8  456.59  3904.6  454.59  3918.2  451.57
  4013.5   446.7  4176.5  437.03  4468.2  435.72  4491.1  434.69  4497.3  429.08
  4504.6  427.85  4511.9  429.24  4518.2  434.91  4526.5  436.06  4954.6  436.22
  4980.2  423.59  4982.4  423.09  5001.9  423.59  5004.6  434.36    5045  435.18
  5089.8  435.31  5121.7  439.19  5279.3  445.84  5513.4  465.24  5589.9  475.81
#Mann= 9 ,-1 , 0
  2004.6     .05       0  2086.6     .12       0  2105.7     .05       0
    2231     .12       0  2310.7     .05       0  4013.5     .12       0
  4980.2     .07       0  5001.9     .12       0    5045     .05       0
Bank Sta=4980.2,5001.9
XS Rating Curve= 0 ,0
Exp/Cntr=0.3,0.1

Type RM Length L Ch R = 1 ,7297    ,1706,1706,1706
BEGIN DESCRIPTION:
Bachelor Creek 12.0
END DESCRIPTION:
XS GIS Cut Line= 3
      2650021.05      6934103.86        2648276.        6933611.
      2646793.16       6933427.2
#Sta/Elev= 30
  3186.6  452.26  3638.7  455.19  3689.6  452.89  4127.1  452.32  4272.5   447.6
  4303.7  442.54  4431.6  436.28  4645.9  431.52  4677.8  428.61  4831.4  431.71
  4885.6  430.95  4909.8  426.48  4916.8  429.83  4937.6  432.03  4968.7  430.85
  4977.7  427.72  4978.5  419.74  4980.7  419.24  5000.5  419.74  5002.4  425.03
    5010  430.91  5020.1  431.65    5141  430.26  5584.4  437.01  5776.5  443.82
  5896.7  449.93  6007.6  459.39  6108.3  461.43  6148.6  465.21  6494.1  472.07
#Mann= 3 ,-1 , 0
  3186.6     .12       0  4978.5     .07       0  5000.5     .12       0
Bank Sta=4978.5,5000.5
XS Rating Curve= 0 ,0
Exp/Cntr=0.3,0.1

Type RM Length L Ch R = 1 ,5591    ,1756,1756,1756
BEGIN DESCRIPTION:
Bachelor Creek 9.0
END DESCRIPTION:
XS GIS Cut Line= 3
      2649725.97      6933610.97        2648326.        6932061.
      2646463.23      6931617.29
#Sta/Elev= 30
  2911.1  452.66  3236.5   448.1  3505.5  437.81  3859.7   429.4    4072  429.61
  4150.4  425.64  4157.2   427.9  4171.4  422.88  4192.3  425.58  4213.9  424.04
  4228.1  428.84  4234.9  427.06  4787.1  428.44  4900.7  426.18  4921.6  428.21
    4950  427.76  4957.5  426.27  4967.4  420.17  4969.6  419.67  4989.5  420.17
  4992.6  427.62  5023.4   428.5  5435.9  428.14  5678.5  428.19  5862.7  429.28
  6159.5  433.89  6444.7  445.94  6469.7  443.91  6623.9  451.78  6914.6  458.65
#Mann= 7 ,-1 , 0
  2911.1     .12       0  4967.4     .07       0  4989.5     .12       0
  5435.9     .05       0  5678.5     .12       0  5862.7     .05       0
  6159.5     .12       0
Bank Sta=4967.4,4989.5
XS Rating Curve= 0 ,0
Exp/Cntr=0.3,0.1

Type RM Length L Ch R = 1 ,3835    ,1019,1019,1019
BEGIN DESCRIPTION:
Bachelor Creek 6.0
END DESCRIPTION:
XS GIS Cut Line= 3
        2650126.      6932861.01        2649526.        6930861.
      2648976.01      6929711.02
#Sta/Elev= 30
  2912.2  450.18  3047.9  446.04  3170.6  446.68  3423.8  435.98  3868.4  427.13
  3945.8  427.09    3978  421.91  4005.8  427.04  4038.9  427.57  4077.2  421.16
  4110.2  422.87  4115.5  426.98  4143.3  424.89  4148.5   426.8    4165  425.53
  4178.7  421.63  4219.9  426.99    4808  424.62    4969  426.05  4978.5  425.78
  4989.8  417.86  4997.8  417.66    5000  417.16  5019.9  417.66  5022.4  424.29
  5031.5  423.23  5044.6  425.91  5246.7  422.84  5801.9  427.79    6275  449.37
#Mann= 5 ,-1 , 0
  2912.2     .05       0  3868.4     .12       0  4178.7     .05       0
  4997.8     .04       0  5019.9     .05       0
Bank Sta=4997.8,5019.9
XS Rating Curve= 0 ,0
Exp/Cntr=0.3,0.1

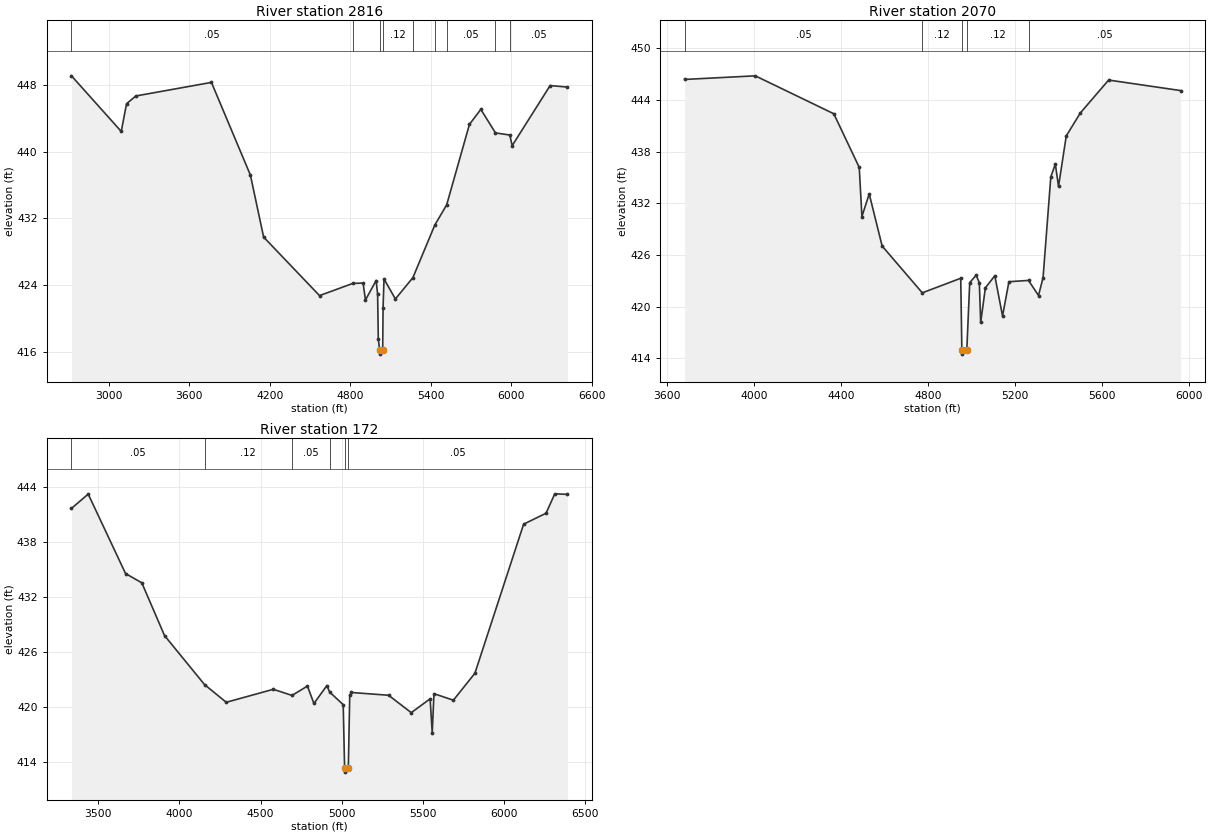
Type RM Length L Ch R = 1 ,2816    ,746,746,746
BEGIN DESCRIPTION:
Bachelor Creek 5.0
END DESCRIPTION:
XS GIS Cut Line= 3
      2650987.64      6932706.87      2650387.63      6930506.85
      2649387.62      6929506.84
#Sta/Elev= 30
  2723.5  449.13  3094.2  442.45  3133.9  445.78    3203  446.71  3766.1  448.34
  4056.3  437.21  4154.9  429.76  4571.2  422.73  4818.6  424.19  4895.9  424.24
  4913.3   422.2  4992.7  424.54  5003.9  422.92  5009.2  417.51    5019   416.2
  5021.3   415.7  5041.8   416.2  5044.5  421.23  5051.6  424.72  5136.4  422.33
  5266.9  424.89  5430.4  431.22  5518.3  433.63    5688   443.3  5772.8   445.1
    5882  442.27  5988.7  442.02  6006.2  440.74    6289  447.96  6418.1  447.78
#Mann= 9 ,-1 , 0
  2723.5     .05       0  4818.6     .12       0    5019     .07       0
  5041.8     .12       0  5266.9     .05       0  5430.4     .12       0
  5518.3     .05       0    5882     .12       0  5988.7     .05       0
Bank Sta=5019,5041.8
XS Rating Curve= 0 ,0
Exp/Cntr=0.3,0.1

Type RM Length L Ch R = 1 ,2070    ,1898,1898,1898
BEGIN DESCRIPTION:
Mapping XS c4b2fa72
END DESCRIPTION:
XS GIS Cut Line= 3
      2651322.11      6931720.47      2650992.26      6930440.12
      2650429.04      6929664.61
#Sta/Elev= 30
  3681.1  446.36    4006  446.78  4367.1  442.38    4484  436.16  4496.3  430.46
  4529.9  433.08  4589.3  427.04    4774  421.61  4950.7   423.3  4955.8     415
  4958.1   414.5  4978.6     415    4992   422.8  5021.6  423.65  5036.2  422.79
  5042.4  418.17    5064  422.19  5107.4  423.59  5142.9  418.92  5172.3   422.9
  5262.3  423.05  5308.3   421.3  5329.2  423.36  5364.8  435.05  5385.6  436.54
  5400.3  433.96  5435.9  439.81  5500.8  442.48  5630.7  446.29  5961.7  445.07
#Mann= 5 ,-1 , 0
  3681.1     .05       0    4774     .12       0  4955.8     .07       0
  4978.6     .12       0  5262.3     .05       0
Bank Sta=4955.8,4978.6
XS Rating Curve= 0 ,0
Exp/Cntr=0.3,0.1

Type RM Length L Ch R = 1 ,172     ,0,0,0
BEGIN DESCRIPTION:
Bachelor Creek 1.0
END DESCRIPTION:
XS GIS Cut Line= 5
      2651785.54      6931524.11      2651808.23      6930578.32
      2651813.44      6929934.22      2651842.96      6929633.87
      2650761.33      6929206.14
#Sta/Elev= 30
  3335.4  441.64  3438.5   443.2  3668.6  434.53  3768.6  433.52  3908.7  427.76
  4155.2  422.41  4288.8  420.48  4578.8   421.9  4693.9  421.23  4788.8  422.25
  4828.8  420.35  4908.8  422.31  4925.6   421.6  5009.2  420.22  5017.7  413.36
    5020  412.86  5040.8  413.36  5049.4  421.24  5059.4  421.55  5288.6  421.25
  5428.4  419.35  5544.6  420.86  5557.5  417.14  5568.2  421.42  5687.9  420.71
  5820.4  423.65  6120.5  439.92  6258.4  441.11  6312.4  443.23  6390.5  443.17
#Mann= 6 ,-1 , 0
  3335.4     .05       0  4155.2     .12       0  4693.9     .05       0
  4925.6     .12       0  5017.7     .07       0  5040.8     .05       0
Bank Sta=5017.7,5040.8
XS Rating Curve= 0 ,0
Exp/Cntr=0.3,0.1

Chan Stop Cuts=-1
Use User Specified Reach Order=0
Composite Channel Slope=5