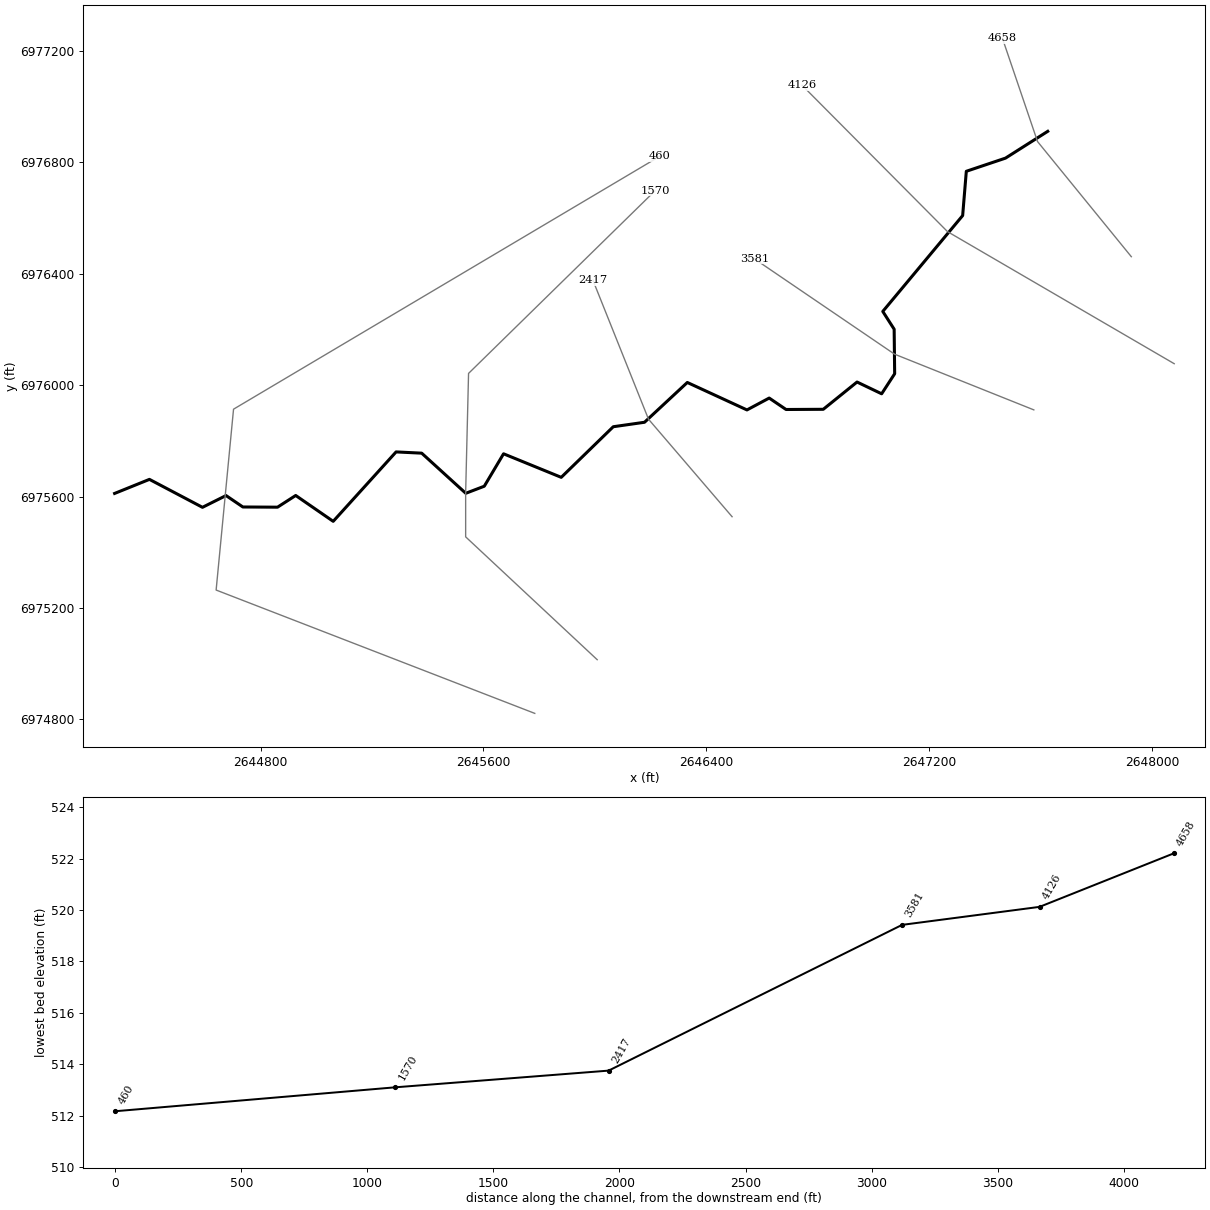
--- Bachelor Creek Trib 1.prj (project) ---

Proj Title=Bachelor Creek Trib 1 Base Level Engineering
Current Plan=p01
Default Exp/Contr=0.3,0.1
English Units
Geom File=g01
Flow File=f01
Plan File=p01
BEGIN DESCRIPTION:
Bachelor Creek Trib 1
END DESCRIPTION:

--- Bachelor Creek Trib 1.p01 (plan) ---

Plan Title=Multiple Run
Short Identifier=Multiple
Geom File=g01
Flow File=f01
Subcritical Flow
K Sum by GR= 0
Std Step Tol= 0.01
Critical Tol= 0.01
Num of Std Step Trials= 20
Max Error Tol= 0.3
Flow Tol Ratio= 0.001
Split Flow NTrial= 30
Split Flow Tol= 0.02
Split Flow Ratio= 0.02
Log Output Level= 0
Friction Slope Method= 1
Unsteady Friction Slope Method= 2
Unsteady Bridges Friction Slope Method= 1
Parabolic Critical Depth
Global Vel Dist=  1 , 1 , 1
Global Log Level= 0
CheckData=True
Encroach Param= -1, 0, 0, 0
BEGIN DESCRIPTION:
Multiple Run
END DESCRIPTION:

--- Bachelor Creek Trib 1.f01 (steady flow) ---

Flow Title=Multiple
Number of Profiles=7
Profile Names=10-year,25-year,50-year,1pct_min,100-year,1pct_plu,500-year
River Rch & RM= Bachelor Creek T,Reach-1,4658
     527     695     828     489     976    1947    1356
Boundary for River Rch & Prof#=Bachelor Creek T,Reach-1,1
Up Type=0
Dn Type=3
Dn Slope=0.005
Boundary for River Rch & Prof#=Bachelor Creek T,Reach-1,2
Up Type=0
Dn Type=3
Dn Slope=0.005
Boundary for River Rch & Prof#=Bachelor Creek T,Reach-1,3
Up Type=0
Dn Type=3
Dn Slope=0.005
Boundary for River Rch & Prof#=Bachelor Creek T,Reach-1,4
Up Type=0
Dn Type=3
Dn Slope=0.005
Boundary for River Rch & Prof#=Bachelor Creek T,Reach-1,5
Up Type=0
Dn Type=3
Dn Slope=0.005
Boundary for River Rch & Prof#=Bachelor Creek T,Reach-1,6
Up Type=0
Dn Type=3
Dn Slope=0.005
Boundary for River Rch & Prof#=Bachelor Creek T,Reach-1,7
Up Type=0
Dn Type=3
Dn Slope=0.005

--- Bachelor Creek Trib 1.g01 (geometry) ---

Geom Title=Existing Conditions

River Reach=Bachelor Creek T,Reach-1
Reach XY= 30
      2647626.00      6976911.00      2647474.42      6976814.82
      2647333.68      6976767.52      2647320.53      6976608.55
      2647033.79      6976264.42      2647074.61      6976200.57
      2647076.44      6976040.67      2647029.70      6975968.70
      2646941.37      6976010.98      2646820.14      6975913.06
      2646686.44      6975912.37      2646625.99      6975953.41
      2646546.20      6975910.78      2646332.04      6976009.39
      2646178.43      6975866.52      2646066.21      6975850.48
      2645879.42      6975668.79      2645672.33      6975753.31
      2645603.14      6975636.92      2645536.69      6975611.53
      2645378.43      6975755.60      2645286.48      6975760.07
      2645060.76      6975510.84      2644926.10      6975603.67
      2644860.84      6975561.65      2644736.44      6975562.37
      2644675.99      6975603.41      2644591.41      6975561.14
      2644401.01      6975661.48      2644276.00      6975611.00

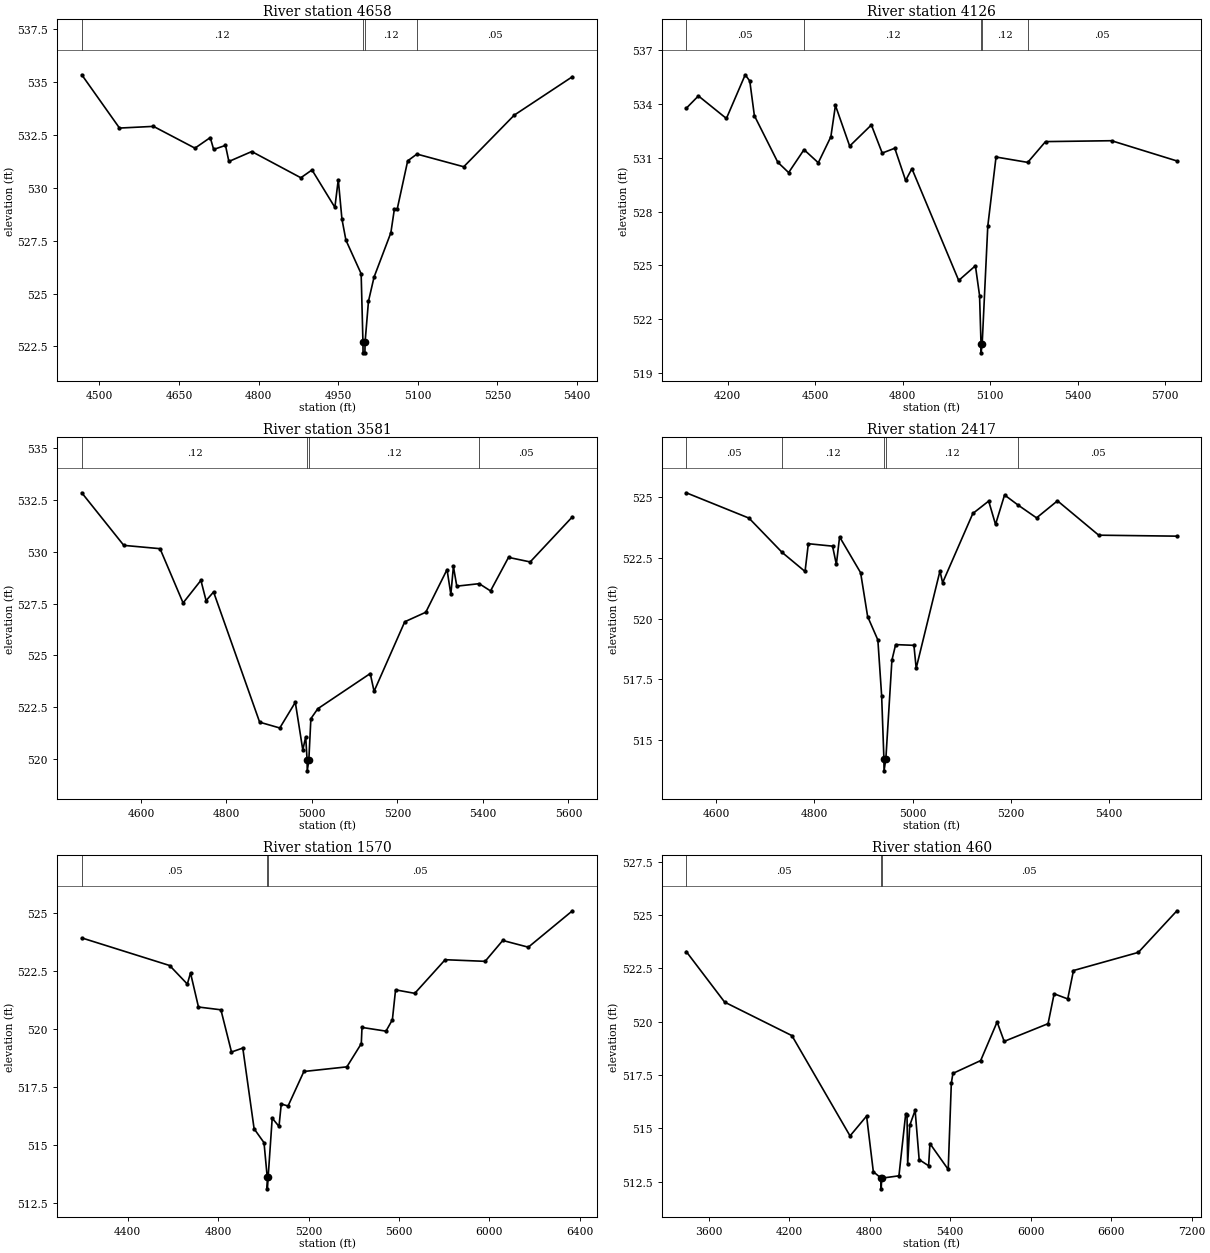
Type RM Length L Ch R = 1,4658,532,532,532
BEGIN DESCRIPTION:
Bachelor Creek Trib 1 5.0
END DESCRIPTION:
XS GIS Cut Line= 3
      2647926.03      6976460.96      2647589.35      6976874.29
      2647463.32      6977244.85
#Sta/Elev= 30
  4466.9  535.35  4538.0  532.83  4602.0  532.91  4680.2  531.88  4709.0  532.38
  4715.4  531.82  4737.7  532.01  4744.1  531.25  4787.2  531.72  4879.7  530.48
  4900.7  530.85  4943.8  529.08  4950.2  530.39  4957.1  528.53  4964.6  527.53
  4993.3  525.94  4996.7  522.70  4996.9  522.20  5000.4  522.20  5000.7  522.70
  5007.1  524.64  5017.6  525.78  5049.3  527.88  5055.8  528.98  5061.1  528.98
  5081.0  531.28  5098.4  531.60  5186.6  531.00  5281.7  533.44  5391.4  535.26
#Mann=4,-1,0
  4466.9    0.12       0  4996.7    0.07       0  5000.7    0.12       0
  5098.4    0.05       0
Bank Sta=4996.7,5000.7
Exp/Cntr=0.3,0.1

Type RM Length L Ch R = 1,4126,545,545,545
BEGIN DESCRIPTION:
Bachelor Creek Trib 1 4.0
END DESCRIPTION:
XS GIS Cut Line= 3
      2648080.07      6976076.75      2647266.12      6976550.95
      2646744.11      6977076.30
#Sta/Elev= 30
  4058.0  533.77  4099.7  534.46  4195.7  533.20  4260.2  535.64  4275.9  535.29
  4291.6  533.36  4371.9  530.76  4409.1  530.18  4461.8  531.46  4510.8  530.73
  4553.9  532.18  4569.6  533.93  4618.4  531.66  4692.8  532.84  4730.0  531.27
  4773.1  531.54  4810.3  529.74  4831.8  530.40  4992.3  524.16  5049.6  524.98
  5063.8  523.32  5068.8  520.62  5069.1  520.12  5072.8  520.62  5092.0  527.19
  5120.3  531.05  5229.0  530.75  5290.0  531.91  5516.3  531.96  5740.6  530.83
#Mann=5,-1,0
  4058.0    0.05       0  4461.8    0.12       0  5068.8    0.07       0
  5072.8    0.12       0  5229.0    0.05       0
Bank Sta=5068.8,5072.8
Exp/Cntr=0.3,0.1

Type RM Length L Ch R = 1,3581,1164,1164,1164
BEGIN DESCRIPTION:
Bachelor Creek Trib 1 3.0
END DESCRIPTION:
XS GIS Cut Line= 3
      2647576.04      6975910.98      2647076.00      6976111.00
      2646572.40      6976453.68
#Sta/Elev= 30
  4461.6  532.85  4559.9  530.31  4644.7  530.15  4698.6  527.53  4740.3  528.62
  4752.4  527.64  4769.9  528.06  4877.7  521.77  4924.8  521.49  4961.1  522.73
  4978.6  520.43  4985.4  521.06  4988.7  519.92  4989.0  519.42  4992.7  519.92
  4997.5  521.94  5013.7  522.42  5136.4  524.12  5145.3  523.26  5217.1  526.62
  5266.3  527.08  5316.0  529.14  5324.9  527.94  5330.9  529.29  5338.8  528.34
  5391.2  528.46  5417.7  528.11  5459.8  529.73  5510.5  529.51  5609.3  531.69
#Mann=4,-1,0
  4461.6    0.12       0  4988.7    0.07       0  4992.7    0.12       0
  5391.2    0.05       0
Bank Sta=4988.7,4992.7
Exp/Cntr=0.3,0.1

Type RM Length L Ch R = 1,2417,847,847,847
BEGIN DESCRIPTION:
Bachelor Creek Trib 1 2.0
END DESCRIPTION:
XS GIS Cut Line= 3
      2646492.77      6975527.44      2646192.75      6975877.46
      2645993.06      6976376.70
#Sta/Elev= 30
  4539.0  525.16  4666.7  524.12  4734.3  522.71  4780.8  521.93  4787.5  523.07
  4836.8  522.97  4844.5  522.22  4851.1  523.35  4893.9  521.88  4908.2  520.08
  4929.0  519.12  4936.7  516.83  4941.3  514.25  4941.6  513.75  4945.3  514.25
  4957.6  518.29  4965.2  518.93  5002.4  518.90  5007.0  517.96  5055.4  521.95
  5060.8  521.47  5122.3  524.31  5154.6  524.82  5168.5  523.86  5186.9  525.07
  5214.1  524.66  5252.0  524.13  5294.6  524.83  5378.5  523.42  5537.7  523.38
#Mann=5,-1,0
  4539.0    0.05       0  4734.3    0.12       0  4941.3    0.07       0
  4945.3    0.12       0  5214.1    0.05       0
Bank Sta=4941.3,4945.3
Exp/Cntr=0.3,0.1

Type RM Length L Ch R = 1,1570,1110,1110,1110
BEGIN DESCRIPTION:
Mapping XS cffd5788
END DESCRIPTION:
XS GIS Cut Line= 5
      2646008.49      6975014.15      2645536.27      6975455.12
      2645536.27      6975614.84      2645546.69      6976041.93
      2646215.70      6976697.07
#Sta/Elev= 30
  4197.4  523.92  4585.9  522.73  4664.1  521.93  4678.2  522.41  4713.4  520.94
  4812.6  520.82  4859.4  519.00  4909.4  519.17  4959.4  515.69  5003.2  515.09
  5017.4  513.60  5017.6  513.10  5021.4  513.60  5039.4  516.15  5069.4  515.79
  5079.4  516.76  5109.4  516.67  5179.4  518.16  5369.5  518.36  5433.3  519.36
  5436.4  520.06  5542.4  519.90  5570.7  520.39  5584.8  521.68  5669.7  521.53
  5804.1  522.98  5980.8  522.91  6058.7  523.81  6171.7  523.52  6366.8  525.09
#Mann=3,-1,0
  4197.4    0.05       0  5017.4    0.03       0  5021.4    0.05       0
Bank Sta=5017.4,5021.4
Exp/Cntr=0.3,0.1

Type RM Length L Ch R = 1,460,0,0,0
BEGIN DESCRIPTION:
Bachelor Creek Trib 1 1.0
END DESCRIPTION:
XS GIS Cut Line= 4
      2645784.39      6974821.40      2644640.44      6975264.15
      2644702.94      6975913.46      2646231.92      6976820.64
#Sta/Elev= 30
  3433.0  523.29  3719.1  520.92  4220.4  519.35  4653.7  514.65  4777.0  515.58
  4827.3  512.97  4885.5  512.67  4885.8  512.17  4889.5  512.67  5018.1  512.78
  5068.4  515.68  5078.2  515.65  5083.2  513.32  5098.5  515.14  5138.7  515.85
  5168.8  513.54  5239.2  513.25  5249.2  514.29  5385.3  513.08  5408.5  517.12
  5420.4  517.58  5627.1  518.18  5749.8  519.99  5802.5  519.08  6129.5  519.91
  6174.7  521.31  6276.0  521.07  6318.9  522.40  6802.2  523.25  7089.8  525.20
#Mann=3,-1,0
  3433.0    0.05       0  4885.5    0.03       0  4889.5    0.05       0
Bank Sta=4885.5,4889.5
Exp/Cntr=0.3,0.1

Chan Stop Cuts=-1