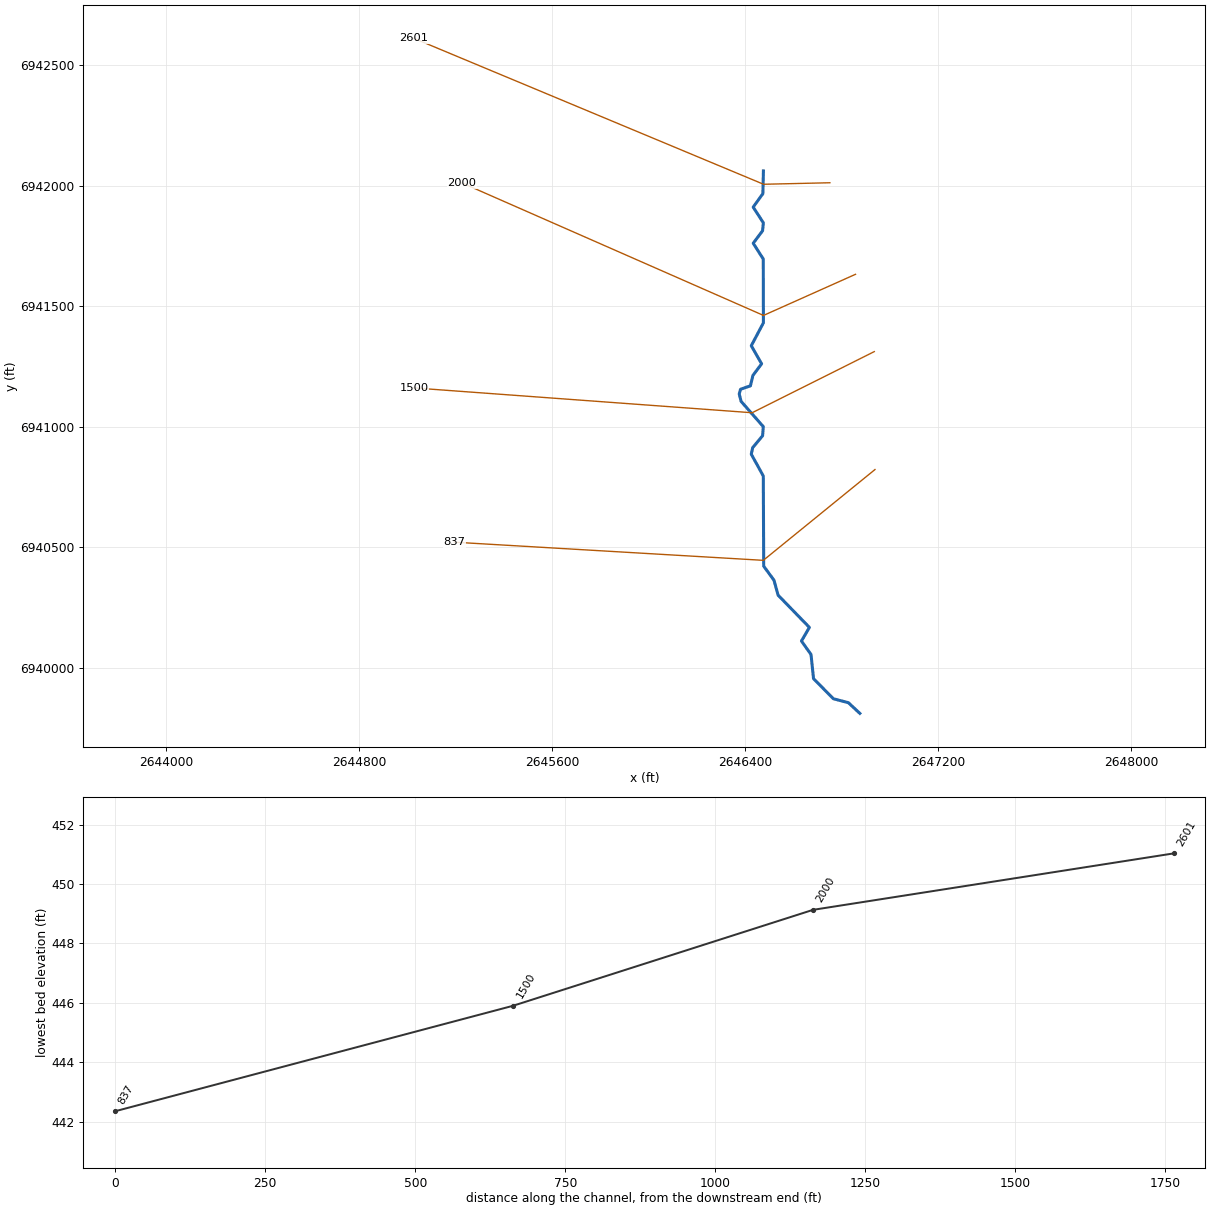
--- Bachelor Creek Trib 11.prj (project) ---

Proj Title=Bachelor Creek Trib 11 Base Level Engineering
Current Plan=p01
Default Exp/Contr=0.3,0.1
English Units
Geom File=g01
Flow File=f01
Plan File=p01
BEGIN DESCRIPTION:
Bachelor Creek Trib 11
END DESCRIPTION:

--- Bachelor Creek Trib 11.p01 (plan) ---

Plan Title=Multiple Run
Short Identifier=Multiple
Geom File=g01
Flow File=f01
Subcritical Flow
K Sum by GR= 0
Std Step Tol= 0.01
Critical Tol= 0.01
Num of Std Step Trials= 20
Max Error Tol= 0.3
Flow Tol Ratio= 0.001
Split Flow NTrial= 30
Split Flow Tol= 0.02
Split Flow Ratio= 0.02
Log Output Level= 0
Friction Slope Method= 1
Unsteady Friction Slope Method= 2
Unsteady Bridges Friction Slope Method= 1
Parabolic Critical Depth
Global Vel Dist=  1 , 1 , 1
Global Log Level= 0
CheckData=True
Encroach Param= -1, 0, 0, 0
BEGIN DESCRIPTION:
Multiple Run
END DESCRIPTION:

--- Bachelor Creek Trib 11.f01 (steady flow) ---

Flow Title=Multiple
Number of Profiles=7
Profile Names=10-year,25-year,50-year,1pct_min,100-year,1pct_plu,500-year
River Rch & RM= Bachelor Creek T,Reach-1,2601
     438     574     681     401     800    1597    1103
Boundary for River Rch & Prof#=Bachelor Creek T,Reach-1,1
Up Type=0
Dn Type=3
Dn Slope=0.005
Boundary for River Rch & Prof#=Bachelor Creek T,Reach-1,2
Up Type=0
Dn Type=3
Dn Slope=0.005
Boundary for River Rch & Prof#=Bachelor Creek T,Reach-1,3
Up Type=0
Dn Type=3
Dn Slope=0.005
Boundary for River Rch & Prof#=Bachelor Creek T,Reach-1,4
Up Type=0
Dn Type=3
Dn Slope=0.005
Boundary for River Rch & Prof#=Bachelor Creek T,Reach-1,5
Up Type=0
Dn Type=3
Dn Slope=0.005
Boundary for River Rch & Prof#=Bachelor Creek T,Reach-1,6
Up Type=0
Dn Type=3
Dn Slope=0.005
Boundary for River Rch & Prof#=Bachelor Creek T,Reach-1,7
Up Type=0
Dn Type=3
Dn Slope=0.005

--- Bachelor Creek Trib 11.g01 (geometry) ---

Geom Title=Existing Conditions

River Reach=Bachelor Creek T,Reach-1
Reach XY= 30
      2646476.00      6942061.00      2646473.66      6941966.77
      2646433.54      6941910.99      2646475.71      6941845.64
      2646472.36      6941812.65      2646433.59      6941761.01
      2646475.34      6941695.84      2646475.92      6941431.03
      2646425.69      6941335.96      2646468.45      6941260.97
      2646432.48      6941212.98      2646422.07      6941169.64
      2646381.11      6941155.23      2646375.56      6941136.01
      2646383.41      6941105.24      2646475.39      6941000.38
      2646472.63      6940962.74      2646431.42      6940913.20
      2646425.61      6940886.00      2646475.46      6940795.79
      2646477.20      6940421.50      2646519.86      6940363.17
      2646536.76      6940301.32      2646666.70      6940167.67
      2646633.80      6940111.10      2646673.45      6940055.11
      2646683.85      6939954.81      2646766.27      6939871.69
      2646828.35      6939855.29      2646876.00      6939811.00

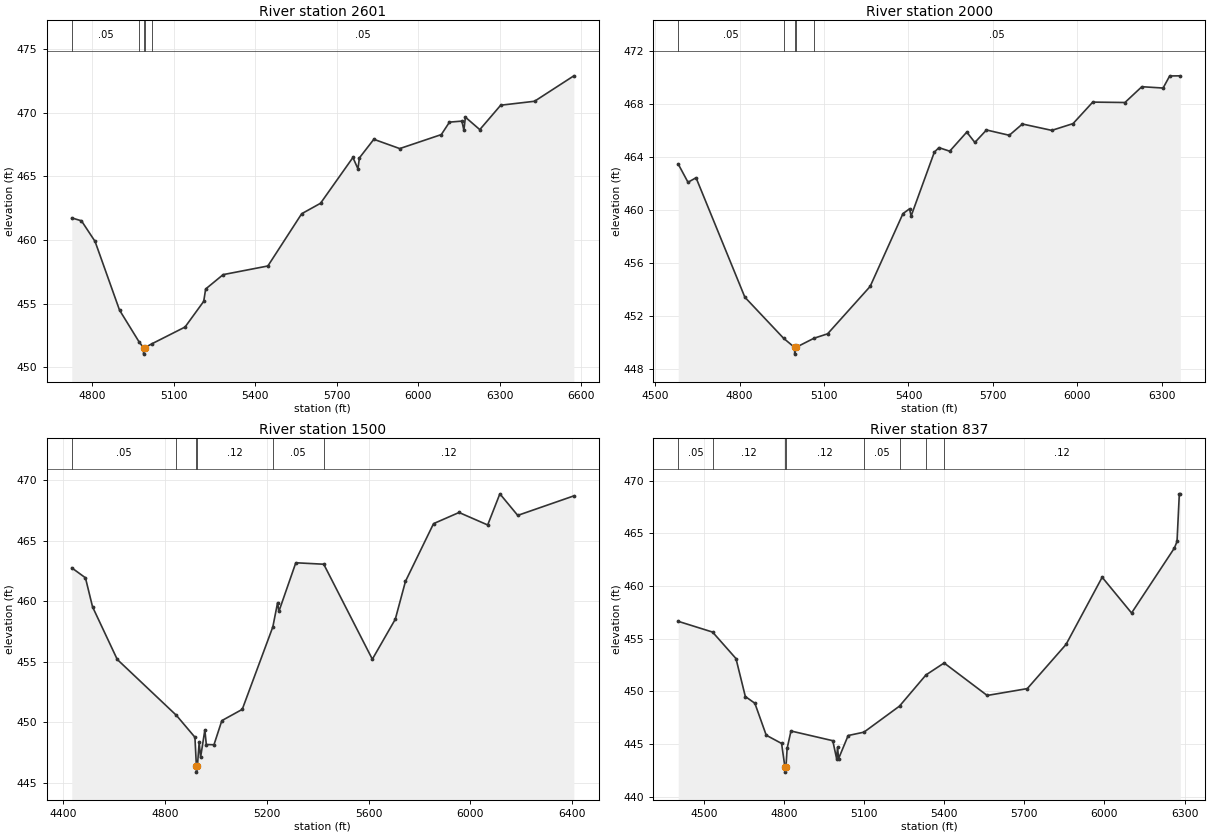
Type RM Length L Ch R = 1,2601,601,601,601
BEGIN DESCRIPTION:
Bachelor Creek Trib 11 5.0
END DESCRIPTION:
XS GIS Cut Line= 3
      2646751.67      6942011.98      2646476.64      6942005.69
      2645025.97      6942611.01
#Sta/Elev= 30
  4724.9  461.74  4760.6  461.51  4810.6  459.89  4900.6  454.49  4972.9  451.98
  4989.0  451.53  4989.2  451.03  4993.0  451.53  5019.4  451.84  5141.6  453.16
  5210.3  455.18  5217.4  456.15  5281.7  457.28  5446.3  457.96  5570.8  462.07
  5640.0  462.89  5759.2  466.49  5777.6  465.60  5783.1  466.46  5836.1  467.92
  5931.4  467.19  6084.3  468.29  6114.4  469.27  6160.1  469.35  6167.4  468.63
  6172.9  469.66  6225.9  468.68  6302.8  470.60  6427.3  470.91  6571.9  472.91
#Mann=5,-1,0
  4724.9    0.05       0  4972.9    0.12       0  4989.0    0.07       0
  4993.0    0.12       0  5019.4    0.05       0
Bank Sta=4989,4993
Exp/Cntr=0.3,0.1

Type RM Length L Ch R = 1,2000,500,500,500
BEGIN DESCRIPTION:
Bachelor Creek Trib 11 4.0
END DESCRIPTION:
XS GIS Cut Line= 3
      2646857.97      6941632.23      2646476.38      6941461.61
      2645225.96      6942011.02
#Sta/Elev= 30
  4582.0  463.45  4616.7  462.08  4645.3  462.42  4818.7  453.42  4956.1  450.33
  4995.5  449.63  4995.7  449.13  4999.5  449.63  5064.6  450.33  5112.7  450.66
  5263.8  454.23  5380.5  459.72  5403.9  460.08  5409.3  459.53  5491.9  464.35
  5508.2  464.69  5546.5  464.42  5607.1  465.86  5635.9  465.08  5677.1  466.02
  5758.1  465.62  5804.8  466.47  5909.2  465.99  5984.7  466.50  6054.7  468.12
  6169.1  468.09  6229.1  469.28  6304.6  469.18  6328.0  470.09  6365.8  470.10
#Mann=5,-1,0
  4582.0    0.05       0  4956.1    0.12       0  4995.5    0.07       0
  4999.5    0.12       0  5064.6    0.05       0
Bank Sta=4995.5,4999.5
Exp/Cntr=0.3,0.1

Type RM Length L Ch R = 1,1500,663,663,663
BEGIN DESCRIPTION:
Bachelor Creek Trib 11 3.0
END DESCRIPTION:
XS GIS Cut Line= 3
      2646935.91      6941311.63      2646429.14      6941057.99
      2645026.02      6941161.00
#Sta/Elev= 30
  4433.3  462.76  4487.0  461.94  4515.0  459.54  4612.1  455.20  4844.9  450.58
  4917.4  448.78  4923.2  446.40  4923.5  445.90  4927.2  446.40  4934.1  448.36
  4939.7  447.12  4956.5  449.39  4962.1  448.18  4992.3  448.16  5023.2  450.15
  5103.4  451.08  5223.7  457.89  5242.4  459.89  5247.4  459.16  5314.0  463.18
  5423.8  463.06  5614.8  455.22  5705.0  458.52  5745.1  461.65  5855.4  466.41
  5955.7  467.33  6068.2  466.30  6116.1  468.87  6186.3  467.09  6406.9  468.70
#Mann=6,-1,0
  4433.3    0.05       0  4844.9    0.12       0  4923.2    0.07       0
  4927.2    0.12       0  5223.7    0.05       0  5423.8    0.12       0
Bank Sta=4923.2,4927.2
Exp/Cntr=0.3,0.1

Type RM Length L Ch R = 1,837,0,0,0
BEGIN DESCRIPTION:
Bachelor Creek Trib 11 2.0
END DESCRIPTION:
XS GIS Cut Line= 3
      2646938.78      6940822.43      2646475.56      6940445.82
      2645193.67      6940521.11
#Sta/Elev= 30
  4403.0  456.65  4531.7  455.63  4619.3  453.12  4654.4  449.52  4690.1  448.88
  4732.7  445.85  4790.2  445.07  4802.6  442.85  4802.8  442.35  4806.6  442.85
  4811.0  444.60  4825.4  446.25  4982.0  445.33  4996.4  443.63  4999.9  444.71
  5003.8  443.63  5039.6  445.82  5098.8  446.14  5232.0  448.61  5331.3  451.57
  5399.2  452.70  5560.5  449.62  5710.8  450.27  5856.0  454.46  5991.3  460.83
  6101.5  457.44  6261.7  463.59  6271.8  464.22  6280.4  468.74  6284.1  468.74
#Mann=8,-1,0
  4403.0    0.05       0  4531.7    0.12       0  4802.6    0.07       0
  4806.6    0.12       0  5098.8    0.05       0  5232.0    0.12       0
  5331.3    0.05       0  5399.2    0.12       0
Bank Sta=4802.6,4806.6
Exp/Cntr=0.3,0.1

Chan Stop Cuts=-1