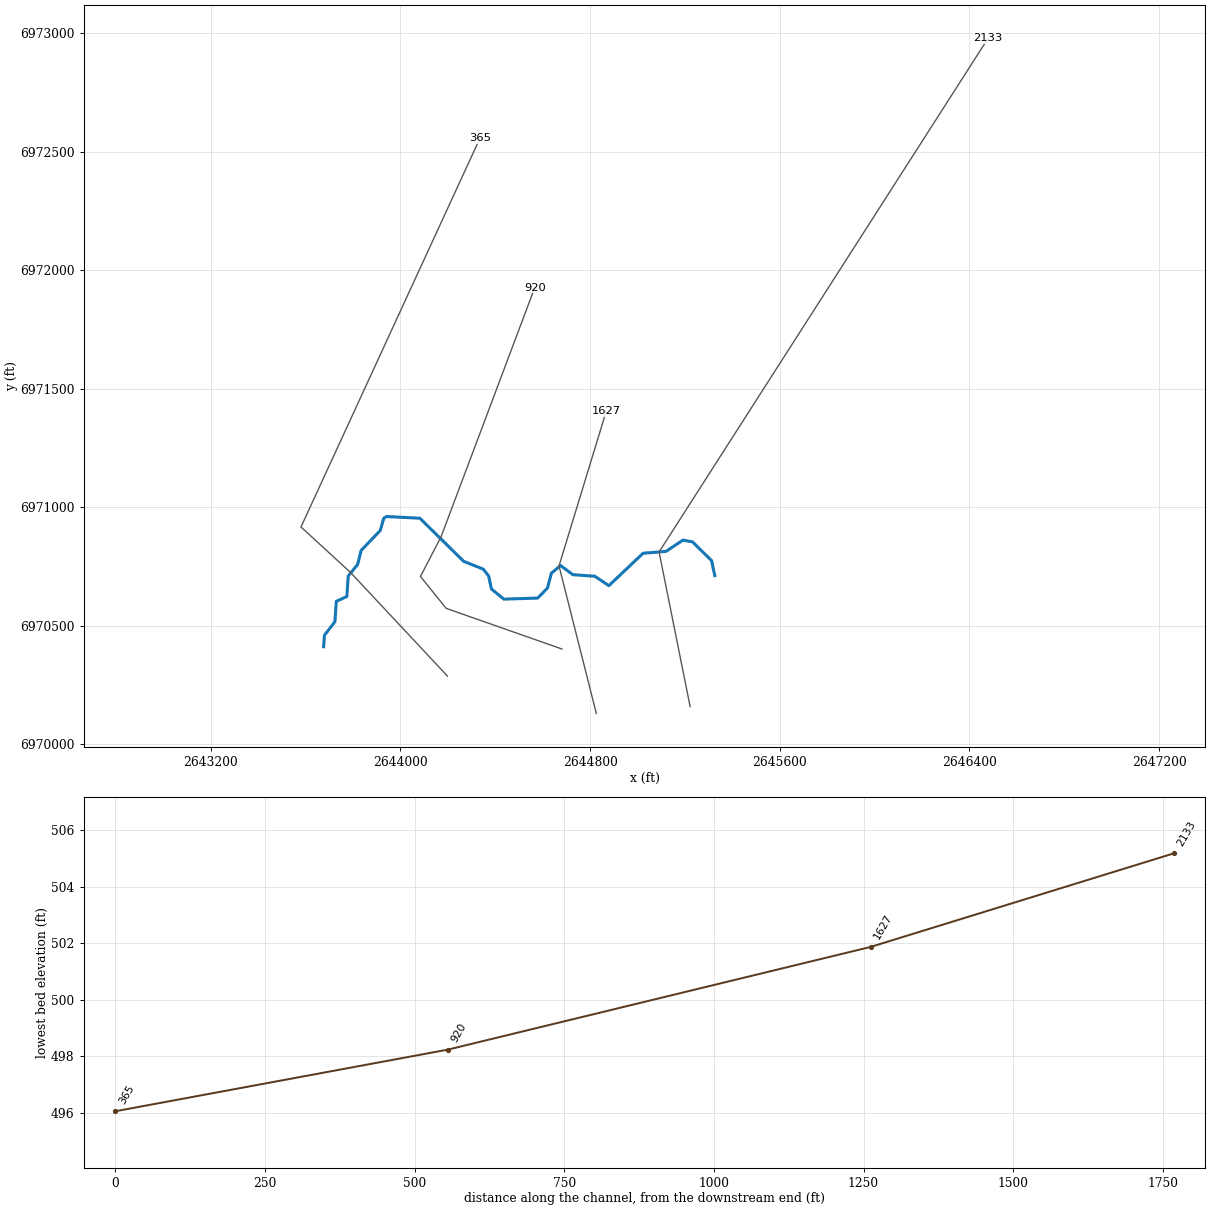
--- Bachelor Creek Trib 2.prj (project) ---

Proj Title=Bachelor Creek Trib 2 Base Level Engineering
Current Plan=p01
Default Exp/Contr=0.3,0.1
English Units
Geom File=g01
Flow File=f01
Plan File=p01
BEGIN DESCRIPTION:
Bachelor Creek Trib 2
END DESCRIPTION:

--- Bachelor Creek Trib 2.p01 (plan) ---

Plan Title=Multiple Run
Short Identifier=Multiple
Geom File=g01
Flow File=f01
Subcritical Flow
K Sum by GR= 0
Std Step Tol= 0.01
Critical Tol= 0.01
Num of Std Step Trials= 20
Max Error Tol= 0.3
Flow Tol Ratio= 0.001
Split Flow NTrial= 30
Split Flow Tol= 0.02
Split Flow Ratio= 0.02
Log Output Level= 0
Friction Slope Method= 1
Unsteady Friction Slope Method= 2
Unsteady Bridges Friction Slope Method= 1
Parabolic Critical Depth
Global Vel Dist=  1 , 1 , 1
Global Log Level= 0
CheckData=True
Encroach Param= -1, 0, 0, 0
BEGIN DESCRIPTION:
Multiple Run
END DESCRIPTION:

--- Bachelor Creek Trib 2.f01 (steady flow) ---

Flow Title=Multiple
Number of Profiles=7
Profile Names=10-year,25-year,50-year,1pct_min,100-year,1pct_plu,500-year
River Rch & RM= Bachelor Creek T,Reach-1,2133
     673     908    1100     661    1320    2633    1896
Boundary for River Rch & Prof#=Bachelor Creek T,Reach-1,1
Up Type=0
Dn Type=3
Dn Slope=0.005
Boundary for River Rch & Prof#=Bachelor Creek T,Reach-1,2
Up Type=0
Dn Type=3
Dn Slope=0.005
Boundary for River Rch & Prof#=Bachelor Creek T,Reach-1,3
Up Type=0
Dn Type=3
Dn Slope=0.005
Boundary for River Rch & Prof#=Bachelor Creek T,Reach-1,4
Up Type=0
Dn Type=3
Dn Slope=0.005
Boundary for River Rch & Prof#=Bachelor Creek T,Reach-1,5
Up Type=0
Dn Type=3
Dn Slope=0.005
Boundary for River Rch & Prof#=Bachelor Creek T,Reach-1,6
Up Type=0
Dn Type=3
Dn Slope=0.005
Boundary for River Rch & Prof#=Bachelor Creek T,Reach-1,7
Up Type=0
Dn Type=3
Dn Slope=0.005

--- Bachelor Creek Trib 2.g01 (geometry) ---

Geom Title=Existing Conditions

River Reach=Bachelor Creek T,Reach-1
Reach XY= 30
      2645326.00      6970711.00      2645312.54      6970774.32
      2645232.07      6970853.54      2645191.42      6970860.97
      2645120.03      6970813.38      2645023.57      6970805.48
      2644879.42      6970668.79      2644820.11      6970708.44
      2644727.49      6970715.10      2644675.69      6970753.77
      2644636.78      6970721.39      2644620.26      6970658.47
      2644578.70      6970616.35      2644436.29      6970611.97
      2644384.03      6970654.64      2644372.10      6970709.53
      2644349.83      6970738.13      2644266.34      6970771.79
      2644082.19      6970953.20      2643941.84      6970960.36
      2643929.39      6970952.90      2643915.07      6970901.64
      2643834.16      6970817.05      2643819.86      6970758.83
      2643779.85      6970709.35      2643773.92      6970623.01
      2643729.55      6970602.50      2643723.74      6970517.01
      2643679.64      6970459.50      2643676.00      6970411.00

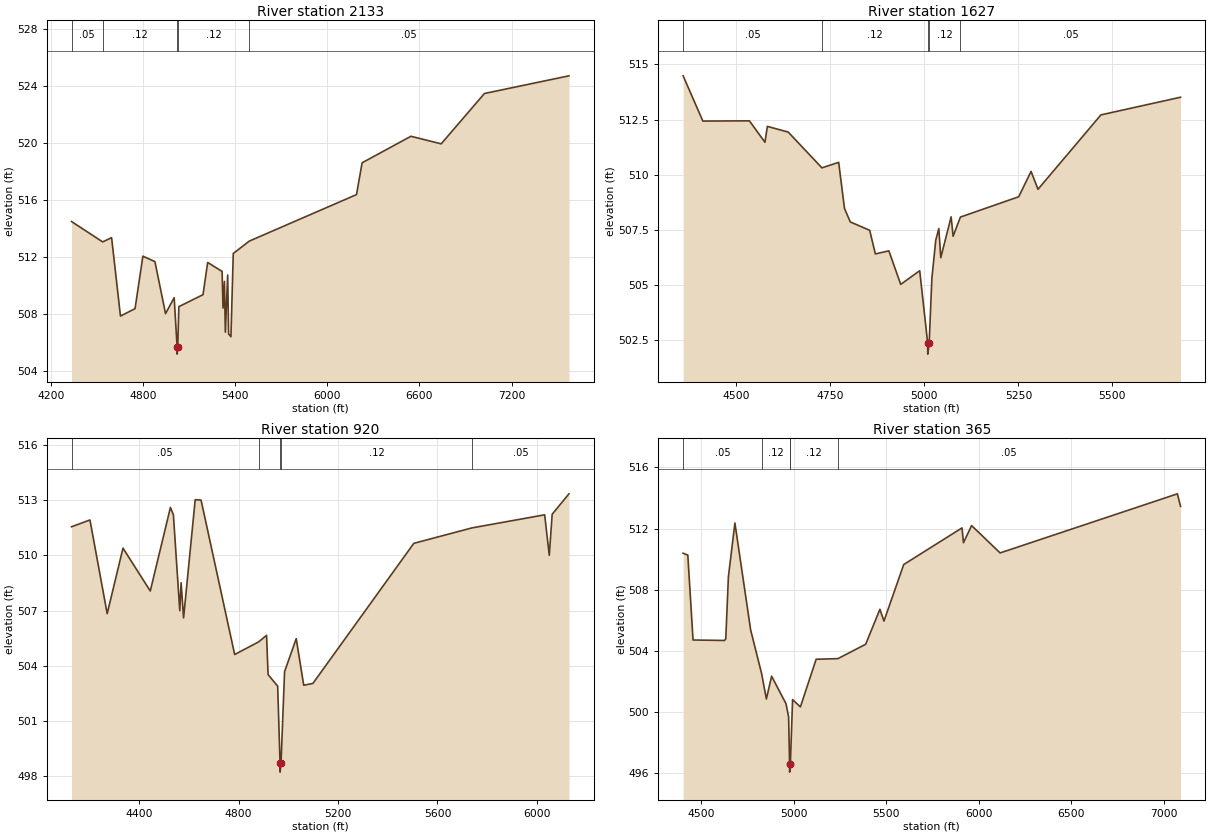
Type RM Length L Ch R = 1,2133,506,506,506
BEGIN DESCRIPTION:
Bachelor Creek Trib 2 4.0
END DESCRIPTION:
XS GIS Cut Line= 3
      2645222.04      6970158.70      2645091.06      6970810.87
      2646478.89      6972977.50
#Sta/Elev= 30
  4334.8  514.48  4537.8  513.05  4595.6  513.35  4653.3  507.85  4748.3  508.37
  4799.2  512.05  4877.7  511.67  4946.8  508.02  5003.0  509.14  5022.1  505.68
  5022.4  505.18  5026.1  505.68  5033.4  508.51  5190.7  509.35  5221.1  511.61
  5315.0  510.98  5320.9  508.41  5330.2  510.28  5336.1  506.72  5351.3  510.73
  5357.3  506.60  5372.5  506.40  5387.7  512.24  5492.5  513.11  6190.0  516.37
  6226.4  518.60  6544.3  520.46  6741.3  519.93  7022.8  523.46  7573.0  524.70
#Mann=5,-1,0
  4334.8    0.05       0  4537.8    0.12       0  5022.1    0.07       0
  5026.1    0.12       0  5492.5    0.05       0
Bank Sta=5022.1,5026.1
Exp/Cntr=0.3,0.1

Type RM Length L Ch R = 1,1627,707,707,707
BEGIN DESCRIPTION:
Bachelor Creek Trib 2 3.0
END DESCRIPTION:
XS GIS Cut Line= 3
      2644826.21      6970130.05      2644668.98      6970751.99
      2644867.88      6971403.50
#Sta/Elev= 30
  4358.5  514.48  4411.0  512.43  4534.8  512.44  4576.1  511.47  4582.5  512.19
  4638.0  511.93  4727.6  510.31  4772.1  510.56  4787.6  508.47  4803.0  507.86
  4854.6  507.48  4869.7  506.41  4905.6  506.55  4937.1  505.03  4987.6  505.65
  5008.8  502.37  5009.0  501.87  5012.8  502.37  5019.9  505.30  5030.3  507.03
  5038.4  507.56  5043.6  506.24  5071.2  508.09  5076.4  507.21  5095.8  508.08
  5250.9  509.00  5283.7  510.15  5302.2  509.34  5469.5  512.71  5681.2  513.51
#Mann=5,-1,0
  4358.5    0.05       0  4727.6    0.12       0  5008.8    0.07       0
  5012.8    0.12       0  5095.8    0.05       0
Bank Sta=5008.8,5012.8
Exp/Cntr=0.3,0.1

Type RM Length L Ch R = 1,920,555,555,555
BEGIN DESCRIPTION:
Mapping XS b1a2314b
END DESCRIPTION:
XS GIS Cut Line= 5
      2644681.29      6970401.59      2644193.02      6970573.02
      2644084.52      6970707.57      2644171.32      6970874.67
      2644566.29      6971925.03
#Sta/Elev= 30
  4128.0  511.56  4202.1  511.93  4271.4  506.84  4335.0  510.40  4444.7  508.07
  4525.8  512.61  4537.7  512.21  4563.4  507.00  4568.7  508.52  4578.7  506.61
  4625.4  513.03  4649.0  513.01  4784.2  504.62  4881.1  505.31  4912.4  505.66
  4918.6  503.53  4957.2  502.90  4966.7  498.73  4966.9  498.23  4970.7  498.73
  4984.9  503.69  5031.8  505.48  5062.0  502.95  5098.9  503.05  5504.8  510.66
  5739.0  511.50  6031.1  512.21  6049.7  510.01  6061.3  512.24  6128.8  513.35
#Mann=5,-1,0
  4128.0    0.05       0  4881.1    0.12       0  4966.7    0.07       0
  4970.7    0.12       0  5739.0    0.05       0
Bank Sta=4966.7,4970.7
Exp/Cntr=0.3,0.1

Type RM Length L Ch R = 1,365,0,0,0
BEGIN DESCRIPTION:
Bachelor Creek Trib 2 2.0
END DESCRIPTION:
XS GIS Cut Line= 4
      2644198.24      6970287.51      2643789.77      6970724.13
      2643580.61      6970916.34      2644335.59      6972556.46
#Sta/Elev= 30
  4402.1  510.38  4427.4  510.26  4455.7  504.70  4625.7  504.67  4632.5  504.77
  4646.7  508.84  4681.9  512.36  4766.9  505.36  4826.0  502.51  4851.9  500.84
  4880.2  502.33  4957.9  500.53  4972.0  499.67  4977.4  496.55  4977.6  496.05
  4981.4  496.55  4993.5  500.80  5035.7  500.32  5120.8  503.44  5238.4  503.48
  5388.3  504.42  5465.3  506.71  5487.3  505.94  5593.9  509.64  5909.0  512.04
  5916.7  511.07  5960.7  512.19  6114.8  510.40  7072.6  514.27  7089.6  513.45
#Mann=5,-1,0
  4402.1    0.05       0  4826.0    0.12       0  4977.4    0.07       0
  4981.4    0.12       0  5238.4    0.05       0
Bank Sta=4977.4,4981.4
Exp/Cntr=0.3,0.1

Chan Stop Cuts=-1