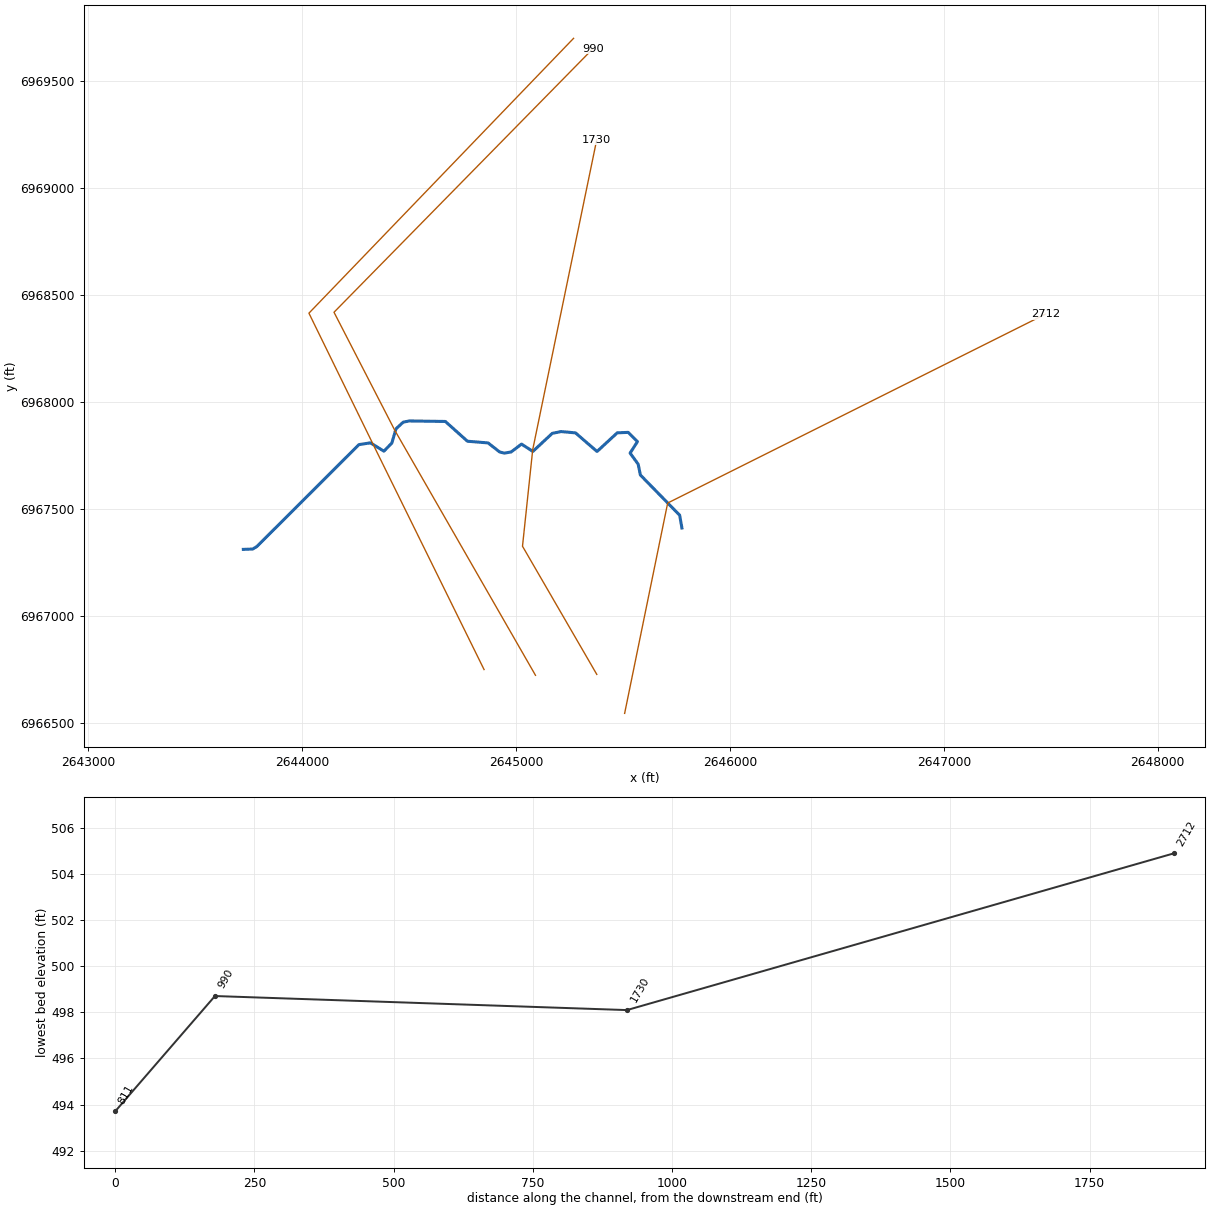
--- Bachelor Creek Trib 3.prj (project) ---

Proj Title=Bachelor Creek Trib 3 Base Level Engineering
Current Plan=p01
Default Exp/Contr=0.3,0.1
English Units
Geom File=g01
Flow File=f01
Plan File=p01
BEGIN DESCRIPTION:
Bachelor Creek Trib 3
END DESCRIPTION:

--- Bachelor Creek Trib 3.p01 (plan) ---

Plan Title=Multiple Run
Short Identifier=Multiple
Geom File=g01
Flow File=f01
Subcritical Flow
K Sum by GR= 0
Std Step Tol= 0.01
Critical Tol= 0.01
Num of Std Step Trials= 20
Max Error Tol= 0.3
Flow Tol Ratio= 0.001
Split Flow NTrial= 30
Split Flow Tol= 0.02
Split Flow Ratio= 0.02
Log Output Level= 0
Friction Slope Method= 1
Unsteady Friction Slope Method= 2
Unsteady Bridges Friction Slope Method= 1
Parabolic Critical Depth
Global Vel Dist=  1 , 1 , 1
Global Log Level= 0
CheckData=True
Encroach Param= -1, 0, 0, 0
BEGIN DESCRIPTION:
Multiple Run
END DESCRIPTION:

--- Bachelor Creek Trib 3.f01 (steady flow) ---

Flow Title=Multiple
Number of Profiles=7
Profile Names=10-year,25-year,50-year,1pct_min,100-year,1pct_plu,500-year
River Rch & RM= Bachelor Creek T,Reach-1,2712
     426     558     663     391     780    1556    1078
Boundary for River Rch & Prof#=Bachelor Creek T,Reach-1,1
Up Type=0
Dn Type=3
Dn Slope=0.005
Boundary for River Rch & Prof#=Bachelor Creek T,Reach-1,2
Up Type=0
Dn Type=3
Dn Slope=0.005
Boundary for River Rch & Prof#=Bachelor Creek T,Reach-1,3
Up Type=0
Dn Type=3
Dn Slope=0.005
Boundary for River Rch & Prof#=Bachelor Creek T,Reach-1,4
Up Type=0
Dn Type=3
Dn Slope=0.005
Boundary for River Rch & Prof#=Bachelor Creek T,Reach-1,5
Up Type=0
Dn Type=3
Dn Slope=0.005
Boundary for River Rch & Prof#=Bachelor Creek T,Reach-1,6
Up Type=0
Dn Type=3
Dn Slope=0.005
Boundary for River Rch & Prof#=Bachelor Creek T,Reach-1,7
Up Type=0
Dn Type=3
Dn Slope=0.005

--- Bachelor Creek Trib 3.g01 (geometry) ---

Geom Title=Existing Conditions

River Reach=Bachelor Creek T,Reach-1
Reach XY= 30
      2645776.00      6967411.00      2645765.48      6967470.79
      2645581.81      6967658.71      2645571.56      6967709.35
      2645533.78      6967761.10      2645568.11      6967814.66
      2645524.82      6967857.90      2645473.76      6967855.91
      2645379.33      6967768.61      2645278.43      6967855.57
      2645210.92      6967861.78      2645169.83      6967853.21
      2645079.33      6967769.01      2645026.09      6967803.16
      2644978.30      6967766.63      2644946.21      6967760.79
      2644923.83      6967766.40      2644870.03      6967808.62
      2644773.58      6967816.54      2644670.14      6967908.94
      2644500.79      6967911.33      2644473.30      6967905.64
      2644439.46      6967874.61      2644420.14      6967808.18
      2644383.01      6967770.03      2644319.96      6967809.01
      2644266.32      6967800.79      2643789.27      6967324.47
      2643769.86      6967312.68      2643726.00      6967311.00

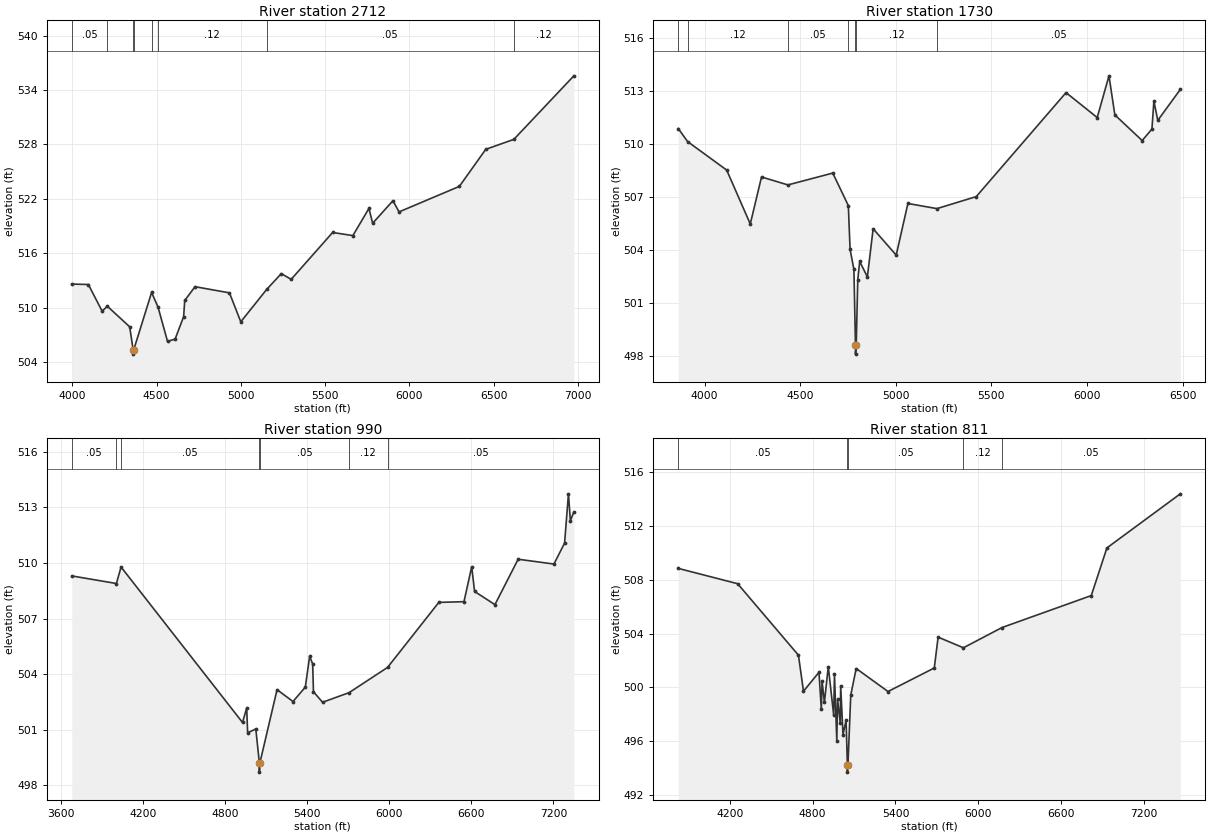
Type RM Length L Ch R = 1,2712,982,982,982
BEGIN DESCRIPTION:
Bachelor Creek Trib 3 5.0
END DESCRIPTION:
XS GIS Cut Line= 3
      2645508.24      6966544.46      2645709.40      6967527.69
      2647475.98      6968410.99
#Sta/Elev= 30
  3996.4  512.62  4094.9  512.57  4176.6  509.63  4207.3  510.18  4339.9  507.91
  4360.4  505.40  4360.7  504.90  4364.4  505.40  4470.0  511.70  4508.4  510.07
  4564.5  506.30  4609.6  506.56  4660.1  509.03  4666.5  510.81  4727.8  512.33
  4931.9  511.65  4999.1  508.46  5152.4  512.02  5239.4  513.77  5298.1  513.14
  5544.0  518.30  5664.2  517.96  5759.3  520.95  5781.6  519.32  5901.8  521.80
  5938.1  520.57  6295.9  523.38  6452.4  527.46  6619.2  528.56  6975.1  535.56
#Mann=8,-1,0
  3996.4    0.05       0  4207.3    0.12       0  4360.4    0.07       0
  4364.4    0.12       0  4470.0    0.05       0  4508.4    0.12       0
  5152.4    0.05       0  6619.2    0.12       0
Bank Sta=4360.4,4364.4
Exp/Cntr=0.3,0.1

Type RM Length L Ch R = 1,1730,740,740,740
BEGIN DESCRIPTION:
Mapping XS 4c8dfa80
END DESCRIPTION:
XS GIS Cut Line= 4
      2645378.03      6966726.72      2645030.80      6967325.70
      2645078.55      6967777.09      2645377.94      6969226.34
#Sta/Elev= 30
  3862.1  510.86  3911.2  510.12  4115.5  508.51  4238.9  505.46  4297.7  508.12
  4435.8  507.67  4670.4  508.34  4751.8  506.50  4760.9  504.03  4781.0  502.89
  4789.1  498.60  4789.3  498.10  4793.1  498.60  4801.1  502.30  4811.2  503.34
  4851.4  502.47  4881.6  505.19  5002.2  503.70  5063.4  506.62  5215.4  506.33
  5420.9  507.01  5890.5  512.89  6053.6  511.48  6115.1  513.84  6145.8  511.63
  6288.7  510.18  6339.8  510.83  6350.0  512.41  6370.4  511.32  6488.2  513.07
#Mann=7,-1,0
  3862.1    0.05       0  3911.2    0.12       0  4435.8    0.05       0
  4751.8    0.12       0  4789.1    0.07       0  4793.1    0.12       0
  5215.4    0.05       0
Bank Sta=4789.1,4793.1
Exp/Cntr=0.3,0.1

Type RM Length L Ch R = 1,990,179,179,179
BEGIN DESCRIPTION:
Bachelor Creek Trib 3 4.0
END DESCRIPTION:
XS GIS Cut Line= 4
      2645091.56      6966722.42      2644434.02      6967867.34
      2644149.73      6968419.45      2645360.63      6969652.06
#Sta/Elev= 30
  3679.7  509.30  4005.9  508.89  4039.9  509.78  4927.5  501.39  4958.1  502.17
  4964.9  500.83  5024.7  501.04  5050.5  499.21  5050.8  498.71  5054.5  499.21
  5179.9  503.16  5296.6  502.52  5386.5  503.30  5418.1  504.96  5440.3  504.55
  5445.9  503.05  5512.5  502.48  5706.3  503.00  5987.3  504.36  6362.0  507.87
  6545.9  507.91  6602.4  509.79  6623.6  508.46  6772.2  507.75  6941.8  510.20
  7203.5  509.94  7281.2  511.07  7309.5  513.73  7323.6  512.28  7348.9  512.75
#Mann=7,-1,0
  3679.7    0.05       0  4005.9    0.12       0  4039.9    0.05       0
  5050.5    0.03       0  5054.5    0.05       0  5706.3    0.12       0
  5987.3    0.05       0
Bank Sta=5050.5,5054.5
Exp/Cntr=0.3,0.1

Type RM Length L Ch R = 1,811,0,0,0
BEGIN DESCRIPTION:
Bachelor Creek Trib 3 3.0
END DESCRIPTION:
XS GIS Cut Line= 4
      2644851.12      6966749.29      2644332.07      6967802.87
      2644032.54      6968415.11      2645269.51      6969699.82
#Sta/Elev= 30
  3825.5  508.85  4256.1  507.71  4696.9  502.40  4733.4  499.72  4845.7  501.13
  4862.6  498.38  4868.2  500.47  4885.1  498.89  4913.1  501.55  4952.5  497.93
  4958.0  500.98  4974.9  496.04  4980.5  499.11  5000.0  497.35  5003.0  500.12
  5019.9  496.50  5042.4  497.57  5051.6  494.21  5051.8  493.71  5055.6  494.21
  5076.1  499.43  5115.5  501.41  5346.2  499.70  5681.6  501.45  5709.4  503.74
  5892.9  502.95  6171.5  504.45  6819.7  506.83  6932.9  510.37  7465.0  514.39
#Mann=5,-1,0
  3825.5    0.05       0  5051.6    0.03       0  5055.6    0.05       0
  5892.9    0.12       0  6171.5    0.05       0
Bank Sta=5051.6,5055.6
Exp/Cntr=0.3,0.1

Chan Stop Cuts=-1