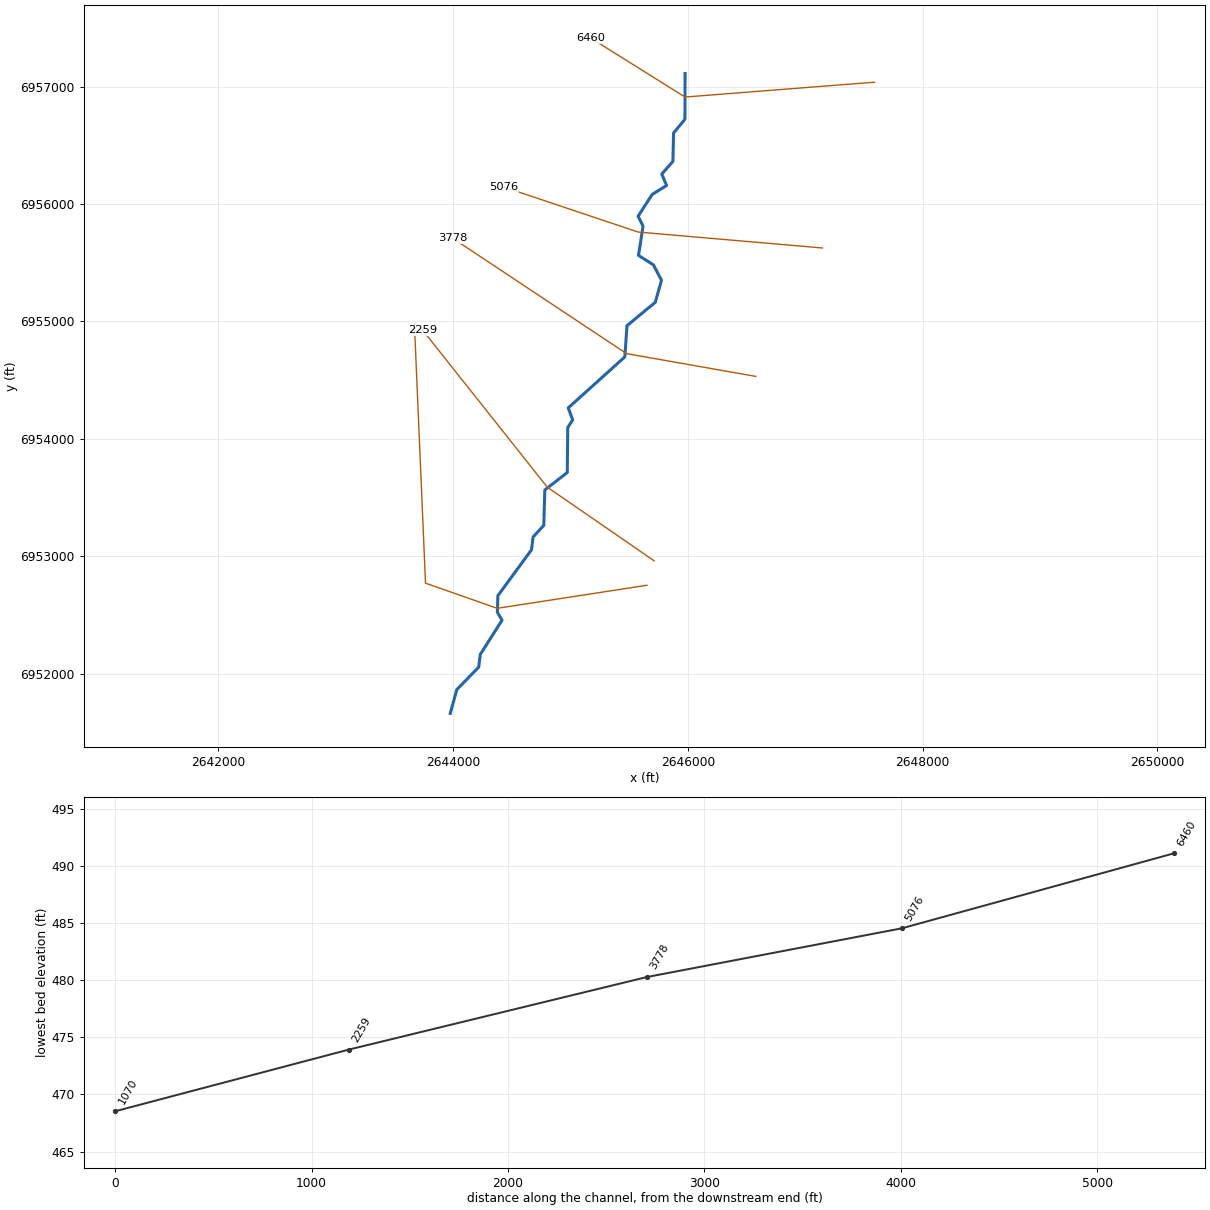
--- Bachelor Creek Trib 4.prj (project) ---

Proj Title=Bachelor Creek Trib 4 Base Level Engineering
Current Plan=p01
Default Exp/Contr=0.3,0.1
English Units
Geom File=g01
Flow File=f01
Plan File=p01
Y Axis Title=Elevation
X Axis Title(PF)=Main Channel Distance
X Axis Title(XS)=Station
BEGIN DESCRIPTION:
Bachelor Creek Trib 4
END DESCRIPTION:
DSS Export Rating Curves= 0
DSS Export Rating Curve Sorted= 0
DSS Export Volume Flow Curves= 0
DXF OffsetX= 0
DXF OffsetY= 0
DXF ScaleX= 1
DXF ScaleY= 10

--- Bachelor Creek Trib 4.p01 (plan) ---

Plan Title=Multiple Run
Short Identifier=Multiple
Geom File=g01
Flow File=f01
Subcritical Flow
K Sum by GR= 0
Std Step Tol= 0.01
Critical Tol= 0.01
Num of Std Step Trials= 20
Max Error Tol= 0.3
Flow Tol Ratio= 0.001
Split Flow NTrial= 30
Split Flow Tol= 0.02
Split Flow Ratio= 0.02
Log Output Level= 0
Friction Slope Method= 1
Unsteady Friction Slope Method= 2
Unsteady Bridges Friction Slope Method= 1
Parabolic Critical Depth
Global Vel Dist=  1 , 1 , 1
Global Log Level= 0
CheckData=True
Encroach Param= -1, 0, 0, 0
BEGIN DESCRIPTION:
Multiple Run
END DESCRIPTION:

--- Bachelor Creek Trib 4.f01 (steady flow) ---

Flow Title=Multiple
Program Version=4.10
Number of Profiles= 7
Profile Names=10-year,25-year,50-year,1pct_min,100-year,1pct_plu,500-year
River Rch & RM=Bachelor Creek T,Reach-1         ,6460
     472     625     747     444     885    1766    1241
River Rch & RM=Bachelor Creek T,Reach-1         ,5076
     627     843    1017     609    1216    2426    1735
River Rch & RM=Bachelor Creek T,Reach-1         ,2259
     689     929    1125     675    1348    2689    1933
Boundary for River Rch & Prof#=Bachelor Creek T,Reach-1         , 1
Up Type= 0
Dn Type= 3
Dn Slope=0.005
Boundary for River Rch & Prof#=Bachelor Creek T,Reach-1         , 2
Up Type= 0
Dn Type= 3
Dn Slope=0.005
Boundary for River Rch & Prof#=Bachelor Creek T,Reach-1         , 3
Up Type= 0
Dn Type= 3
Dn Slope=0.005
Boundary for River Rch & Prof#=Bachelor Creek T,Reach-1         , 4
Up Type= 0
Dn Type= 3
Dn Slope=0.005
Boundary for River Rch & Prof#=Bachelor Creek T,Reach-1         , 5
Up Type= 0
Dn Type= 3
Dn Slope=0.005
Boundary for River Rch & Prof#=Bachelor Creek T,Reach-1         , 6
Up Type= 0
Dn Type= 3
Dn Slope=0.005
Boundary for River Rch & Prof#=Bachelor Creek T,Reach-1         , 7
Up Type= 0
Dn Type= 3
Dn Slope=0.005
DSS Import GetInterval= 0
DSS Import GetPeak= 0
DSS Import FillOption= 0

--- Bachelor Creek Trib 4.g01 (geometry) ---

Geom Title=Existing Conditions

River Reach=Bachelor Creek T,Reach-1
Reach XY= 30
      2645976.00      6957111.00      2645974.94      6956721.44
      2645878.07      6956605.14      2645872.45      6956362.47
      2645777.67      6956254.94      2645818.28      6956157.34
      2645695.64      6956081.47      2645576.01      6955895.64
      2645618.19      6955810.91      2645579.37      6955562.28
      2645706.37      6955481.47      2645775.25      6955350.32
      2645722.39      6955162.48      2645481.45      6954963.47
      2645462.71      6954697.35      2644981.11      6954263.30
      2645018.41      6954161.01      2644976.66      6954095.84
      2644972.47      6953712.45      2644781.36      6953563.70
      2644772.45      6953262.47      2644681.54      6953163.42
      2644668.12      6953054.84      2644381.47      6952663.44
      2644377.38      6952521.44      2644416.85      6952454.27
      2644231.77      6952163.32      2644218.14      6952054.83
      2644031.52      6951863.43      2643976.00      6951661.00

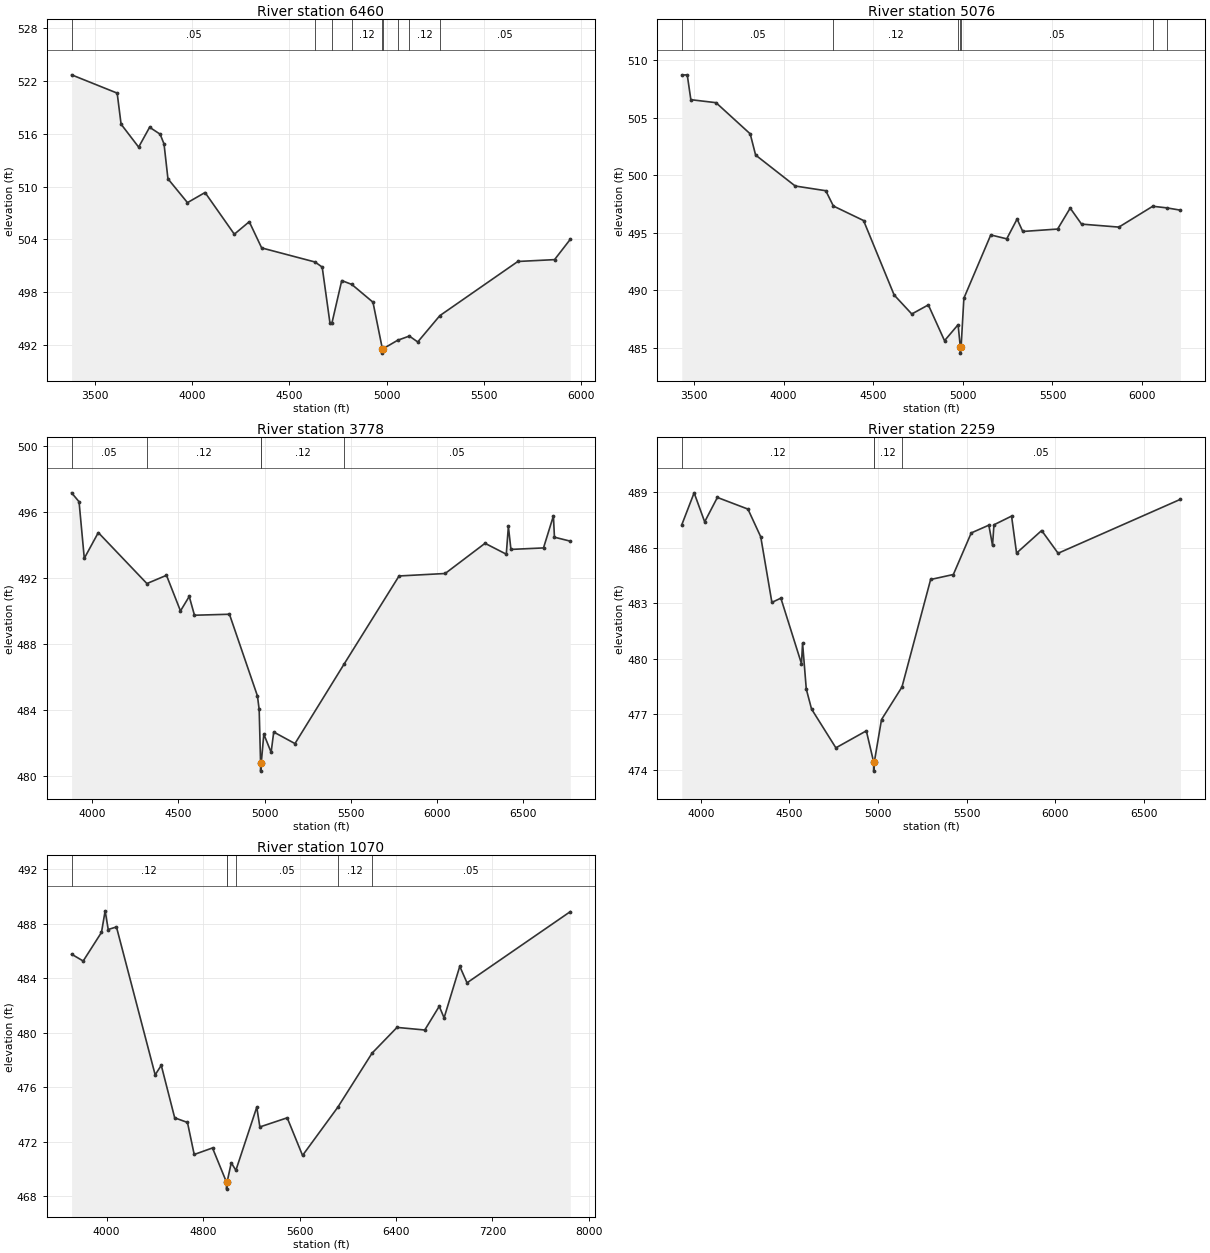
Type RM Length L Ch R = 1,6460,1384,1384,1384
BEGIN DESCRIPTION:
Bachelor Creek Trib 4 5.0
END DESCRIPTION:
XS GIS Cut Line= 3
      2647589.38      6957037.37      2645976.00      6956911.00
      2645176.02      6957410.99
#Sta/Elev= 30
  3381.7  522.72  3615.8  520.64  3635.9  517.11  3726.1  514.50  3782.4  516.76
  3836.5  515.97  3856.5  514.86  3876.6  510.90  3976.9  508.19  4067.2  509.34
  4217.6  504.60  4294.3  506.02  4358.1  503.04  4632.2  501.44  4669.0  500.86
  4709.1  494.46  4718.8  494.48  4769.3  499.33  4821.1  498.89  4929.8  496.87
  4978.0  491.58  4978.2  491.08  4982.0  491.58  5056.4  492.54  5116.6  493.02
  5159.8  492.35  5273.2  495.34  5674.0  501.50  5862.6  501.71  5943.4  504.02
#Mann=9,-1,0
  3381.7    0.05       0  4632.2    0.12       0  4718.8    0.05       0
  4821.1    0.12       0  4978.0    0.07       0  4982.0    0.12       0
  5056.4    0.05       0  5116.6    0.12       0  5273.2    0.05       0
Bank Sta=4978,4982
Exp/Cntr=0.3,0.1

Type RM Length L Ch R = 1,5076,1298,1298,1298
BEGIN DESCRIPTION:
Bachelor Creek Trib 4 2.0
END DESCRIPTION:
XS GIS Cut Line= 3
      2647146.30      6955625.15      2645576.00      6955761.00
      2644432.62      6956144.35
#Sta/Elev= 30
  3432.0  508.69  3462.4  508.71  3482.5  506.55  3623.0  506.29  3813.7  503.58
  3843.8  501.74  4064.7  499.05  4235.3  498.64  4277.7  497.31  4446.1  496.05
  4616.7  489.58  4715.1  487.93  4807.4  488.72  4897.8  485.61  4973.4  487.00
  4986.1  485.03  4986.3  484.53  4990.1  485.03  5005.7  489.30  5155.8  494.80
  5244.8  494.46  5302.6  496.18  5334.2  495.10  5528.7  495.31  5598.8  497.13
  5662.1  495.74  5870.5  495.48  6059.4  497.29  6138.2  497.15  6214.1  496.95
#Mann=7,-1,0
  3432.0    0.05       0  4277.7    0.12       0  4973.4    0.05       0
  4986.1    0.04       0  4990.1    0.05       0  6059.4   0.075       0
  6138.2    0.05       0
Bank Sta=4986.1,4990.1
Exp/Cntr=0.3,0.1

Type RM Length L Ch R = 1,3778,1519,1519,1519
BEGIN DESCRIPTION:
Mapping XS 9635ba2b
END DESCRIPTION:
XS GIS Cut Line= 3
      2646578.63      6954531.37      2645477.93      6954725.21
      2643996.45      6955708.25
#Sta/Elev= 30
  3879.7  497.14  3923.0  496.60  3953.4  493.17  4034.7  494.73  4317.0  491.64
  4430.7  492.14  4511.9  489.98  4562.7  490.86  4593.1  489.72  4796.2  489.78
  4958.7  484.83  4968.8  484.01  4977.0  480.77  4977.2  480.27  4981.0  480.77
  4995.8  482.51  5038.3  481.41  5053.3  482.64  5176.7  481.94  5461.4  486.75
  5781.1  492.10  6048.8  492.25  6280.3  494.08  6403.7  493.42  6415.8  495.10
  6430.7  493.71  6619.8  493.80  6677.3  495.74  6683.3  494.45  6775.3  494.21
#Mann=5,-1,0
  3879.7    0.05       0  4317.0    0.12       0  4977.0    0.07       0
  4981.0    0.12       0  5461.4    0.05       0
Bank Sta=4977,4981
Exp/Cntr=0.3,0.1

Type RM Length L Ch R = 1,2259,1189,1189,1189
BEGIN DESCRIPTION:
Mapping XS 227fbae1
END DESCRIPTION:
XS GIS Cut Line= 3
      2645713.26      6952959.96      2644802.03      6953588.19
      2643740.70      6954925.52
#Sta/Elev= 30
  3893.2  487.25  3962.8  488.98  4022.3  487.41  4094.0  488.73  4266.4  488.10
  4338.7  486.60  4401.6  483.05  4452.3  483.28  4568.7  479.73  4574.7  480.85
  4595.7  478.36  4625.4  477.28  4762.7  475.18  4934.5  476.10  4975.7  474.42
  4976.0  473.92  4979.7  474.42  5020.2  476.71  5135.6  478.47  5297.4  484.29
  5425.6  484.56  5526.6  486.81  5625.9  487.23  5646.7  486.13  5654.7  487.25
  5754.1  487.72  5782.3  485.72  5923.9  486.94  6016.8  485.71  6707.3  488.63
#Mann=4,-1,0
  3893.2    0.12       0  4975.7    0.07       0  4979.7    0.12       0
  5135.6    0.05       0
Bank Sta=4975.7,4979.7
Exp/Cntr=0.3,0.1

Type RM Length L Ch R = 1,1070,0,0,0
BEGIN DESCRIPTION:
Bachelor Creek Trib 4 1.0
END DESCRIPTION:
XS GIS Cut Line= 4
      2645651.00      6952752.26      2644375.54      6952555.83
      2643765.07      6952770.33      2643671.16      6954966.76
#Sta/Elev= 30
  3709.5  485.76  3805.6  485.26  3957.4  487.36  3987.7  488.94  4013.2  487.57
  4081.5  487.76  4402.6  476.91  4453.2  477.61  4564.5  473.76  4670.5  473.42
  4726.3  471.07  4878.1  471.55  4994.6  469.03  4994.9  468.53  4998.7  469.03
  5033.6  470.46  5072.1  469.91  5245.2  474.54  5270.9  473.09  5497.7  473.76
  5624.9  471.00  5917.6  474.54  6201.3  478.50  6408.4  480.39  6638.6  480.20
  6758.7  481.94  6798.8  481.09  6928.9  484.87  6989.0  483.66  7845.5  488.88
#Mann=6,-1,0
  3709.5    0.12       0  4994.6    0.07       0  4998.7    0.12       0
  5072.1    0.05       0  5917.6    0.12       0  6201.3    0.05       0
Bank Sta=4994.6,4998.7
Exp/Cntr=0.3,0.1

Chan Stop Cuts=-1