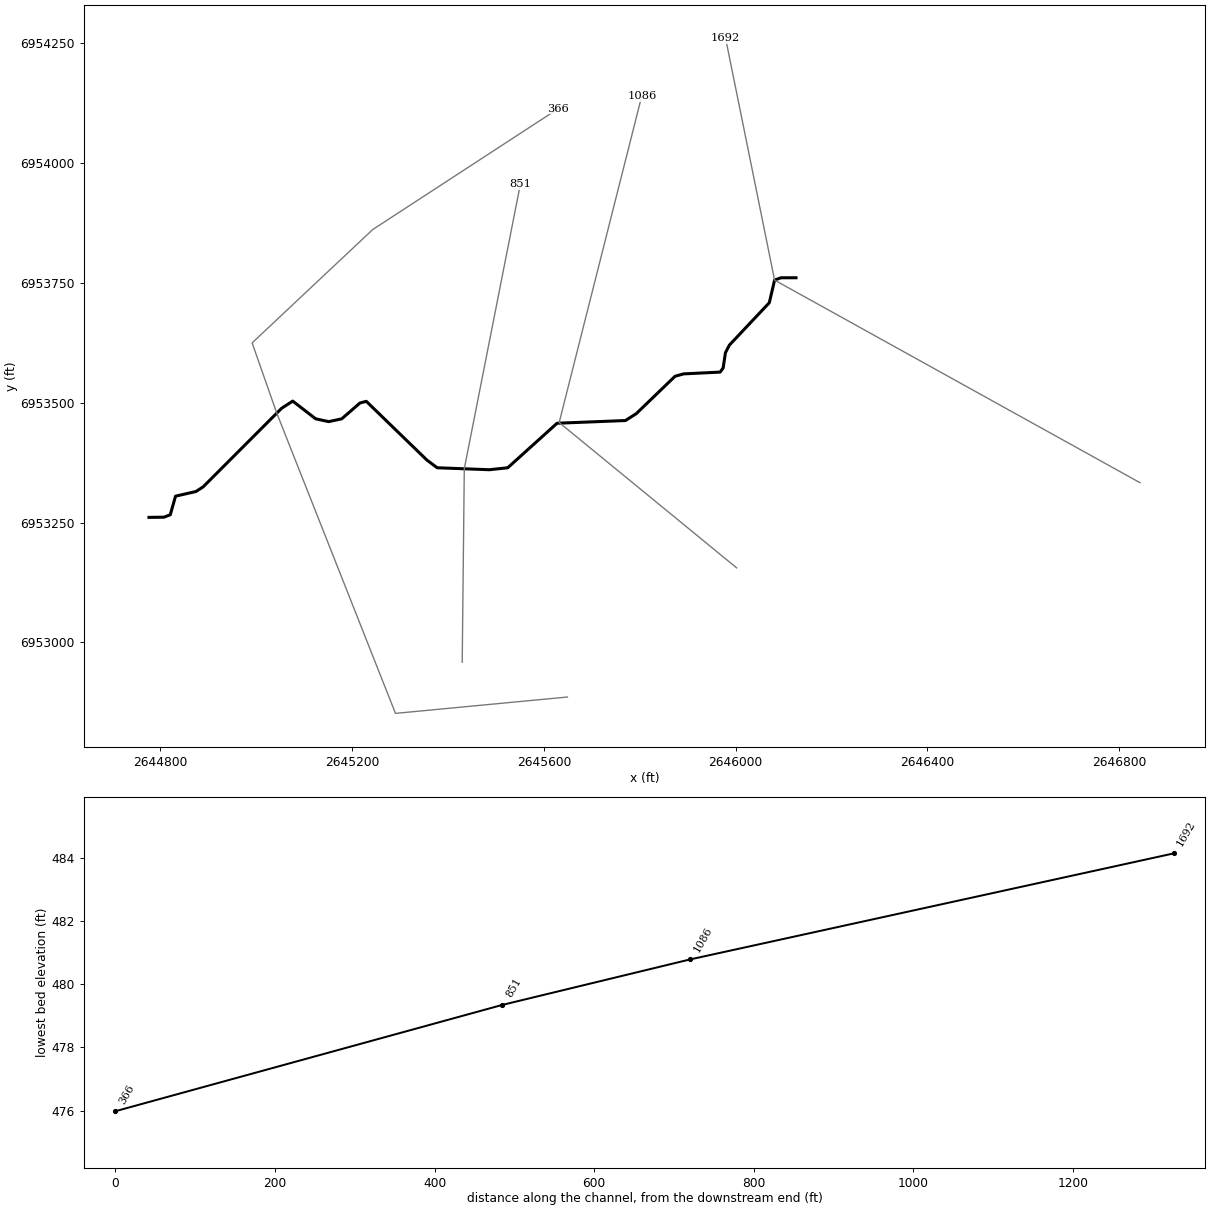
--- Bachelor Creek Trib 4_1.prj (project) ---

Proj Title=Bachelor Creek Trib 4_1 Base Level Engineering
Current Plan=p01
Default Exp/Contr=0.3,0.1
English Units
Geom File=g01
Flow File=f01
Plan File=p01
BEGIN DESCRIPTION:
Bachelor Creek Trib 4_1
END DESCRIPTION:

--- Bachelor Creek Trib 4_1.p01 (plan) ---

Plan Title=Multiple Run
Short Identifier=Multiple
Geom File=g01
Flow File=f01
Subcritical Flow
K Sum by GR= 0
Std Step Tol= 0.01
Critical Tol= 0.01
Num of Std Step Trials= 20
Max Error Tol= 0.3
Flow Tol Ratio= 0.001
Split Flow NTrial= 30
Split Flow Tol= 0.02
Split Flow Ratio= 0.02
Log Output Level= 0
Friction Slope Method= 1
Unsteady Friction Slope Method= 2
Unsteady Bridges Friction Slope Method= 1
Parabolic Critical Depth
Global Vel Dist=  1 , 1 , 1
Global Log Level= 0
CheckData=True
Encroach Param= -1, 0, 0, 0
BEGIN DESCRIPTION:
Multiple Run
END DESCRIPTION:

--- Bachelor Creek Trib 4_1.f01 (steady flow) ---

Flow Title=Multiple
Number of Profiles=7
Profile Names=10-year,25-year,50-year,1pct_min,100-year,1pct_plu,500-year
River Rch & RM= Bachelor Creek T,Reach-1,1692
     150     182     206     116     232     464     294
Boundary for River Rch & Prof#=Bachelor Creek T,Reach-1,1
Up Type=0
Dn Type=3
Dn Slope=0.005
Boundary for River Rch & Prof#=Bachelor Creek T,Reach-1,2
Up Type=0
Dn Type=3
Dn Slope=0.005
Boundary for River Rch & Prof#=Bachelor Creek T,Reach-1,3
Up Type=0
Dn Type=3
Dn Slope=0.005
Boundary for River Rch & Prof#=Bachelor Creek T,Reach-1,4
Up Type=0
Dn Type=3
Dn Slope=0.005
Boundary for River Rch & Prof#=Bachelor Creek T,Reach-1,5
Up Type=0
Dn Type=3
Dn Slope=0.005
Boundary for River Rch & Prof#=Bachelor Creek T,Reach-1,6
Up Type=0
Dn Type=3
Dn Slope=0.005
Boundary for River Rch & Prof#=Bachelor Creek T,Reach-1,7
Up Type=0
Dn Type=3
Dn Slope=0.005

--- Bachelor Creek Trib 4_1.g01 (geometry) ---

Geom Title=Existing Conditions

River Reach=Bachelor Creek T,Reach-1
Reach XY= 30
      2646126.00      6953761.00      2646094.46      6953760.93
      2646081.32      6953756.08      2646070.27      6953708.87
      2645986.92      6953620.37      2645978.74      6953604.48
      2645974.00      6953572.74      2645967.66      6953564.17
      2645891.35      6953560.41      2645873.64      6953555.44
      2645792.75      6953477.47      2645770.14      6953463.08
      2645627.47      6953457.44      2645524.53      6953364.54
      2645486.19      6953360.45      2645377.47      6953364.53
      2645355.84      6953380.60      2645229.41      6953503.18
      2645216.13      6953499.62      2645178.29      6953466.69
      2645151.00      6953460.79      2645123.71      6953466.69
      2645075.91      6953503.65      2645052.64      6953488.54
      2644889.00      6953324.68      2644874.04      6953315.01
      2644831.41      6953305.29      2644820.43      6953266.50
      2644807.39      6953261.43      2644776.00      6953261.00

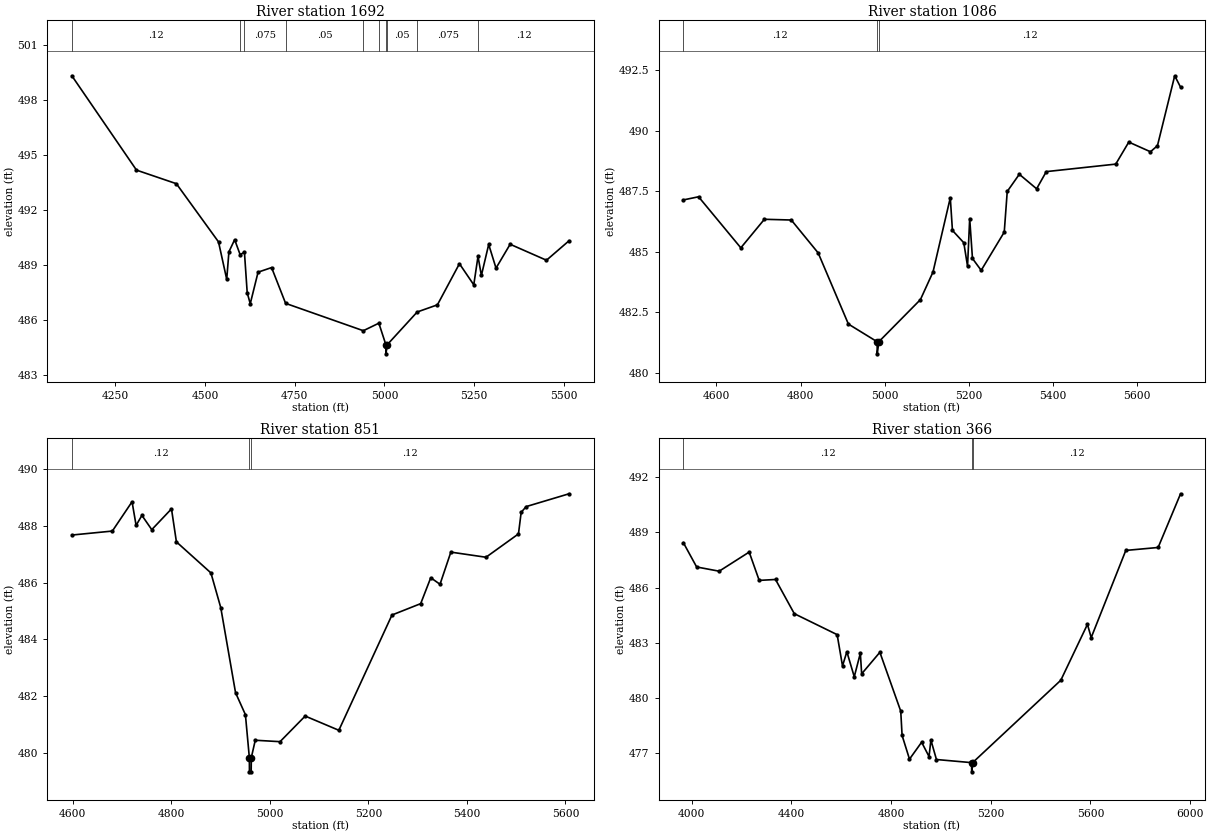
Type RM Length L Ch R = 1,1692,606,606,606
BEGIN DESCRIPTION:
Bachelor Creek Trib 4_1 3.0
END DESCRIPTION:
XS GIS Cut Line= 3
      2646843.70      6953333.41      2646081.32      6953756.08
      2645979.10      6954260.53
#Sta/Elev= 30
  4128.3  499.30  4308.6  494.16  4419.8  493.42  4537.3  490.25  4560.2  488.21
  4566.3  489.71  4582.3  490.37  4597.5  489.56  4609.6  489.68  4617.3  487.48
  4625.8  486.88  4647.6  488.60  4685.3  488.85  4724.4  486.90  4941.1  485.41
  4984.4  485.82  5003.9  484.65  5004.1  484.15  5007.9  484.65  5091.3  486.43
  5147.7  486.82  5209.1  489.06  5249.1  487.91  5260.9  489.46  5270.3  488.42
  5290.7  490.11  5311.1  488.82  5350.5  490.12  5451.8  489.25  5514.7  490.31
#Mann=10,-1,0
  4128.3    0.12       0  4597.5    0.05       0  4609.6   0.075       0
  4724.4    0.05       0  4941.1    0.12       0  4984.4    0.05       0
  5003.9    0.03       0  5007.9    0.05       0  5091.3   0.075       0
  5260.9    0.12       0
Bank Sta=5003.9,5007.9
Exp/Cntr=0.3,0.1

Type RM Length L Ch R = 1,1086,235,235,235
BEGIN DESCRIPTION:
Bachelor Creek Trib 4_1 2.0
END DESCRIPTION:
XS GIS Cut Line= 3
      2646002.05      6953155.73      2645631.86      6953458.92
      2645804.19      6954140.27
#Sta/Elev= 30
  4521.5  487.15  4557.6  487.28  4658.0  485.17  4714.0  486.35  4777.9  486.32
  4841.8  484.96  4913.6  482.02  4981.9  481.29  4982.1  480.79  4985.9  481.29
  5084.7  483.03  5114.6  484.17  5155.7  487.24  5160.8  485.89  5187.8  485.38
  5196.7  484.41  5201.8  486.38  5208.4  484.73  5229.1  484.24  5283.9  485.82
  5291.0  487.50  5319.7  488.21  5360.8  487.61  5383.8  488.32  5548.8  488.63
  5579.8  489.54  5631.3  489.14  5647.9  489.39  5688.9  492.28  5702.8  491.81
#Mann=3,-1,0
  4521.5    0.12       0  4981.9    0.07       0  4985.9    0.12       0
Bank Sta=4981.9,4985.9
Exp/Cntr=0.3,0.1

Type RM Length L Ch R = 1,851,485,485,485
BEGIN DESCRIPTION:
Mapping XS 1eb937b8
END DESCRIPTION:
XS GIS Cut Line= 3
      2645429.56      6952958.84      2645433.90      6953362.49
      2645550.93      6953956.29
#Sta/Elev= 30
  4598.3  487.67  4680.5  487.81  4720.5  488.84  4728.7  488.01  4740.5  488.36
  4760.5  487.86  4800.5  488.59  4810.5  487.43  4880.5  486.34  4900.5  485.12
  4930.5  482.13  4950.5  481.36  4958.5  479.85  4958.7  479.35  4962.2  479.35
  4962.5  479.85  4970.5  480.46  5020.8  480.41  5071.8  481.31  5140.1  480.81
  5247.9  484.86  5306.2  485.26  5326.6  486.17  5345.4  485.94  5367.4  487.07
  5438.7  486.89  5504.6  487.71  5510.1  488.47  5520.3  488.67  5607.2  489.12
#Mann=3,-1,0
  4598.3    0.12       0  4958.5    0.07       0  4962.5    0.12       0
Bank Sta=4958.5,4962.5
Exp/Cntr=0.3,0.1

Type RM Length L Ch R = 1,366,0,0,0
BEGIN DESCRIPTION:
Bachelor Creek Trib 4_1 1.0
END DESCRIPTION:
XS GIS Cut Line= 6
      2645649.04      6952886.21      2645290.30      6952852.08
      2645042.65      6953478.55      2644991.20      6953625.08
      2645242.93      6953861.62      2645629.22      6954113.36
#Sta/Elev= 30
  3966.0  488.44  4019.3  487.12  4109.7  486.89  4230.2  487.93  4270.4  486.39
  4335.9  486.44  4411.3  484.58  4583.3  483.44  4604.8  481.74  4622.3  482.51
  4652.0  481.15  4676.4  482.43  4681.7  481.31  4754.8  482.48  4838.6  479.28
  4844.0  477.96  4873.7  476.67  4922.4  477.59  4952.2  476.81  4959.6  477.71
  4981.9  476.65  5123.1  476.48  5123.3  475.98  5127.1  476.48  5481.1  480.96
  5588.0  484.00  5603.1  483.28  5742.0  488.02  5871.8  488.18  5961.8  491.10
#Mann=3,-1,0
  3966.0    0.12       0  5123.1    0.07       0  5127.1    0.12       0
Bank Sta=5123.1,5127.1
Exp/Cntr=0.3,0.1

Chan Stop Cuts=-1