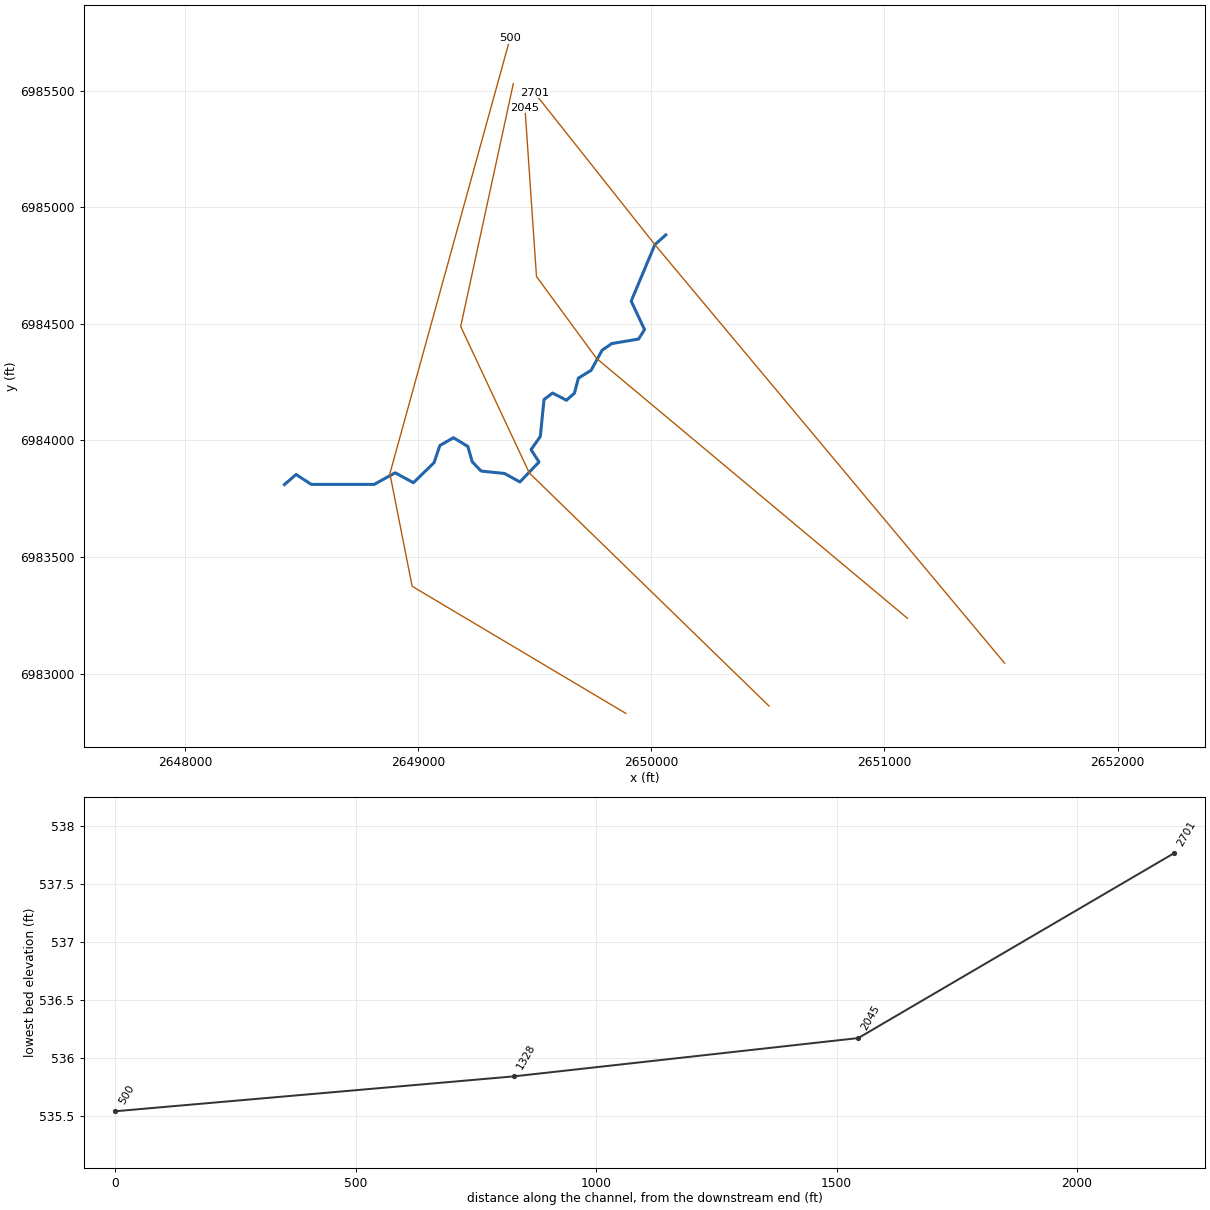
--- Bachelor Creek Trib 5.prj (project) ---

Proj Title=Bachelor Creek Trib 5 Base Level Engineering
Current Plan=p01
Default Exp/Contr=0.3,0.1
English Units
Geom File=g01
Flow File=f01
Plan File=p01
BEGIN DESCRIPTION:
Bachelor Creek Trib 5
END DESCRIPTION:

--- Bachelor Creek Trib 5.p01 (plan) ---

Plan Title=Multiple Run
Short Identifier=Multiple
Geom File=g01
Flow File=f01
Subcritical Flow
K Sum by GR= 0
Std Step Tol= 0.01
Critical Tol= 0.01
Num of Std Step Trials= 20
Max Error Tol= 0.3
Flow Tol Ratio= 0.001
Split Flow NTrial= 30
Split Flow Tol= 0.02
Split Flow Ratio= 0.02
Log Output Level= 0
Friction Slope Method= 1
Unsteady Friction Slope Method= 2
Unsteady Bridges Friction Slope Method= 1
Parabolic Critical Depth
Global Vel Dist=  1 , 1 , 1
Global Log Level= 0
CheckData=True
Encroach Param= -1, 0, 0, 0
BEGIN DESCRIPTION:
Multiple Run
END DESCRIPTION:

--- Bachelor Creek Trib 5.f01 (steady flow) ---

Flow Title=Multiple
Number of Profiles=7
Profile Names=10-year,25-year,50-year,1pct_min,100-year,1pct_plu,500-year
River Rch & RM= Bachelor Creek T,Reach-1,2701
     546     726     870     518    1034    2062    1455
Boundary for River Rch & Prof#=Bachelor Creek T,Reach-1,1
Up Type=0
Dn Type=3
Dn Slope=0.005
Boundary for River Rch & Prof#=Bachelor Creek T,Reach-1,2
Up Type=0
Dn Type=3
Dn Slope=0.005
Boundary for River Rch & Prof#=Bachelor Creek T,Reach-1,3
Up Type=0
Dn Type=3
Dn Slope=0.005
Boundary for River Rch & Prof#=Bachelor Creek T,Reach-1,4
Up Type=0
Dn Type=3
Dn Slope=0.005
Boundary for River Rch & Prof#=Bachelor Creek T,Reach-1,5
Up Type=0
Dn Type=3
Dn Slope=0.005
Boundary for River Rch & Prof#=Bachelor Creek T,Reach-1,6
Up Type=0
Dn Type=3
Dn Slope=0.005
Boundary for River Rch & Prof#=Bachelor Creek T,Reach-1,7
Up Type=0
Dn Type=3
Dn Slope=0.005

--- Bachelor Creek Trib 5.g01 (geometry) ---

Geom Title=Existing Conditions

River Reach=Bachelor Creek T,Reach-1
Reach XY= 30
      2650061.88      6984881.74      2650015.01      6984840.08
      2649913.44      6984597.89      2649970.74      6984475.49
      2649945.05      6984435.08      2649830.11      6984415.60
      2649788.44      6984386.95      2649741.57      6984301.01
      2649686.88      6984267.16      2649669.94      6984202.89
      2649635.86      6984172.68      2649575.75      6984203.55
      2649539.37      6984175.11      2649523.54      6984016.86
      2649483.81      6983960.90      2649518.01      6983907.63
      2649436.11      6983822.10      2649370.11      6983858.43
      2649269.55      6983868.74      2649231.75      6983908.46
      2649212.51      6983974.69      2649151.00      6984011.66
      2649092.50      6983978.23      2649067.83      6983904.94
      2648979.42      6983818.81      2648901.04      6983861.31
      2648810.79      6983811.54      2648541.15      6983811.60
      2648475.86      6983854.09      2648426.00      6983811.00

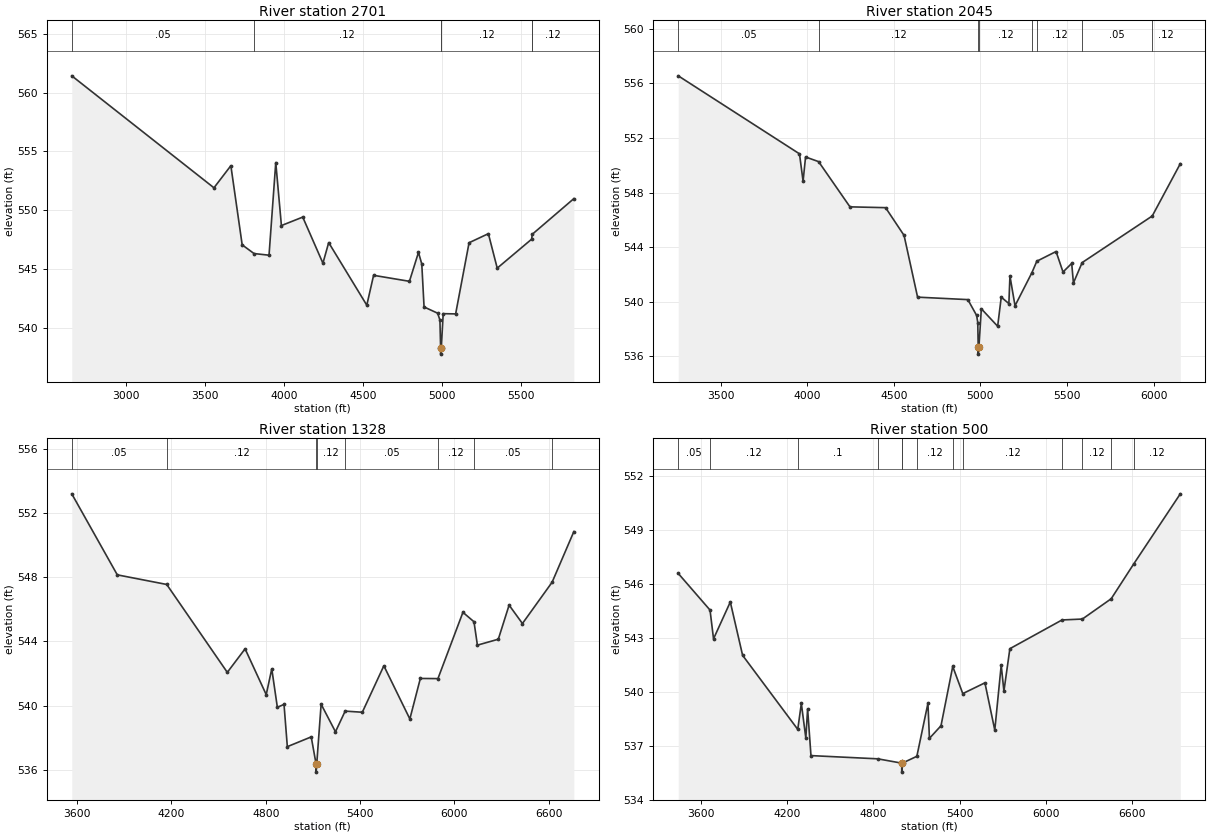
Type RM Length L Ch R = 1,2701,656,656,656
BEGIN DESCRIPTION:
Bachelor Creek Trib 5 4.0
END DESCRIPTION:
XS GIS Cut Line= 3
      2651515.42      6983044.55      2650015.01      6984840.08
      2649498.04      6985492.48
#Sta/Elev= 30
  2660.1  561.42  3558.5  551.90  3665.3  553.78  3736.8  547.05  3811.7  546.31
  3906.5  546.17  3949.0  554.05  3984.7  548.69  4119.4  549.41  4247.0  545.49
  4283.4  547.24  4524.2  541.92  4567.1  544.46  4793.6  543.95  4850.8  546.41
  4871.6  545.42  4886.0  541.77  4971.8  541.24  4986.2  540.66  4990.7  538.26
  4990.9  537.76  4994.7  538.26  5007.0  541.20  5085.5  541.18  5170.4  547.23
  5292.3  548.00  5348.3  545.07  5565.5  547.53  5569.8  547.95  5832.4  550.98
#Mann=6,-1,0
  2660.1    0.05       0  3811.7    0.12       0  4990.7    0.07       0
  4994.7    0.12       0  5565.5    0.05       0  5569.8    0.12       0
Bank Sta=4990.7,4994.7
Exp/Cntr=0.3,0.1

Type RM Length L Ch R = 1,2045,717,717,717
BEGIN DESCRIPTION:
Mapping XS 8b3b5f0b
END DESCRIPTION:
XS GIS Cut Line= 4
      2651098.29      6983237.28      2649764.96      6984351.85
      2649507.15      6984703.41      2649457.72      6985426.64
#Sta/Elev= 30
  3255.5  556.54  3955.5  550.83  3976.3  548.83  3990.6  550.60  4065.9  550.26
  4247.0  546.95  4452.6  546.89  4559.3  544.86  4637.4  540.34  4927.6  540.16
  4978.3  539.00  4984.8  538.48  4987.4  536.67  4987.6  536.17  4991.4  536.67
  5005.4  539.49  5099.6  538.21  5120.4  540.34  5164.4  539.87  5170.6  541.89
  5199.9  539.71  5297.7  542.14  5325.7  542.97  5436.9  543.68  5477.0  542.18
  5527.1  542.81  5537.1  541.38  5587.5  542.87  5992.1  546.28  6154.2  550.11
#Mann=8,-1,0
  3255.5    0.05       0  4065.9    0.12       0  4987.4    0.07       0
  4991.4    0.12       0  5297.7    0.05       0  5325.7    0.12       0
  5587.5    0.05       0  5992.1    0.12       0
Bank Sta=4987.4,4991.4
Exp/Cntr=0.3,0.1

Type RM Length L Ch R = 1,1328,828,828,828
BEGIN DESCRIPTION:
Bachelor Creek Trib 5 2.0
END DESCRIPTION:
XS GIS Cut Line= 4
      2650504.98      6982860.54      2649476.47      6983860.52
      2649182.06      6984489.02      2649407.76      6985530.71
#Sta/Elev= 30
  3565.5  553.22  3855.1  548.16  4169.6  547.56  4555.1  542.07  4668.2  543.54
  4802.7  540.68  4838.0  542.29  4873.5  539.89  4915.9  540.07  4937.0  537.43
  5089.0  538.04  5120.0  536.34  5120.2  535.84  5124.0  536.34  5152.0  540.08
  5243.3  538.36  5304.9  539.65  5414.1  539.58  5551.1  542.48  5716.5  539.16
  5783.3  541.69  5895.2  541.68  6054.2  545.82  6124.6  545.23  6146.3  543.77
  6279.3  544.14  6348.0  546.27  6432.8  545.12  6621.6  547.70  6759.9  550.86
#Mann=8,-1,0
  3565.5    0.05       0  4169.6    0.12       0  5120.0    0.07       0
  5124.0    0.12       0  5304.9    0.05       0  5895.2    0.12       0
  6124.6    0.05       0  6621.6    0.12       0
Bank Sta=5120,5124
Exp/Cntr=0.3,0.1

Type RM Length L Ch R = 1,500,0,0,0
BEGIN DESCRIPTION:
Bachelor Creek Trib 5 1.0
END DESCRIPTION:
XS GIS Cut Line= 4
      2649890.40      6982829.30      2648973.73      6983374.44
      2648878.27      6983857.78      2649393.86      6985725.11
#Sta/Elev= 30
  3440.8  546.60  3662.2  544.56  3686.6  542.96  3803.4  545.01  3889.1  542.04
  4273.1  537.92  4298.1  539.36  4329.3  537.44  4341.8  539.06  4365.1  536.46
  4830.4  536.28  4997.1  536.04  4997.3  535.54  5001.1  536.04  5102.5  536.42
  5179.7  539.37  5190.1  537.42  5270.6  538.12  5352.4  541.42  5422.3  539.91
  5576.5  540.51  5645.2  537.88  5689.9  541.49  5708.8  540.05  5750.3  542.41
  6113.6  544.01  6255.1  544.06  6455.9  545.19  6612.1  547.12  6937.2  551.03
#Mann=13,-1,0
  3440.8    0.05       0  3662.2    0.12       0  4273.1     0.1       0
  4830.4    0.05       0  4997.1    0.03       0  5001.1    0.05       0
  5102.5    0.12       0  5352.4    0.05       0  5422.3    0.12       0
  6113.6    0.05       0  6255.1    0.12       0  6455.9    0.05       0
  6612.1    0.12       0
Bank Sta=4997.1,5001.1
Exp/Cntr=0.3,0.1

Chan Stop Cuts=-1