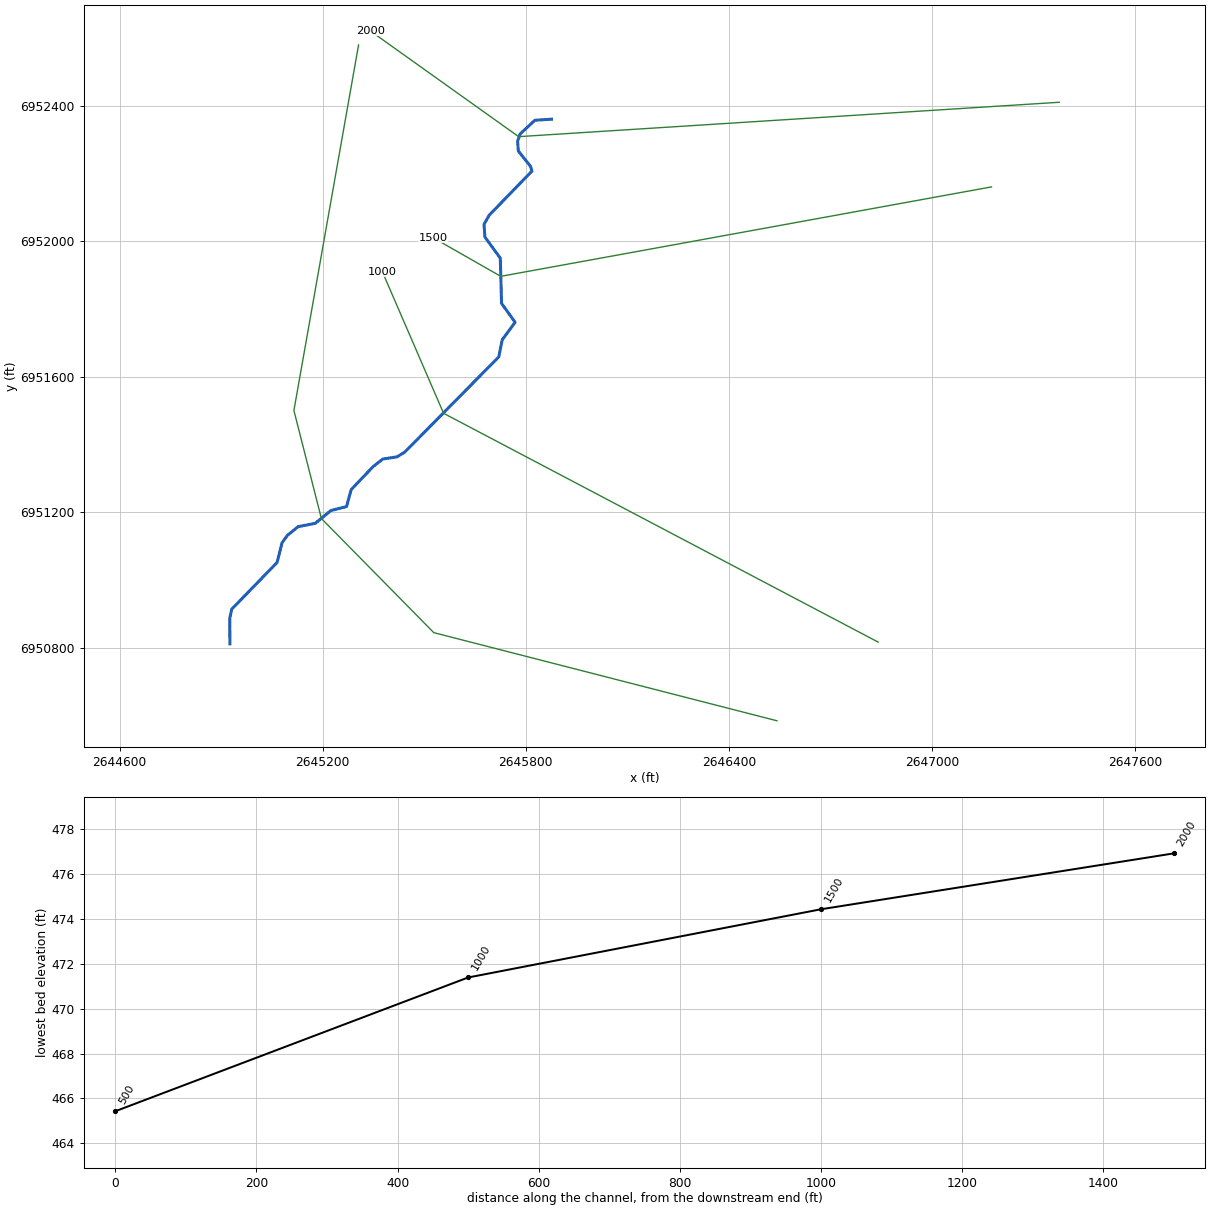
--- Bachelor Creek Trib 6.prj (project) ---

Proj Title=Bachelor Creek Trib 6 Base Level Engineering
Current Plan=p01
Default Exp/Contr=0.3,0.1
English Units
Geom File=g01
Flow File=f01
Plan File=p01
BEGIN DESCRIPTION:
Bachelor Creek Trib 6
END DESCRIPTION:

--- Bachelor Creek Trib 6.p01 (plan) ---

Plan Title=Multiple Run
Short Identifier=Multiple
Geom File=g01
Flow File=f01
Subcritical Flow
K Sum by GR= 0
Std Step Tol= 0.01
Critical Tol= 0.01
Num of Std Step Trials= 20
Max Error Tol= 0.3
Flow Tol Ratio= 0.001
Split Flow NTrial= 30
Split Flow Tol= 0.02
Split Flow Ratio= 0.02
Log Output Level= 0
Friction Slope Method= 1
Unsteady Friction Slope Method= 2
Unsteady Bridges Friction Slope Method= 1
Parabolic Critical Depth
Global Vel Dist=  1 , 1 , 1
Global Log Level= 0
CheckData=True
Encroach Param= -1, 0, 0, 0
BEGIN DESCRIPTION:
Multiple Run
END DESCRIPTION:

--- Bachelor Creek Trib 6.f01 (steady flow) ---

Flow Title=Multiple
Number of Profiles=7
Profile Names=10-year,25-year,50-year,1pct_min,100-year,1pct_plu,500-year
River Rch & RM= Bachelor Creek T,Reach-1,2000
     300     386     452     264     528    1053     715
Boundary for River Rch & Prof#=Bachelor Creek T,Reach-1,1
Up Type=0
Dn Type=3
Dn Slope=0.005
Boundary for River Rch & Prof#=Bachelor Creek T,Reach-1,2
Up Type=0
Dn Type=3
Dn Slope=0.005
Boundary for River Rch & Prof#=Bachelor Creek T,Reach-1,3
Up Type=0
Dn Type=3
Dn Slope=0.005
Boundary for River Rch & Prof#=Bachelor Creek T,Reach-1,4
Up Type=0
Dn Type=3
Dn Slope=0.005
Boundary for River Rch & Prof#=Bachelor Creek T,Reach-1,5
Up Type=0
Dn Type=3
Dn Slope=0.005
Boundary for River Rch & Prof#=Bachelor Creek T,Reach-1,6
Up Type=0
Dn Type=3
Dn Slope=0.005
Boundary for River Rch & Prof#=Bachelor Creek T,Reach-1,7
Up Type=0
Dn Type=3
Dn Slope=0.005

--- Bachelor Creek Trib 6.g01 (geometry) ---

Geom Title=Existing Conditions

River Reach=Bachelor Creek T,Reach-1
Reach XY= 30
      2645876.00      6952361.00      2645826.94      6952357.86
      2645783.23      6952317.30      2645775.91      6952295.73
      2645777.97      6952267.06      2645814.62      6952220.87
      2645818.18      6952207.59      2645692.22      6952077.68
      2645676.60      6952050.38      2645679.34      6952012.75
      2645724.75      6951950.50      2645728.47      6951816.86
      2645768.47      6951760.99      2645730.45      6951709.35
      2645720.19      6951658.71      2645442.67      6951377.65
      2645419.95      6951363.54      2645377.64      6951357.03
      2645349.12      6951334.72      2645284.28      6951266.77
      2645270.39      6951216.59      2645224.14      6951204.76
      2645178.20      6951167.10      2645127.42      6951157.14
      2645095.63      6951131.47      2645079.89      6951109.57
      2645065.21      6951051.34      2644931.35      6950913.50
      2644925.41      6950886.25      2644926.00      6950811.00

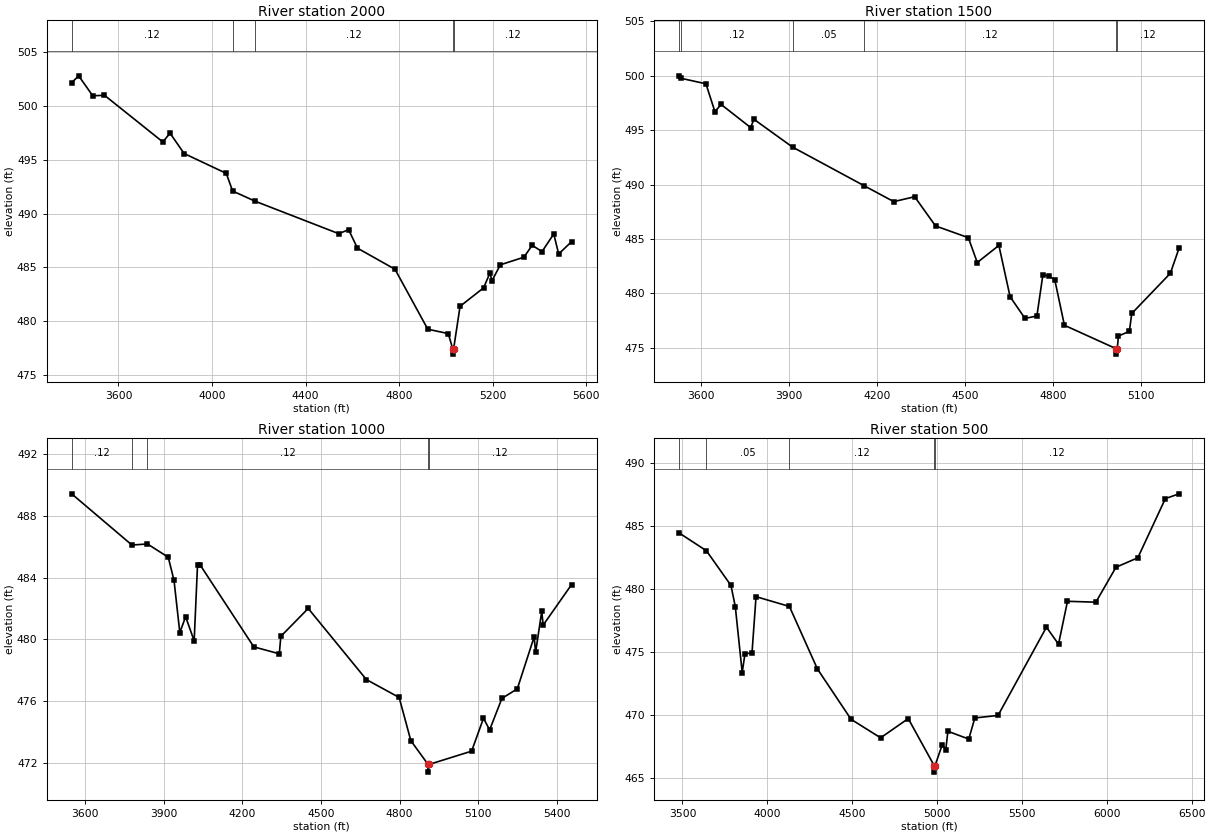
Type RM Length L Ch R = 1,2000,500,500,500
BEGIN DESCRIPTION:
Bachelor Creek Trib 6 4.0
END DESCRIPTION:
XS GIS Cut Line= 3
      2647375.99      6952411.00      2645778.92      6952309.41
      2645340.88      6952621.78
#Sta/Elev= 30
  3399.7  502.18  3429.7  502.82  3489.9  500.96  3540.0  501.01  3789.5  496.67
  3820.5  497.48  3880.7  495.59  4061.0  493.74  4088.1  492.10  4184.4  491.15
  4542.0  488.13  4584.1  488.50  4622.2  486.78  4782.5  484.82  4922.8  479.24
  5010.5  478.83  5029.4  477.42  5029.7  476.92  5033.4  477.42  5060.9  481.37
  5161.7  483.09  5188.8  484.48  5197.4  483.74  5233.0  485.23  5333.8  485.94
  5369.5  487.05  5411.3  486.46  5461.7  488.10  5482.6  486.24  5538.0  487.39
#Mann=5,-1,0
  3399.7    0.12       0  4088.1    0.05       0  4184.4    0.12       0
  5029.4    0.07       0  5033.4    0.12       0
Bank Sta=5029.4,5033.4
Exp/Cntr=0.3,0.1

Type RM Length L Ch R = 1,1500,500,500,500
BEGIN DESCRIPTION:
Bachelor Creek Trib 6 3.0
END DESCRIPTION:
XS GIS Cut Line= 3
      2647175.98      6952161.00      2645726.16      6951896.77
      2645525.96      6952011.02
#Sta/Elev= 30
  3526.3  499.98  3533.2  499.75  3617.8  499.25  3648.3  496.70  3669.7  497.35
  3770.2  495.23  3781.4  495.99  3912.9  493.44  4157.1  489.89  4258.1  488.43
  4329.3  488.88  4400.4  486.20  4512.3  485.12  4542.7  482.84  4616.4  484.41
  4654.6  479.70  4705.4  477.71  4746.0  477.93  4766.4  481.71  4786.7  481.61
  4807.0  481.25  4839.8  477.08  5016.0  474.93  5016.3  474.43  5020.0  474.93
  5023.8  476.09  5061.2  476.52  5069.3  478.16  5200.9  481.85  5230.5  484.15
#Mann=6,-1,0
  3526.3    0.05       0  3533.2    0.12       0  3912.9    0.05       0
  4157.1    0.12       0  5016.0    0.07       0  5020.0    0.12       0
Bank Sta=5016,5020
Exp/Cntr=0.3,0.1

Type RM Length L Ch R = 1,1000,500,500,500
BEGIN DESCRIPTION:
Bachelor Creek Trib 6 2.0
END DESCRIPTION:
XS GIS Cut Line= 3
      2646840.72      6950816.34      2645557.16      6951492.14
      2645375.98      6951911.04
#Sta/Elev= 30
  3549.4  489.43  3779.3  486.11  3838.5  486.18  3917.8  485.32  3939.8  483.82
  3961.9  480.44  3984.2  481.46  4016.7  479.90  4029.4  484.79  4038.7  484.84
  4244.1  479.51  4341.5  479.06  4347.2  480.19  4451.7  482.00  4673.6  477.39
  4798.6  476.23  4843.1  473.43  4908.9  471.89  4909.1  471.39  4912.9  471.89
  5075.0  472.75  5120.2  474.88  5143.7  474.13  5190.6  476.17  5249.3  476.79
  5313.5  480.16  5319.0  479.15  5342.5  481.81  5347.9  480.92  5456.4  483.55
#Mann=5,-1,0
  3549.4    0.12       0  3779.3    0.05       0  3838.5    0.12       0
  4908.9    0.07       0  4912.9    0.12       0
Bank Sta=4908.9,4912.9
Exp/Cntr=0.3,0.1

Type RM Length L Ch R = 1,500,0,0,0
BEGIN DESCRIPTION:
Bachelor Creek Trib 6 1.0
END DESCRIPTION:
XS GIS Cut Line= 5
      2646542.09      6950583.71      2645528.22      6950844.12
      2645196.16      6951181.27      2645115.02      6951500.37
      2645306.00      6952580.26
#Sta/Elev= 30
  3480.0  484.46  3641.2  483.04  3785.7  480.28  3811.2  478.60  3851.9  473.35
  3868.3  474.86  3909.6  474.90  3933.4  479.39  4130.1  478.61  4295.0  473.64
  4493.5  469.63  4667.6  468.16  4830.3  469.69  4983.7  465.93  4984.0  465.43
  4987.7  465.93  5030.7  467.61  5051.3  467.21  5064.1  468.68  5186.9  468.06
  5222.7  469.74  5359.4  469.94  5644.7  476.96  5715.8  475.61  5768.6  479.02
  5936.0  478.95  6054.3  481.73  6182.9  482.48  6345.4  487.19  6425.9  487.57
#Mann=5,-1,0
  3480.0    0.12       0  3641.2    0.05       0  4130.1    0.12       0
  4983.7    0.07       0  4987.7    0.12       0
Bank Sta=4983.7,4987.7
Exp/Cntr=0.3,0.1

Chan Stop Cuts=-1