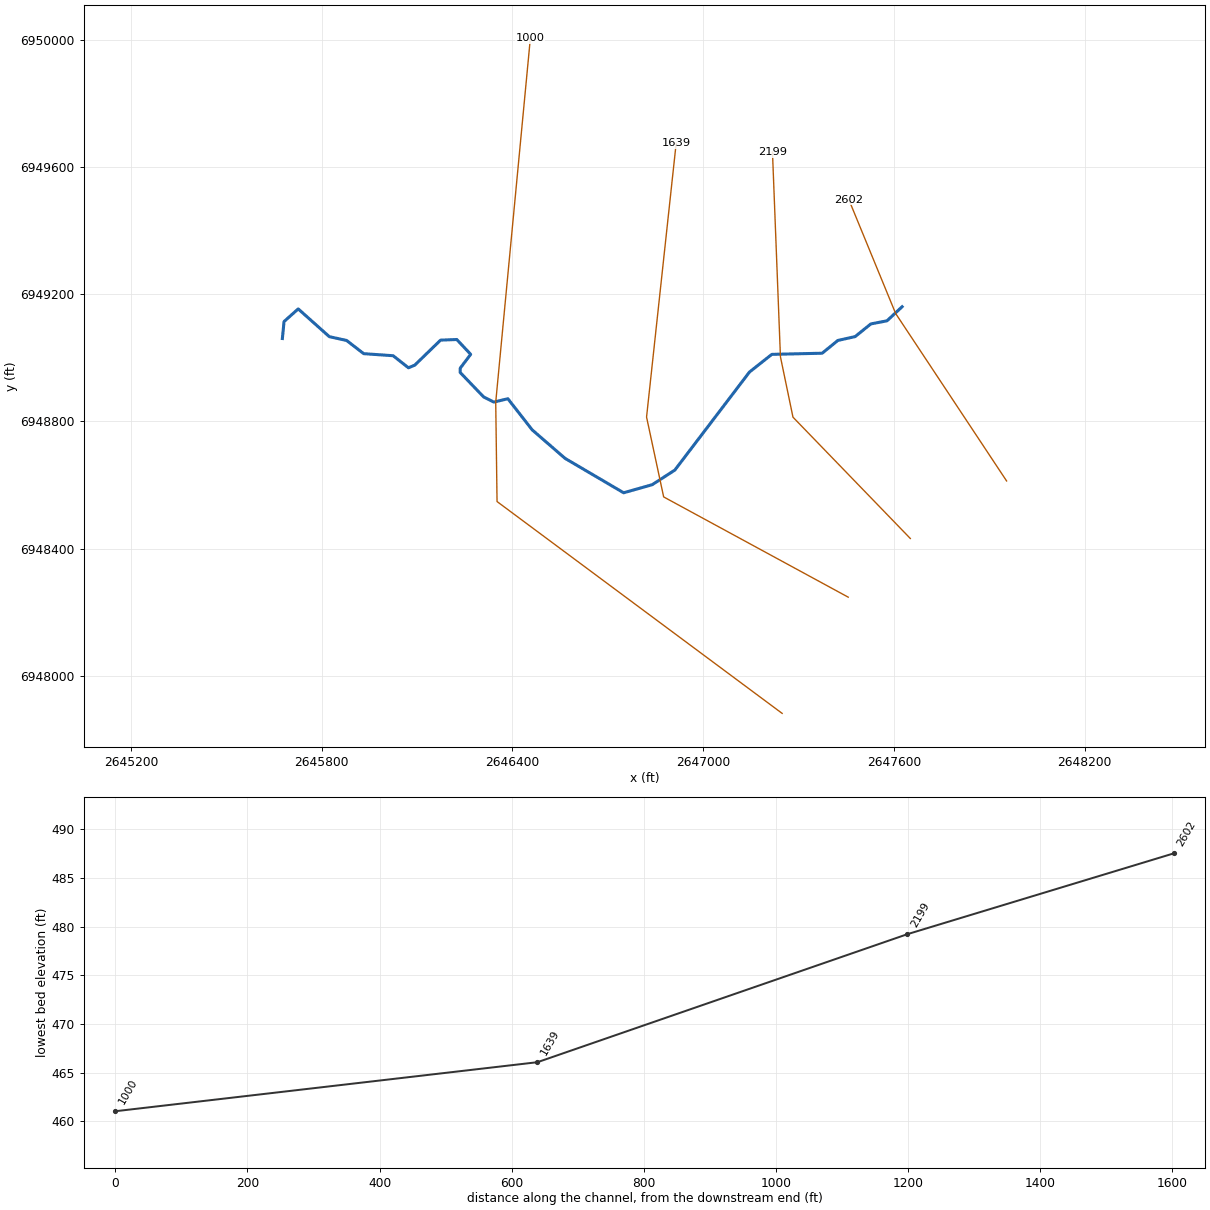
--- Bachelor Creek Trib 7.prj (project) ---

Proj Title=Bachelor Creek Trib 7 Base Level Engineering
Current Plan=p01
Default Exp/Contr=0.3,0.1
English Units
Geom File=g01
Flow File=f01
Plan File=p01
BEGIN DESCRIPTION:
Bachelor Creek Trib 7
END DESCRIPTION:

--- Bachelor Creek Trib 7.p01 (plan) ---

Plan Title=Multiple Run
Short Identifier=Multiple
Geom File=g01
Flow File=f01
Subcritical Flow
K Sum by GR= 0
Std Step Tol= 0.01
Critical Tol= 0.01
Num of Std Step Trials= 20
Max Error Tol= 0.3
Flow Tol Ratio= 0.001
Split Flow NTrial= 30
Split Flow Tol= 0.02
Split Flow Ratio= 0.02
Log Output Level= 0
Friction Slope Method= 1
Unsteady Friction Slope Method= 2
Unsteady Bridges Friction Slope Method= 1
Parabolic Critical Depth
Global Vel Dist=  1 , 1 , 1
Global Log Level= 0
CheckData=True
Encroach Param= -1, 0, 0, 0
BEGIN DESCRIPTION:
Multiple Run
END DESCRIPTION:

--- Bachelor Creek Trib 7.f01 (steady flow) ---

Flow Title=Multiple
Number of Profiles=7
Profile Names=10-year,25-year,50-year,1pct_min,100-year,1pct_plu,500-year
River Rch & RM= Bachelor Creek T,Reach-1,2602
     197     247     284     164     327     652     428
Boundary for River Rch & Prof#=Bachelor Creek T,Reach-1,1
Up Type=0
Dn Type=3
Dn Slope=0.005
Boundary for River Rch & Prof#=Bachelor Creek T,Reach-1,2
Up Type=0
Dn Type=3
Dn Slope=0.005
Boundary for River Rch & Prof#=Bachelor Creek T,Reach-1,3
Up Type=0
Dn Type=3
Dn Slope=0.005
Boundary for River Rch & Prof#=Bachelor Creek T,Reach-1,4
Up Type=0
Dn Type=3
Dn Slope=0.005
Boundary for River Rch & Prof#=Bachelor Creek T,Reach-1,5
Up Type=0
Dn Type=3
Dn Slope=0.005
Boundary for River Rch & Prof#=Bachelor Creek T,Reach-1,6
Up Type=0
Dn Type=3
Dn Slope=0.005
Boundary for River Rch & Prof#=Bachelor Creek T,Reach-1,7
Up Type=0
Dn Type=3
Dn Slope=0.005

--- Bachelor Creek Trib 7.g01 (geometry) ---

Geom Title=Existing Conditions

River Reach=Bachelor Creek T,Reach-1
Reach XY= 30
      2647626.00      6949161.00      2647578.36      6949116.67
      2647527.67      6949106.96      2647478.20      6949067.07
      2647423.82      6949054.88      2647374.45      6949014.75
      2647215.95      6949011.11      2647145.70      6948955.50
      2646910.89      6948647.02      2646839.52      6948600.98
      2646749.74      6948575.66      2646565.57      6948683.85
      2646461.98      6948773.64      2646385.52      6948871.55
      2646341.32      6948860.95      2646309.25      6948877.22
      2646235.30      6948954.32      2646235.62      6948967.68
      2646268.53      6949011.28      2646224.82      6949057.90
      2646173.76      6949055.91      2646092.69      6948977.33
      2646072.78      6948968.88      2646024.50      6949006.90
      2645931.97      6949013.33      2645878.17      6949054.86
      2645823.70      6949066.86      2645725.83      6949154.17
      2645681.31      6949114.37      2645676.00      6949061.00

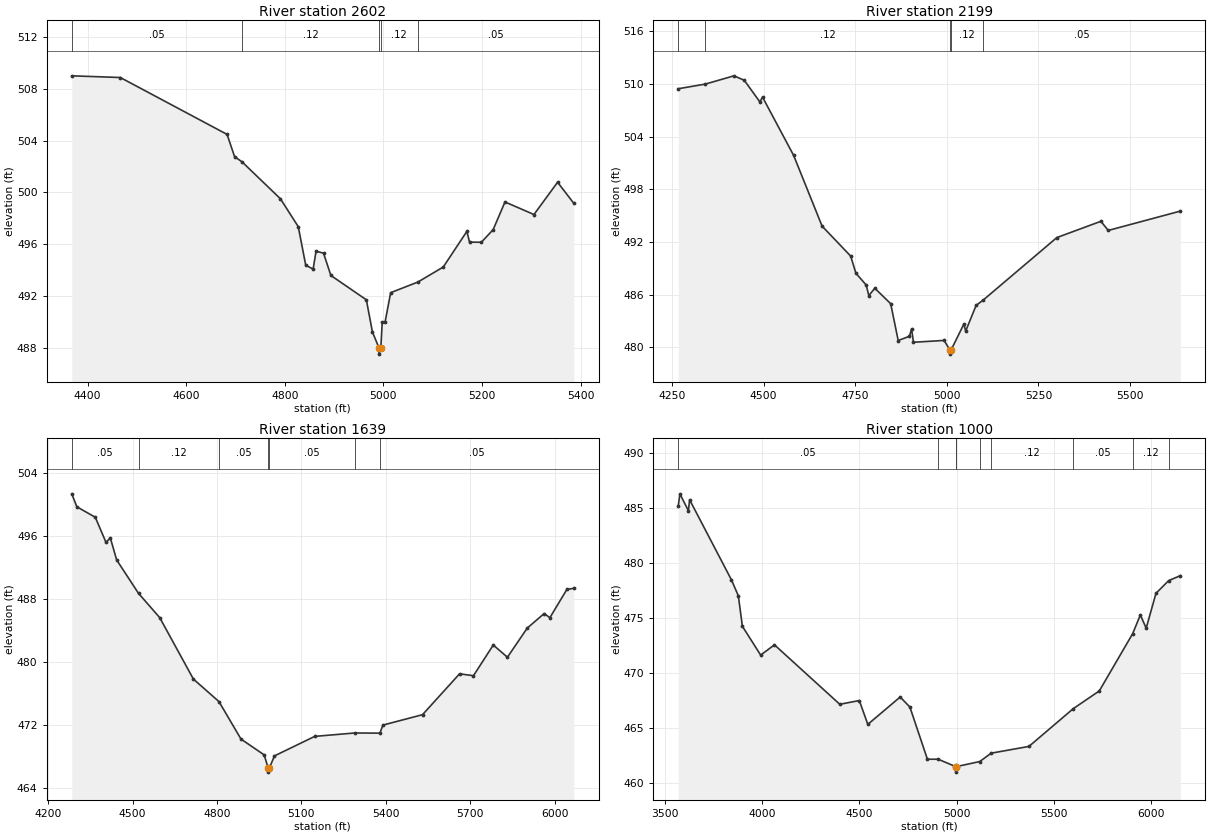
Type RM Length L Ch R = 1,2602,403,403,403
BEGIN DESCRIPTION:
Bachelor Creek Trib 7 4.0
END DESCRIPTION:
XS GIS Cut Line= 3
      2647954.74      6948612.84      2647605.61      6949139.78
      2647458.71      6949497.16
#Sta/Elev= 30
  4367.9  509.00  4466.4  508.87  4683.0  504.48  4698.1  502.77  4713.4  502.36
  4791.3  499.51  4827.4  497.36  4842.5  494.39  4857.5  494.09  4863.5  495.47
  4878.6  495.32  4893.5  493.60  4965.5  491.72  4977.8  489.24  4990.9  488.03
  4991.1  487.53  4994.9  488.03  4997.7  489.99  5003.4  489.99  5014.8  492.27
  5070.0  493.09  5121.5  494.25  5169.4  497.00  5174.8  496.17  5198.8  496.16
  5222.8  497.14  5246.7  499.27  5305.5  498.30  5353.4  500.79  5386.4  499.16
#Mann=5,-1,0
  4367.9    0.05       0  4713.4    0.12       0  4990.9    0.07       0
  4994.9    0.12       0  5070.0    0.05       0
Bank Sta=4990.9,4994.9
Exp/Cntr=0.3,0.1

Type RM Length L Ch R = 1,2199,560,560,560
BEGIN DESCRIPTION:
Mapping XS 2243881e
END DESCRIPTION:
XS GIS Cut Line= 4
      2647651.81      6948431.81      2647282.58      6948813.58
      2647243.15      6949003.58      2647218.11      6949647.44
#Sta/Elev= 30
  4267.4  509.44  4341.4  509.97  4419.3  510.91  4447.6  510.40  4490.1  507.94
  4497.3  508.49  4582.2  501.85  4659.8  493.80  4737.8  490.39  4751.9  488.45
  4780.2  487.09  4787.2  485.89  4803.6  486.73  4846.9  484.97  4867.4  480.78
  4898.0  481.26  4903.9  482.10  4909.0  480.58  4992.6  480.79  5008.0  479.73
  5008.2  479.23  5012.0  479.73  5046.5  482.65  5051.5  481.86  5080.0  484.78
  5099.7  485.40  5300.2  492.50  5420.3  494.35  5440.3  493.31  5636.9  495.51
#Mann=5,-1,0
  4267.4    0.05       0  4341.4    0.12       0  5008.0    0.07       0
  5012.0    0.12       0  5099.7    0.05       0
Bank Sta=5008,5012
Exp/Cntr=0.3,0.1

Type RM Length L Ch R = 1,1639,639,639,639
BEGIN DESCRIPTION:
Bachelor Creek Trib 7 3.0
END DESCRIPTION:
XS GIS Cut Line= 4
      2647456.43      6948247.18      2646875.70      6948562.64
      2646821.92      6948813.96      2646915.14      6949675.75
#Sta/Elev= 30
  4283.7  501.34  4301.7  499.70  4367.3  498.37  4405.3  495.19  4420.8  495.75
  4443.3  492.96  4520.9  488.73  4596.3  485.65  4716.1  477.86  4806.9  475.01
  4885.2  470.26  4967.8  468.25  4981.8  466.57  4982.1  466.07  4985.8  466.57
  5004.3  468.13  5147.4  470.60  5289.4  471.03  5379.0  471.01  5389.7  472.03
  5530.5  473.35  5662.2  478.53  5711.6  478.29  5782.0  482.18  5832.3  480.63
  5902.7  484.32  5963.0  486.17  5983.2  485.64  6043.5  489.22  6068.4  489.37
#Mann=7,-1,0
  4283.7    0.05       0  4520.9    0.12       0  4806.9    0.05       0
  4981.8    0.03       0  4985.8    0.05       0  5289.4    0.12       0
  5379.0    0.05       0
Bank Sta=4981.8,4985.8
Exp/Cntr=0.3,0.1

Type RM Length L Ch R = 1,1000,0,0,0
BEGIN DESCRIPTION:
Bachelor Creek Trib 7 2.0
END DESCRIPTION:
XS GIS Cut Line= 4
      2647248.50      6947881.54      2646351.48      6948548.03
      2646347.33      6948860.58      2646456.27      6950005.51
#Sta/Elev= 30
  3569.9  485.12  3578.3  486.26  3622.2  484.73  3628.4  485.72  3843.3  478.46
  3878.7  477.02  3899.6  474.25  3993.5  471.64  4064.4  472.57  4400.2  467.18
  4500.4  467.52  4544.2  465.36  4710.4  467.84  4760.4  466.93  4850.4  462.20
  4905.6  462.20  4995.7  461.53  4996.0  461.03  4999.7  461.53  5119.3  461.99
  5178.6  462.75  5372.1  463.36  5599.7  466.78  5733.7  468.39  5905.5  473.59
  5944.7  475.28  5974.8  474.08  6025.0  477.24  6090.1  478.39  6150.1  478.84
#Mann=9,-1,0
  3569.9    0.05       0  4905.6    0.12       0  4995.7    0.07       0
  4999.7    0.12       0  5119.3    0.05       0  5178.6    0.12       0
  5599.7    0.05       0  5905.5    0.12       0  6090.1    0.05       0
Bank Sta=4995.7,4999.7
Exp/Cntr=0.3,0.1

Chan Stop Cuts=-1