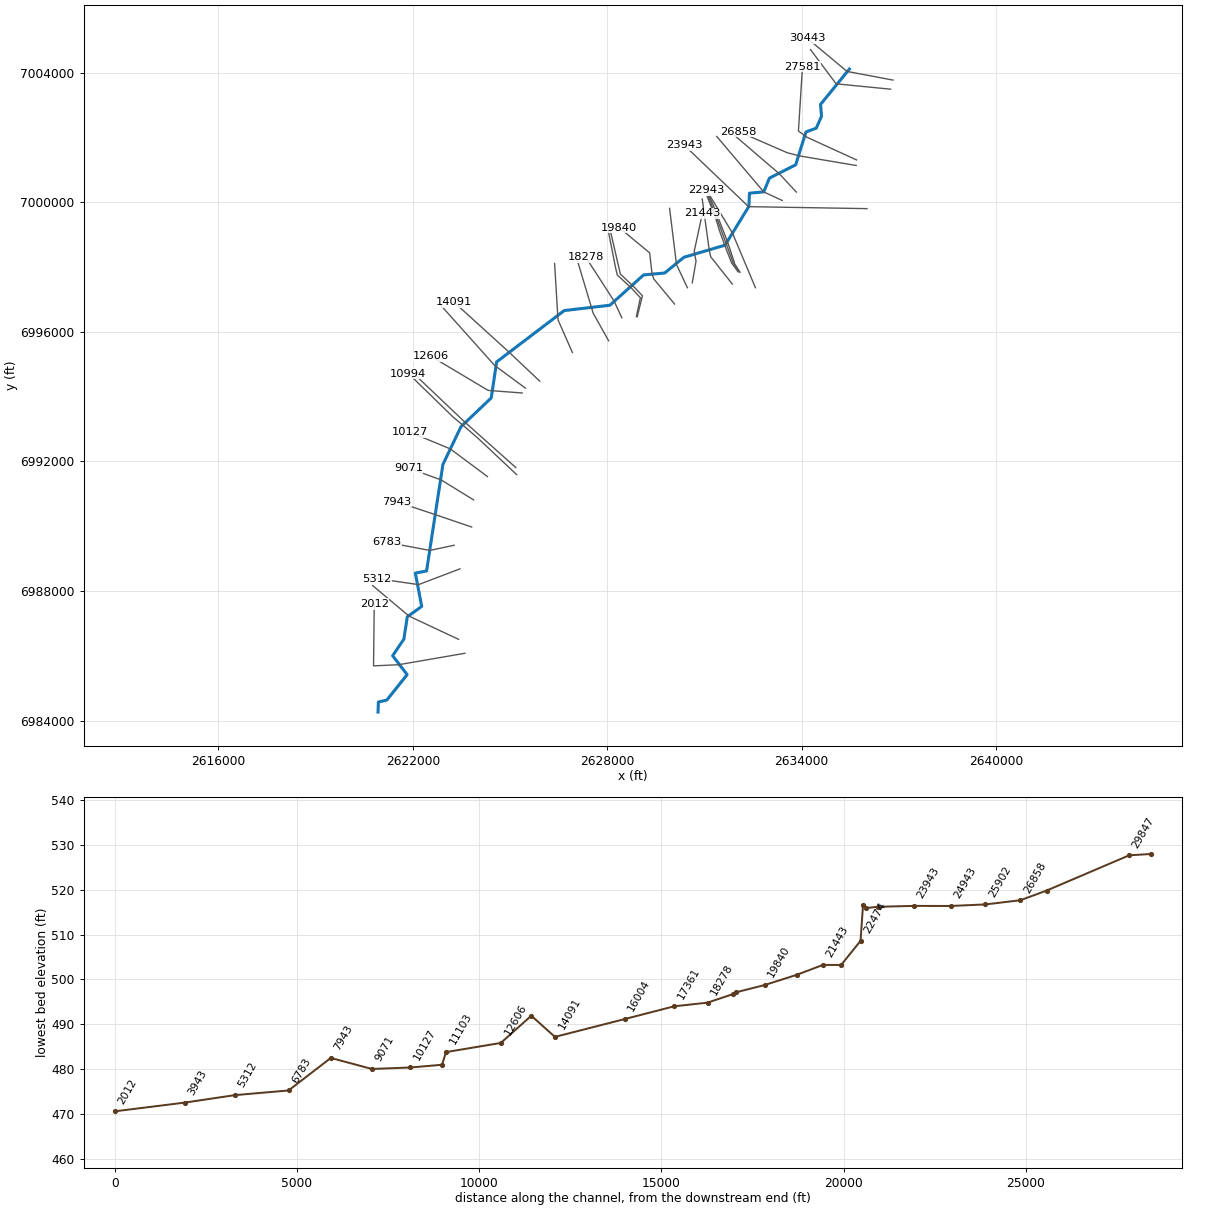
--- Berry Creek.prj (project) ---

Proj Title=Berry Creek Base Level Engineering
Current Plan=p01
Default Exp/Contr=0.3,0.1
English Units
Geom File=g01
Flow File=f01
Plan File=p01
Y Axis Title=Elevation
X Axis Title(PF)=Main Channel Distance
X Axis Title(XS)=Station
BEGIN DESCRIPTION:
Berry Creek
END DESCRIPTION:
DSS Export Rating Curves= 0
DSS Export Rating Curve Sorted= 0
DSS Export Volume Flow Curves= 0
DXF OffsetX= 0
DXF OffsetY= 0
DXF ScaleX= 1
DXF ScaleY= 10

--- Berry Creek.p01 (plan) ---

Plan Title=Multiple Run
Short Identifier=Multiple
Geom File=g01
Flow File=f01
Subcritical Flow
K Sum by GR= 0
Std Step Tol= 0.01
Critical Tol= 0.01
Num of Std Step Trials= 20
Max Error Tol= 0.3
Flow Tol Ratio= 0.001
Split Flow NTrial= 30
Split Flow Tol= 0.02
Split Flow Ratio= 0.02
Log Output Level= 0
Friction Slope Method= 1
Unsteady Friction Slope Method= 2
Unsteady Bridges Friction Slope Method= 1
Parabolic Critical Depth
Global Vel Dist=  1 , 1 , 1
Global Log Level= 0
CheckData=True
Encroach Param= -1, 0, 0, 0
BEGIN DESCRIPTION:
Multiple Run
END DESCRIPTION:

--- Berry Creek.f01 (steady flow) ---

Flow Title=Multiple
Program Version=4.10
Number of Profiles= 7
Profile Names=10-year,25-year,50-year,1pct_min,100-year,1pct_plu,500-year
River Rch & RM=Berry Creek,Reach-1         ,30443
     331     424     497     289     577    1150     775
River Rch & RM=Berry Creek,Reach-1         ,27581
     370     477     560     327     652    1301     881
River Rch & RM=Berry Creek,Reach-1         ,26858
     400     517     609     356     710    1416     963
River Rch & RM=Berry Creek,Reach-1         ,25902
     415     538     633     370     739    1474    1003
River Rch & RM=Berry Creek,Reach-1         ,22943
     689     923    1111     663    1323    2640    1875
River Rch & RM=Berry Creek,Reach-1         ,21943
     696     932    1122     669    1335    2665    1891
River Rch & RM=Berry Creek,Reach-1         ,20728
     699     936    1127     672    1342    2677    1900
River Rch & RM=Berry Creek,Reach-1         ,19840
     717     961    1158     691    1379    2751    1955
River Rch & RM=Berry Creek,Reach-1         ,19059
     849    1147    1388     831    1659    3309    2370
River Rch & RM=Berry Creek,Reach-1         ,14091
    1337    1847    2270    1378    2750    5488    4040
River Rch & RM=Berry Creek,Reach-1         ,11103
    1397    1932    2375    1442    2878    5742    4228
River Rch & RM=Berry Creek,Reach-1         ,10127
    1397    1932    2375    1442    2878    5742    4228
River Rch & RM=Berry Creek,Reach-1         ,6783
    1500    2074    2549    1547    3087    6160    4532
Boundary for River Rch & Prof#=Berry Creek,Reach-1         , 1
Up Type= 0
Dn Type= 3
Dn Slope=0.00105
Boundary for River Rch & Prof#=Berry Creek,Reach-1         , 2
Up Type= 0
Dn Type= 3
Dn Slope=0.00105
Boundary for River Rch & Prof#=Berry Creek,Reach-1         , 3
Up Type= 0
Dn Type= 3
Dn Slope=0.00105
Boundary for River Rch & Prof#=Berry Creek,Reach-1         , 4
Up Type= 0
Dn Type= 3
Dn Slope=0.00105
Boundary for River Rch & Prof#=Berry Creek,Reach-1         , 5
Up Type= 0
Dn Type= 3
Dn Slope=0.00105
Boundary for River Rch & Prof#=Berry Creek,Reach-1         , 6
Up Type= 0
Dn Type= 3
Dn Slope=0.00105
Boundary for River Rch & Prof#=Berry Creek,Reach-1         , 7
Up Type= 0
Dn Type= 3
Dn Slope=0.00105
DSS Import GetInterval= 0
DSS Import GetPeak= 0
DSS Import FillOption= 0

--- Berry Creek.g01 (geometry) ---

Geom Title=Existing Conditions

River Reach=Berry Creek,Reach-1
Reach XY= 30
      2635476.00      7004111.00      2634585.06      7003018.00
      2634616.70      7002654.33      2634453.30      7002287.09
      2634134.99      7002168.07      2633817.86      7001154.91
      2633008.96      7000744.76      2632832.38      7000318.98
      2632392.43      7000278.62      2632372.51      6999869.48
      2631639.56      6998674.49      2630369.40      6998301.44
      2629774.53      6997814.54      2629123.54      6997755.54
      2628083.00      6996819.83      2626673.53      6996655.55
      2624586.78      6995070.68      2624420.37      6993958.64
      2623486.76      6993070.68      2622928.33      6991905.03
      2622424.03      6988616.65      2622077.04      6988550.90
      2622274.49      6987522.87      2621829.51      6987202.52
      2621722.86      6986512.64      2621376.87      6986000.67
      2621824.39      6985417.04      2621196.16      6984630.60
      2620936.32      6984571.18      2620926.00      6984261.00

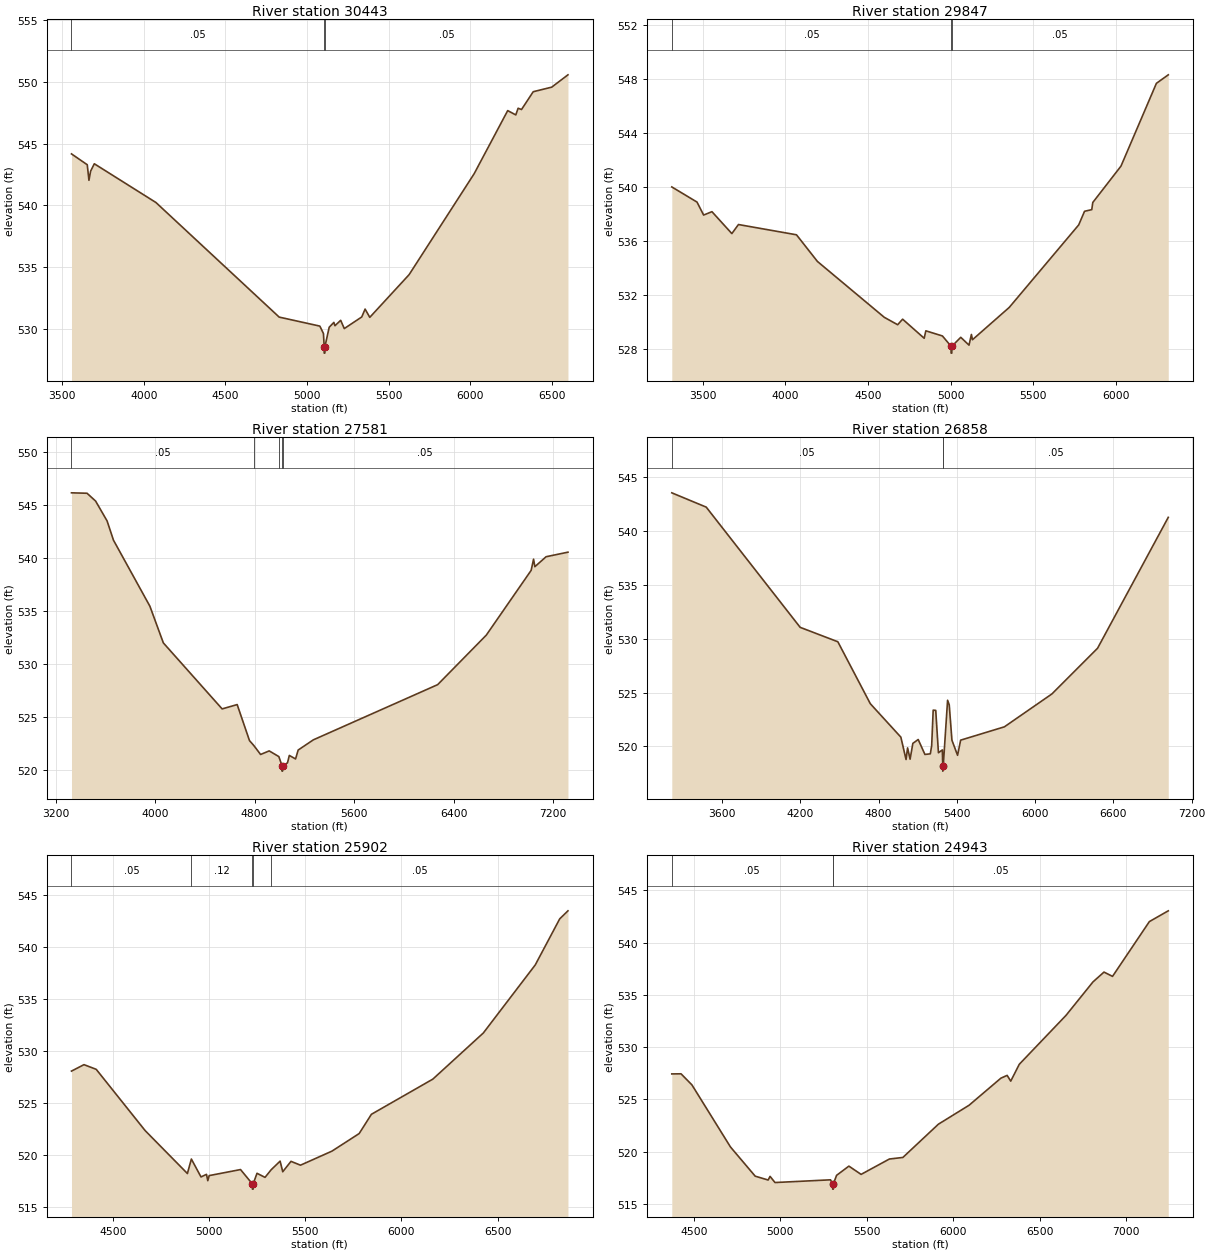
Type RM Length L Ch R = 1,30443,596,596,596
BEGIN DESCRIPTION:
Berry Creek 64.0
END DESCRIPTION:
XS GIS Cut Line= 3
      2636821.04      7003770.64      2635402.75      7004037.63
      2634175.97      7005061.02
#Sta/Elev= 30
  3556.8  544.17  3653.5  543.29  3663.7  542.03  3673.9  542.77  3696.6  543.37
  4074.0  540.23  4828.9  530.94  5078.0  530.21  5100.0  529.61  5104.6  528.52
  5104.8  528.02  5108.3  528.02  5108.6  528.52  5135.2  530.12  5163.9  530.51
  5170.4  530.24  5205.5  530.68  5227.6  530.01  5334.4  530.95  5355.2  531.59
  5383.8  530.92  5624.6  534.38  6022.9  542.56  6228.6  547.68  6278.0  547.33
  6292.3  547.87  6313.2  547.77  6384.8  549.21  6498.0  549.58  6597.6  550.58
#Mann=3,-1,0
  3556.8    0.05       0  5104.6    0.03       0  5108.6    0.05       0
Bank Sta=5104.6,5108.6
Exp/Cntr=0.3,0.1

Type RM Length L Ch R = 1,29847,2266,2266,2266
BEGIN DESCRIPTION:
Berry Creek 63.0
END DESCRIPTION:
XS GIS Cut Line= 3
      2636748.10      7003489.39      2635067.24      7003654.94
      2634275.99      7004711.01
#Sta/Elev= 30
  3311.0  540.02  3463.8  538.90  3504.0  537.94  3554.3  538.19  3674.9  536.57
  3715.0  537.24  4066.7  536.48  4193.5  534.51  4598.5  530.38  4679.7  529.83
  4709.8  530.24  4840.5  528.83  4850.5  529.38  4951.0  529.00  5003.9  528.23
  5004.1  527.73  5007.6  527.73  5007.9  528.23  5062.1  528.90  5112.1  528.32
  5126.7  529.11  5133.0  528.72  5355.9  531.11  5776.8  537.21  5812.2  538.22
  5856.0  538.34  5862.2  538.87  6033.1  541.56  6247.7  547.68  6319.6  548.31
#Mann=3,-1,0
  3311.0    0.05       0  5003.9    0.03       0  5007.9    0.05       0
Bank Sta=5003.9,5007.9
Exp/Cntr=0.3,0.1

Type RM Length L Ch R = 1,27581,723,723,723
BEGIN DESCRIPTION:
Berry Creek 58.0
END DESCRIPTION:
XS GIS Cut Line= 4
      2635697.72      7001305.38      2634176.54      7002000.81
      2633903.17      7002197.95      2634028.14      7004176.57
#Sta/Elev= 30
  3327.4  546.12  3452.4  546.08  3521.5  545.34  3613.6  543.47  3665.1  541.65
  3957.9  535.42  4066.0  531.96  4538.8  525.73  4659.7  526.14  4758.7  522.74
  4793.9  522.27  4848.1  521.43  4917.2  521.77  4994.8  521.23  5020.6  520.36
  5020.8  519.86  5024.3  519.86  5024.6  520.36  5064.3  520.64  5079.0  521.34
  5129.3  521.01  5150.2  521.85  5271.9  522.81  6271.9  528.02  6662.7  532.69
  7023.4  538.80  7043.1  539.86  7053.5  539.15  7143.7  540.09  7319.6  540.52
#Mann=5,-1,0
  3327.4    0.05       0  4793.9    0.12       0  4994.8    0.05       0
  5020.6   0.035       0  5024.6    0.05       0
Bank Sta=5020.6,5024.6
Exp/Cntr=0.3,0.1

Type RM Length L Ch R = 1,26858,956,956,956
BEGIN DESCRIPTION:
Mapping XS 96249d9a
END DESCRIPTION:
XS GIS Cut Line= 4
      2635686.31      7001133.63      2633922.41      7001432.24
      2633554.35      7001529.46      2632054.32      7002182.25
#Sta/Elev= 30
  3214.6  543.57  3478.6  542.24  4198.7  531.06  4487.4  529.72  4736.3  523.96
  4970.4  520.85  5010.2  518.77  5022.0  519.85  5041.3  518.80  5062.3  520.27
  5103.3  520.63  5155.0  519.24  5196.4  519.30  5206.7  520.07  5218.2  523.36
  5237.8  523.34  5258.5  519.40  5288.4  519.66  5291.5  518.19  5291.8  517.69
  5295.5  518.19  5328.6  524.28  5341.2  523.86  5361.9  520.57  5405.2  519.16
  5428.6  520.57  5764.2  521.81  6128.5  524.87  6478.4  529.12  7020.2  541.29
#Mann=3,-1,0
  3214.6    0.05       0  5291.5    0.03       0  5295.5    0.05       0
Bank Sta=5291.5,5295.5
Exp/Cntr=0.3,0.1

Type RM Length L Ch R = 1,25902,959,959,959
BEGIN DESCRIPTION:
Berry Creek 54.0
END DESCRIPTION:
XS GIS Cut Line= 3
      2633838.42      7000311.77      2633320.99      7000870.91
      2631940.18      7002055.29
#Sta/Elev= 30
  4284.5  528.10  4349.5  528.72  4413.1  528.27  4667.6  522.38  4887.1  518.26
  4907.7  519.65  4957.9  517.93  4986.3  518.18  4993.1  517.57  5000.4  518.06
  5163.3  518.64  5224.9  517.26  5225.2  516.76  5228.7  516.76  5228.9  517.26
  5248.9  518.28  5290.6  517.89  5322.5  518.62  5369.1  519.45  5382.8  518.43
  5425.6  519.43  5475.0  519.06  5638.5  520.41  5780.1  522.10  5843.7  523.95
  6163.1  527.33  6425.4  531.76  6695.4  538.30  6822.7  542.73  6865.5  543.50
#Mann=5,-1,0
  4284.5    0.05       0  4907.7    0.12       0  5224.9    0.07       0
  5228.9    0.12       0  5322.5    0.05       0
Bank Sta=5224.9,5228.9
Exp/Cntr=0.3,0.1

Type RM Length L Ch R = 1,24943,1000,1000,1000
BEGIN DESCRIPTION:
Berry Creek 53.0
END DESCRIPTION:
XS GIS Cut Line= 3
      2633401.72      7000054.51      2632831.88      7000318.68
      2631380.97      7002030.13
#Sta/Elev= 30
  4371.9  527.43  4425.4  527.44  4488.4  526.38  4711.4  520.44  4854.3  517.65
  4929.3  517.28  4940.3  517.63  4968.9  517.04  5290.0  517.30  5302.3  516.91
  5302.6  516.41  5306.1  516.41  5306.3  516.91  5325.2  517.73  5396.3  518.61
  5466.9  517.82  5630.6  519.29  5708.6  519.44  5914.0  522.62  6091.2  524.43
  6275.3  527.02  6311.6  527.29  6332.5  526.74  6381.9  528.35  6652.2  533.03
  6808.2  536.23  6871.9  537.17  6921.3  536.76  7134.4  542.00  7243.7  543.03
#Mann=3,-1,0
  4371.9    0.05       0  5302.3    0.03       0  5306.3    0.05       0
Bank Sta=5302.3,5306.3
Exp/Cntr=0.3,0.1

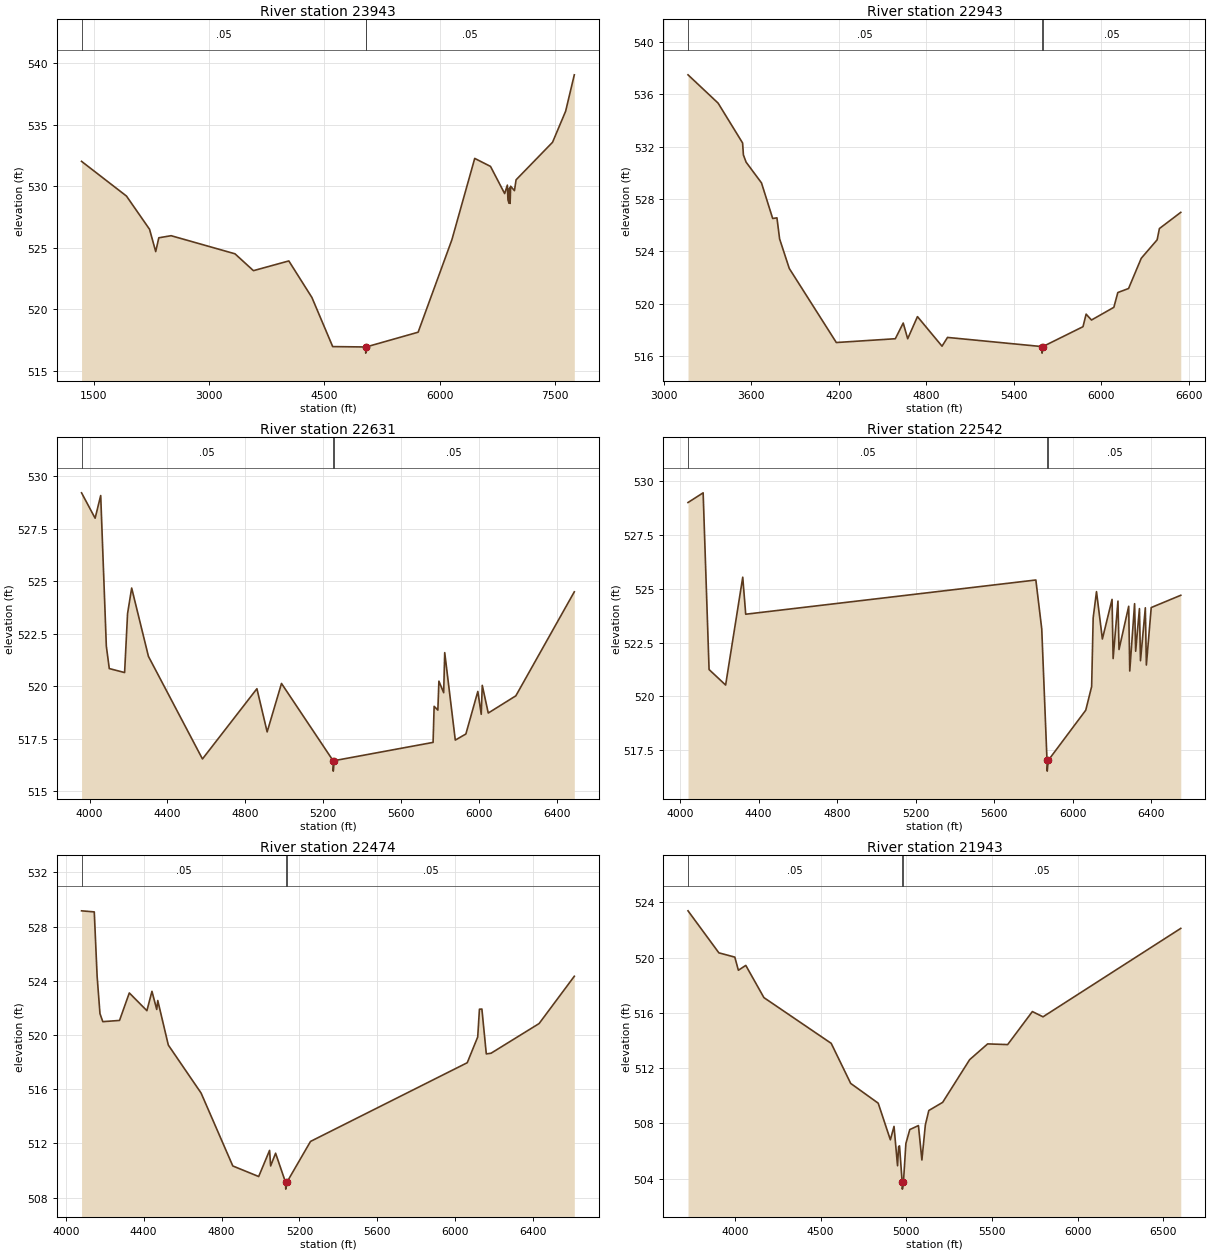
Type RM Length L Ch R = 1,23943,1000,1000,1000
BEGIN DESCRIPTION:
Berry Creek 51.0
END DESCRIPTION:
XS GIS Cut Line= 3
      2636019.81      6999801.89      2632363.82      6999863.15
      2630376.02      7001760.98
#Sta/Elev= 30
  1343.5  532.01  1927.4  529.19  2227.4  526.49  2307.4  524.68  2347.5  525.80
  2507.5  525.97  3337.6  524.50  3577.6  523.13  4037.7  523.92  4337.7  520.95
  4607.8  516.96  5036.9  516.93  5037.4  516.43  5041.6  516.93  5718.3  518.13
  6157.0  525.64  6453.9  532.25  6659.0  531.60  6843.0  529.39  6878.2  530.08
  6885.5  528.89  6899.6  528.61  6906.5  529.84  6913.8  528.59  6920.7  529.99
  6970.4  529.63  6991.4  530.51  7465.4  533.56  7635.3  536.08  7748.3  539.04
#Mann=3,-1,0
  1343.5    0.05       0  5036.9    0.03       0  5041.6    0.05       0
Bank Sta=5036.9,5041.6
Exp/Cntr=0.3,0.1

Type RM Length L Ch R = 1,22943,312,312,312
BEGIN DESCRIPTION:
Berry Creek 49.0
END DESCRIPTION:
XS GIS Cut Line= 3
      2632575.99      6997361.02      2631865.13      6999051.76
      2631066.11      7000372.82
#Sta/Elev= 30
  3165.9  537.50  3372.0  535.34  3540.1  532.29  3545.6  531.38  3563.8  530.83
  3669.6  529.24  3746.3  526.52  3775.5  526.57  3793.8  524.96  3860.1  522.70
  4182.6  517.04  4587.0  517.33  4641.2  518.53  4671.8  517.33  4738.8  519.02
  4907.2  516.76  4944.9  517.43  5591.9  516.73  5593.0  516.23  5598.3  516.73
  5873.6  518.25  5895.0  519.21  5931.8  518.76  6085.1  519.73  6112.3  520.86
  6186.0  521.17  6273.0  523.48  6381.9  524.89  6397.4  525.75  6543.9  526.99
#Mann=3,-1,0
  3165.9    0.05       0  5591.9    0.03       0  5598.3    0.05       0
Bank Sta=5591.9,5598.3
Exp/Cntr=0.3,0.1

Type RM Length L Ch R = 1,22631,89,89,89
BEGIN DESCRIPTION:
Mapping XS a48fe3e8
END DESCRIPTION:
XS GIS Cut Line= 6
      2632099.10      6997838.10      2631925.63      6998109.61
      2631922.71      6998147.17      2631709.05      6998794.45
      2631278.17      6999899.77      2631153.25      7000176.77
#Sta/Elev= 30
  3958.5  529.22  4028.2  528.01  4056.9  529.09  4085.8  521.91  4101.0  520.84
  4179.7  520.65  4194.9  523.46  4216.0  524.68  4302.2  521.42  4579.7  516.53
  4859.5  519.88  4912.1  517.82  4985.8  520.13  5250.7  516.45  5251.7  515.95
  5257.1  516.45  5764.6  517.32  5770.0  519.04  5789.1  518.86  5794.5  520.24
  5819.0  519.69  5824.4  521.60  5878.7  517.43  5933.1  517.72  5994.5  519.75
  6012.0  518.66  6017.3  520.04  6048.1  518.72  6189.8  519.54  6490.2  524.50
#Mann=3,-1,0
  3958.5    0.05       0  5250.7    0.03       0  5257.1    0.05       0
Bank Sta=5250.7,5257.1
Exp/Cntr=0.3,0.1

Type RM Length L Ch R = 1,22542,68,68,68
BEGIN DESCRIPTION:
Mapping XS 6c9d63cb
END DESCRIPTION:
XS GIS Cut Line= 5
      2632073.04      6997851.15      2631888.07      6998131.63
      2631673.54      6998716.87      2631470.71      6999273.30
      2631127.41      7000167.41
#Sta/Elev= 30
  4040.7  529.01  4117.7  529.46  4147.9  521.25  4232.2  520.53  4319.4  525.54
  4334.5  523.82  5812.0  525.41  5842.0  523.14  5868.8  517.03  5869.9  516.53
  5875.2  517.03  6066.1  519.36  6096.1  520.46  6103.9  523.65  6120.8  524.87
  6150.8  522.67  6200.1  524.51  6205.5  521.76  6230.1  524.43  6235.5  522.18
  6284.8  524.19  6290.2  521.18  6314.8  524.31  6320.2  522.10  6339.5  524.08
  6344.8  521.66  6369.5  524.12  6374.8  521.46  6399.5  524.13  6550.0  524.70
#Mann=3,-1,0
  4040.7    0.05       0  5868.8    0.03       0  5875.2    0.05       0
Bank Sta=5868.8,5875.2
Exp/Cntr=0.3,0.1

Type RM Length L Ch R = 1,22474,531,531,531
BEGIN DESCRIPTION:
Mapping XS 93f1b2a2
END DESCRIPTION:
XS GIS Cut Line= 6
      2632039.21      6997852.85      2631841.27      6998123.72
      2631628.54      6998666.75      2631482.95      6999073.21
      2631337.80      6999536.91      2631084.33      7000182.72
#Sta/Elev= 30
  4081.3  529.16  4146.6  529.08  4161.3  524.32  4175.9  521.57  4190.5  520.98
  4276.3  521.07  4326.5  523.10  4416.8  521.79  4442.8  523.22  4467.3  521.88
  4472.6  522.54  4526.9  519.25  4695.1  515.71  4857.9  510.33  4990.8  509.55
  5046.8  511.48  5052.2  510.33  5077.6  511.27  5128.8  509.12  5129.8  508.62
  5135.2  509.12  5256.9  512.14  6061.7  517.95  6115.4  519.85  6124.3  521.90
  6136.9  521.91  6159.5  518.60  6183.9  518.65  6430.6  520.84  6611.4  524.33
#Mann=3,-1,0
  4081.3    0.05       0  5128.8    0.03       0  5135.2    0.05       0
Bank Sta=5128.8,5135.2
Exp/Cntr=0.3,0.1

Type RM Length L Ch R = 1,21943,500,500,500
BEGIN DESCRIPTION:
Berry Creek 47.0
END DESCRIPTION:
XS GIS Cut Line= 4
      2631862.66      6997474.67      2631196.02      6998314.91
      2631151.25      6998510.99      2630934.06      7000097.39
#Sta/Elev= 30
  3726.3  523.39  3906.3  520.35  3999.3  520.04  4020.1  519.09  4063.4  519.44
  4169.1  517.11  4561.7  513.80  4675.4  510.90  4835.9  509.47  4906.9  506.82
  4928.2  507.79  4948.7  504.94  4955.0  506.33  4960.2  506.38  4975.8  503.75
  4976.9  503.25  4983.1  503.75  4997.4  506.55  5020.2  507.56  5070.6  507.85
  5090.8  505.36  5111.0  507.90  5131.2  508.94  5212.0  509.53  5369.4  512.62
  5474.4  513.76  5591.1  513.71  5735.4  516.10  5797.4  515.72  6601.2  522.12
#Mann=3,-1,0
  3726.3    0.05       0  4975.8    0.03       0  4983.1    0.05       0
Bank Sta=4975.8,4983.1
Exp/Cntr=0.3,0.1

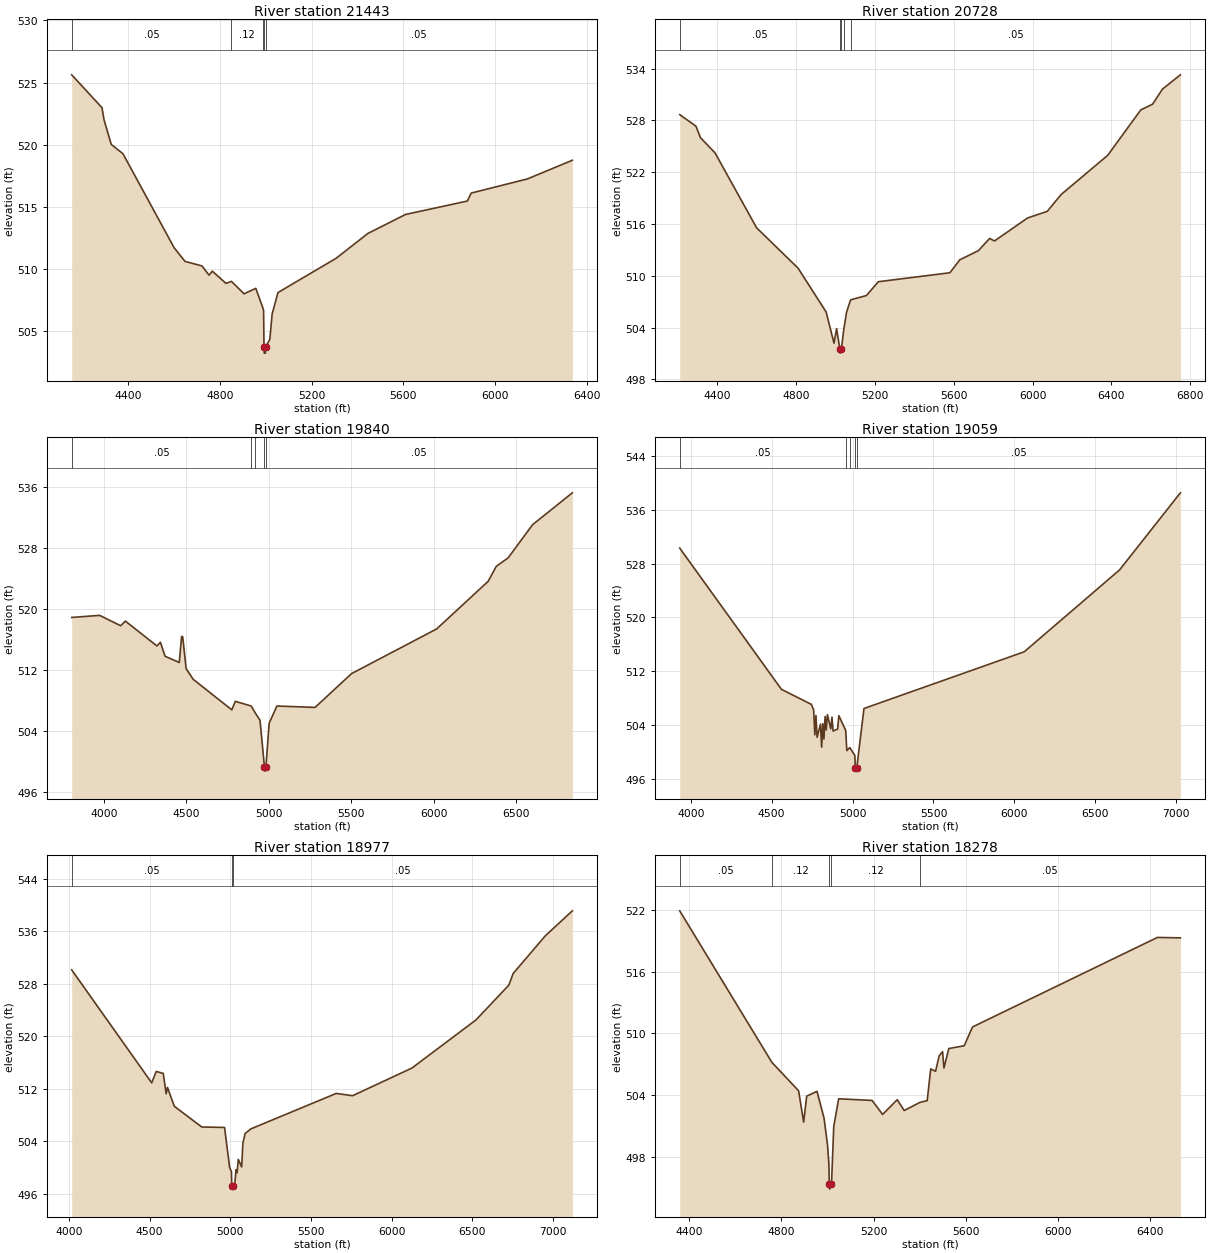
Type RM Length L Ch R = 1,21443,715,715,715
BEGIN DESCRIPTION:
Berry Creek 46.0
END DESCRIPTION:
XS GIS Cut Line= 5
      2630626.00      6997511.00      2630743.06      6998183.70
      2630708.71      6998343.13      2630687.50      6998489.25
      2630937.50      6999652.44
#Sta/Elev= 30
  4154.1  525.63  4286.1  522.99  4295.5  521.99  4326.7  520.03  4377.4  519.29
  4600.7  511.73  4648.1  510.63  4722.5  510.26  4753.0  509.52  4767.4  509.84
  4827.0  508.86  4850.7  509.02  4905.8  508.02  4956.9  508.46  4986.2  506.97
  4990.9  506.69  4992.7  503.75  4993.8  503.25  4998.9  503.25  5000.1  503.75
  5018.1  504.36  5028.2  506.39  5053.6  508.12  5307.5  510.88  5445.4  512.87
  5609.7  514.40  5879.5  515.48  5896.1  516.12  6141.6  517.26  6337.4  518.76
#Mann=5,-1,0
  4154.1    0.05       0  4850.7    0.12       0  4986.2    0.05       0
  4992.7    0.03       0  5000.1    0.05       0
Bank Sta=4992.7,5000.1
Exp/Cntr=0.3,0.1

Type RM Length L Ch R = 1,20728,888,888,888
BEGIN DESCRIPTION:
Berry Creek 45.0
END DESCRIPTION:
XS GIS Cut Line= 3
      2630476.01      6997360.97      2630139.38      6998074.22
      2629926.00      6999810.97
#Sta/Elev= 30
  4211.3  528.67  4293.8  527.33  4316.6  526.00  4390.4  524.24  4600.9  515.57
  4811.4  510.89  4953.5  505.82  4993.6  502.21  5006.8  503.89  5023.0  501.55
  5024.2  501.05  5031.0  501.55  5042.7  503.72  5057.2  505.79  5077.7  507.22
  5158.0  507.72  5218.4  509.32  5581.1  510.36  5631.5  511.86  5726.0  512.92
  5782.6  514.33  5807.3  514.04  5974.9  516.70  6074.8  517.47  6145.3  519.42
  6381.4  523.96  6549.1  529.22  6608.8  529.88  6659.2  531.63  6749.8  533.28
#Mann=5,-1,0
  4211.3    0.05       0  5023.0    0.03       0  5031.0    0.05       0
  5042.7    0.12       0  5077.7    0.05       0
Bank Sta=5023,5031
Exp/Cntr=0.3,0.1

Type RM Length L Ch R = 1,19840,781,781,781
BEGIN DESCRIPTION:
Berry Creek 43.0
END DESCRIPTION:
XS GIS Cut Line= 5
      2630080.42      6996856.74      2629434.58      6997635.39
      2629381.03      6997811.81      2629310.61      6998436.44
      2628376.03      6999210.97
#Sta/Elev= 30
  3804.0  518.89  3973.7  519.16  4101.3  517.80  4129.9  518.41  4321.4  515.15
  4342.2  515.64  4370.8  513.80  4456.8  512.99  4471.1  516.42  4477.6  516.35
  4498.5  512.18  4541.4  510.78  4775.8  506.78  4796.9  507.90  4893.5  507.28
  4916.1  506.44  4946.9  505.41  4974.0  499.25  4975.3  498.75  4982.6  499.25
  5002.2  505.02  5049.5  507.28  5281.0  507.10  5502.4  511.53  6018.7  517.38
  6331.3  523.62  6380.8  525.59  6452.4  526.69  6600.8  531.04  6842.4  535.22
#Mann=5,-1,0
  3804.0    0.05       0  4893.5    0.12       0  4916.1    0.05       0
  4974.0    0.03       0  4982.6    0.05       0
Bank Sta=4974,4982.6
Exp/Cntr=0.3,0.1

Type RM Length L Ch R = 1,19059,82,82,82
BEGIN DESCRIPTION:
Berry Creek 41.0
END DESCRIPTION:
XS GIS Cut Line= 5
      2628926.00      6996460.99      2629088.13      6997113.28
      2628813.62      6997398.65      2628406.70      6997781.69
      2628076.00      6999210.99
#Sta/Elev= 30
  3931.9  530.33  4560.5  509.31  4745.4  507.07  4759.5  506.27  4766.7  502.54
  4773.7  505.42  4780.9  502.18  4802.0  504.14  4809.0  500.71  4816.1  504.20
  4823.0  501.92  4830.3  505.27  4837.2  503.26  4844.4  505.55  4865.5  503.44
  4872.7  505.17  4879.6  503.10  4907.9  503.41  4915.2  505.40  4957.7  503.19
  4964.5  500.19  4983.0  500.65  5014.0  499.48  5016.7  497.64  5018.0  497.14
  5026.0  497.64  5070.7  506.46  6061.1  514.90  6650.1  527.08  7025.9  538.55
#Mann=5,-1,0
  3931.9    0.05       0  4957.7    0.12       0  4983.0    0.05       0
  5016.7    0.03       0  5026.0    0.05       0
Bank Sta=5016.7,5026
Exp/Cntr=0.3,0.1

Type RM Length L Ch R = 1,18977,699,699,699
BEGIN DESCRIPTION:
Mapping XS d4b6caa9
END DESCRIPTION:
XS GIS Cut Line= 6
      2628902.21      6996475.96      2629023.75      6997051.07
      2628756.82      6997339.70      2628311.94      6997754.20
      2628255.52      6997988.57      2628010.29      6999236.44
#Sta/Elev= 30
  4017.6  530.12  4513.3  512.92  4541.3  514.65  4584.9  514.36  4602.8  511.26
  4610.8  512.23  4653.3  509.36  4823.2  506.20  4964.6  506.13  4996.0  500.06
  5007.1  499.38  5009.3  497.24  5010.7  496.74  5018.6  497.24  5028.1  497.50
  5035.5  499.70  5042.3  499.23  5049.7  501.27  5070.7  500.12  5078.0  503.72
  5092.2  505.21  5127.3  505.91  5656.6  511.31  5757.6  510.96  6125.3  515.17
  6522.8  522.51  6726.6  527.82  6752.4  529.56  6950.8  535.28  7119.4  539.11
#Mann=3,-1,0
  4017.6    0.05       0  5009.3    0.03       0  5018.6    0.05       0
Bank Sta=5009.3,5018.6
Exp/Cntr=0.3,0.1

Type RM Length L Ch R = 1,18278,917,917,917
BEGIN DESCRIPTION:
Berry Creek 40.0
END DESCRIPTION:
XS GIS Cut Line= 3
      2628450.97      6996433.60      2628207.92      6996957.90
      2627343.35      6998294.68
#Sta/Elev= 30
  4360.1  521.91  4759.4  507.17  4875.3  504.40  4897.3  501.35  4910.4  503.88
  4955.1  504.34  4985.5  501.75  5000.6  499.15  5006.6  497.31  5008.4  495.33
  5009.7  494.83  5017.9  495.33  5027.7  500.93  5048.9  503.62  5193.9  503.46
  5239.4  502.10  5302.8  503.53  5333.1  502.48  5401.1  503.27  5432.7  503.44
  5447.9  506.53  5469.0  506.30  5484.2  507.78  5499.3  508.21  5505.3  506.62
  5526.4  508.51  5593.0  508.78  5629.3  510.61  6430.3  519.32  6530.0  519.28
#Mann=5,-1,0
  4360.1    0.05       0  4759.4    0.12       0  5008.4    0.07       0
  5017.9    0.12       0  5401.1    0.05       0
Bank Sta=5008.4,5017.9
Exp/Cntr=0.3,0.1

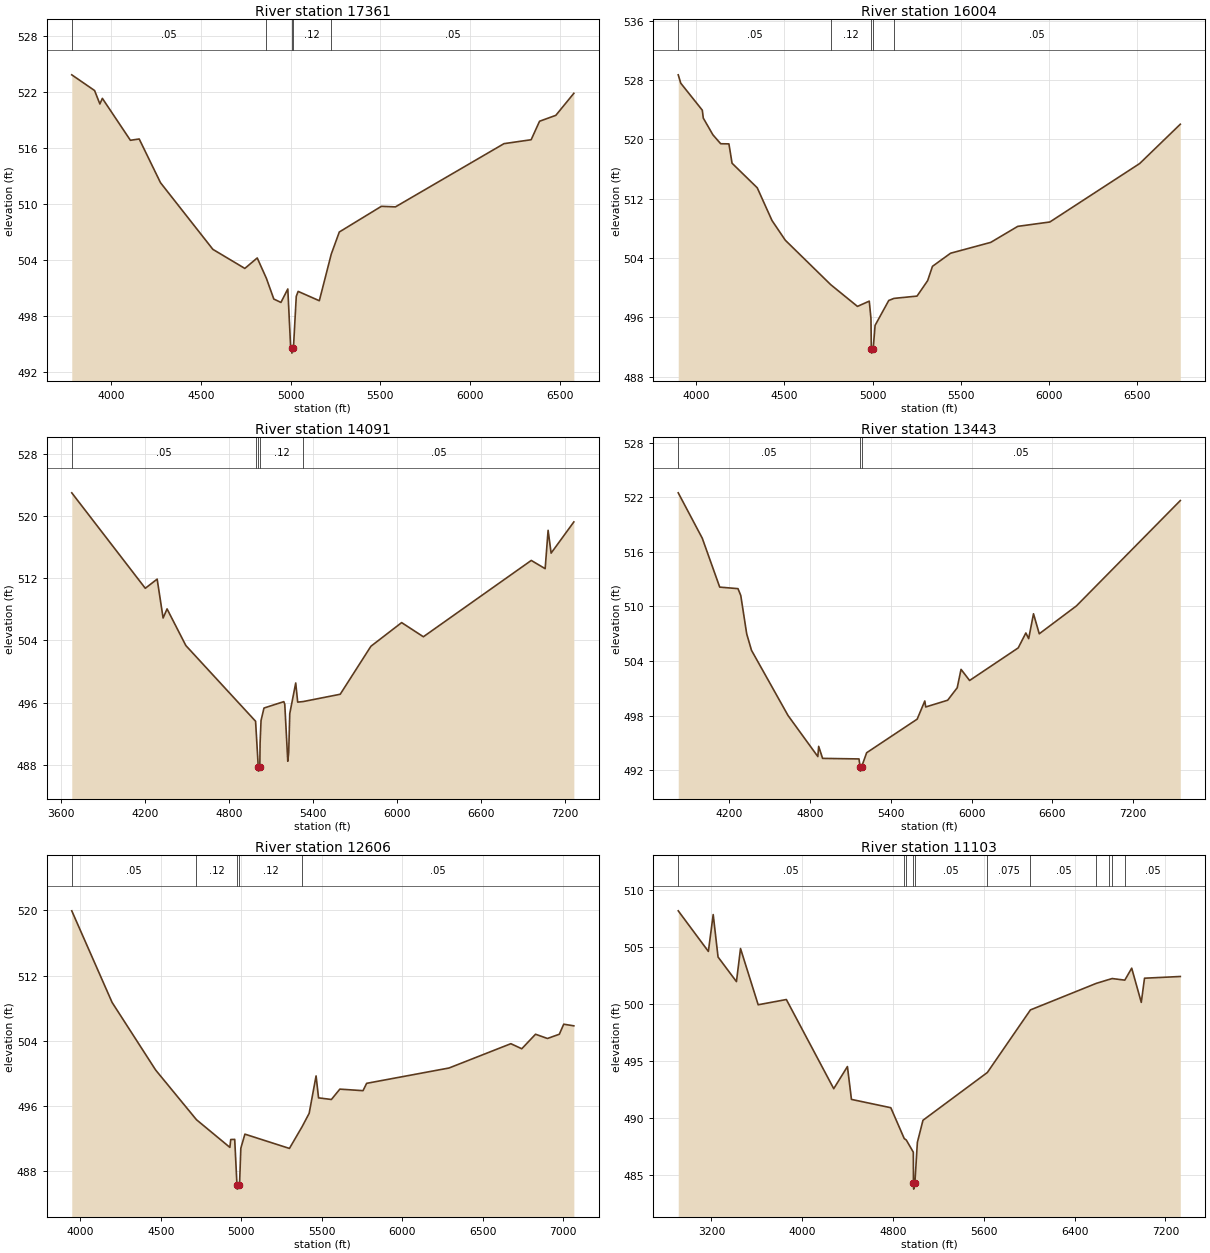
Type RM Length L Ch R = 1,17361,1357,1357,1357
BEGIN DESCRIPTION:
Berry Creek 37.0
END DESCRIPTION:
XS GIS Cut Line= 3
      2628042.68      6995724.18      2627567.33      6996574.27
      2627042.65      6998324.24
#Sta/Elev= 30
  3778.6  523.81  3905.8  522.13  3935.4  520.69  3949.3  521.29  4105.7  516.80
  4154.8  516.94  4273.6  512.26  4565.9  505.12  4744.1  503.08  4813.2  504.20
  4864.1  502.03  4905.8  499.80  4945.5  499.44  4983.8  500.88  4999.7  494.63
  5005.3  494.51  5006.6  494.01  5015.1  494.51  5031.0  500.09  5041.5  500.62
  5159.6  499.62  5226.2  504.61  5271.1  506.98  5505.9  509.73  5584.3  509.67
  6189.8  516.44  6341.4  516.86  6388.2  518.84  6478.9  519.47  6579.5  521.83
#Mann=5,-1,0
  3778.6    0.05       0  4864.1    0.12       0  5005.3    0.07       0
  5015.1    0.12       0  5226.2    0.05       0
Bank Sta=5005.3,5015.1
Exp/Cntr=0.3,0.1

Type RM Length L Ch R = 1,16004,1913,1913,1913
BEGIN DESCRIPTION:
Berry Creek 35.0
END DESCRIPTION:
XS GIS Cut Line= 3
      2626925.99      6995361.03      2626481.70      6996369.50
      2626376.00      6998110.99
#Sta/Elev= 30
  3898.0  528.68  3912.4  527.55  4034.5  523.91  4040.0  522.85  4094.7  520.59
  4138.7  519.39  4185.4  519.37  4203.2  516.76  4346.0  513.45  4429.6  509.04
  4505.1  506.38  4762.6  500.39  4914.2  497.46  4981.1  498.17  4990.7  495.85
  4993.0  491.66  4994.4  491.16  5003.1  491.66  5014.1  494.90  5091.7  498.26
  5121.6  498.54  5252.0  498.85  5312.1  500.93  5339.4  502.86  5442.3  504.63
  5669.8  506.09  5823.0  508.25  6005.1  508.84  6514.3  516.72  6744.7  522.02
#Mann=5,-1,0
  3898.0    0.05       0  4762.6    0.12       0  4993.0    0.07       0
  5003.1    0.12       0  5121.6    0.05       0
Bank Sta=4993,5003.1
Exp/Cntr=0.3,0.1

Type RM Length L Ch R = 1,14091,648,648,648
BEGIN DESCRIPTION:
Berry Creek 31.0
END DESCRIPTION:
XS GIS Cut Line= 3
      2625916.52      6994478.09      2624952.82      6995387.29
      2623276.00      6996911.00
#Sta/Elev= 30
  3675.1  522.95  4200.9  510.68  4285.8  511.86  4328.3  506.86  4356.6  508.03
  4491.0  503.32  4989.6  493.59  5009.0  487.68  5010.5  487.18  5019.9  487.68
  5021.9  490.78  5028.7  493.69  5049.8  495.29  5191.5  496.11  5198.4  495.77
  5219.9  488.45  5226.6  489.61  5234.1  494.57  5276.7  498.51  5290.8  496.05
  5329.7  496.12  5594.9  497.06  5814.5  503.23  6034.2  506.27  6189.6  504.45
  6961.3  514.26  7060.6  513.20  7081.6  518.13  7103.2  515.20  7265.7  519.21
#Mann=5,-1,0
  3675.1    0.05       0  4989.6    0.12       0  5009.0    0.07       0
  5019.9    0.12       0  5329.7    0.05       0
Bank Sta=5009,5019.9
Exp/Cntr=0.3,0.1

Type RM Length L Ch R = 1,13443,837,837,837
BEGIN DESCRIPTION:
Berry Creek 30.0
END DESCRIPTION:
XS GIS Cut Line= 3
      2625475.99      6994261.01      2624525.76      6994960.81
      2622826.00      6996861.00
#Sta/Elev= 30
  3819.9  522.49  3998.5  517.50  4128.0  512.13  4263.8  511.96  4284.6  511.20
  4328.5  506.99  4364.0  505.19  4635.6  498.02  4856.9  493.51  4863.1  494.63
  4892.4  493.31  5162.6  493.25  5170.8  492.41  5172.5  491.91  5182.7  492.41
  5219.4  493.93  5594.7  497.62  5651.5  499.62  5658.3  498.96  5821.3  499.70
  5892.3  501.07  5920.7  503.09  5984.3  501.87  6345.4  505.45  6402.2  507.09
  6423.1  506.47  6459.0  509.20  6501.7  507.00  6777.5  510.06  7549.5  521.64
#Mann=3,-1,0
  3819.9    0.05       0  5170.8    0.03       0  5182.7    0.05       0
Bank Sta=5170.8,5182.7
Exp/Cntr=0.3,0.1

Type RM Length L Ch R = 1,12606,1503,1503,1503
BEGIN DESCRIPTION:
Berry Creek 28.0
END DESCRIPTION:
XS GIS Cut Line= 3
      2625376.00      6994111.00      2624325.33      6994190.92
      2622549.75      6995249.90
#Sta/Elev= 30
  3946.3  519.95  4197.0  508.72  4467.8  500.43  4721.5  494.34  4929.1  490.95
  4934.6  491.91  4959.2  491.93  4973.3  486.33  4975.0  485.83  4985.2  486.33
  4989.3  486.41  4997.2  490.84  5022.5  492.57  5299.4  490.82  5378.9  493.51
  5422.0  495.12  5465.0  499.71  5480.4  497.02  5560.2  496.82  5612.8  498.09
  5756.8  497.90  5779.3  498.80  6291.6  500.68  6675.9  503.66  6743.7  503.04
  6829.3  504.82  6903.3  504.30  6977.2  504.82  7004.5  506.05  7067.4  505.85
#Mann=5,-1,0
  3946.3    0.05       0  4721.5    0.12       0  4973.3    0.07       0
  4985.2    0.12       0  5378.9    0.05       0
Bank Sta=4973.3,4985.2
Exp/Cntr=0.3,0.1

Type RM Length L Ch R = 1,11103,109,109,109
BEGIN DESCRIPTION:
Berry Creek 26.0
END DESCRIPTION:
XS GIS Cut Line= 3
      2625178.64      6991808.85      2623616.60      6993201.78
      2621926.23      6994806.98
#Sta/Elev= 30
  2907.1  508.20  3172.6  504.64  3215.2  507.87  3257.9  504.15  3420.1  501.99
  3456.0  504.89  3611.5  499.96  3859.8  500.42  4277.3  492.60  4397.9  494.54
  4433.4  491.66  4780.3  490.93  4898.7  488.22  4916.4  488.10  4978.5  487.03
  4980.0  484.29  4981.7  483.79  4992.1  484.29  5014.2  487.89  5063.6  489.83
  5630.9  494.02  6010.5  499.51  6591.3  501.84  6703.4  502.18  6731.1  502.26
  6842.0  502.12  6902.8  503.17  6987.3  500.17  7015.7  502.29  7331.1  502.44
#Mann=11,-1,0
  2907.1    0.05       0  4898.7    0.12       0  4916.4    0.05       0
  4980.0    0.03       0  4992.1    0.05       0  5630.9   0.075       0
  6010.5    0.05       0  6591.3   0.075       0  6703.4    0.05       0
  6731.1   0.075       0  6842.0    0.05       0
Bank Sta=4980,4992.1
Exp/Cntr=0.3,0.1

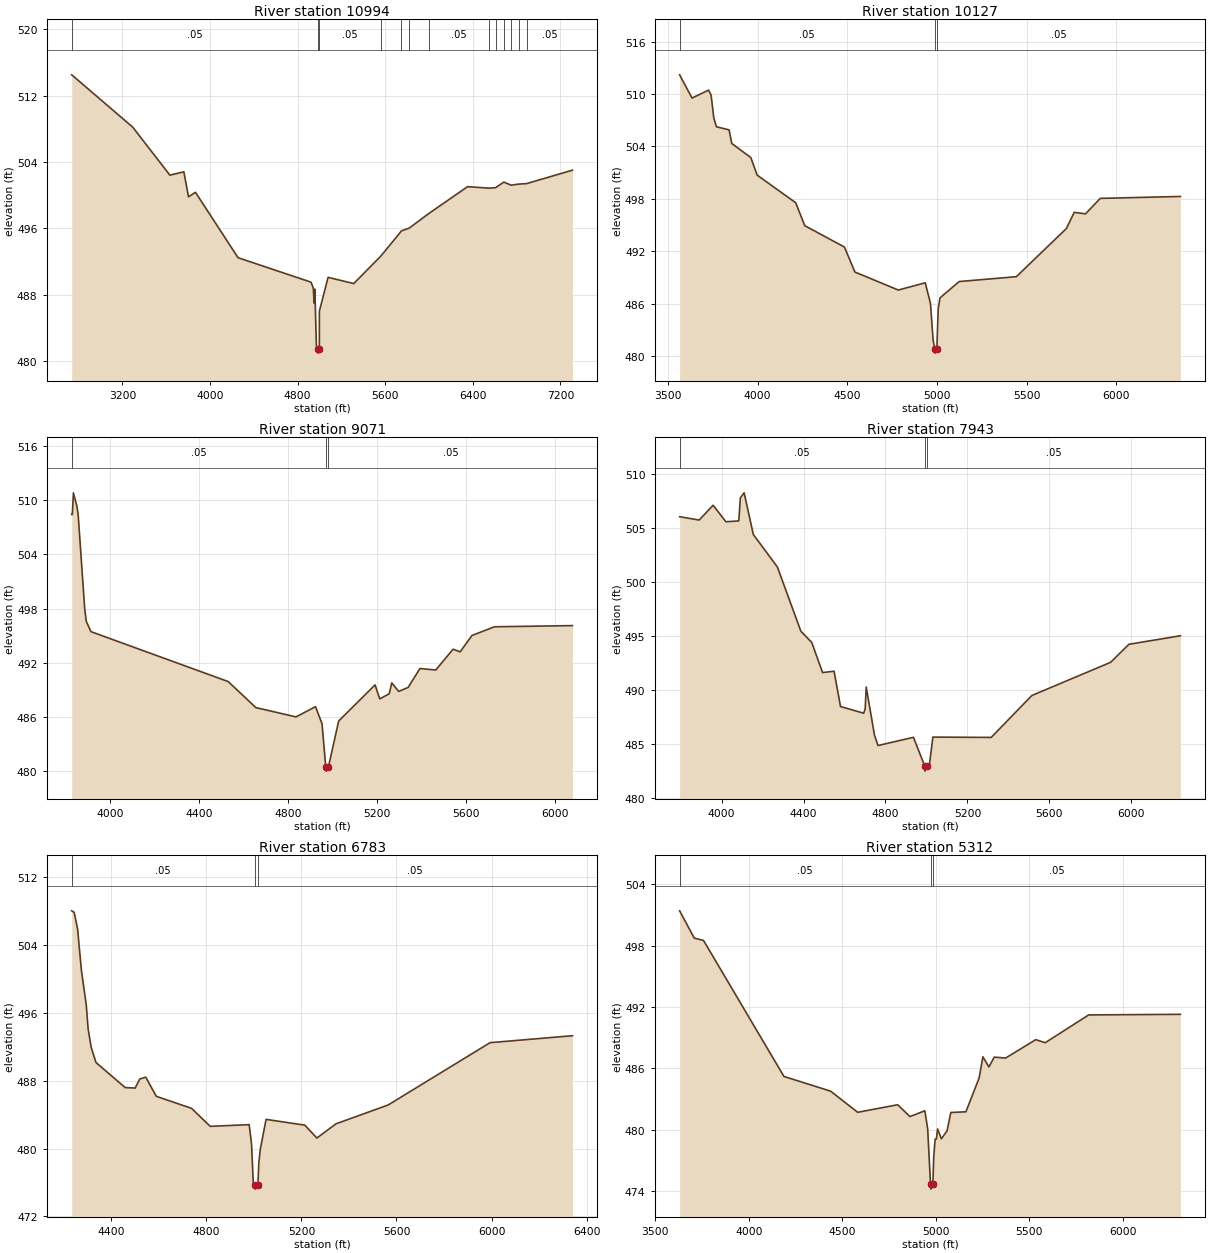
Type RM Length L Ch R = 1,10994,867,867,867
BEGIN DESCRIPTION:
Berry Creek 25.0
END DESCRIPTION:
XS GIS Cut Line= 5
      2625204.67      6991591.85      2624001.21      6992722.77
      2623539.22      6993124.38      2623242.75      6993368.38
      2621862.70      6994712.47
#Sta/Elev= 30
  2736.4  514.53  3293.9  508.22  3633.3  502.43  3760.8  502.83  3803.3  499.82
  3866.8  500.36  4256.0  492.47  4922.2  489.52  4943.1  488.82  4950.7  486.99
  4957.3  488.68  4971.6  481.87  4986.4  481.46  4988.1  480.96  4998.5  481.46
  4998.8  486.02  5078.3  490.10  5312.9  489.35  5561.1  492.68  5748.3  495.70
  5819.0  496.04  5999.4  497.81  6352.4  501.04  6546.8  500.86  6608.6  500.92
  6683.7  501.59  6750.2  501.22  6820.5  501.35  6891.8  501.41  7310.4  503.03
#Mann=13,-1,0
  2736.4    0.05       0  4986.4    0.03       0  4998.5    0.05       0
  5561.1   0.075       0  5748.3    0.05       0  5819.0   0.075       0
  5999.4    0.05       0  6546.8   0.075       0  6608.6    0.05       0
  6683.7   0.075       0  6750.2    0.05       0  6820.5   0.075       0
  6891.8    0.05       0
Bank Sta=4986.4,4998.5
Exp/Cntr=0.3,0.1

Type RM Length L Ch R = 1,10127,1056,1056,1056
BEGIN DESCRIPTION:
Berry Creek 24.0
END DESCRIPTION:
XS GIS Cut Line= 3
      2624302.79      6991531.93      2623152.24      6992387.84
      2621899.65      6992907.22
#Sta/Elev= 30
  3566.0  512.20  3635.2  509.54  3726.9  510.45  3741.5  509.87  3756.2  507.28
  3770.8  506.26  3841.7  505.90  3856.3  504.35  3962.6  502.73  3998.2  500.72
  4212.9  497.56  4263.0  494.94  4484.3  492.49  4542.5  489.63  4784.4  487.57
  4934.6  488.40  4963.8  486.01  4978.4  481.84  4986.8  480.85  4988.5  480.35
  4999.1  480.85  5006.8  485.43  5016.7  486.67  5123.1  488.54  5442.1  489.10
  5721.0  494.61  5764.5  496.46  5827.4  496.29  5909.8  498.06  6356.0  498.28
#Mann=3,-1,0
  3566.0    0.05       0  4986.8    0.04       0  4999.1    0.05       0
Bank Sta=4986.8,4999.1
Exp/Cntr=0.3,0.1

Type RM Length L Ch R = 1,9071,1128,1128,1128
BEGIN DESCRIPTION:
Berry Creek 22.0
END DESCRIPTION:
XS GIS Cut Line= 3
      2623875.97      6990811.02      2622876.04      6991425.98
      2621861.08      6991796.00
#Sta/Elev= 30
  3826.1  508.42  3829.0  508.42  3833.8  510.81  3849.2  509.35  3855.1  508.43
  3884.8  497.93  3891.8  496.58  3913.0  495.45  4530.5  489.93  4655.1  487.05
  4835.7  486.02  4923.7  487.15  4953.1  485.25  4969.6  480.52  4971.3  480.02
  4982.1  480.52  5027.9  485.56  5191.6  489.56  5212.9  488.01  5255.5  488.58
  5267.1  489.78  5298.1  488.84  5340.6  489.28  5393.9  491.37  5465.1  491.21
  5542.9  493.51  5574.8  493.22  5628.0  495.03  5729.5  495.99  6080.3  496.12
#Mann=3,-1,0
  3826.1    0.05       0  4969.6    0.04       0  4982.1    0.05       0
Bank Sta=4969.6,4982.1
Exp/Cntr=0.3,0.1

Type RM Length L Ch R = 1,7943,1160,1160,1160
BEGIN DESCRIPTION:
Berry Creek 19.0
END DESCRIPTION:
XS GIS Cut Line= 3
      2623816.73      6989973.75      2622675.91      6990361.79
      2621500.01      6990754.67
#Sta/Elev= 30
  3795.0  506.03  3890.4  505.72  3958.4  507.09  4021.1  505.56  4083.9  505.64
  4091.5  507.78  4109.9  508.24  4154.9  504.38  4272.1  501.38  4387.0  495.43
  4440.1  494.39  4492.9  491.60  4549.1  491.73  4580.5  488.46  4693.6  487.84
  4700.7  488.23  4706.0  490.26  4746.4  485.81  4763.5  484.85  4936.5  485.61
  4991.1  482.98  4992.8  482.48  5003.6  482.98  5014.5  483.08  5031.5  485.63
  5316.2  485.60  5514.7  489.48  5899.1  492.55  5988.6  494.22  6239.8  495.01
#Mann=3,-1,0
  3795.0    0.05       0  4991.1    0.04       0  5003.6    0.05       0
Bank Sta=4991.1,5003.6
Exp/Cntr=0.3,0.1

Type RM Length L Ch R = 1,6783,1471,1471,1471
BEGIN DESCRIPTION:
Berry Creek 16.0
END DESCRIPTION:
XS GIS Cut Line= 3
      2623276.02      6989411.01      2622526.45      6989250.81
      2621209.60      6989500.40
#Sta/Elev= 30
  4233.5  508.02  4243.8  507.84  4258.3  505.88  4274.4  500.99  4294.9  496.91
  4302.6  494.11  4315.3  491.95  4335.8  490.14  4458.5  487.19  4500.6  487.13
  4519.8  488.20  4545.0  488.42  4589.4  486.16  4737.8  484.74  4816.4  482.62
  4980.2  482.82  4990.2  480.52  4997.7  475.79  5004.3  475.72  5006.1  475.22
  5016.9  475.72  5020.8  478.33  5026.9  479.90  5051.3  483.44  5214.2  482.76
  5265.1  481.24  5345.7  482.92  5565.1  485.14  5993.6  492.48  6340.3  493.30
#Mann=3,-1,0
  4233.5    0.05       0  5004.3    0.04       0  5016.9    0.05       0
Bank Sta=5004.3,5016.9
Exp/Cntr=0.3,0.1

Type RM Length L Ch R = 1,5312,1369,1369,1369
BEGIN DESCRIPTION:
Berry Creek 14.0
END DESCRIPTION:
XS GIS Cut Line= 3
      2623456.53      6988683.04      2622176.04      6988195.66
      2620880.35      6988383.26
#Sta/Elev= 30
  3629.9  501.42  3708.3  498.75  3757.8  498.52  4188.0  485.21  4437.6  483.77
  4582.8  481.70  4796.7  482.44  4862.4  481.28  4942.0  481.85  4957.2  480.07
  4972.2  474.68  4974.0  474.18  4985.0  474.68  4989.3  477.28  4996.9  479.08
  5003.7  479.08  5010.1  480.07  5030.4  479.11  5060.7  479.88  5080.9  481.68
  5161.7  481.75  5232.4  485.06  5252.6  487.13  5284.8  486.14  5313.3  487.10
  5373.9  487.01  5535.6  488.81  5586.1  488.51  5818.5  491.23  6309.2  491.29
#Mann=3,-1,0
  3629.9    0.05       0  4972.2    0.04       0  4985.0    0.05       0
Bank Sta=4972.2,4985
Exp/Cntr=0.3,0.1

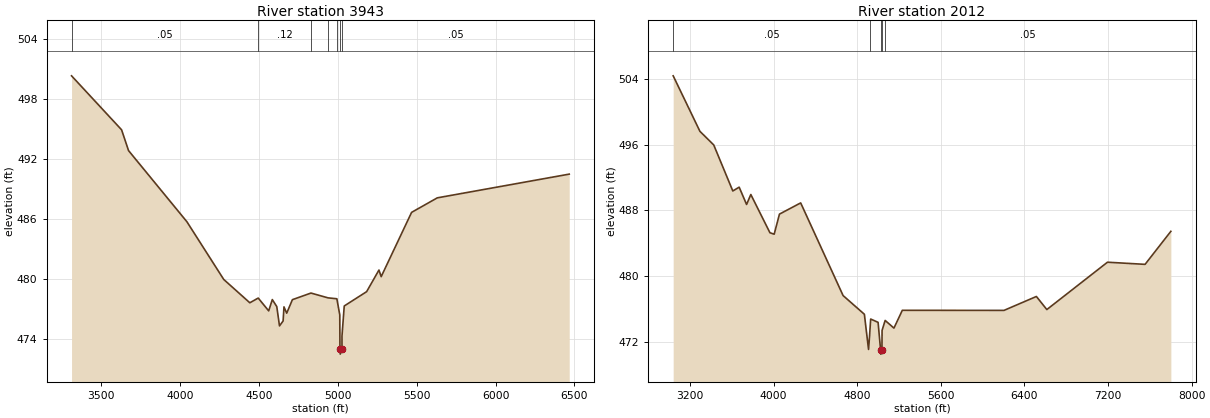
Type RM Length L Ch R = 1,3943,1931,1931,1931
BEGIN DESCRIPTION:
Berry Creek 11.0
END DESCRIPTION:
XS GIS Cut Line= 3
      2623413.01      6986505.89      2621885.89      6987222.27
      2620761.10      6988163.89
#Sta/Elev= 30
  3313.2  500.32  3630.2  494.93  3674.4  492.85  4043.9  485.75  4277.6  479.98
  4442.9  477.65  4496.1  478.12  4562.5  476.84  4585.3  477.97  4613.7  477.27
  4630.9  475.34  4653.8  475.83  4659.3  477.24  4676.6  476.61  4712.7  477.96
  4830.3  478.62  4938.7  478.14  4994.4  478.05  5012.9  476.44  5014.0  473.02
  5015.8  472.52  5026.8  473.02  5026.9  474.33  5041.2  477.33  5183.1  478.76
  5261.1  480.92  5275.4  480.26  5468.0  486.68  5630.7  488.13  6466.9  490.50
#Mann=7,-1,0
  3313.2    0.05       0  4496.1    0.12       0  4830.3    0.05       0
  4938.7    0.12       0  4994.4    0.05       0  5014.0    0.03       0
  5026.8    0.05       0
Bank Sta=5014,5026.8
Exp/Cntr=0.3,0.1

Type RM Length L Ch R = 1,2012,0,0,0
BEGIN DESCRIPTION:
Berry Creek 9.0
END DESCRIPTION:
XS GIS Cut Line= 4
      2623608.32      6986076.19      2621559.18      6985722.79
      2620787.04      6985687.63      2620808.85      6987597.78
#Sta/Elev= 30
  3038.4  504.35  3294.4  497.61  3426.4  495.96  3609.0  490.37  3669.9  490.83
  3740.7  488.73  3781.5  489.94  3964.2  485.30  4004.8  485.12  4055.5  487.56
  4258.5  488.92  4664.4  477.67  4868.0  475.40  4907.9  471.13  4917.5  472.73
  4928.2  474.82  4999.2  474.42  5023.3  471.06  5025.1  470.56  5036.1  471.06
  5037.4  473.44  5066.9  474.65  5151.0  473.72  5231.1  475.88  6204.1  475.87
  6514.1  477.56  6614.1  475.97  7194.2  481.72  7554.2  481.46  7801.0  485.47
#Mann=5,-1,0
  3038.4    0.05       0  4917.5    0.12       0  5023.3    0.07       0
  5036.1    0.12       0  5066.9    0.05       0
Bank Sta=5023.3,5036.1
Exp/Cntr=0.3,0.1

Chan Stop Cuts=-1