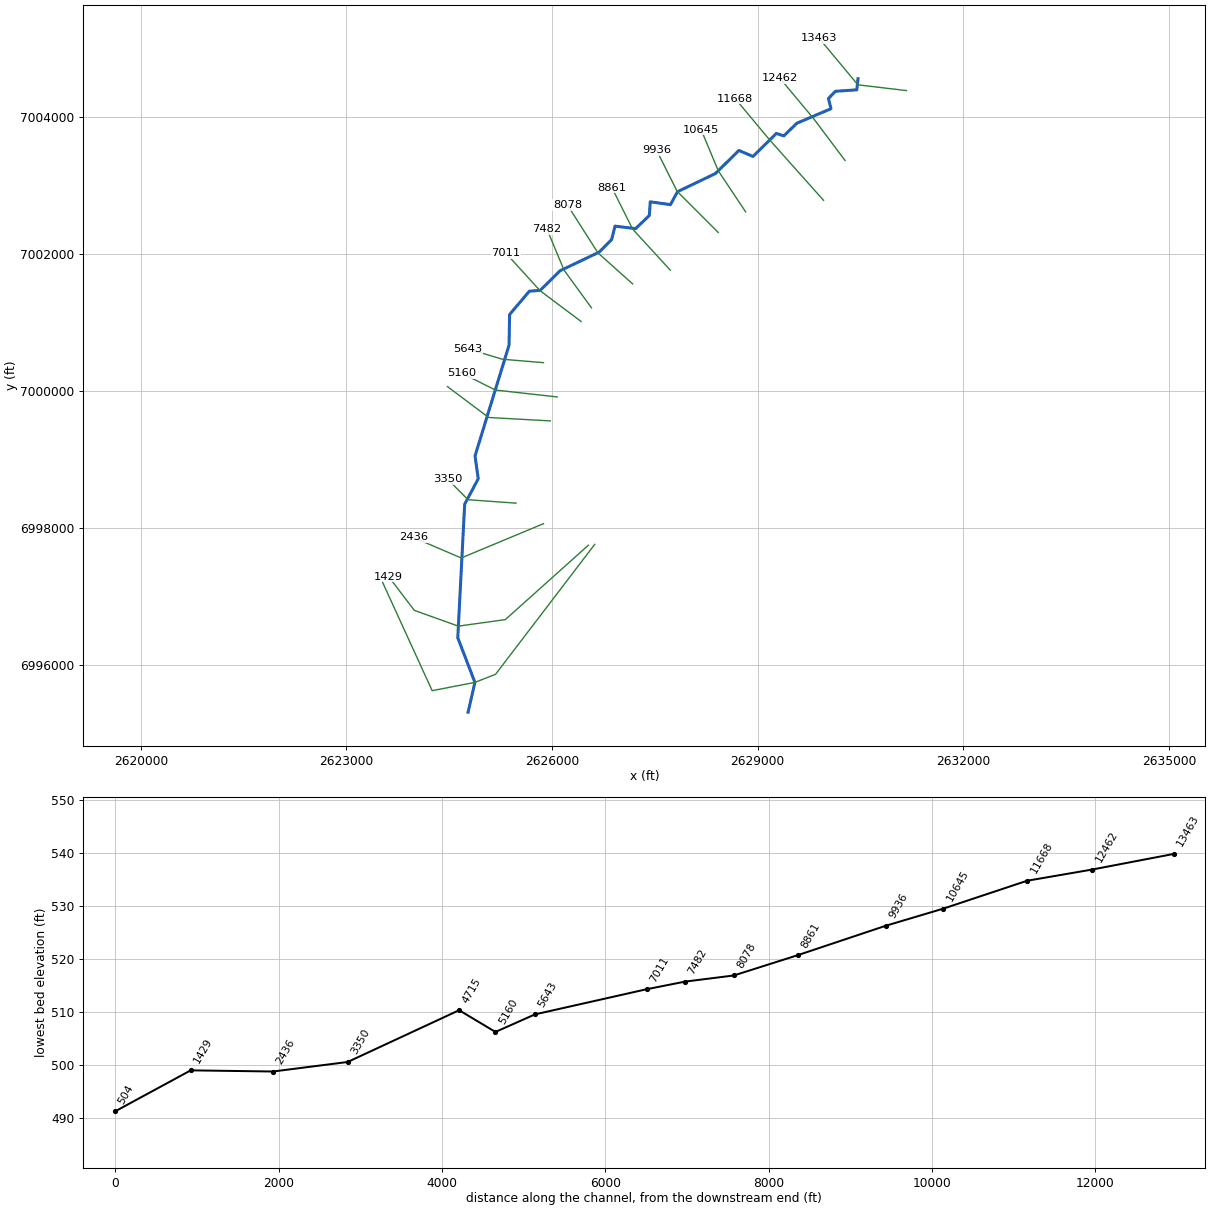
--- Berry Creek Trib 1.prj (project) ---

Proj Title=Berry Creek Trib 1 Base Level Engineering
Current Plan=p01
Default Exp/Contr=0.3,0.1
English Units
Geom File=g01
Flow File=f01
Plan File=p01
BEGIN DESCRIPTION:
Berry Creek Trib 1
END DESCRIPTION:

--- Berry Creek Trib 1.p01 (plan) ---

Plan Title=Multiple Run
Short Identifier=Multiple
Geom File=g01
Flow File=f01
Subcritical Flow
K Sum by GR= 0
Std Step Tol= 0.01
Critical Tol= 0.01
Num of Std Step Trials= 20
Max Error Tol= 0.3
Flow Tol Ratio= 0.001
Split Flow NTrial= 30
Split Flow Tol= 0.02
Split Flow Ratio= 0.02
Log Output Level= 0
Friction Slope Method= 1
Unsteady Friction Slope Method= 2
Unsteady Bridges Friction Slope Method= 1
Parabolic Critical Depth
Global Vel Dist=  1 , 1 , 1
Global Log Level= 0
CheckData=True
Encroach Param= -1, 0, 0, 0
BEGIN DESCRIPTION:
Multiple Run
END DESCRIPTION:

--- Berry Creek Trib 1.f01 (steady flow) ---

Flow Title=Multiple
Number of Profiles=7
Profile Names=10-year,25-year,50-year,1pct_min,100-year,1pct_plu,500-year
River Rch & RM= Berry Creek Trib,Reach-1,13463
     310     395     460     266     532    1061     708
River Rch & RM= Berry Creek Trib,Reach-1,8861
     567     750     896     530    1058    2110    1474
River Rch & RM= Berry Creek Trib,Reach-1,2436
     639     851    1021     607    1211    2417    1703
Boundary for River Rch & Prof#=Berry Creek Trib,Reach-1,1
Up Type=0
Dn Type=3
Dn Slope=0.005
Boundary for River Rch & Prof#=Berry Creek Trib,Reach-1,2
Up Type=0
Dn Type=3
Dn Slope=0.005
Boundary for River Rch & Prof#=Berry Creek Trib,Reach-1,3
Up Type=0
Dn Type=3
Dn Slope=0.005
Boundary for River Rch & Prof#=Berry Creek Trib,Reach-1,4
Up Type=0
Dn Type=3
Dn Slope=0.005
Boundary for River Rch & Prof#=Berry Creek Trib,Reach-1,5
Up Type=0
Dn Type=3
Dn Slope=0.005
Boundary for River Rch & Prof#=Berry Creek Trib,Reach-1,6
Up Type=0
Dn Type=3
Dn Slope=0.005
Boundary for River Rch & Prof#=Berry Creek Trib,Reach-1,7
Up Type=0
Dn Type=3
Dn Slope=0.005

--- Berry Creek Trib 1.g01 (geometry) ---

Geom Title=Existing Conditions

River Reach=Berry Creek Trib,Reach-1
Reach XY= 30
      2630465.10      7004554.04      2630446.90      7004391.96
      2630135.27      7004370.82      2630033.80      7004264.42
      2630070.90      7004116.44      2629573.70      7003905.17
      2629382.73      7003720.15      2629273.71      7003755.88
      2628932.67      7003419.96      2628727.50      7003507.54
      2628382.17      7003168.88      2627831.44      7002905.75
      2627728.68      7002716.29      2627433.91      7002758.10
      2627420.54      7002558.55      2627220.41      7002366.54
      2626919.50      7002403.38      2626870.54      7002208.54
      2626689.60      7002024.34      2626119.94      7001752.86
      2625828.45      7001466.47      2625669.48      7001453.32
      2625381.52      7001113.43      2625373.76      7000666.93
      2624877.22      6999050.50      2624924.03      6998716.89
      2624726.13      6998345.60      2624625.51      6996395.51
      2624875.62      6995745.72      2624776.00      6995311.00

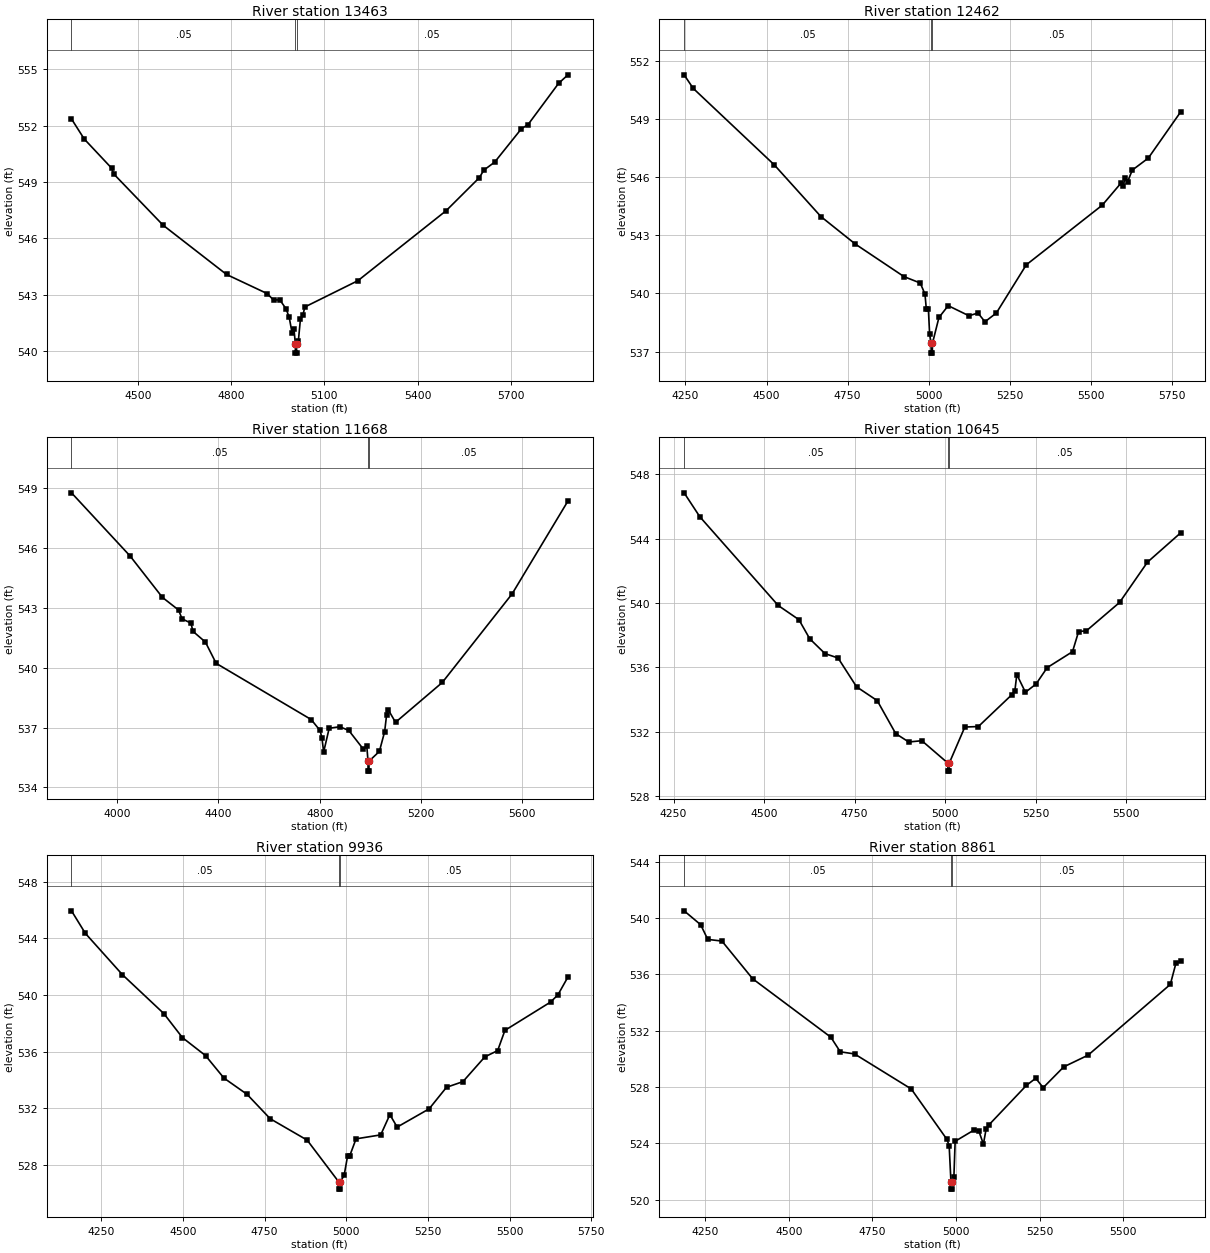
Type RM Length L Ch R = 1,13463,1001,1001,1001
BEGIN DESCRIPTION:
Berry Creek Trib 1 32.0
END DESCRIPTION:
XS GIS Cut Line= 3
      2631171.33      7004381.13      2630462.89      7004465.04
      2629897.92      7005144.16
#Sta/Elev= 30
  4286.6  552.36  4327.6  551.29  4415.5  549.74  4422.9  549.42  4581.0  546.70
  4785.4  544.07  4916.3  543.05  4936.4  542.71  4956.6  542.72  4976.7  542.24
  4986.8  541.79  4995.9  540.97  5002.1  541.17  5006.6  540.38  5006.9  539.88
  5010.4  539.88  5010.6  540.38  5016.4  540.55  5022.9  541.69  5030.7  541.90
  5037.2  542.34  5207.8  543.74  5491.6  547.47  5598.4  549.23  5612.7  549.63
  5647.8  550.06  5733.8  551.84  5754.6  552.05  5853.5  554.26  5883.4  554.71
#Mann=3,-1,0
  4286.6    0.05       0  5006.6   0.035       0  5010.6    0.05       0
Bank Sta=5006.6,5010.6
Exp/Cntr=0.3,0.1

Type RM Length L Ch R = 1,12462,794,794,794
BEGIN DESCRIPTION:
Berry Creek Trib 1 31.0
END DESCRIPTION:
XS GIS Cut Line= 3
      2630275.99      7003361.01      2629826.00      7003961.00
      2629326.01      7004560.99
#Sta/Elev= 30
  4245.9  551.29  4274.0  550.59  4524.0  546.64  4667.8  543.97  4774.0  542.55
  4924.0  540.87  4974.0  540.54  4988.6  539.97  4992.8  539.20  4999.1  539.20
  5003.0  537.90  5007.6  537.42  5007.8  536.92  5011.3  536.92  5011.6  537.42
  5031.7  538.76  5060.3  539.37  5124.1  538.85  5152.1  538.99  5173.6  538.54
  5208.7  538.99  5301.1  541.48  5535.4  544.56  5592.7  545.69  5599.2  545.57
  5607.0  545.96  5613.5  545.77  5627.9  546.37  5677.3  546.99  5776.9  549.37
#Mann=3,-1,0
  4245.9    0.05       0  5007.6   0.035       0  5011.6    0.05       0
Bank Sta=5007.6,5011.6
Exp/Cntr=0.3,0.1

Type RM Length L Ch R = 1,11668,1023,1023,1023
BEGIN DESCRIPTION:
Berry Creek Trib 1 28.0
END DESCRIPTION:
XS GIS Cut Line= 3
      2629962.06      7002779.91      2629176.00      7003661.00
      2628676.00      7004261.00
#Sta/Elev= 30
  3819.2  548.78  4050.7  545.61  4178.6  543.53  4242.1  542.90  4256.3  542.45
  4291.4  542.24  4298.9  541.83  4348.3  541.29  4390.9  540.22  4766.3  537.40
  4801.4  536.85  4808.9  536.47  4815.6  535.77  4837.4  536.96  4879.4  537.04
  4915.1  536.85  4972.0  535.92  4986.2  536.05  4990.9  535.31  4991.1  534.81
  4994.6  534.81  4994.9  535.31  5035.8  535.80  5056.6  536.79  5064.4  537.64
  5070.9  537.89  5099.6  537.26  5284.4  539.26  5560.4  543.71  5781.0  548.37
#Mann=3,-1,0
  3819.2    0.05       0  4990.9   0.035       0  4994.9    0.05       0
Bank Sta=4990.9,4994.9
Exp/Cntr=0.3,0.1

Type RM Length L Ch R = 1,10645,709,709,709
BEGIN DESCRIPTION:
Berry Creek Trib 1 24.0
END DESCRIPTION:
XS GIS Cut Line= 3
      2628825.98      7002611.03      2628426.00      7003211.00
      2628175.99      7003811.02
#Sta/Elev= 30
  4279.0  546.84  4322.5  545.35  4538.9  539.84  4596.0  538.96  4626.0  537.77
  4668.1  536.85  4704.1  536.58  4755.2  534.79  4812.3  533.93  4863.4  531.88
  4899.4  531.36  4935.5  531.44  5007.3  530.05  5007.5  529.55  5011.0  529.55
  5011.3  530.05  5054.2  532.29  5091.6  532.32  5184.2  534.30  5192.4  534.54
  5197.8  535.55  5221.6  534.45  5250.9  534.96  5281.7  535.98  5351.6  536.97
  5368.4  538.22  5390.1  538.27  5481.6  540.03  5558.5  542.53  5650.1  544.35
#Mann=3,-1,0
  4279.0    0.05       0  5007.3    0.03       0  5011.3    0.05       0
Bank Sta=5007.3,5011.3
Exp/Cntr=0.3,0.1

Type RM Length L Ch R = 1,9936,1075,1075,1075
BEGIN DESCRIPTION:
Berry Creek Trib 1 21.0
END DESCRIPTION:
XS GIS Cut Line= 3
      2628425.97      7002311.03      2627826.00      7002911.00
      2627526.00      7003511.00
#Sta/Elev= 30
  4159.1  545.94  4201.5  544.35  4314.6  541.44  4441.9  538.68  4498.5  536.99
  4569.2  535.72  4625.7  534.13  4696.5  532.98  4767.2  531.26  4880.3  529.75
  4977.3  526.79  4977.6  526.29  4981.1  526.29  4981.3  526.79  4993.4  527.26
  5004.0  528.63  5010.4  528.63  5029.9  529.84  5105.4  530.12  5133.4  531.55
  5155.7  530.67  5253.6  531.96  5306.7  533.48  5357.0  533.88  5424.1  535.63
  5463.2  536.07  5485.5  537.50  5625.3  539.50  5647.7  540.01  5678.4  541.27
#Mann=3,-1,0
  4159.1    0.05       0  4977.3    0.03       0  4981.3    0.05       0
Bank Sta=4977.3,4981.3
Exp/Cntr=0.3,0.1

Type RM Length L Ch R = 1,8861,783,783,783
BEGIN DESCRIPTION:
Berry Creek Trib 1 17.0
END DESCRIPTION:
XS GIS Cut Line= 3
      2627725.97      7001761.03      2627176.00      7002361.00
      2626876.01      7002960.98
#Sta/Elev= 30
  4186.9  540.52  4236.5  539.53  4257.5  538.49  4300.0  538.37  4391.9  535.69
  4625.6  531.54  4653.9  530.50  4696.5  530.35  4866.1  527.86  4972.7  524.28
  4979.5  523.83  4984.9  521.24  4985.2  520.74  4988.7  520.74  4988.9  521.24
  4993.7  521.63  4997.4  524.14  5053.9  524.94  5067.9  524.89  5081.9  523.94
  5090.2  525.03  5098.6  525.31  5210.4  528.11  5238.4  528.62  5260.7  527.95
  5322.2  529.43  5394.9  530.26  5640.9  535.29  5657.6  536.79  5671.6  536.92
#Mann=3,-1,0
  4186.9    0.05       0  4984.9   0.035       0  4988.9    0.05       0
Bank Sta=4984.9,4988.9
Exp/Cntr=0.3,0.1

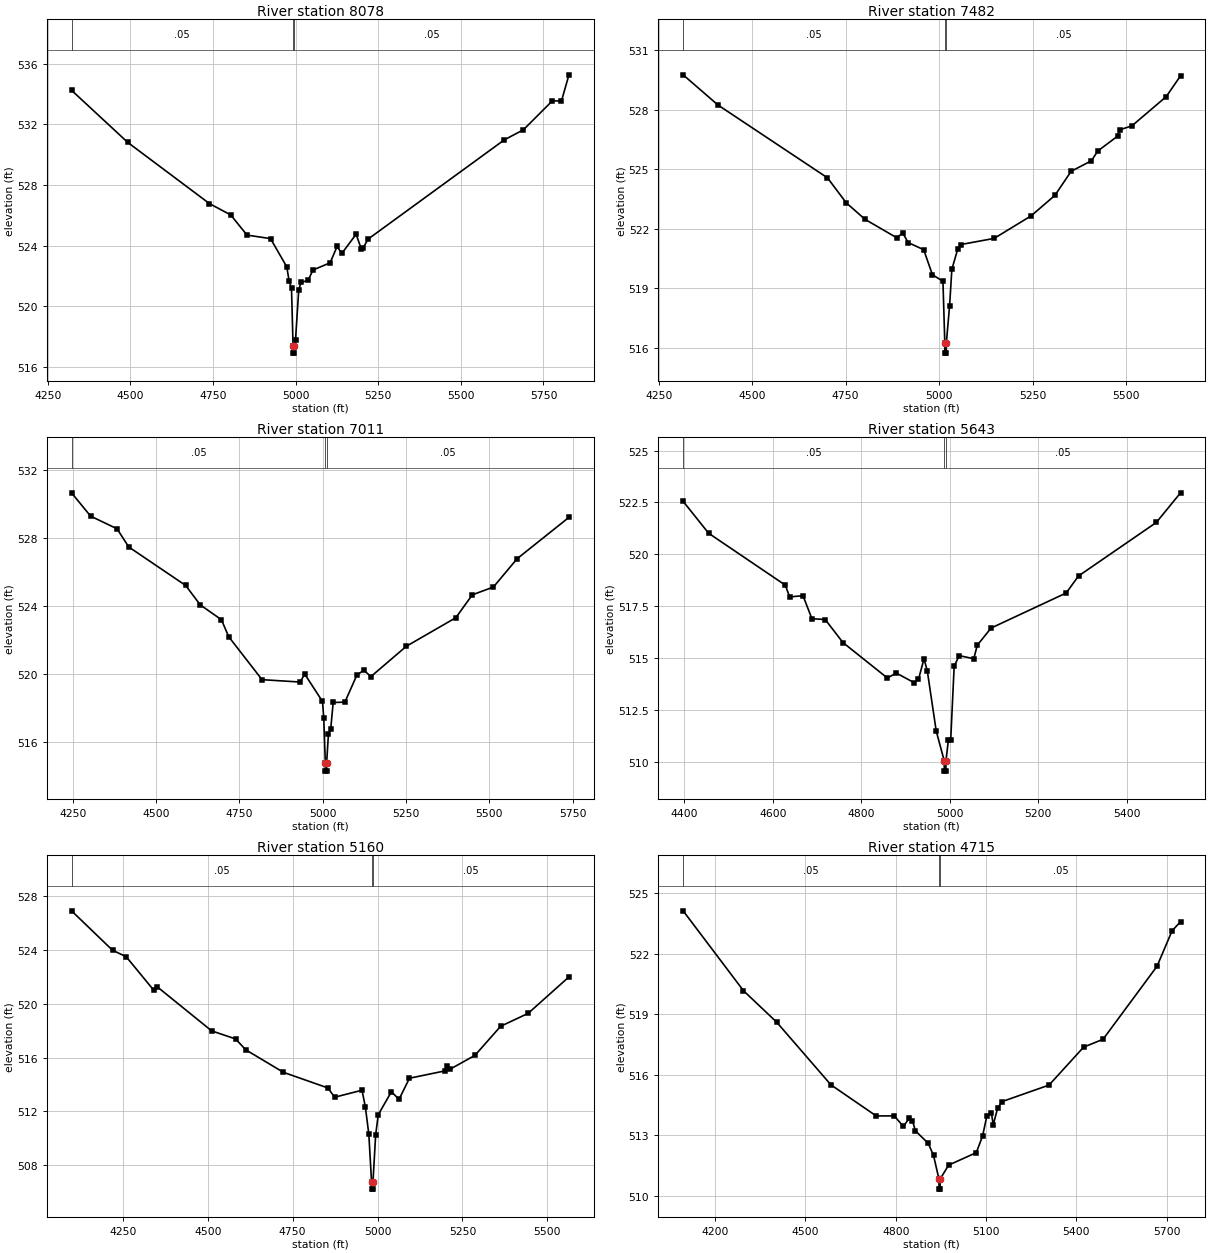
Type RM Length L Ch R = 1,8078,596,596,596
BEGIN DESCRIPTION:
Berry Creek Trib 1 15.0
END DESCRIPTION:
XS GIS Cut Line= 3
      2627175.98      7001561.02      2626670.20      7002013.13
      2626226.02      7002710.96
#Sta/Elev= 30
  4321.6  534.25  4491.7  530.81  4739.1  526.77  4803.5  526.02  4852.8  524.69
  4923.9  524.46  4973.2  522.59  4979.9  521.69  4987.4  521.17  4992.1  517.40
  4992.4  516.90  4995.9  516.90  4996.1  517.40  4999.5  517.76  5009.3  521.08
  5016.2  521.57  5037.4  521.70  5052.6  522.39  5104.2  522.86  5125.4  523.94
  5139.7  523.48  5183.0  524.75  5198.2  523.80  5204.1  523.84  5219.4  524.43
  5631.7  530.98  5689.2  531.64  5777.3  533.56  5804.4  533.53  5827.2  535.27
#Mann=3,-1,0
  4321.6    0.05       0  4992.1   0.035       0  4996.1    0.05       0
Bank Sta=4992.1,4996.1
Exp/Cntr=0.3,0.1

Type RM Length L Ch R = 1,7482,471,471,471
BEGIN DESCRIPTION:
Berry Creek Trib 1 14.0
END DESCRIPTION:
XS GIS Cut Line= 3
      2626575.98      7001211.03      2626176.00      7001761.00
      2625926.01      7002360.97
#Sta/Elev= 30
  4315.4  529.76  4408.5  528.24  4701.4  524.57  4751.6  523.31  4801.8  522.48
  4887.6  521.54  4902.3  521.81  4917.0  521.31  4958.7  520.95  4981.9  519.69
  5010.1  519.36  5015.1  516.24  5015.4  515.74  5018.9  515.74  5019.1  516.24
  5027.9  518.13  5033.9  519.96  5049.6  520.98  5057.7  521.21  5147.1  521.52
  5246.2  522.66  5309.6  523.69  5352.9  524.90  5407.1  525.43  5423.9  525.92
  5477.0  526.67  5482.9  526.99  5515.4  527.19  5607.0  528.66  5645.4  529.71
#Mann=3,-1,0
  4315.4    0.05       0  5015.1   0.035       0  5019.1    0.05       0
Bank Sta=5015.1,5019.1
Exp/Cntr=0.3,0.1

Type RM Length L Ch R = 1,7011,1368,1368,1368
BEGIN DESCRIPTION:
Berry Creek Trib 1 13.0
END DESCRIPTION:
XS GIS Cut Line= 3
      2626426.02      7001010.99      2625826.00      7001461.00
      2625326.02      7002010.98
#Sta/Elev= 30
  4245.8  530.64  4303.1  529.27  4382.3  528.53  4417.7  527.46  4588.5  525.20
  4632.3  524.06  4695.8  523.19  4717.7  522.19  4817.7  519.67  4932.3  519.53
  4945.8  520.00  4999.2  518.39  5002.9  517.43  5007.7  514.80  5007.9  514.30
  5011.4  514.30  5011.7  514.80  5017.1  516.50  5023.9  516.78  5031.3  518.33
  5066.4  518.35  5102.2  519.93  5123.2  520.23  5144.5  519.85  5250.9  521.63
  5399.6  523.31  5448.9  524.65  5512.4  525.11  5583.4  526.77  5739.1  529.20
#Mann=3,-1,0
  4245.8    0.05       0  5007.7    0.03       0  5011.7    0.05       0
Bank Sta=5007.7,5011.7
Exp/Cntr=0.3,0.1

Type RM Length L Ch R = 1,5643,483,483,483
BEGIN DESCRIPTION:
Berry Creek Trib 1 10.0
END DESCRIPTION:
XS GIS Cut Line= 3
      2625875.97      7000411.00      2625276.00      7000461.00
      2624775.97      7000611.01
#Sta/Elev= 30
  4397.6  522.55  4455.3  521.01  4628.4  518.51  4638.4  517.94  4668.5  518.00
  4688.6  516.89  4718.7  516.85  4758.8  515.74  4859.2  514.03  4879.2  514.27
  4919.4  513.81  4929.4  513.96  4942.0  514.96  4949.5  514.36  4969.5  511.48
  4987.6  510.04  4987.9  509.54  4991.4  509.54  4991.6  510.04  4997.1  511.05
  5002.3  511.05  5010.1  514.59  5021.4  515.11  5054.5  514.96  5062.3  515.61
  5093.6  516.44  5263.3  518.13  5291.1  518.95  5466.9  521.53  5521.7  522.96
#Mann=3,-1,0
  4397.6    0.05       0  4987.6    0.03       0  4991.6    0.05       0
Bank Sta=4987.6,4991.6
Exp/Cntr=0.3,0.1

Type RM Length L Ch R = 1,5160,445,445,445
BEGIN DESCRIPTION:
Berry Creek Trib 1 9.0
END DESCRIPTION:
XS GIS Cut Line= 3
      2626075.95      6999911.01      2625176.00      7000011.00
      2624676.01      7000261.00
#Sta/Elev= 30
  4099.0  526.90  4219.7  523.97  4259.9  523.49  4340.4  521.02  4350.5  521.27
  4511.5  517.98  4581.9  517.38  4612.1  516.57  4722.8  514.90  4853.6  513.74
  4873.7  513.05  4954.2  513.57  4964.2  512.31  4974.3  510.29  4982.4  506.72
  4982.6  506.22  4986.1  506.22  4986.4  506.72  4994.4  510.25  5002.0  511.75
  5040.8  513.46  5063.2  512.89  5093.9  514.46  5197.4  515.00  5205.7  515.38
  5214.1  515.14  5286.8  516.16  5362.3  518.32  5443.3  519.28  5563.5  521.99
#Mann=3,-1,0
  4099.0    0.05       0  4982.4   0.035       0  4986.4    0.05       0
Bank Sta=4982.4,4986.4
Exp/Cntr=0.3,0.1

Type RM Length L Ch R = 1,4715,1365,1365,1365
BEGIN DESCRIPTION:
Berry Creek Trib 1 8.0
END DESCRIPTION:
XS GIS Cut Line= 3
      2625976.01      6999561.00      2625076.00      6999611.00
      2624476.00      7000061.00
#Sta/Elev= 30
  4094.3  524.13  4294.6  520.17  4404.8  518.61  4585.1  515.50  4735.3  513.96
  4795.4  513.96  4825.4  513.44  4845.5  513.85  4855.5  513.73  4865.5  513.22
  4908.1  512.60  4925.6  512.00  4943.6  510.83  4943.9  510.33  4947.4  510.33
  4947.6  510.83  4975.7  511.52  5067.6  512.14  5088.4  512.96  5103.0  513.98
  5117.6  514.12  5123.8  513.52  5138.4  514.34  5153.0  514.67  5309.2  515.49
  5423.8  517.37  5488.4  517.76  5667.6  521.38  5717.6  523.14  5745.7  523.59
#Mann=3,-1,0
  4094.3    0.05       0  4943.6    0.03       0  4947.6    0.05       0
Bank Sta=4943.6,4947.6
Exp/Cntr=0.3,0.1

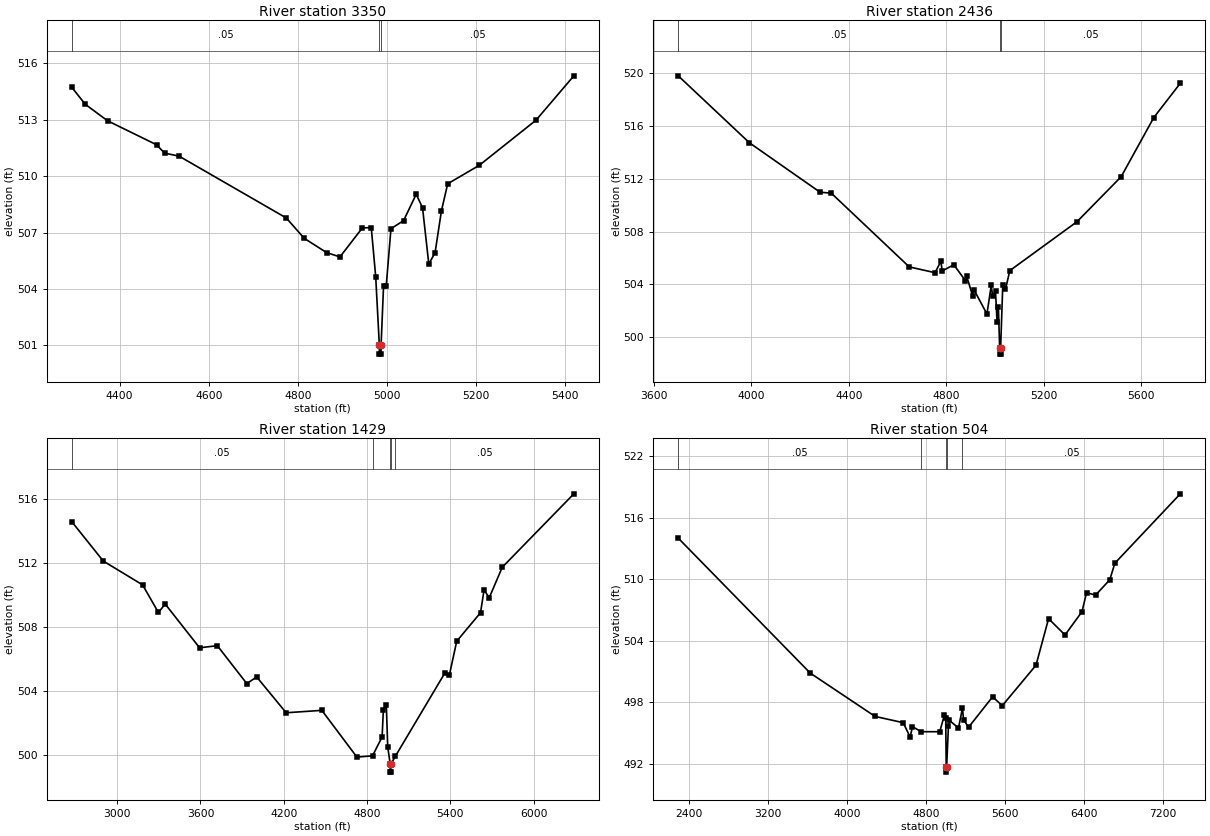
Type RM Length L Ch R = 1,3350,914,914,914
BEGIN DESCRIPTION:
Berry Creek Trib 1 5.0
END DESCRIPTION:
XS GIS Cut Line= 3
      2625476.01      6998361.00      2624776.00      6998411.00
      2624475.97      6998711.03
#Sta/Elev= 30
  4292.9  514.73  4323.0  513.83  4373.1  512.95  4483.4  511.67  4500.9  511.23
  4533.5  511.07  4774.1  507.78  4814.2  506.70  4864.4  505.94  4894.4  505.71
  4944.6  507.25  4964.6  507.27  4974.6  504.66  4982.7  501.04  4982.9  500.54
  4986.4  500.54  4986.7  501.04  4992.2  504.17  4998.2  504.17  5008.8  507.21
  5037.1  507.64  5065.4  509.04  5079.6  508.33  5093.7  505.33  5107.8  505.94
  5122.0  508.16  5136.1  509.60  5206.8  510.58  5334.1  512.98  5419.0  515.34
#Mann=3,-1,0
  4292.9    0.05       0  4982.7    0.03       0  4986.7    0.05       0
Bank Sta=4982.7,4986.7
Exp/Cntr=0.3,0.1

Type RM Length L Ch R = 1,2436,1007,1007,1007
BEGIN DESCRIPTION:
Berry Creek Trib 1 3.0
END DESCRIPTION:
XS GIS Cut Line= 3
      2625875.97      6998060.99      2624676.00      6997561.00
      2623976.04      6997860.98
#Sta/Elev= 30
  3700.0  519.76  3992.5  514.70  4282.3  510.97  4328.3  510.90  4648.4  505.33
  4754.6  504.89  4778.4  505.76  4783.8  505.02  4831.5  505.49  4879.2  504.29
  4884.6  504.62  4908.4  503.16  4913.8  503.62  4967.5  501.77  4985.3  503.94
  4990.8  503.12  5002.7  503.49  5009.0  501.19  5014.5  502.31  5019.7  499.24
  5020.0  498.74  5023.5  498.74  5023.8  499.24  5032.6  503.99  5043.5  503.63
  5061.6  505.05  5337.2  508.74  5518.6  512.14  5652.7  516.61  5761.5  519.20
#Mann=3,-1,0
  3700.0    0.05       0  5019.7    0.03       0  5023.8    0.05       0
Bank Sta=5019.7,5023.8
Exp/Cntr=0.3,0.1

Type RM Length L Ch R = 1,1429,925,925,925
BEGIN DESCRIPTION:
Mapping XS c01333ed
END DESCRIPTION:
XS GIS Cut Line= 5
      2626530.58      6997746.88      2625319.67      6996661.83
      2624633.90      6996566.34      2623991.54      6996796.38
      2623618.61      6997286.39
#Sta/Elev= 30
  2673.3  514.61  2900.2  512.15  3183.5  510.66  3297.1  508.94  3346.5  509.46
  3594.0  506.73  3721.8  506.86  3934.1  504.49  4005.1  504.91  4217.5  502.67
  4474.6  502.82  4727.0  499.90  4839.7  499.98  4908.7  501.16  4917.7  502.86
  4939.0  503.16  4949.1  500.52  4967.1  499.46  4967.5  498.96  4971.1  498.96
  4971.4  499.46  5004.0  499.95  5361.1  505.16  5393.0  505.02  5446.1  507.14
  5617.4  508.92  5642.9  510.34  5680.4  509.86  5773.9  511.76  6289.7  516.35
#Mann=5,-1,0
  2673.3    0.05       0  4839.7    0.12       0  4967.1    0.07       0
  4971.4    0.12       0  5004.0    0.05       0
Bank Sta=4967.1,4971.4
Exp/Cntr=0.3,0.1

Type RM Length L Ch R = 1,504,0,0,0
BEGIN DESCRIPTION:
Berry Creek Trib 1 1.0
END DESCRIPTION:
XS GIS Cut Line= 5
      2626623.54      6997759.10      2625176.44      6995863.22
      2624875.62      6995745.72      2624251.96      6995624.50
      2623526.02      6997210.96
#Sta/Elev= 30
  2292.0  514.02  3630.3  500.86  4287.0  496.64  4571.8  496.03  4642.5  494.62
  4665.3  495.65  4754.2  495.15  4942.4  495.15  4988.9  496.77  5002.4  496.47
  5007.7  491.71  5008.0  491.21  5012.0  491.71  5030.2  495.71  5040.4  496.25
  5132.0  495.51  5172.5  497.45  5183.0  496.33  5233.9  495.58  5478.4  498.56
  5575.1  497.68  5917.4  501.63  6045.0  506.17  6211.6  504.58  6383.7  506.85
  6429.8  508.70  6521.8  508.47  6665.2  509.96  6716.9  511.58  7380.0  518.34
#Mann=5,-1,0
  2292.0    0.05       0  4754.2    0.12       0  5007.7    0.07       0
  5012.0    0.12       0  5172.5    0.05       0
Bank Sta=5007.7,5012
Exp/Cntr=0.3,0.1

Chan Stop Cuts=-1