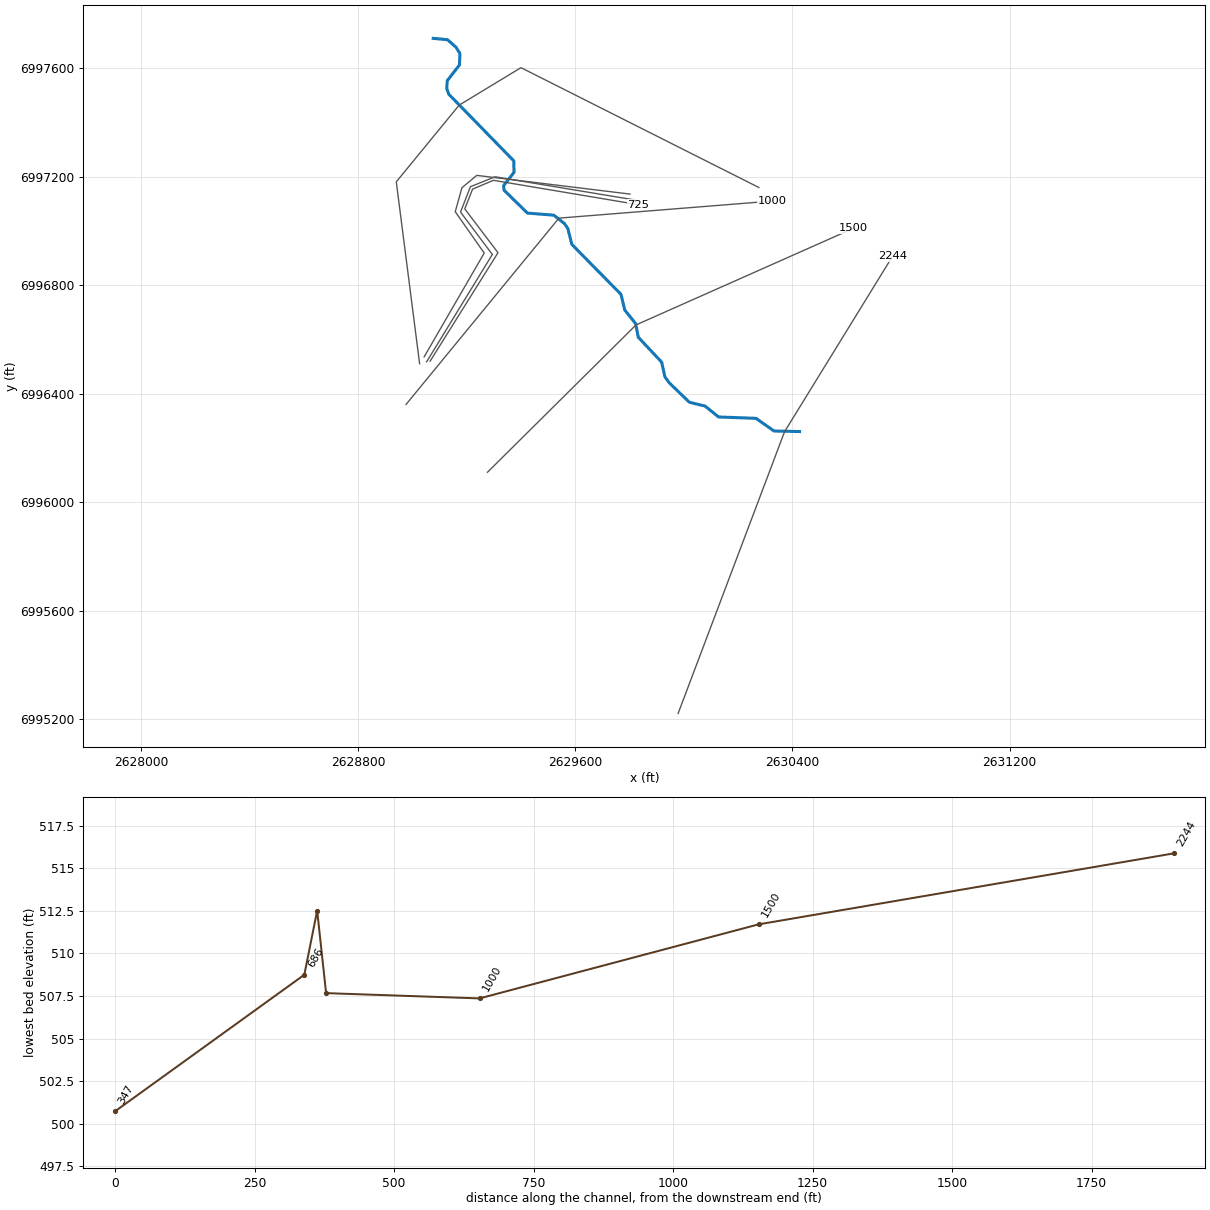
--- Berry Creek Trib 10.prj (project) ---

Proj Title=Berry Creek Trib 10 Base Level Engineering
Current Plan=p01
Default Exp/Contr=0.3,0.1
English Units
Geom File=g01
Flow File=f01
Plan File=p01
BEGIN DESCRIPTION:
Berry Creek Trib 10
END DESCRIPTION:

--- Berry Creek Trib 10.p01 (plan) ---

Plan Title=Multiple Run
Short Identifier=Multiple
Geom File=g01
Flow File=f01
Subcritical Flow
K Sum by GR= 0
Std Step Tol= 0.01
Critical Tol= 0.01
Num of Std Step Trials= 20
Max Error Tol= 0.3
Flow Tol Ratio= 0.001
Split Flow NTrial= 30
Split Flow Tol= 0.02
Split Flow Ratio= 0.02
Log Output Level= 0
Friction Slope Method= 1
Unsteady Friction Slope Method= 2
Unsteady Bridges Friction Slope Method= 1
Parabolic Critical Depth
Global Vel Dist=  1 , 1 , 1
Global Log Level= 0
CheckData=True
Encroach Param= -1, 0, 0, 0
BEGIN DESCRIPTION:
Multiple Run
END DESCRIPTION:

--- Berry Creek Trib 10.f01 (steady flow) ---

Flow Title=Multiple
Number of Profiles=7
Profile Names=10-year,25-year,50-year,1pct_min,100-year,1pct_plu,500-year
River Rch & RM= Berry Creek Trib,Reach-1,2244
     220     276     319     183     366     730     479
Boundary for River Rch & Prof#=Berry Creek Trib,Reach-1,1
Up Type=0
Dn Type=3
Dn Slope=0.005
Boundary for River Rch & Prof#=Berry Creek Trib,Reach-1,2
Up Type=0
Dn Type=3
Dn Slope=0.005
Boundary for River Rch & Prof#=Berry Creek Trib,Reach-1,3
Up Type=0
Dn Type=3
Dn Slope=0.005
Boundary for River Rch & Prof#=Berry Creek Trib,Reach-1,4
Up Type=0
Dn Type=3
Dn Slope=0.005
Boundary for River Rch & Prof#=Berry Creek Trib,Reach-1,5
Up Type=0
Dn Type=3
Dn Slope=0.005
Boundary for River Rch & Prof#=Berry Creek Trib,Reach-1,6
Up Type=0
Dn Type=3
Dn Slope=0.005
Boundary for River Rch & Prof#=Berry Creek Trib,Reach-1,7
Up Type=0
Dn Type=3
Dn Slope=0.005

--- Berry Creek Trib 10.g01 (geometry) ---

Geom Title=Existing Conditions

River Reach=Berry Creek Trib,Reach-1
Reach XY= 30
      2630426.00      6996261.00      2630331.87      6996263.10
      2630265.50      6996309.79      2630127.56      6996314.76
      2630078.17      6996354.86      2630019.93      6996369.13
      2629945.77      6996440.87      2629929.97      6996462.64
      2629917.82      6996517.04      2629831.85      6996608.71
      2629821.81      6996659.27      2629782.10      6996708.81
      2629767.86      6996767.06      2629586.79      6996951.34
      2629572.12      6997009.60      2629559.54      6997028.13
      2629520.29      6997058.92      2629423.55      6997066.53
      2629337.10      6997150.92      2629335.33      6997167.54
      2629374.01      6997217.05      2629372.84      6997259.35
      2629133.48      6997504.94      2629125.96      6997526.34
      2629127.81      6997554.88      2629172.64      6997612.75
      2629174.55      6997655.11      2629160.13      6997678.04
      2629129.00      6997705.85      2629076.00      6997711.00

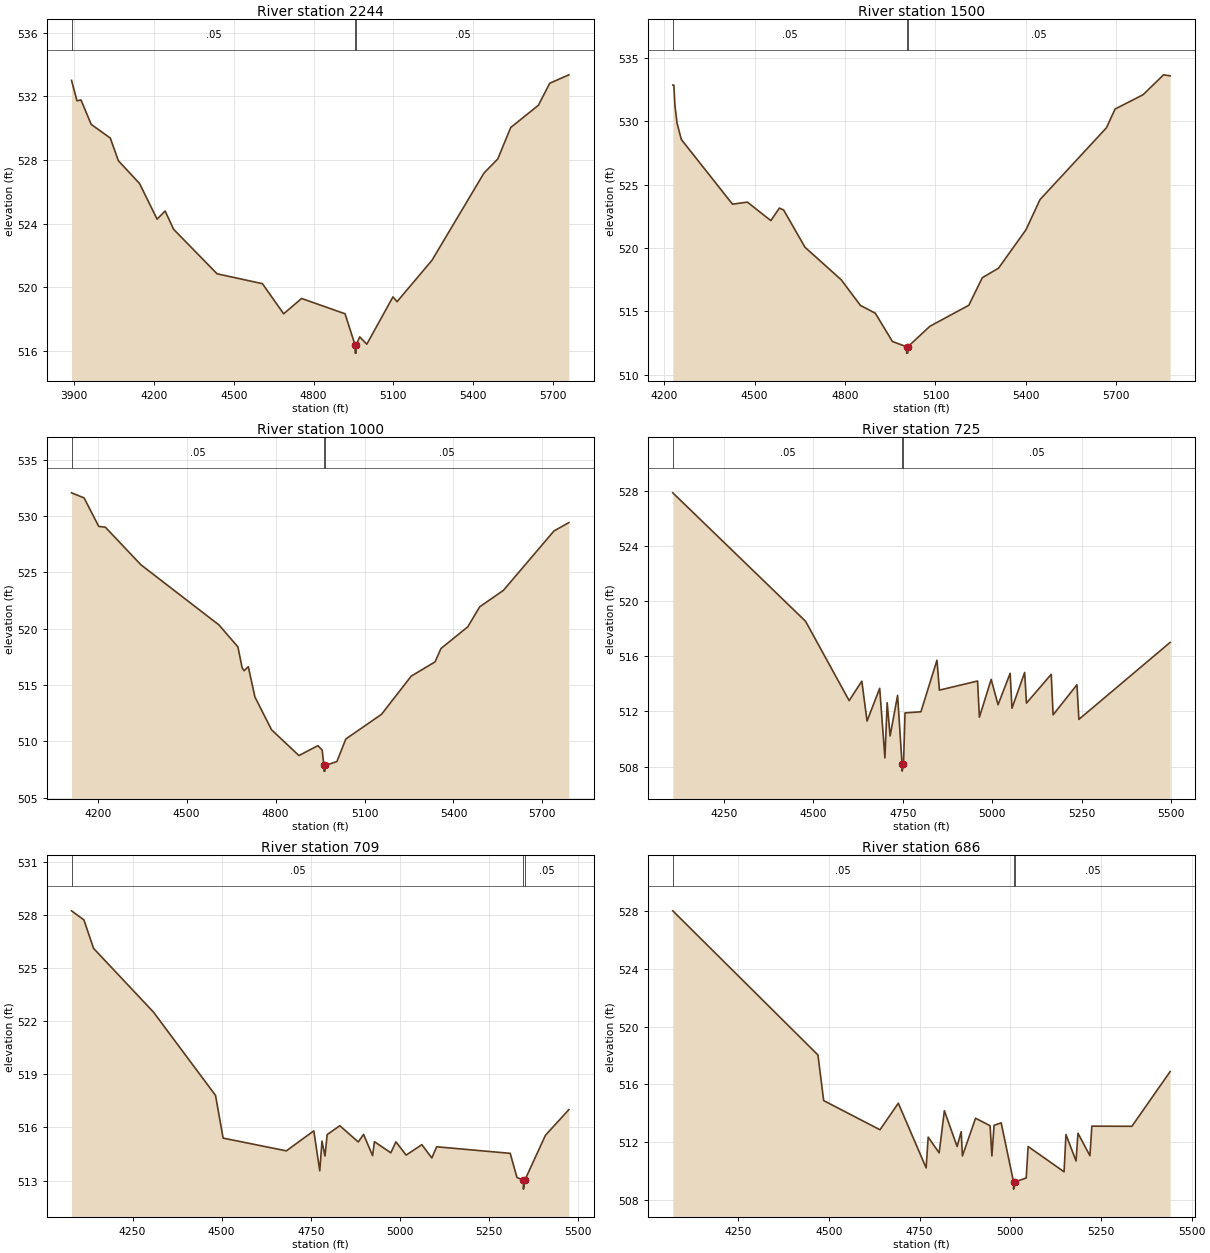
Type RM Length L Ch R = 1,2244,744,744,744
BEGIN DESCRIPTION:
Berry Creek Trib 10 4.0
END DESCRIPTION:
XS GIS Cut Line= 3
      2629978.67      6995221.84      2630370.71      6996260.30
      2630768.72      6996907.28
#Sta/Elev= 30
  3890.0  533.00  3910.5  531.72  3925.7  531.77  3963.9  530.24  4035.8  529.38
  4066.0  527.96  4145.6  526.53  4211.6  524.29  4241.8  524.80  4273.9  523.65
  4437.1  520.86  4607.5  520.24  4687.4  518.35  4754.9  519.31  4918.2  518.35
  4956.0  516.38  4956.2  515.88  4959.7  515.88  4960.0  516.38  4973.3  516.90
  5000.0  516.44  5098.3  519.41  5113.7  519.11  5245.1  521.71  5440.3  527.18
  5492.4  528.07  5540.9  530.04  5645.1  531.44  5687.6  532.82  5759.6  533.35
#Mann=3,-1,0
  3890.0    0.05       0  4956.0    0.03       0  4960.0    0.05       0
Bank Sta=4956,4960
Exp/Cntr=0.3,0.1

Type RM Length L Ch R = 1,1500,500,500,500
BEGIN DESCRIPTION:
Berry Creek Trib 10 3.0
END DESCRIPTION:
XS GIS Cut Line= 3
      2629276.03      6996111.03      2629823.42      6996654.27
      2630626.01      6997011.00
#Sta/Elev= 30
  4228.8  532.87  4232.3  532.87  4235.8  531.29  4242.9  529.87  4257.0  528.58
  4426.7  523.47  4476.3  523.63  4554.0  522.17  4582.3  523.16  4596.4  523.01
  4667.2  520.07  4787.4  517.50  4851.0  515.48  4900.5  514.86  4957.1  512.63
  5004.3  512.21  5004.5  511.71  5008.0  511.71  5008.3  512.21  5081.5  513.83
  5210.7  515.49  5255.2  517.66  5309.2  518.42  5400.2  521.45  5446.7  523.83
  5667.0  529.50  5695.7  530.98  5788.7  532.11  5856.4  533.68  5878.3  533.60
#Mann=3,-1,0
  4228.8    0.05       0  5004.3    0.03       0  5008.3    0.05       0
Bank Sta=5004.3,5008.3
Exp/Cntr=0.3,0.1

Type RM Length L Ch R = 1,1000,275,275,275
BEGIN DESCRIPTION:
Berry Creek Trib 10 2.0
END DESCRIPTION:
XS GIS Cut Line= 3
      2628976.02      6996361.03      2629539.34      6997047.99
      2630326.02      6997111.00
#Sta/Elev= 30
  4111.6  532.05  4153.9  531.60  4203.4  529.07  4225.7  529.00  4345.5  525.67
  4608.9  520.33  4672.8  518.38  4687.1  516.53  4693.6  516.27  4707.9  516.62
  4730.2  513.94  4786.2  511.03  4878.7  508.74  4942.6  509.62  4957.0  509.23
  4962.8  507.86  4963.1  507.36  4966.6  507.36  4966.8  507.86  5006.7  508.21
  5036.8  510.21  5157.2  512.40  5257.5  515.79  5337.7  517.05  5357.8  518.24
  5448.1  520.16  5488.2  521.93  5568.5  523.40  5739.0  528.67  5789.2  529.41
#Mann=3,-1,0
  4111.6    0.05       0  4962.8    0.03       0  4966.8    0.05       0
Bank Sta=4962.8,4966.8
Exp/Cntr=0.3,0.1

Type RM Length L Ch R = 1,725,16,16,16
BEGIN DESCRIPTION:
Mapping XS 942ee3aa
END DESCRIPTION:
XS GIS Cut Line= 6
      2629064.76      6996520.76      2629314.79      6996920.54
      2629192.39      6997082.00      2629221.04      6997154.92
      2629297.86      6997187.47      2629832.03      6997097.65
#Sta/Elev= 30
  4107.4  527.84  4478.3  518.53  4600.0  512.78  4635.4  514.19  4650.0  511.30
  4685.3  513.67  4699.9  508.63  4706.2  512.63  4714.4  510.22  4735.3  513.16
  4747.8  508.17  4748.1  507.67  4751.8  508.17  4756.1  511.89  4800.5  511.97
  4845.3  515.71  4852.1  513.54  4958.7  514.20  4963.8  511.58  4996.7  514.32
  5015.9  512.48  5049.7  514.76  5054.8  512.23  5090.2  514.82  5095.3  512.60
  5164.5  514.69  5169.7  511.75  5236.3  513.93  5241.7  511.42  5496.6  517.00
#Mann=3,-1,0
  4107.4    0.05       0  4747.8    0.03       0  4751.8    0.05       0
Bank Sta=4747.8,4751.8
Exp/Cntr=0.3,0.1

Type RM Length L Ch R = 1,709,23,23,23
BEGIN DESCRIPTION:
Mapping XS 02a75afb
END DESCRIPTION:
XS GIS Cut Line= 6
      2629051.77      6996518.21      2629293.95      6996914.03
      2629176.77      6997070.28      2629213.22      6997164.03
      2629304.37      6997200.49      2629821.80      6997114.57
#Sta/Elev= 30
  4078.5  528.23  4113.2  527.72  4140.4  526.11  4308.7  522.51  4482.8  517.81
  4504.1  515.40  4681.6  514.68  4758.7  515.81  4775.5  513.55  4781.7  515.23
  4790.1  514.39  4796.3  515.60  4831.8  516.10  4883.6  515.18  4898.5  515.61
  4923.8  514.41  4928.9  515.20  4975.0  514.57  4989.3  515.19  5018.0  514.44
  5062.0  515.03  5090.1  514.28  5103.7  514.91  5310.2  514.54  5329.1  513.18
  5347.1  513.02  5347.3  512.52  5351.1  513.02  5409.1  515.56  5474.9  517.01
#Mann=3,-1,0
  4078.5    0.05       0  5347.1    0.03       0  5351.1    0.05       0
Bank Sta=5347.1,5351.1
Exp/Cntr=0.3,0.1

Type RM Length L Ch R = 1,686,339,339,339
BEGIN DESCRIPTION:
Mapping XS 6f15d8d7
END DESCRIPTION:
XS GIS Cut Line= 6
      2629042.66      6996536.44      2629264.00      6996919.24
      2629157.23      6997071.59      2629181.97      6997160.13
      2629236.66      6997205.70      2629801.38      6997136.70
#Sta/Elev= 30
  4070.1  528.02  4470.1  518.04  4485.9  514.88  4641.1  512.86  4691.6  514.70
  4768.3  510.22  4773.9  512.35  4804.2  511.26  4818.5  514.18  4853.6  511.70
  4864.9  512.73  4868.3  511.05  4904.5  513.66  4944.5  513.14  4949.5  511.05
  4955.5  513.17  4975.1  513.34  5009.1  509.25  5009.3  508.75  5013.1  509.25
  5044.1  509.52  5049.3  511.70  5148.4  509.95  5153.6  512.53  5181.4  510.70
  5186.7  512.62  5219.7  511.06  5224.9  513.11  5335.3  513.10  5440.7  516.89
#Mann=3,-1,0
  4070.1    0.05       0  5009.1    0.03       0  5013.1    0.05       0
Bank Sta=5009.1,5013.1
Exp/Cntr=0.3,0.1

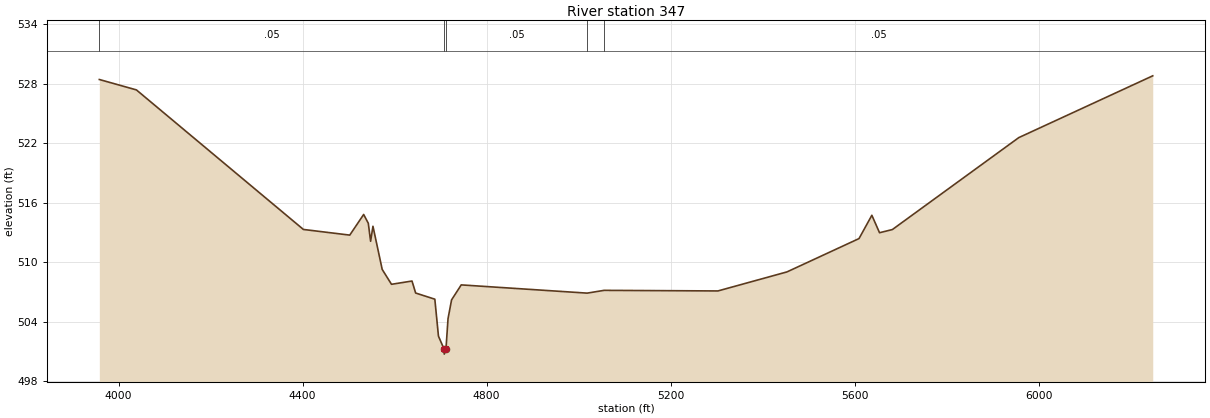
Type RM Length L Ch R = 1,347,0,0,0
BEGIN DESCRIPTION:
Berry Creek Trib 10 1.0
END DESCRIPTION:
XS GIS Cut Line= 5
      2629025.99      6996511.04      2628940.00      6997181.80
      2629171.75      6997464.77      2629399.51      6997602.86
      2630275.98      6997161.01
#Sta/Elev= 30
  3958.0  528.42  4038.6  527.37  4401.6  513.30  4502.4  512.73  4532.6  514.81
  4542.7  513.92  4547.7  512.11  4552.8  513.62  4572.9  509.27  4593.1  507.77
  4637.7  508.10  4645.6  506.89  4687.3  506.27  4695.2  502.54  4707.5  501.23
  4707.8  500.73  4711.5  501.23  4716.0  504.31  4723.7  506.20  4744.7  507.71
  5018.4  506.88  5055.3  507.16  5302.7  507.10  5452.8  509.02  5609.4  512.38
  5637.3  514.73  5654.0  512.97  5681.9  513.29  5956.7  522.56  6247.9  528.79
#Mann=5,-1,0
  3958.0    0.05       0  4707.5    0.03       0  4711.5    0.05       0
  5018.4    0.12       0  5055.3    0.05       0
Bank Sta=4707.5,4711.5
Exp/Cntr=0.3,0.1

Chan Stop Cuts=-1