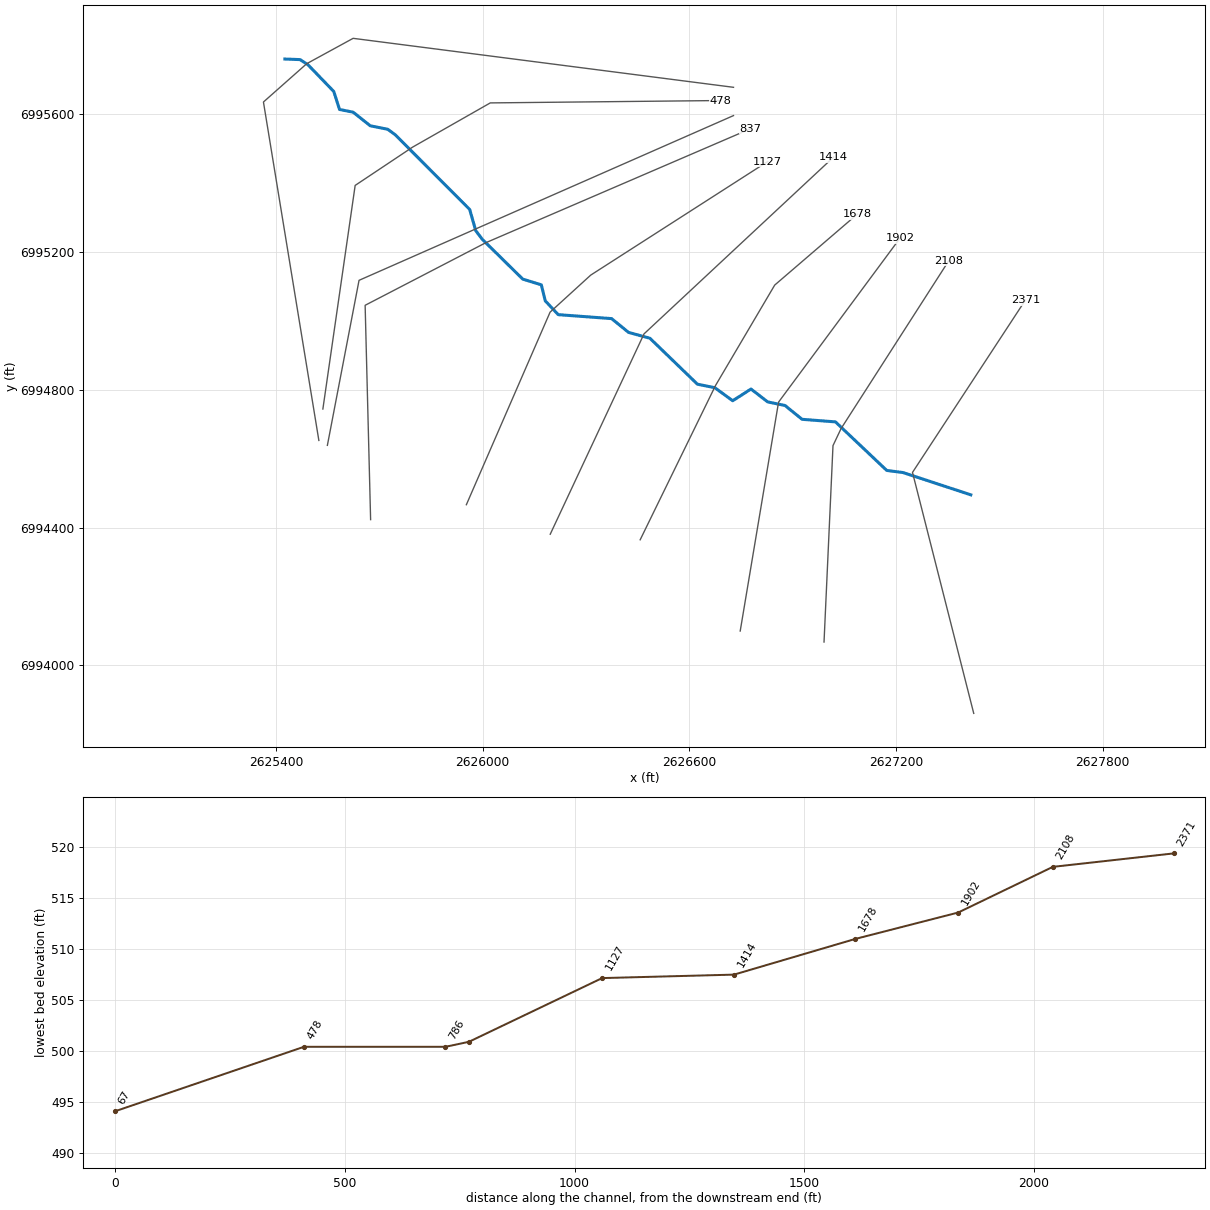
--- Berry Creek Trib 11.prj (project) ---

Proj Title=Berry Creek Trib 11 Base Level Engineering
Current Plan=p01
Default Exp/Contr=0.3,0.1
English Units
Geom File=g01
Flow File=f01
Plan File=p01
BEGIN DESCRIPTION:
Berry Creek Trib 11
END DESCRIPTION:

--- Berry Creek Trib 11.p01 (plan) ---

Plan Title=Multiple Run
Short Identifier=Multiple
Geom File=g01
Flow File=f01
Subcritical Flow
K Sum by GR= 0
Std Step Tol= 0.01
Critical Tol= 0.01
Num of Std Step Trials= 20
Max Error Tol= 0.3
Flow Tol Ratio= 0.001
Split Flow NTrial= 30
Split Flow Tol= 0.02
Split Flow Ratio= 0.02
Log Output Level= 0
Friction Slope Method= 1
Unsteady Friction Slope Method= 2
Unsteady Bridges Friction Slope Method= 1
Parabolic Critical Depth
Global Vel Dist=  1 , 1 , 1
Global Log Level= 0
CheckData=True
Encroach Param= -1, 0, 0, 0
BEGIN DESCRIPTION:
Multiple Run
END DESCRIPTION:

--- Berry Creek Trib 11.f01 (steady flow) ---

Flow Title=Multiple
Number of Profiles=7
Profile Names=10-year,25-year,50-year,1pct_min,100-year,1pct_plu,500-year
River Rch & RM= Berry Creek Trib,Reach-1,2371
     181     224     257     147     293     584     380
Boundary for River Rch & Prof#=Berry Creek Trib,Reach-1,1
Up Type=0
Dn Type=3
Dn Slope=0.005
Boundary for River Rch & Prof#=Berry Creek Trib,Reach-1,2
Up Type=0
Dn Type=3
Dn Slope=0.005
Boundary for River Rch & Prof#=Berry Creek Trib,Reach-1,3
Up Type=0
Dn Type=3
Dn Slope=0.005
Boundary for River Rch & Prof#=Berry Creek Trib,Reach-1,4
Up Type=0
Dn Type=3
Dn Slope=0.005
Boundary for River Rch & Prof#=Berry Creek Trib,Reach-1,5
Up Type=0
Dn Type=3
Dn Slope=0.005
Boundary for River Rch & Prof#=Berry Creek Trib,Reach-1,6
Up Type=0
Dn Type=3
Dn Slope=0.005
Boundary for River Rch & Prof#=Berry Creek Trib,Reach-1,7
Up Type=0
Dn Type=3
Dn Slope=0.005

--- Berry Creek Trib 11.g01 (geometry) ---

Geom Title=Existing Conditions

River Reach=Berry Creek Trib,Reach-1
Reach XY= 30
      2627417.41      6994495.58      2627220.69      6994560.24
      2627173.50      6994566.35      2627024.50      6994707.39
      2626927.59      6994714.83      2626878.17      6994754.91
      2626827.63      6994765.41      2626779.23      6994802.76
      2626726.08      6994768.76      2626674.35      6994806.56
      2626623.71      6994816.81      2626485.68      6994950.24
      2626423.83      6994967.14      2626374.44      6995007.24
      2626219.54      6995018.74      2626181.87      6995058.76
      2626170.36      6995105.35      2626116.58      6995121.89
      2625999.01      6995237.53      2625979.98      6995262.65
      2625962.37      6995324.21      2625746.09      6995541.22
      2625724.36      6995557.05      2625673.78      6995567.09
      2625623.90      6995606.66      2625584.48      6995614.51
      2625567.73      6995666.76      2625492.74      6995744.44
      2625469.87      6995759.33      2625426.00      6995761.00

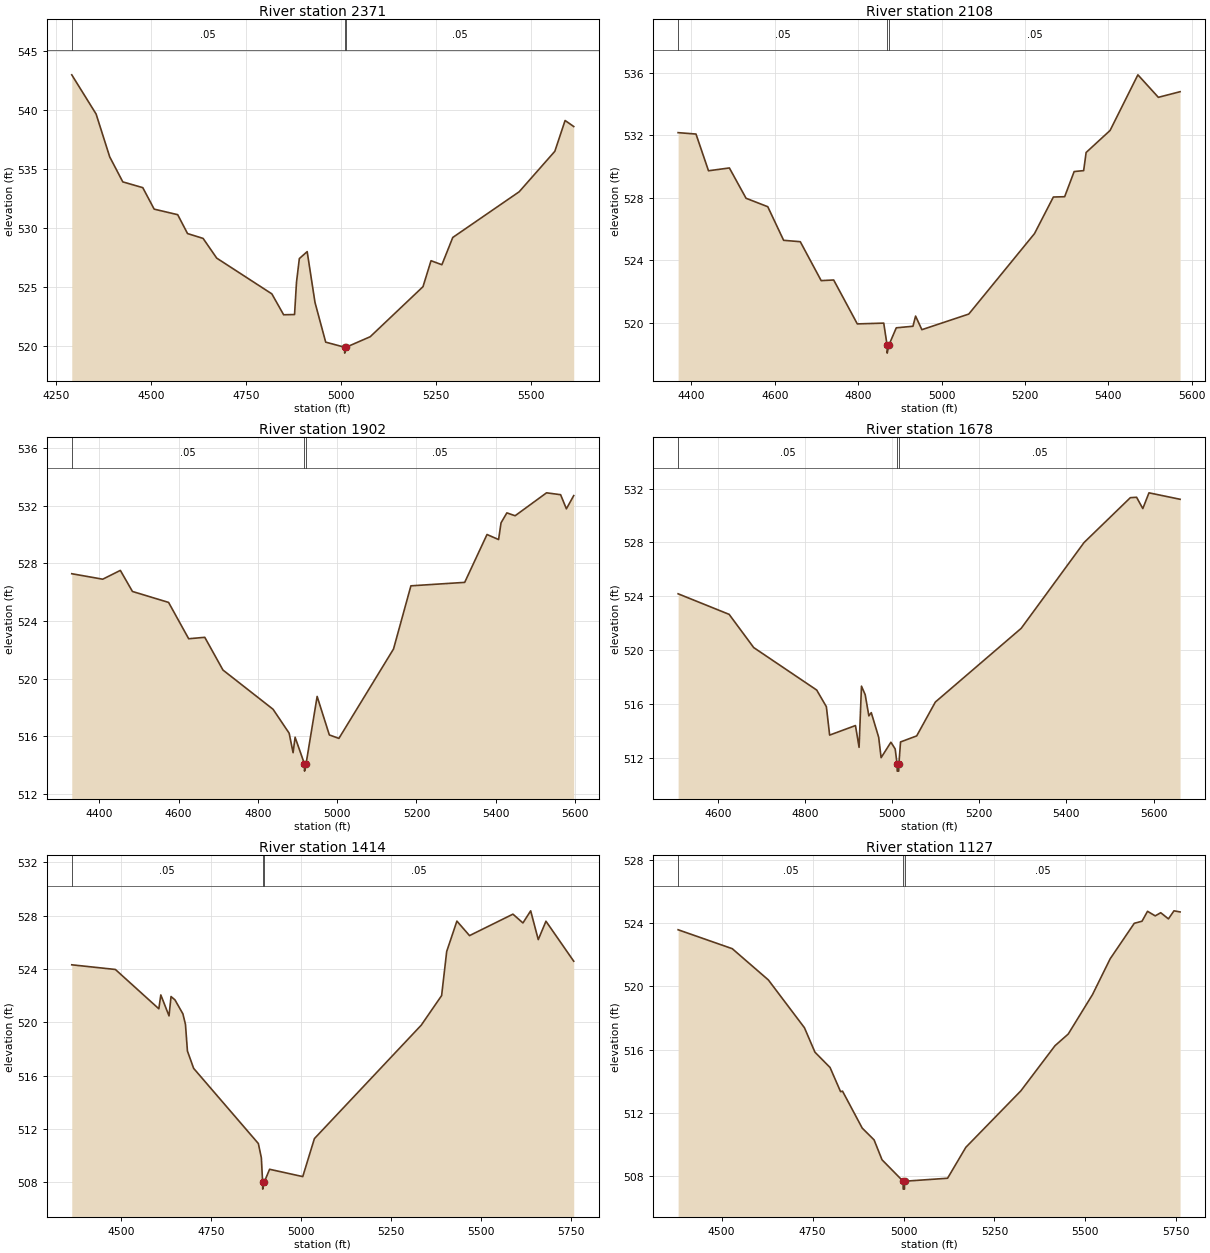
Type RM Length L Ch R = 1,2371,263,263,263
BEGIN DESCRIPTION:
Berry Creek Trib 11 4.0
END DESCRIPTION:
XS GIS Cut Line= 3
      2627426.01      6993860.96      2627248.21      6994560.66
      2627576.01      6995061.01
#Sta/Elev= 30
  4291.6  542.96  4355.6  539.64  4391.4  536.01  4425.8  533.89  4478.4  533.40
  4508.3  531.58  4570.2  531.11  4596.1  529.51  4637.0  529.10  4672.8  527.43
  4817.8  524.40  4848.8  522.63  4877.5  522.65  4882.6  525.38  4890.1  527.39
  4910.7  527.98  4931.3  523.67  4959.4  520.31  5009.1  519.88  5009.4  519.38
  5013.1  519.88  5076.5  520.77  5215.3  525.01  5236.4  527.21  5265.0  526.87
  5293.6  529.18  5468.2  533.05  5562.0  536.48  5589.0  539.09  5611.7  538.58
#Mann=3,-1,0
  4291.6    0.05       0  5009.1    0.04       0  5013.1    0.05       0
Bank Sta=5009.1,5013.1
Exp/Cntr=0.3,0.1

Type RM Length L Ch R = 1,2108,206,206,206
BEGIN DESCRIPTION:
Mapping XS d8829b82
END DESCRIPTION:
XS GIS Cut Line= 4
      2626991.32      6994068.16      2627017.36      6994638.45
      2627040.80      6994687.93      2627353.27      6995174.86
#Sta/Elev= 30
  4368.1  532.17  4411.0  532.08  4441.0  529.73  4491.1  529.91  4531.1  527.97
  4583.2  527.43  4621.2  525.28  4661.2  525.19  4711.3  522.70  4741.3  522.74
  4798.0  519.93  4861.4  519.98  4869.5  518.56  4869.7  518.06  4873.5  518.56
  4891.5  519.68  4931.5  519.78  4937.8  520.43  4952.9  519.56  5065.4  520.56
  5223.1  525.71  5268.3  528.05  5295.4  528.07  5318.2  529.68  5341.0  529.74
  5346.9  530.90  5404.4  532.31  5471.1  535.87  5520.2  534.43  5572.3  534.79
#Mann=3,-1,0
  4368.1    0.05       0  4869.5    0.04       0  4873.5    0.05       0
Bank Sta=4869.5,4873.5
Exp/Cntr=0.3,0.1

Type RM Length L Ch R = 1,1902,224,224,224
BEGIN DESCRIPTION:
Mapping XS 7916fd91
END DESCRIPTION:
XS GIS Cut Line= 3
      2626747.92      6994100.04      2626859.31      6994764.81
      2627211.95      6995240.89
#Sta/Elev= 30
  4330.5  527.27  4408.6  526.89  4453.1  527.50  4483.6  526.04  4574.8  525.28
  4625.5  522.76  4666.1  522.86  4712.0  520.59  4838.4  517.87  4879.0  516.21
  4888.9  514.86  4894.0  515.93  4917.6  514.08  4917.8  513.58  4921.6  514.08
  4949.6  518.76  4980.4  516.09  5004.5  515.85  5142.3  522.05  5186.2  526.43
  5321.9  526.67  5378.2  529.99  5407.4  529.64  5413.6  530.80  5428.3  531.49
  5449.1  531.29  5528.4  532.88  5563.9  532.75  5578.5  531.77  5597.0  532.69
#Mann=3,-1,0
  4330.5    0.05       0  4917.6    0.04       0  4921.6    0.05       0
Bank Sta=4917.6,4921.6
Exp/Cntr=0.3,0.1

Type RM Length L Ch R = 1,1678,264,264,264
BEGIN DESCRIPTION:
Mapping XS 14065835
END DESCRIPTION:
XS GIS Cut Line= 4
      2626457.46      6994365.01      2626676.21      6994812.93
      2626848.09      6995104.59      2627087.66      6995310.31
#Sta/Elev= 30
  4508.2  524.18  4625.4  522.65  4681.8  520.18  4826.5  517.02  4848.7  515.78
  4856.2  513.67  4915.5  514.38  4923.8  512.76  4929.3  517.31  4937.8  516.68
  4946.3  515.10  4951.8  515.34  4968.8  513.51  4974.4  511.99  4996.9  513.14
  5006.7  512.64  5011.2  511.49  5011.4  510.99  5014.9  510.99  5015.2  511.49
  5019.0  513.16  5056.1  513.61  5099.0  516.13  5296.1  521.61  5440.4  527.99
  5546.8  531.33  5561.1  531.36  5575.4  530.52  5589.6  531.69  5661.0  531.21
#Mann=3,-1,0
  4508.2    0.05       0  5011.2    0.03       0  5015.2    0.05       0
Bank Sta=5011.2,5015.2
Exp/Cntr=0.3,0.1

Type RM Length L Ch R = 1,1414,287,287,287
BEGIN DESCRIPTION:
Mapping XS 02946073
END DESCRIPTION:
XS GIS Cut Line= 3
      2626196.30      6994381.17      2626468.57      6994962.83
      2627019.50      6995476.68
#Sta/Elev= 30
  4361.8  524.32  4483.1  523.97  4603.9  521.02  4609.4  522.06  4632.2  520.49
  4637.8  521.94  4648.7  521.69  4670.8  520.64  4677.9  519.85  4683.4  517.85
  4700.7  516.55  4880.6  510.91  4888.9  509.84  4892.5  507.99  4892.7  507.49
  4896.5  507.99  4911.8  508.98  5004.0  508.43  5036.4  511.28  5333.4  519.79
  5390.1  522.01  5404.2  525.32  5432.6  527.60  5467.7  526.51  5588.4  528.12
  5616.2  527.46  5637.7  528.37  5658.8  526.21  5680.2  527.59  5757.4  524.59
#Mann=3,-1,0
  4361.8    0.05       0  4892.5    0.03       0  4896.5    0.05       0
Bank Sta=4892.5,4896.5
Exp/Cntr=0.3,0.1

Type RM Length L Ch R = 1,1127,290,290,290
BEGIN DESCRIPTION:
Mapping XS 847af75a
END DESCRIPTION:
XS GIS Cut Line= 4
      2625952.77      6994466.89      2626195.83      6995025.95
      2626313.89      6995133.59      2626827.76      6995463.44
#Sta/Elev= 30
  4380.3  523.59  4529.2  522.39  4628.4  520.41  4727.6  517.38  4756.5  515.83
  4798.0  514.86  4826.9  513.33  4832.3  513.36  4886.4  511.02  4919.1  510.27
  4940.9  509.01  4998.9  507.65  4999.1  507.15  5002.6  507.15  5002.9  507.65
  5121.1  507.84  5171.3  509.80  5322.6  513.38  5416.4  516.24  5452.8  516.98
  5519.5  519.48  5568.1  521.75  5634.4  524.00  5655.6  524.13  5670.8  524.76
  5691.9  524.47  5707.1  524.67  5728.3  524.28  5743.5  524.79  5760.3  524.72
#Mann=3,-1,0
  4380.3    0.05       0  4998.9    0.03       0  5002.9    0.05       0
Bank Sta=4998.9,5002.9
Exp/Cntr=0.3,0.1

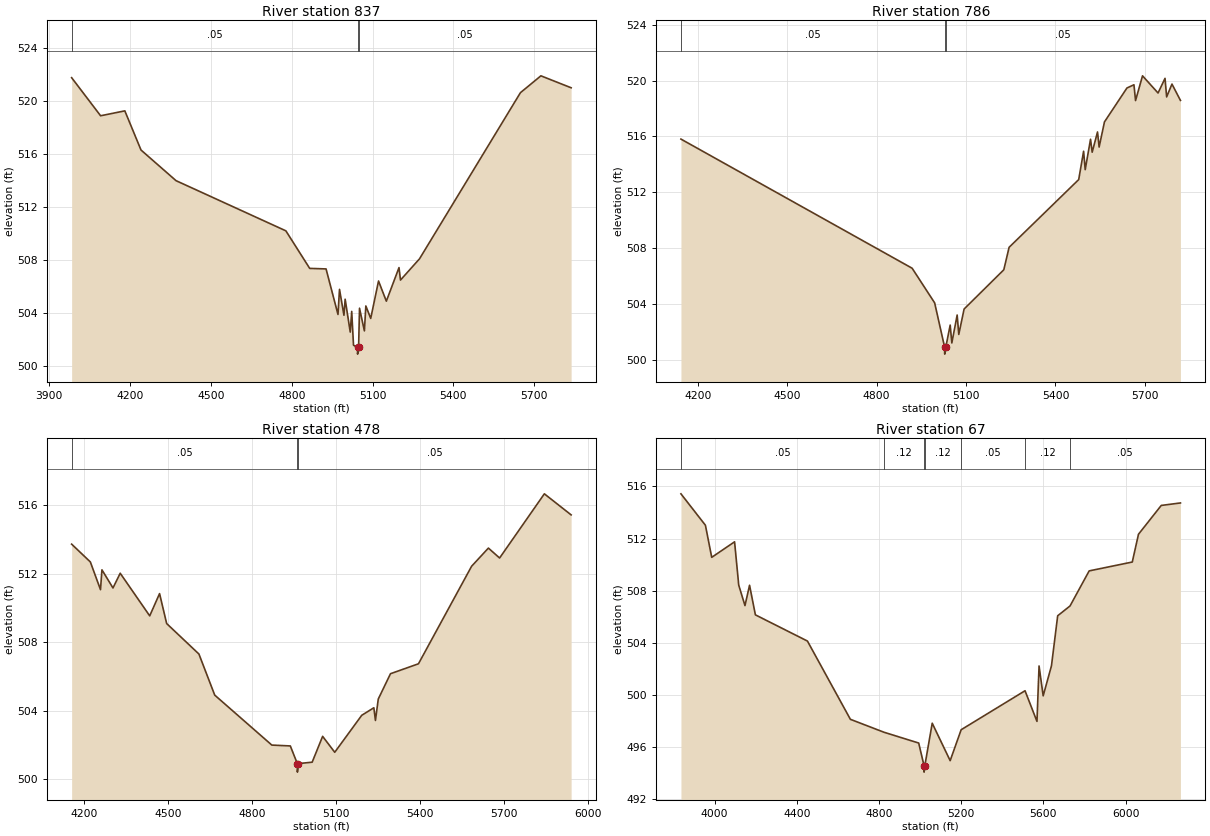
Type RM Length L Ch R = 1,837,51,51,51
BEGIN DESCRIPTION:
Berry Creek Trib 11 3.0
END DESCRIPTION:
XS GIS Cut Line= 4
      2625674.73      6994423.56      2625658.82      6995045.93
      2626008.96      6995227.51      2626777.99      6995558.66
#Sta/Elev= 30
  3983.0  521.73  4090.5  518.86  4180.5  519.23  4240.5  516.28  4370.6  513.97
  4778.3  510.19  4866.8  507.36  4927.5  507.32  4971.8  503.89  4977.4  505.78
  4993.9  503.83  4998.4  505.04  5017.3  502.56  5022.7  504.12  5029.4  501.57
  5044.3  501.40  5044.5  500.90  5048.3  501.40  5051.7  504.36  5069.8  502.65
  5075.2  504.53  5093.3  503.59  5122.3  506.41  5151.3  504.89  5198.3  507.42
  5203.8  506.48  5274.4  508.08  5649.1  520.60  5725.1  521.87  5837.3  520.97
#Mann=3,-1,0
  3983.0    0.05       0  5044.3    0.03       0  5048.3    0.05       0
Bank Sta=5044.3,5048.3
Exp/Cntr=0.3,0.1

Type RM Length L Ch R = 1,786,308,308,308
BEGIN DESCRIPTION:
Berry Creek Trib 11 2.0
END DESCRIPTION:
XS GIS Cut Line= 4
      2625549.19      6994639.25      2625641.14      6995118.42
      2625978.53      6995267.05      2626728.45      6995596.77
#Sta/Elev= 30
  4143.4  515.81  4919.1  506.56  4994.6  504.08  5028.0  500.91  5028.3  500.41
  5032.0  500.91  5046.7  502.49  5052.2  501.21  5070.1  503.21  5075.5  501.82
  5093.4  503.64  5226.6  506.45  5244.4  508.06  5477.9  512.91  5494.3  514.94
  5499.7  513.62  5517.6  515.80  5523.1  514.87  5541.0  516.32  5546.4  515.24
  5564.3  517.04  5639.8  519.47  5663.2  519.70  5668.6  518.57  5692.0  520.34
  5744.1  519.11  5767.5  520.16  5772.9  518.83  5790.8  519.75  5819.2  518.58
#Mann=3,-1,0
  4143.4    0.05       0  5028.0    0.03       0  5032.0    0.05       0
Bank Sta=5028,5032
Exp/Cntr=0.3,0.1

Type RM Length L Ch R = 1,478,411,411,411
BEGIN DESCRIPTION:
Mapping XS e7300730
END DESCRIPTION:
XS GIS Cut Line= 5
      2625536.12      6994744.75      2625629.86      6995394.00
      2625796.53      6995505.11      2626022.22      6995633.59
      2626691.69      6995640.52
#Sta/Elev= 30
  4154.1  513.73  4221.0  512.69  4257.3  511.07  4262.4  512.23  4301.9  511.17
  4327.7  512.03  4433.2  509.54  4468.4  510.84  4493.8  509.09  4609.1  507.31
  4665.6  504.91  4869.7  501.99  4935.8  501.94  4960.8  500.91  4961.1  500.41
  4964.8  500.91  5013.9  500.99  5051.3  502.50  5094.6  501.57  5191.1  503.73
  5234.4  504.17  5240.1  503.43  5250.2  504.68  5293.9  506.16  5393.9  506.74
  5583.9  512.44  5643.9  513.50  5683.9  512.92  5843.9  516.67  5939.6  515.44
#Mann=3,-1,0
  4154.1    0.05       0  4960.8    0.04       0  4964.8    0.05       0
Bank Sta=4960.8,4964.8
Exp/Cntr=0.3,0.1

Type RM Length L Ch R = 1,67,0,0,0
BEGIN DESCRIPTION:
Berry Creek Trib 11 1.0
END DESCRIPTION:
XS GIS Cut Line= 5
      2625524.44      6994653.45      2625363.54      6995636.19
      2625489.31      6995747.54      2625623.96      6995821.09
      2626728.51      6995678.88
#Sta/Elev= 30
  3836.2  515.43  3955.3  513.02  3986.0  510.56  4097.2  511.75  4117.4  508.43
  4147.8  506.86  4170.1  508.42  4198.5  506.15  4451.8  504.14  4660.8  498.14
  4824.0  497.15  4993.3  496.32  5019.2  494.59  5019.4  494.09  5023.2  494.59
  5059.1  497.84  5146.4  494.97  5199.9  497.34  5510.8  500.33  5568.9  497.98
  5579.0  502.23  5599.1  499.94  5639.4  502.24  5669.7  506.08  5729.7  506.83
  5822.9  509.52  6032.7  510.20  6062.9  512.33  6173.8  514.54  6267.1  514.73
#Mann=7,-1,0
  3836.2    0.05       0  4824.0    0.12       0  5019.2    0.07       0
  5023.2    0.12       0  5199.9    0.05       0  5510.8    0.12       0
  5729.7    0.05       0
Bank Sta=5019.2,5023.2
Exp/Cntr=0.3,0.1

Chan Stop Cuts=-1