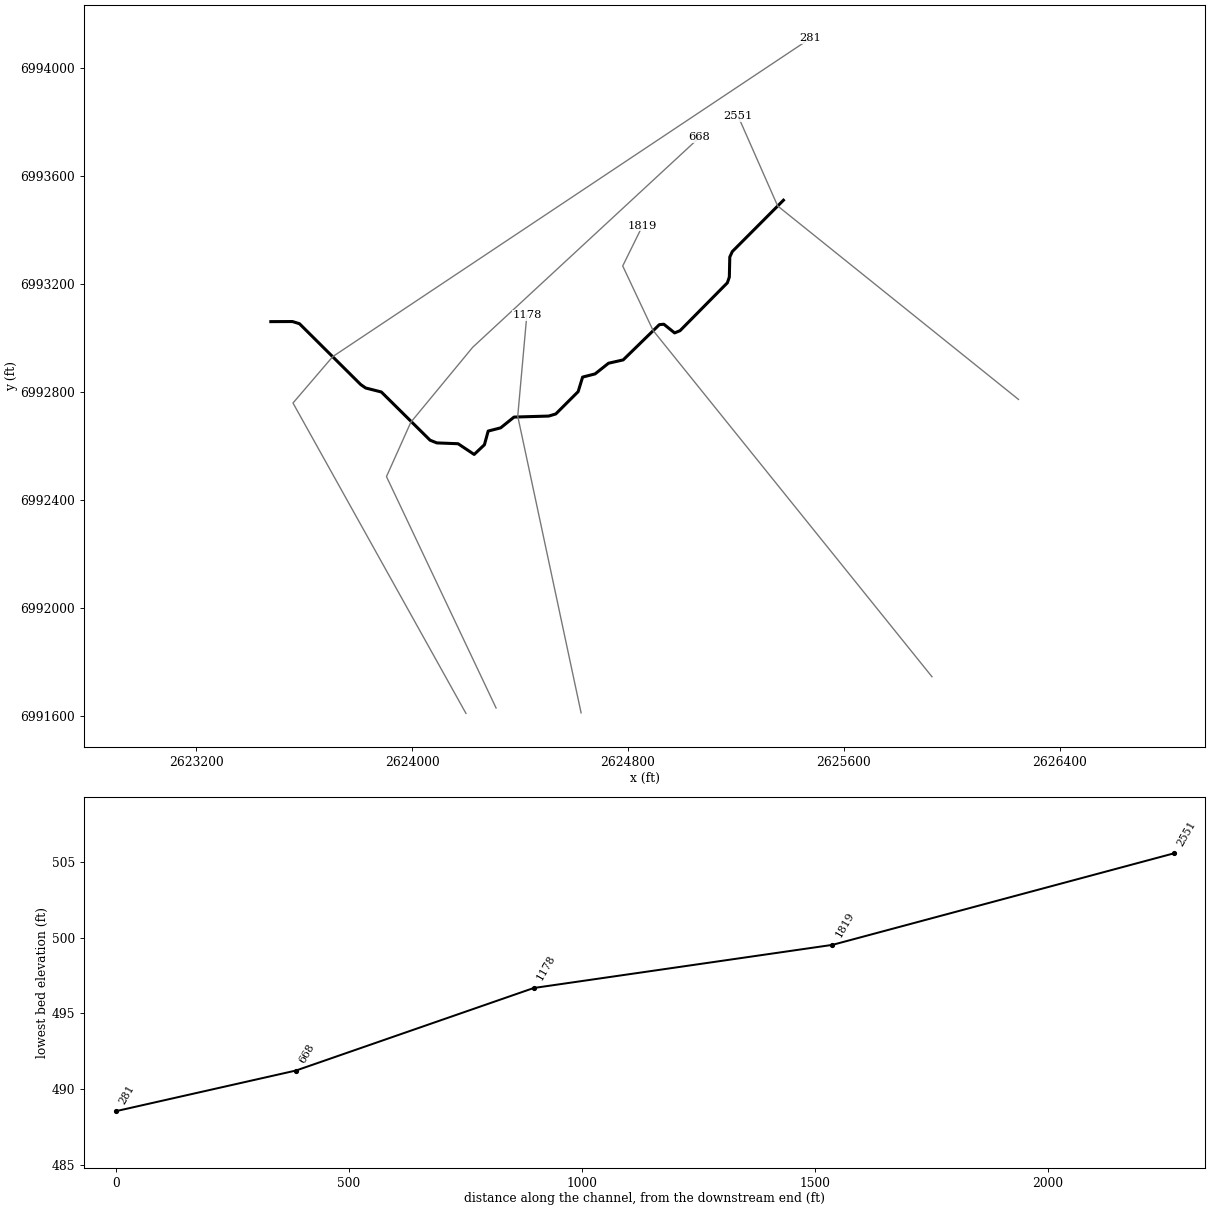
--- Berry Creek Trib 12.prj (project) ---

Proj Title=Berry Creek Trib 12 Base Level Engineering
Current Plan=p01
Default Exp/Contr=0.3,0.1
English Units
Geom File=g01
Flow File=f01
Plan File=p01
BEGIN DESCRIPTION:
Berry Creek Trib 12
END DESCRIPTION:

--- Berry Creek Trib 12.p01 (plan) ---

Plan Title=Multiple Run
Short Identifier=Multiple
Geom File=g01
Flow File=f01
Subcritical Flow
K Sum by GR= 0
Std Step Tol= 0.01
Critical Tol= 0.01
Num of Std Step Trials= 20
Max Error Tol= 0.3
Flow Tol Ratio= 0.001
Split Flow NTrial= 30
Split Flow Tol= 0.02
Split Flow Ratio= 0.02
Log Output Level= 0
Friction Slope Method= 1
Unsteady Friction Slope Method= 2
Unsteady Bridges Friction Slope Method= 1
Parabolic Critical Depth
Global Vel Dist=  1 , 1 , 1
Global Log Level= 0
CheckData=True
Encroach Param= -1, 0, 0, 0
BEGIN DESCRIPTION:
Multiple Run
END DESCRIPTION:

--- Berry Creek Trib 12.f01 (steady flow) ---

Flow Title=Multiple
Number of Profiles=7
Profile Names=10-year,25-year,50-year,1pct_min,100-year,1pct_plu,500-year
River Rch & RM= Berry Creek Trib,Reach-1,2551
     316     407     478     280     558    1114     759
Boundary for River Rch & Prof#=Berry Creek Trib,Reach-1,1
Up Type=0
Dn Type=3
Dn Slope=0.005
Boundary for River Rch & Prof#=Berry Creek Trib,Reach-1,2
Up Type=0
Dn Type=3
Dn Slope=0.005
Boundary for River Rch & Prof#=Berry Creek Trib,Reach-1,3
Up Type=0
Dn Type=3
Dn Slope=0.005
Boundary for River Rch & Prof#=Berry Creek Trib,Reach-1,4
Up Type=0
Dn Type=3
Dn Slope=0.005
Boundary for River Rch & Prof#=Berry Creek Trib,Reach-1,5
Up Type=0
Dn Type=3
Dn Slope=0.005
Boundary for River Rch & Prof#=Berry Creek Trib,Reach-1,6
Up Type=0
Dn Type=3
Dn Slope=0.005
Boundary for River Rch & Prof#=Berry Creek Trib,Reach-1,7
Up Type=0
Dn Type=3
Dn Slope=0.005

--- Berry Creek Trib 12.g01 (geometry) ---

Geom Title=Existing Conditions

River Reach=Berry Creek Trib,Reach-1
Reach XY= 30
      2625376.00      6993511.00      2625186.52      6993320.79
      2625177.17      6993300.52      2625175.47      6993226.22
      2625168.14      6993204.83      2624992.67      6993027.39
      2624972.67      6993019.16      2624932.67      6993051.38
      2624916.00      6993049.76      2624782.05      6992919.14
      2624727.71      6992906.82      2624677.85      6992867.24
      2624631.61      6992855.41      2624615.12      6992801.56
      2624532.21      6992718.81      2624506.01      6992710.98
      2624377.53      6992707.25      2624327.84      6992667.27
      2624281.61      6992655.35      2624267.72      6992604.61
      2624229.65      6992568.73      2624170.12      6992608.43
      2624091.22      6992611.51      2624066.21      6992621.52
      2623885.68      6992800.22      2623827.65      6992814.98
      2623809.33      6992827.65      2623582.22      6993053.26
      2623556.14      6993061.33      2623476.00      6993061.00

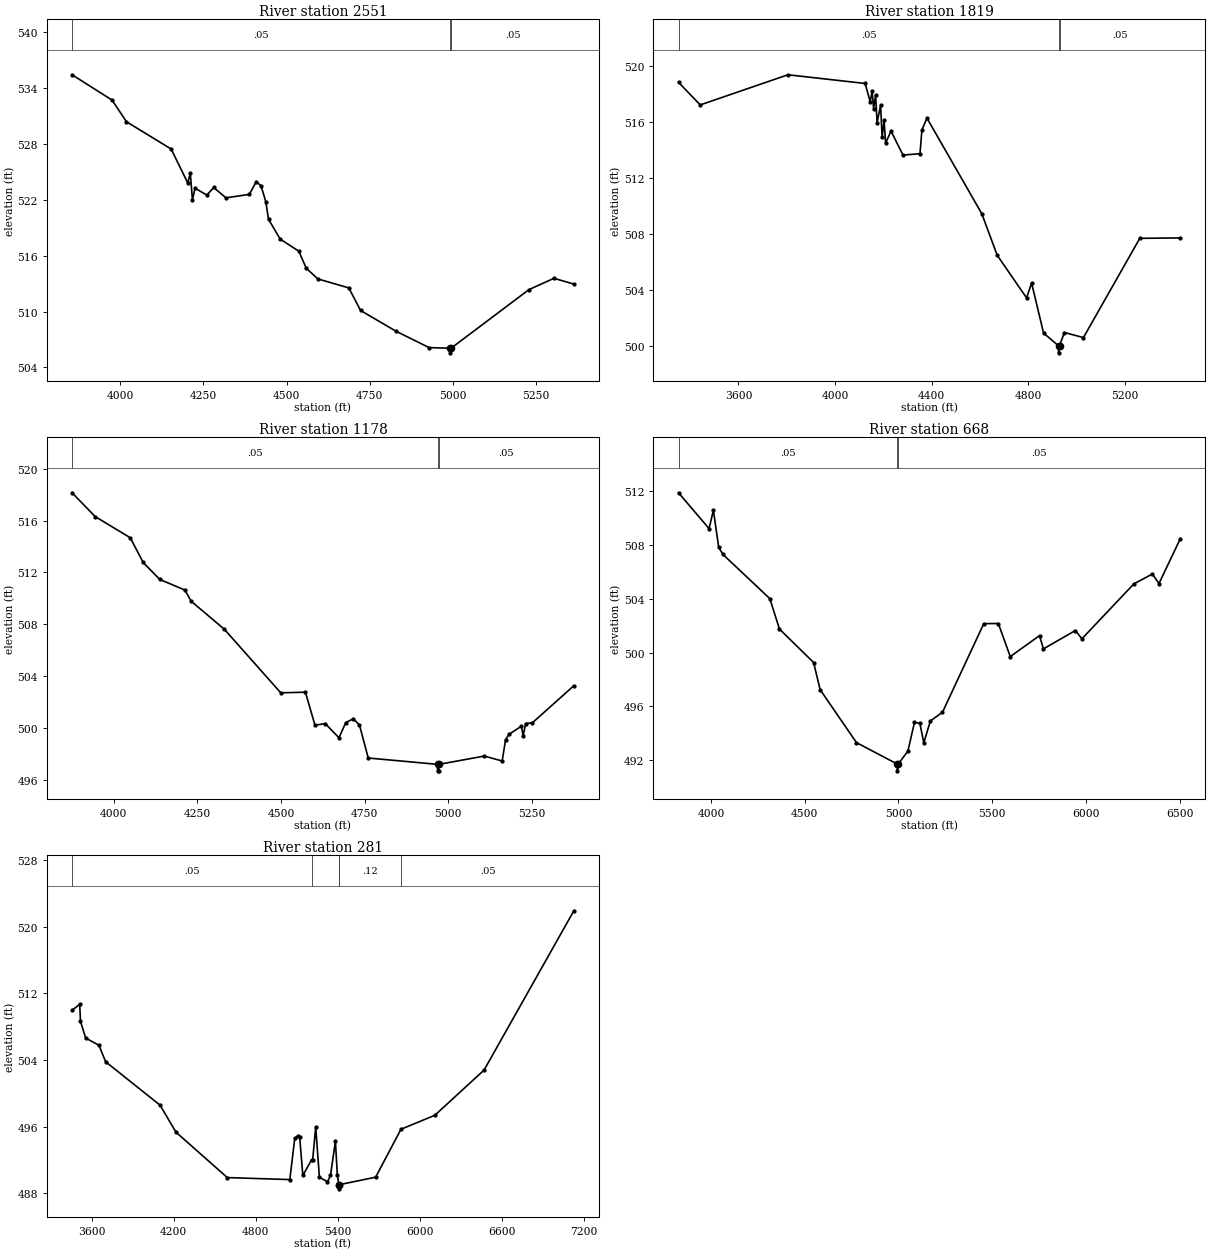
Type RM Length L Ch R = 1,2551,732,732,732
BEGIN DESCRIPTION:
Berry Creek Trib 12 4.0
END DESCRIPTION:
XS GIS Cut Line= 3
      2626247.28      6992772.55      2625354.54      6993489.78
      2625207.78      6993822.92
#Sta/Elev= 30
  3855.0  535.42  3975.4  532.70  4018.6  530.38  4153.0  527.45  4203.0  523.80
  4210.6  524.85  4217.0  522.01  4225.0  523.25  4260.2  522.50  4281.0  523.32
  4317.8  522.21  4388.2  522.58  4409.0  523.95  4423.4  523.50  4437.8  521.78
  4445.8  519.91  4481.0  517.78  4537.0  516.48  4559.4  514.65  4594.6  513.50
  4687.4  512.54  4722.6  510.12  4829.8  507.88  4929.0  506.13  4991.0  506.07
  4991.3  505.57  4995.0  506.07  5228.8  512.35  5304.3  513.57  5364.2  512.95
#Mann=3,-1,0
  3855.0    0.05       0  4991.0    0.03       0  4995.0    0.05       0
Bank Sta=4991,4995
Exp/Cntr=0.3,0.1

Type RM Length L Ch R = 1,1819,641,641,641
BEGIN DESCRIPTION:
Berry Creek Trib 12 3.0
END DESCRIPTION:
XS GIS Cut Line= 4
      2625926.54      6991744.77      2624892.67      6993028.52
      2624780.28      6993267.33      2624853.81      6993416.56
#Sta/Elev= 30
  3351.7  518.83  3441.7  517.22  3804.8  519.37  4124.7  518.75  4145.5  517.45
  4153.5  518.20  4159.9  516.96  4167.9  517.93  4174.3  515.96  4188.7  517.18
  4195.1  514.91  4203.1  516.13  4209.5  514.50  4231.9  515.35  4281.5  513.64
  4351.9  513.74  4359.9  515.43  4380.7  516.28  4607.8  509.46  4671.8  506.49
  4793.4  503.45  4814.2  504.51  4863.8  500.94  4925.8  500.03  4926.0  499.53
  4929.8  500.03  4950.1  500.98  5028.9  500.62  5262.4  507.70  5430.3  507.73
#Mann=3,-1,0
  3351.7    0.05       0  4925.8    0.03       0  4929.8    0.05       0
Bank Sta=4925.8,4929.8
Exp/Cntr=0.3,0.1

Type RM Length L Ch R = 1,1178,510,510,510
BEGIN DESCRIPTION:
Berry Creek Trib 12 2.0
END DESCRIPTION:
XS GIS Cut Line= 3
      2624626.01      6991610.98      2624391.20      6992710.48
      2624424.81      6993084.38
#Sta/Elev= 30
  3875.7  518.14  3944.9  516.30  4049.6  514.67  4088.3  512.76  4137.8  511.45
  4213.2  510.63  4231.7  509.77  4330.7  507.61  4499.5  502.70  4573.1  502.75
  4601.7  500.20  4632.4  500.33  4673.3  499.23  4693.8  500.41  4716.5  500.70
  4734.7  500.21  4760.9  497.67  4967.9  497.18  4968.1  496.68  4971.6  496.68
  4971.9  497.18  5107.7  497.82  5161.2  497.44  5171.2  499.08  5181.2  499.49
  5218.8  500.13  5223.8  499.37  5231.4  500.33  5251.5  500.39  5375.4  503.25
#Mann=3,-1,0
  3875.7    0.05       0  4967.9    0.03       0  4971.9    0.05       0
Bank Sta=4967.9,4971.9
Exp/Cntr=0.3,0.1

Type RM Length L Ch R = 1,668,387,387,387
BEGIN DESCRIPTION:
Mapping XS 3b0ab263
END DESCRIPTION:
XS GIS Cut Line= 5
      2624310.87      6991628.99      2623904.64      6992486.60
      2623994.91      6992687.99      2624224.08      6992965.77
      2625064.39      6993743.58
#Sta/Elev= 30
  3827.5  511.84  3990.4  509.18  4013.2  510.55  4041.5  507.80  4064.2  507.27
  4314.4  503.99  4365.4  501.74  4547.4  499.26  4582.2  497.25  4776.1  493.32
  4994.1  491.73  4994.3  491.23  4998.1  491.73  5050.1  492.69  5085.3  494.83
  5114.0  494.75  5134.8  493.31  5170.0  494.93  5234.4  495.57  5454.6  502.14
  5532.2  502.15  5595.7  499.70  5751.7  501.25  5772.6  500.27  5942.7  501.63
  5977.9  501.02  6254.0  505.08  6353.2  505.82  6388.4  505.11  6502.3  508.44
#Mann=3,-1,0
  3827.5    0.05       0  4994.1    0.03       0  4998.1    0.05       0
Bank Sta=4994.1,4998.1
Exp/Cntr=0.3,0.1

Type RM Length L Ch R = 1,281,0,0,0
BEGIN DESCRIPTION:
Berry Creek Trib 12 1.0
END DESCRIPTION:
XS GIS Cut Line= 4
      2624199.21      6991609.00      2623558.16      6992759.32
      2623705.60      6992931.41      2625476.01      6994111.01
#Sta/Elev= 30
  3456.5  509.95  3512.4  510.68  3518.1  508.63  3555.8  506.63  3653.0  505.76
  3702.1  503.78  4099.9  498.58  4216.5  495.34  4592.1  489.89  5049.5  489.65
  5085.5  494.58  5108.6  494.92  5121.6  494.75  5144.7  490.14  5208.9  492.02
  5216.8  492.02  5238.8  495.97  5265.8  489.95  5324.9  489.38  5346.9  490.14
  5383.0  494.24  5397.0  490.21  5408.0  489.04  5408.3  488.54  5412.0  489.04
  5677.5  489.94  5862.7  495.69  6110.2  497.36  6470.8  502.79  7127.4  521.89
#Mann=5,-1,0
  3456.5    0.05       0  5208.9    0.12       0  5408.0    0.03       0
  5412.0    0.12       0  5862.7    0.05       0
Bank Sta=5408,5412
Exp/Cntr=0.3,0.1

Chan Stop Cuts=-1