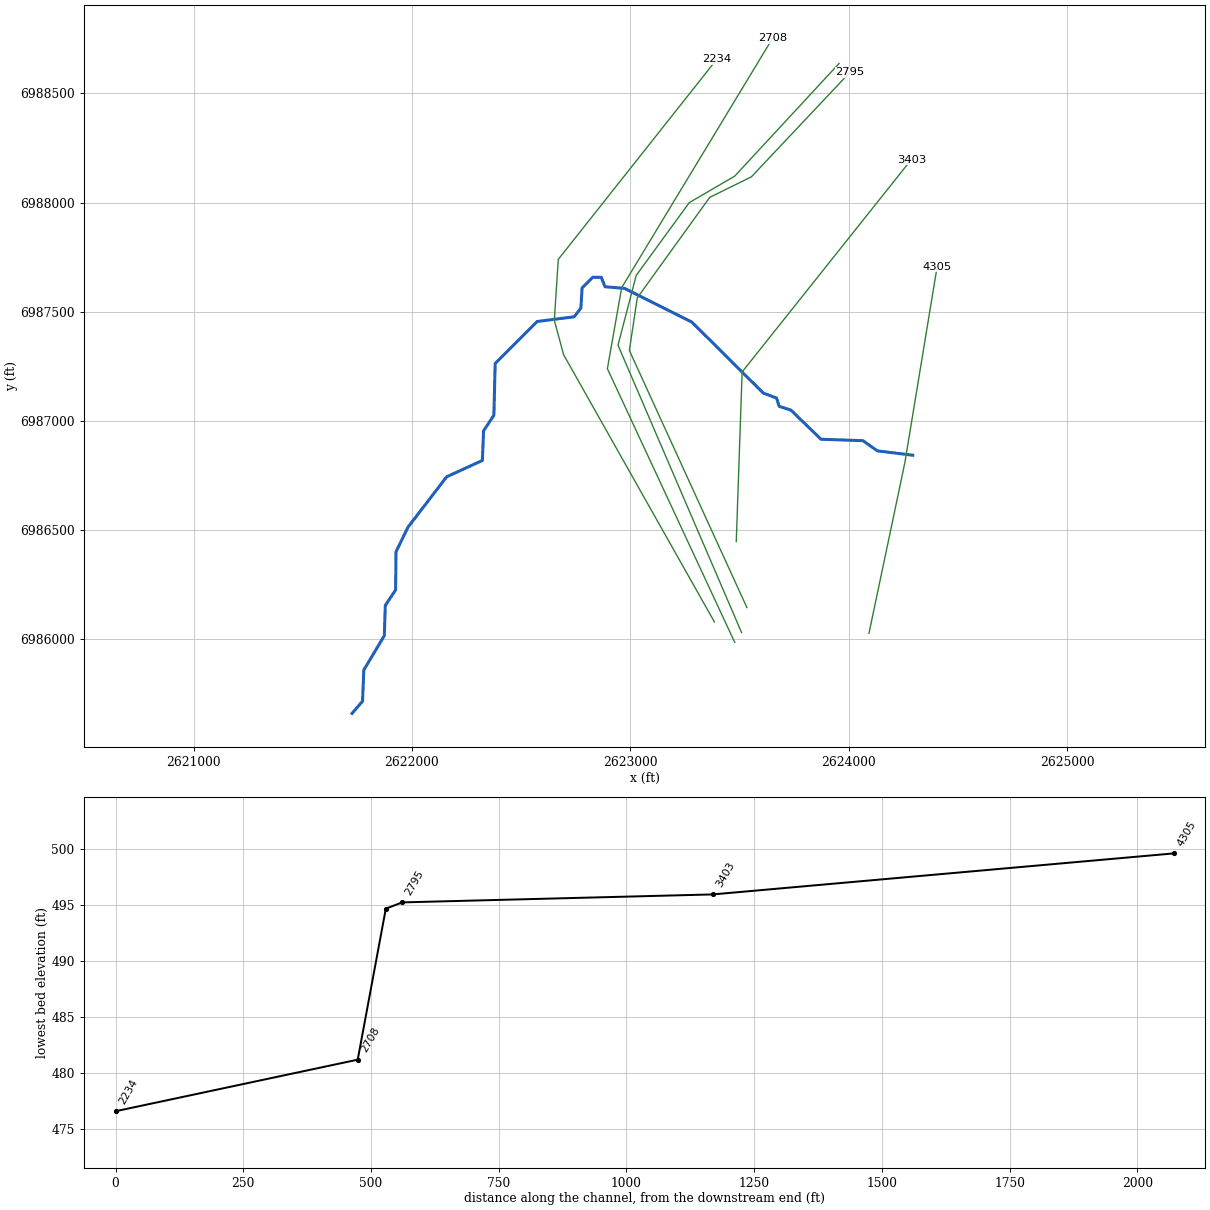
--- Berry Creek Trib 13.prj (project) ---

Proj Title=Berry Creek Trib 13 Base Level Engineering
Current Plan=p01
Default Exp/Contr=0.3,0.1
English Units
Geom File=g01
Flow File=f01
Plan File=p01
BEGIN DESCRIPTION:
Berry Creek Trib 13
END DESCRIPTION:

--- Berry Creek Trib 13.p01 (plan) ---

Plan Title=Multiple Run
Short Identifier=Multiple
Geom File=g01
Flow File=f01
Subcritical Flow
K Sum by GR= 0
Std Step Tol= 0.01
Critical Tol= 0.01
Num of Std Step Trials= 20
Max Error Tol= 0.3
Flow Tol Ratio= 0.001
Split Flow NTrial= 30
Split Flow Tol= 0.02
Split Flow Ratio= 0.02
Log Output Level= 0
Friction Slope Method= 1
Unsteady Friction Slope Method= 2
Unsteady Bridges Friction Slope Method= 1
Parabolic Critical Depth
Global Vel Dist=  1 , 1 , 1
Global Log Level= 0
CheckData=True
Encroach Param= -1, 0, 0, 0
BEGIN DESCRIPTION:
Multiple Run
END DESCRIPTION:

--- Berry Creek Trib 13.f01 (steady flow) ---

Flow Title=Multiple
Number of Profiles=7
Profile Names=10-year,25-year,50-year,1pct_min,100-year,1pct_plu,500-year
River Rch & RM= Berry Creek Trib,Reach-1,4305
     345     449     531     312     623    1243     857
Boundary for River Rch & Prof#=Berry Creek Trib,Reach-1,1
Up Type=0
Dn Type=3
Dn Slope=0.005
Boundary for River Rch & Prof#=Berry Creek Trib,Reach-1,2
Up Type=0
Dn Type=3
Dn Slope=0.005
Boundary for River Rch & Prof#=Berry Creek Trib,Reach-1,3
Up Type=0
Dn Type=3
Dn Slope=0.005
Boundary for River Rch & Prof#=Berry Creek Trib,Reach-1,4
Up Type=0
Dn Type=3
Dn Slope=0.005
Boundary for River Rch & Prof#=Berry Creek Trib,Reach-1,5
Up Type=0
Dn Type=3
Dn Slope=0.005
Boundary for River Rch & Prof#=Berry Creek Trib,Reach-1,6
Up Type=0
Dn Type=3
Dn Slope=0.005
Boundary for River Rch & Prof#=Berry Creek Trib,Reach-1,7
Up Type=0
Dn Type=3
Dn Slope=0.005

--- Berry Creek Trib 13.g01 (geometry) ---

Geom Title=Existing Conditions

River Reach=Berry Creek Trib,Reach-1
Reach XY= 30
      2624293.79      6986843.23      2624131.87      6986863.10
      2624065.50      6986909.80      2623873.55      6986916.46
      2623735.43      6987050.15      2623681.77      6987066.98
      2623670.23      6987105.02      2623609.51      6987127.71
      2623282.06      6987452.86      2622974.35      6987607.15
      2622884.47      6987614.62      2622867.30      6987658.04
      2622827.73      6987658.08      2622779.55      6987609.79
      2622773.93      6987516.69      2622743.22      6987477.24
      2622573.55      6987455.53      2622381.46      6987263.45
      2622375.48      6987026.22      2622328.28      6986955.05
      2622322.93      6986819.28      2622159.29      6986744.37
      2621981.84      6986513.29      2621927.20      6986400.50
      2621925.48      6986226.22      2621878.27      6986155.06
      2621873.75      6986016.93      2621779.75      6985859.44
      2621774.09      6985716.79      2621726.00      6985661.00

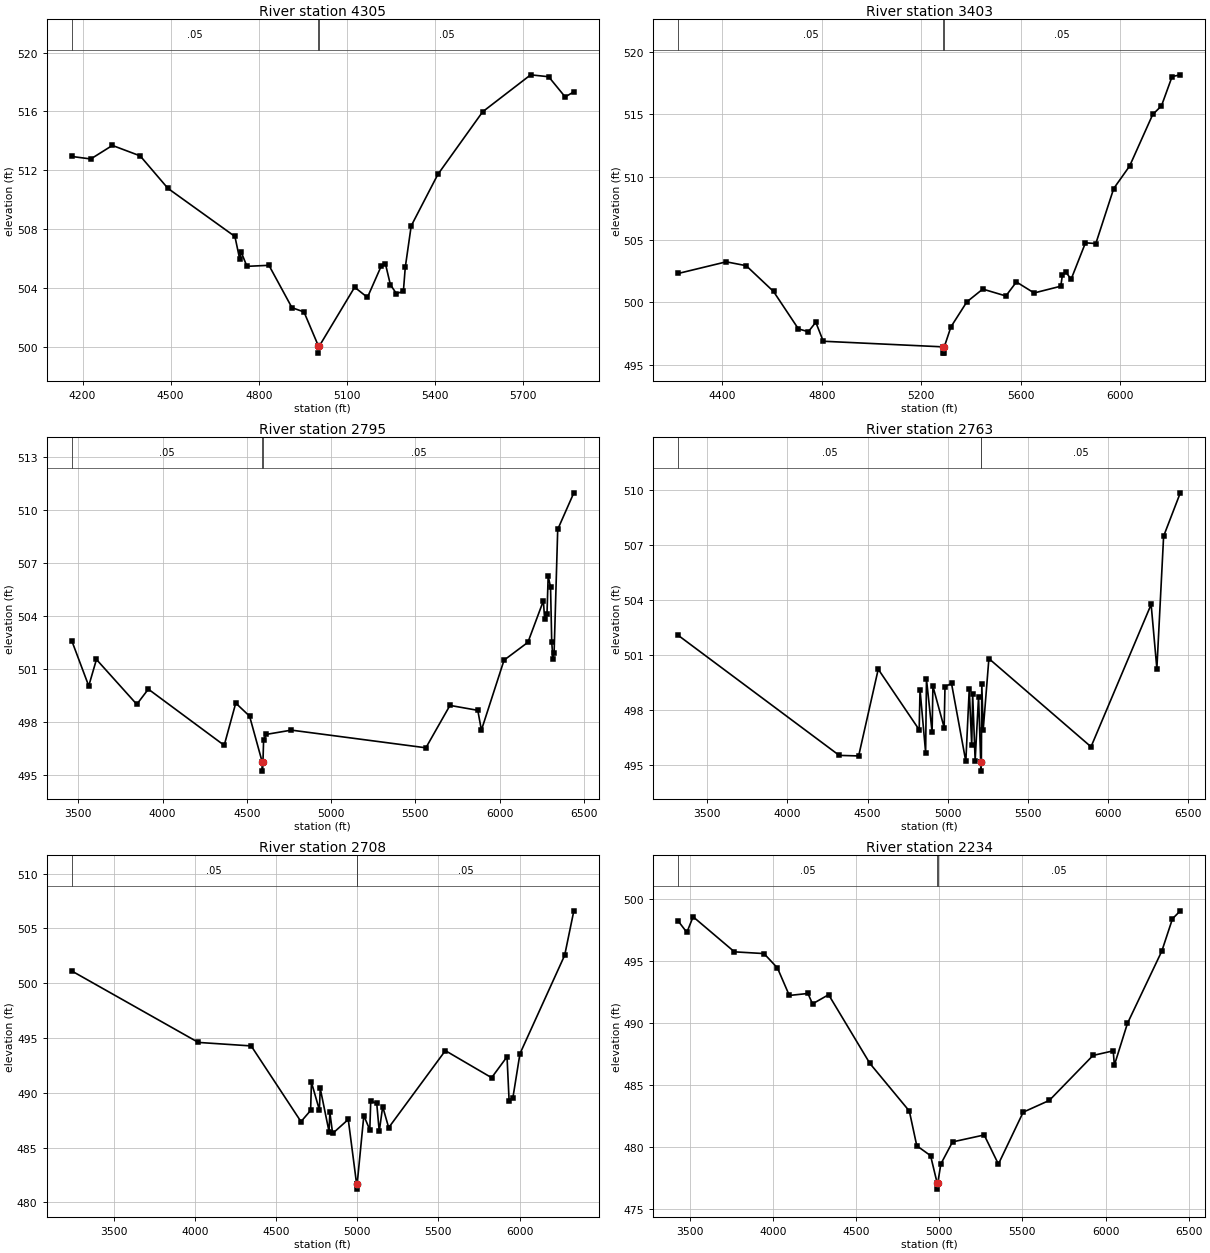
Type RM Length L Ch R = 1,4305,902,902,902
BEGIN DESCRIPTION:
Berry Creek Trib 13 8.0
END DESCRIPTION:
XS GIS Cut Line= 3
      2624093.20      6986027.71      2624257.53      6986808.84
      2624405.50      6987707.11
#Sta/Elev= 30
  4163.4  512.94  4228.1  512.77  4301.6  513.69  4396.1  512.98  4490.7  510.77
  4718.6  507.50  4734.8  505.97  4739.9  506.44  4759.5  505.47  4834.4  505.54
  4912.7  502.66  4953.6  502.37  5002.4  500.07  5002.6  499.57  5006.4  500.07
  5126.0  504.05  5169.6  503.36  5217.2  505.52  5230.7  505.65  5247.6  504.23
  5267.9  503.62  5291.9  503.77  5298.3  505.40  5318.5  508.22  5409.2  511.72
  5561.8  515.98  5725.1  518.49  5786.3  518.36  5842.4  516.99  5872.0  517.33
#Mann=3,-1,0
  4163.4    0.05       0  5002.4    0.05       0  5006.4    0.05       0
Bank Sta=5002.4,5006.4
Exp/Cntr=0.3,0.1

Type RM Length L Ch R = 1,3403,608,608,608
BEGIN DESCRIPTION:
Berry Creek Trib 13 7.0
END DESCRIPTION:
XS GIS Cut Line= 3
      2623485.55      6986447.78      2623512.36      6987224.62
      2624286.92      6988196.91
#Sta/Elev= 30
  4222.7  502.29  4416.0  503.22  4496.1  502.91  4606.1  500.85  4706.2  497.86
  4746.2  497.63  4776.2  498.39  4806.3  496.87  5289.3  496.42  5289.5  495.92
  5293.0  495.92  5293.3  496.42  5320.1  498.02  5384.2  500.02  5448.2  501.04
  5541.1  500.49  5583.5  501.61  5654.8  500.73  5762.1  501.27  5768.5  502.15
  5782.9  502.38  5803.8  501.83  5861.4  504.74  5903.1  504.68  5975.1  509.08
  6039.2  510.88  6132.1  515.00  6167.3  515.69  6210.0  518.03  6243.1  518.17
#Mann=3,-1,0
  4222.7    0.05       0  5289.3    0.03       0  5293.3    0.05       0
Bank Sta=5289.3,5293.3
Exp/Cntr=0.3,0.1

Type RM Length L Ch R = 1,2795,32,32,32
BEGIN DESCRIPTION:
Berry Creek Trib 13 6.0
END DESCRIPTION:
XS GIS Cut Line= 6
      2623534.17      6986145.71      2622995.97      6987322.81
      2623032.12      6987563.70      2623364.02      6988024.20
      2623554.71      6988118.02      2624005.83      6988596.53
#Sta/Elev= 30
  3461.6  502.59  3562.3  500.03  3608.0  501.53  3847.3  498.99  3915.8  499.85
  4366.0  496.67  4434.5  499.06  4516.6  498.32  4591.9  495.71  4592.2  495.21
  4595.9  495.71  4599.8  496.99  4616.0  497.29  4764.7  497.53  5562.6  496.53
  5705.4  498.93  5870.5  498.65  5892.0  497.53  6026.3  501.49  6167.9  502.50
  6259.7  504.85  6267.0  503.81  6281.2  504.13  6288.0  506.24  6302.2  505.63
  6309.1  502.53  6316.4  501.56  6323.2  501.90  6344.7  508.89  6440.4  510.96
#Mann=3,-1,0
  3461.6    0.05       0  4591.9    0.03       0  4595.9    0.05       0
Bank Sta=4591.9,4595.9
Exp/Cntr=0.3,0.1

Type RM Length L Ch R = 1,2763,55,55,55
BEGIN DESCRIPTION:
Mapping XS cf3ad28c
END DESCRIPTION:
XS GIS Cut Line= 6
      2623509.84      6986031.18      2622943.88      6987347.12
      2623027.22      6987666.56      2623270.27      6987999.90
      2623478.60      6988121.42      2623956.48      6988637.39
#Sta/Elev= 30
  3319.2  502.07  4323.1  495.51  4444.0  495.48  4566.2  500.22  4821.5  496.91
  4826.7  499.11  4861.7  495.66  4866.9  499.68  4902.0  496.78  4907.1  499.29
  4977.2  497.03  4982.4  499.27  5023.1  499.44  5112.3  495.18  5133.6  499.13
  5149.1  496.06  5154.9  498.86  5170.4  495.23  5191.7  498.72  5205.1  495.15
  5205.3  494.65  5209.1  495.15  5211.9  499.40  5220.8  496.92  5256.1  500.80
  5892.9  495.98  6267.7  503.76  6303.4  500.25  6345.5  507.49  6449.6  509.86
#Mann=3,-1,0
  3319.2    0.05       0  5205.1    0.04       0  5209.1    0.05       0
Bank Sta=5205.1,5209.1
Exp/Cntr=0.3,0.1

Type RM Length L Ch R = 1,2708,474,474,474
BEGIN DESCRIPTION:
Berry Creek Trib 13 5.0
END DESCRIPTION:
XS GIS Cut Line= 4
      2623478.60      6985986.01      2622895.27      6987239.48
      2622960.61      6987610.31      2623651.59      6988752.34
#Sta/Elev= 30
  3240.9  501.12  4020.7  494.60  4346.5  494.28  4653.4  487.37  4712.7  488.39
  4717.8  490.96  4766.9  488.43  4772.0  490.41  4826.2  486.46  4831.3  488.21
  4848.4  486.29  4944.7  487.57  4995.8  481.71  4996.1  481.21  4999.8  481.71
  5040.6  487.92  5077.4  486.62  5083.2  489.23  5120.1  489.05  5135.6  486.48
  5156.9  488.74  5193.8  486.82  5543.0  493.85  5828.1  491.38  5923.1  493.29
  5935.8  489.28  5959.2  489.55  6002.7  493.57  6278.2  502.55  6334.8  506.61
#Mann=3,-1,0
  3240.9    0.05       0  4995.8    0.04       0  4999.8    0.05       0
Bank Sta=4995.8,4999.8
Exp/Cntr=0.3,0.1

Type RM Length L Ch R = 1,2234,0,0,0
BEGIN DESCRIPTION:
Mapping XS 4193972f
END DESCRIPTION:
XS GIS Cut Line= 5
      2623385.67      6986079.38      2622694.71      6987303.73
      2622652.28      6987461.32      2622670.46      6987740.14
      2623396.87      6988657.23
#Sta/Elev= 30
  3431.3  498.25  3483.2  497.34  3520.7  498.60  3769.1  495.77  3946.8  495.63
  4027.7  494.47  4099.1  492.25  4211.1  492.41  4238.5  491.57  4335.3  492.31
  4583.7  486.76  4820.6  482.92  4865.4  480.12  4948.3  479.32  4987.7  477.12
  4987.9  476.62  4991.7  477.12  5010.1  478.65  5080.2  480.43  5270.6  480.99
  5356.1  478.64  5505.1  482.83  5662.2  483.78  5925.0  487.41  6046.3  487.78
  6053.2  486.62  6131.7  489.99  6338.5  495.83  6402.6  498.44  6449.7  499.08
#Mann=3,-1,0
  3431.3    0.05       0  4987.7    0.04       0  4991.7    0.05       0
Bank Sta=4987.7,4991.7
Exp/Cntr=0.3,0.1

Chan Stop Cuts=-1