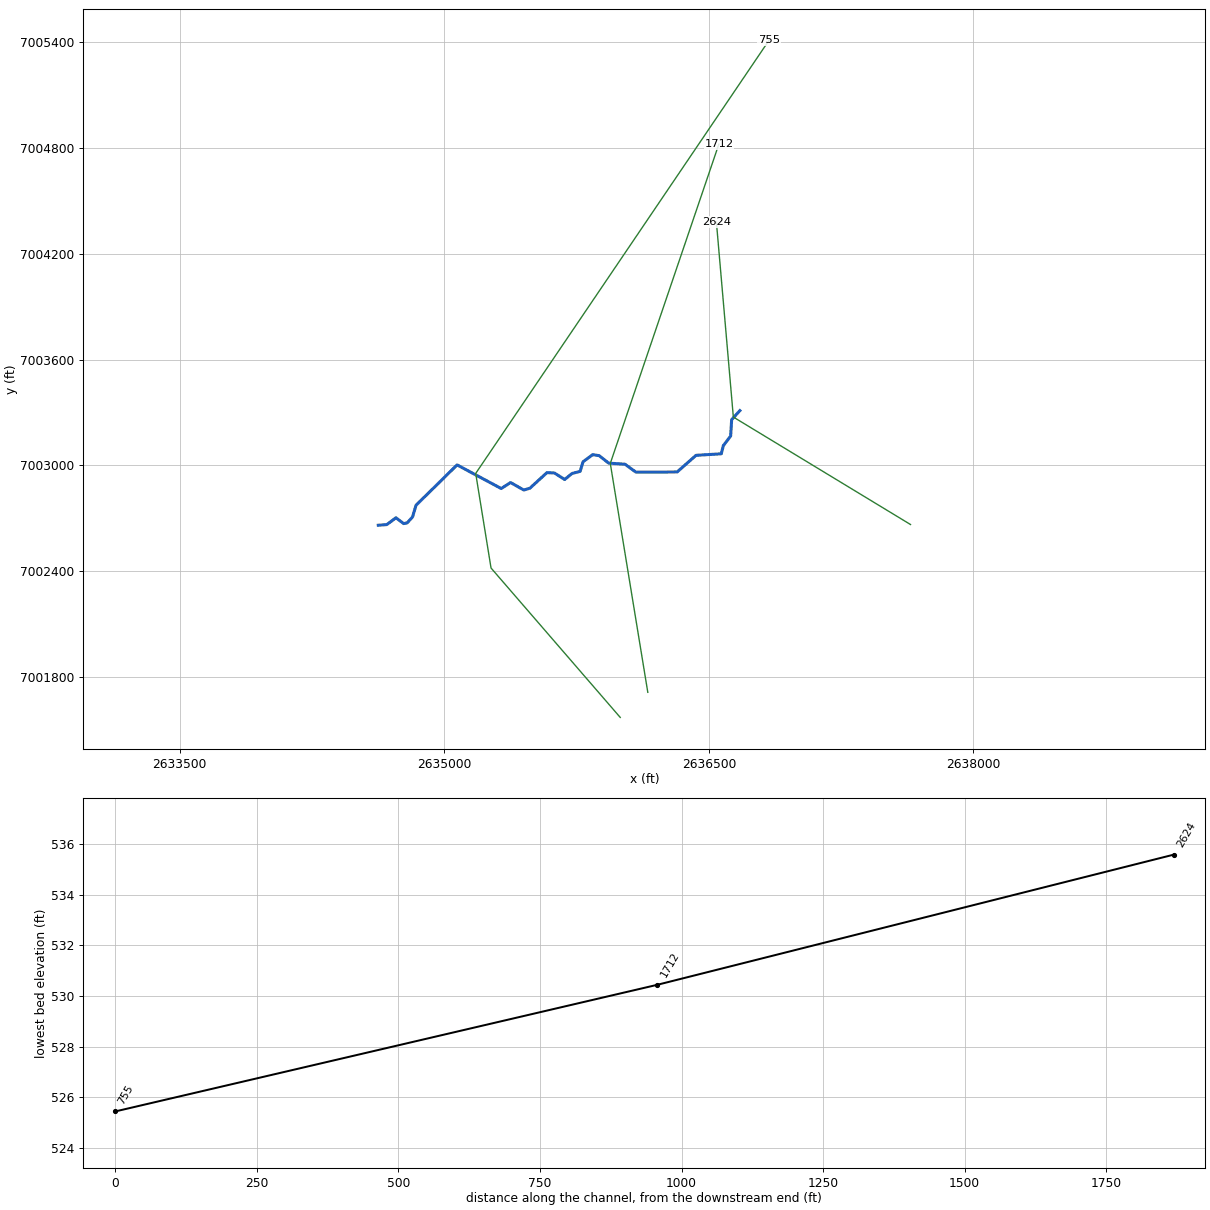
--- Berry Creek Trib 2.prj (project) ---

Proj Title=Berry Creek Trib 2 Base Level Engineering
Current Plan=p01
Default Exp/Contr=0.3,0.1
English Units
Geom File=g01
Flow File=f01
Plan File=p01
BEGIN DESCRIPTION:
Berry Creek Trib 2
END DESCRIPTION:

--- Berry Creek Trib 2.p01 (plan) ---

Plan Title=Multiple Run
Short Identifier=Multiple
Geom File=g01
Flow File=f01
Subcritical Flow
K Sum by GR= 0
Std Step Tol= 0.01
Critical Tol= 0.01
Num of Std Step Trials= 20
Max Error Tol= 0.3
Flow Tol Ratio= 0.001
Split Flow NTrial= 30
Split Flow Tol= 0.02
Split Flow Ratio= 0.02
Log Output Level= 0
Friction Slope Method= 1
Unsteady Friction Slope Method= 2
Unsteady Bridges Friction Slope Method= 1
Parabolic Critical Depth
Global Vel Dist=  1 , 1 , 1
Global Log Level= 0
CheckData=True
Encroach Param= -1, 0, 0, 0
BEGIN DESCRIPTION:
Multiple Run
END DESCRIPTION:

--- Berry Creek Trib 2.f01 (steady flow) ---

Flow Title=Multiple
Number of Profiles=7
Profile Names=10-year,25-year,50-year,1pct_min,100-year,1pct_plu,500-year
River Rch & RM= Berry Creek Trib,Reach-1,2624
     240     303     351     202     404     806     533
Boundary for River Rch & Prof#=Berry Creek Trib,Reach-1,1
Up Type=0
Dn Type=3
Dn Slope=0.005
Boundary for River Rch & Prof#=Berry Creek Trib,Reach-1,2
Up Type=0
Dn Type=3
Dn Slope=0.005
Boundary for River Rch & Prof#=Berry Creek Trib,Reach-1,3
Up Type=0
Dn Type=3
Dn Slope=0.005
Boundary for River Rch & Prof#=Berry Creek Trib,Reach-1,4
Up Type=0
Dn Type=3
Dn Slope=0.005
Boundary for River Rch & Prof#=Berry Creek Trib,Reach-1,5
Up Type=0
Dn Type=3
Dn Slope=0.005
Boundary for River Rch & Prof#=Berry Creek Trib,Reach-1,6
Up Type=0
Dn Type=3
Dn Slope=0.005
Boundary for River Rch & Prof#=Berry Creek Trib,Reach-1,7
Up Type=0
Dn Type=3
Dn Slope=0.005

--- Berry Creek Trib 2.g01 (geometry) ---

Geom Title=Existing Conditions

River Reach=Berry Creek Trib,Reach-1
Reach XY= 30
      2636676.00      7003311.00      2636629.39      7003259.60
      2636623.71      7003166.93      2636582.30      7003112.78
      2636570.59      7003066.18      2636427.48      7003057.44
      2636320.14      7002963.07      2636086.50      7002962.22
      2636024.40      7003007.14      2635931.96      7003013.38
      2635878.15      7003055.66      2635841.22      7003061.09
      2635786.76      7003020.85      2635770.37      7002966.59
      2635724.05      7002954.45      2635682.66      7002920.41
      2635624.35      7002957.42      2635582.05      7002959.33
      2635485.67      7002871.23      2635451.00      7002860.59
      2635375.92      7002903.17      2635322.77      7002869.24
      2635072.59      7003003.23      2634839.63      7002774.18
      2634820.14      7002708.17      2634789.69      7002674.49
      2634769.49      7002670.50      2634726.08      7002703.41
      2634674.64      7002664.98      2634626.00      7002661.00

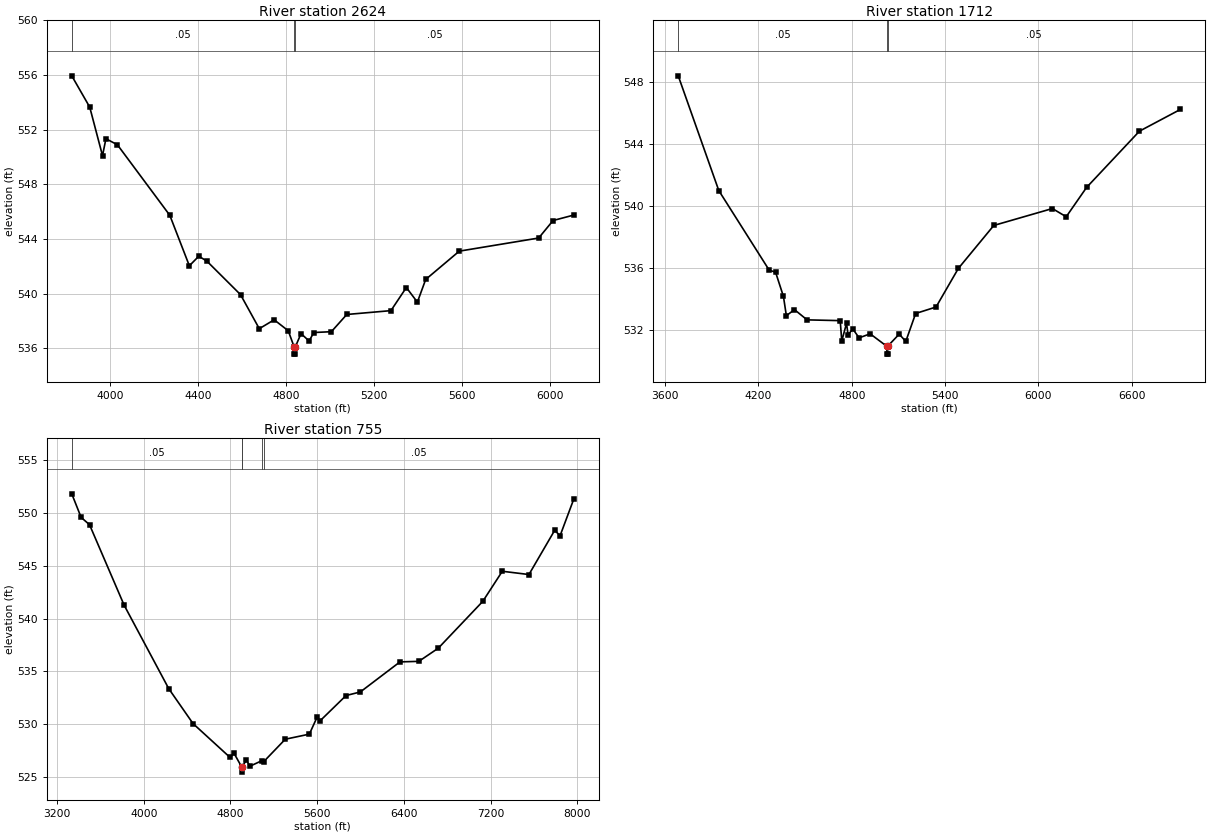
Type RM Length L Ch R = 1,2624,912,912,912
BEGIN DESCRIPTION:
Berry Creek Trib 2 5.0
END DESCRIPTION:
XS GIS Cut Line= 3
      2637643.52      7002665.16      2636638.97      7003274.48
      2636542.84      7004380.41
#Sta/Elev= 30
  3825.1  555.93  3906.9  553.64  3965.0  550.09  3980.5  551.33  4032.7  550.89
  4271.3  545.73  4360.2  542.04  4403.2  542.74  4440.0  542.38  4593.1  539.93
  4678.5  537.44  4746.2  538.09  4810.3  537.29  4837.7  536.08  4838.0  535.58
  4841.5  535.58  4841.7  536.08  4868.5  537.08  4905.3  536.54  4926.6  537.16
  5006.5  537.22  5076.8  538.48  5277.6  538.76  5347.8  540.45  5398.0  539.38
  5435.8  541.04  5588.7  543.11  5950.1  544.07  6015.6  545.35  6110.1  545.75
#Mann=3,-1,0
  3825.1    0.05       0  4837.7    0.03       0  4841.7    0.05       0
Bank Sta=4837.7,4841.7
Exp/Cntr=0.3,0.1

Type RM Length L Ch R = 1,1712,957,957,957
BEGIN DESCRIPTION:
Berry Creek Trib 2 4.0
END DESCRIPTION:
XS GIS Cut Line= 3
      2636153.94      7001713.79      2635941.27      7003011.68
      2636556.72      7004821.39
#Sta/Elev= 30
  3684.8  548.39  3945.4  540.99  4269.7  535.85  4310.2  535.73  4360.9  534.16
  4379.7  532.92  4431.8  533.31  4512.9  532.65  4725.7  532.60  4735.8  531.29
  4766.2  532.42  4776.4  531.69  4806.8  532.06  4847.3  531.49  4918.2  531.75
  5026.0  530.94  5026.2  530.44  5029.7  530.44  5030.0  530.94  5104.9  531.73
  5147.2  531.26  5210.5  533.06  5341.7  533.48  5485.2  535.97  5712.9  538.74
  6089.4  539.83  6178.2  539.30  6309.0  541.19  6648.8  544.82  6911.5  546.22
#Mann=3,-1,0
  3684.8    0.05       0  5026.0    0.03       0  5030.0    0.05       0
Bank Sta=5026,5030
Exp/Cntr=0.3,0.1

Type RM Length L Ch R = 1,755,0,0,0
BEGIN DESCRIPTION:
Berry Creek Trib 2 3.0
END DESCRIPTION:
XS GIS Cut Line= 4
      2635997.72      7001571.38      2635265.06      7002418.63
      2635178.19      7002954.95      2636841.66      7005411.15
#Sta/Elev= 30
  3336.6  551.82  3422.7  549.59  3500.5  548.89  3819.7  541.26  4231.0  533.35
  4455.0  530.04  4796.6  526.83  4833.9  527.21  4902.8  525.94  4903.1  525.44
  4906.8  525.94  4945.4  526.56  4981.6  526.01  5090.4  526.53  5107.3  526.44
  5305.7  528.56  5527.4  529.04  5599.3  530.66  5623.2  530.27  5865.9  532.70
  5997.7  533.04  6363.2  535.89  6536.9  535.94  6716.6  537.19  7127.0  541.63
  7306.8  544.48  7552.4  544.17  7789.1  548.35  7840.0  547.86  7966.5  551.34
#Mann=5,-1,0
  3336.6    0.05       0  4902.8    0.03       0  4906.8    0.05       0
  5090.4    0.12       0  5107.3    0.05       0
Bank Sta=4902.8,4906.8
Exp/Cntr=0.3,0.1

Chan Stop Cuts=-1