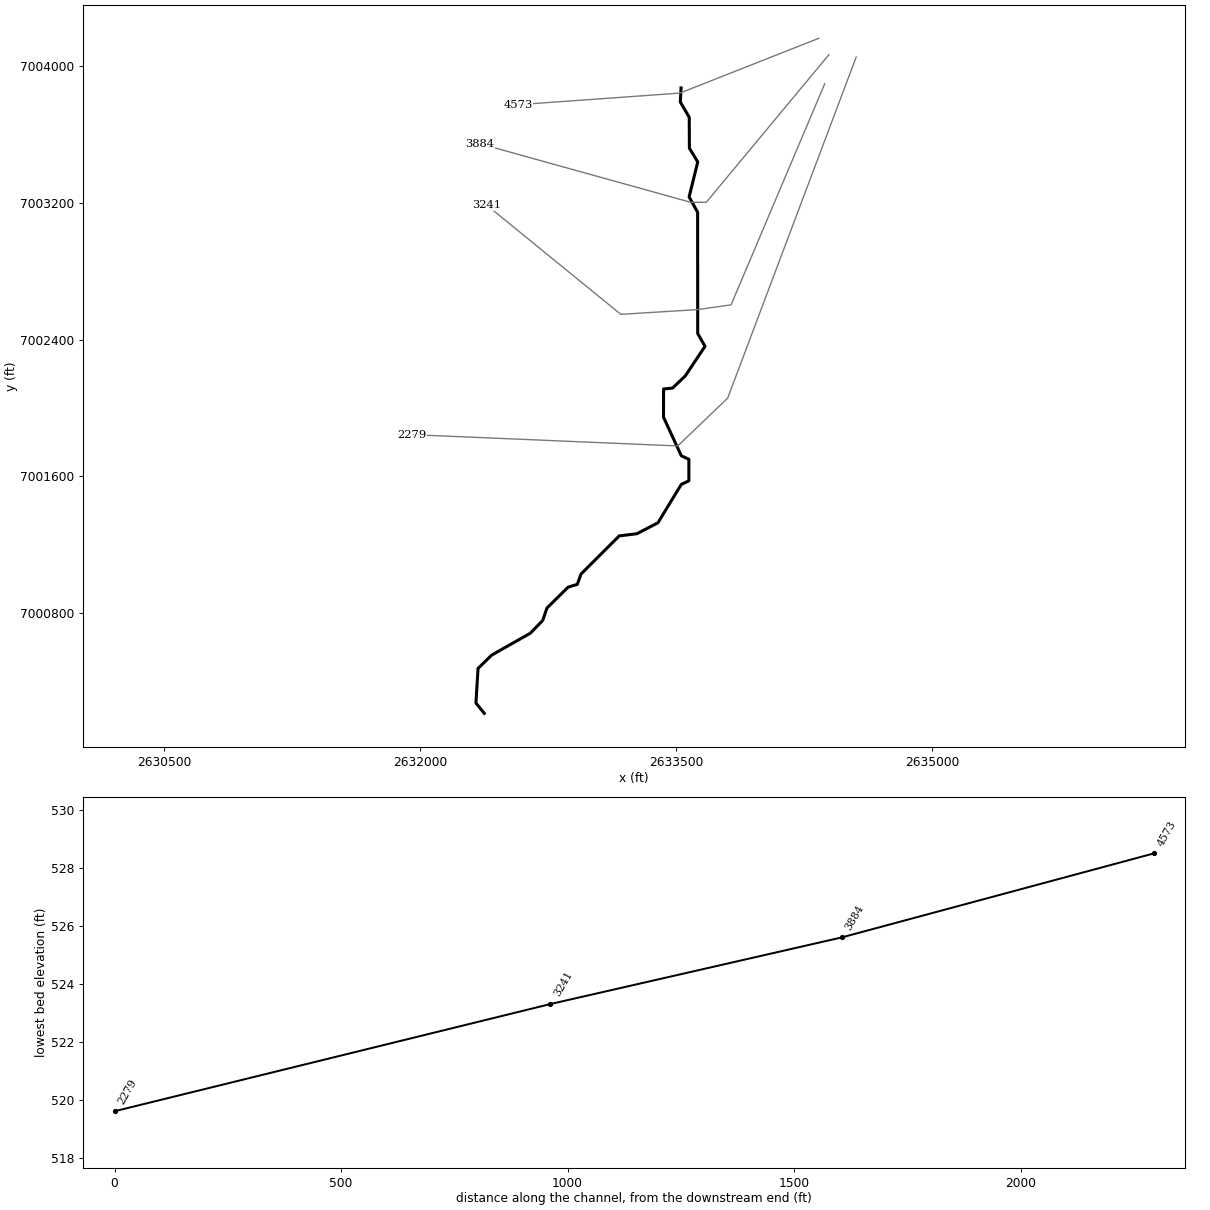
--- Berry Creek Trib 3.prj (project) ---

Proj Title=Berry Creek Trib 3 Base Level Engineering
Current Plan=p01
Default Exp/Contr=0.3,0.1
English Units
Geom File=g01
Flow File=f01
Plan File=p01
Y Axis Title=Elevation
X Axis Title(PF)=Main Channel Distance
X Axis Title(XS)=Station
BEGIN DESCRIPTION:
Berry Creek Trib 3
END DESCRIPTION:
DSS Export Rating Curves= 0
DSS Export Rating Curve Sorted= 0
DSS Export Volume Flow Curves= 0
DXF OffsetX= 0
DXF OffsetY= 0
DXF ScaleX= 1
DXF ScaleY= 10

--- Berry Creek Trib 3.p01 (plan) ---

Plan Title=Multiple Run
Short Identifier=Multiple
Geom File=g01
Flow File=f01
Subcritical Flow
K Sum by GR= 0
Std Step Tol= 0.01
Critical Tol= 0.01
Num of Std Step Trials= 20
Max Error Tol= 0.3
Flow Tol Ratio= 0.001
Split Flow NTrial= 30
Split Flow Tol= 0.02
Split Flow Ratio= 0.02
Log Output Level= 0
Friction Slope Method= 1
Unsteady Friction Slope Method= 2
Unsteady Bridges Friction Slope Method= 1
Parabolic Critical Depth
Global Vel Dist=  1 , 1 , 1
Global Log Level= 0
CheckData=True
Encroach Param= -1, 0, 0, 0
BEGIN DESCRIPTION:
Multiple Run
END DESCRIPTION:

--- Berry Creek Trib 3.f01 (steady flow) ---

Flow Title=Multiple
Program Version=4.10
Number of Profiles= 7
Profile Names=10-year,25-year,50-year,1pct_min,100-year,1pct_plu,500-year
River Rch & RM=Berry Creek Trib,Reach-1         ,4573
     191     237     270     154     306     611     393
River Rch & RM=Berry Creek Trib,Reach-1         ,2279
     353     455     533     311     620    1238     838
Boundary for River Rch & Prof#=Berry Creek Trib,Reach-1         , 1
Up Type= 0
Dn Type= 3
Dn Slope=0.00381
Boundary for River Rch & Prof#=Berry Creek Trib,Reach-1         , 2
Up Type= 0
Dn Type= 3
Dn Slope=0.00381
Boundary for River Rch & Prof#=Berry Creek Trib,Reach-1         , 3
Up Type= 0
Dn Type= 3
Dn Slope=0.00381
Boundary for River Rch & Prof#=Berry Creek Trib,Reach-1         , 4
Up Type= 0
Dn Type= 3
Dn Slope=0.00381
Boundary for River Rch & Prof#=Berry Creek Trib,Reach-1         , 5
Up Type= 0
Dn Type= 3
Dn Slope=0.00381
Boundary for River Rch & Prof#=Berry Creek Trib,Reach-1         , 6
Up Type= 0
Dn Type= 3
Dn Slope=0.00381
Boundary for River Rch & Prof#=Berry Creek Trib,Reach-1         , 7
Up Type= 0
Dn Type= 3
Dn Slope=0.00381
DSS Import GetInterval= 0
DSS Import GetPeak= 0
DSS Import FillOption= 0

--- Berry Creek Trib 3.g01 (geometry) ---

Geom Title=Existing Conditions

River Reach=Berry Creek Trib,Reach-1
Reach XY= 30
      2633528.27      7003874.31      2633524.11      7003792.02
      2633576.30      7003702.43      2633577.22      7003521.50
      2633626.09      7003440.90      2633575.60      7003236.00
      2633625.48      7003145.78      2633625.89      7002435.88
      2633668.67      7002360.90      2633553.02      7002187.49
      2633478.54      7002116.30      2633426.00      7002111.00
      2633425.55      7001945.81      2633529.91      7001719.65
      2633574.10      7001699.04      2633574.10      7001572.96
      2633529.94      7001552.34      2633393.05      7001327.49
      2633270.03      7001263.33      2633166.21      7001250.48
      2632942.73      7001027.48      2632920.38      7000966.62
      2632866.58      7000950.11      2632742.65      7000827.67
      2632717.85      7000754.93      2632646.13      7000680.77
      2632419.93      7000552.85      2632339.36      7000474.34
      2632326.96      7000271.40      2632376.00      7000211.00

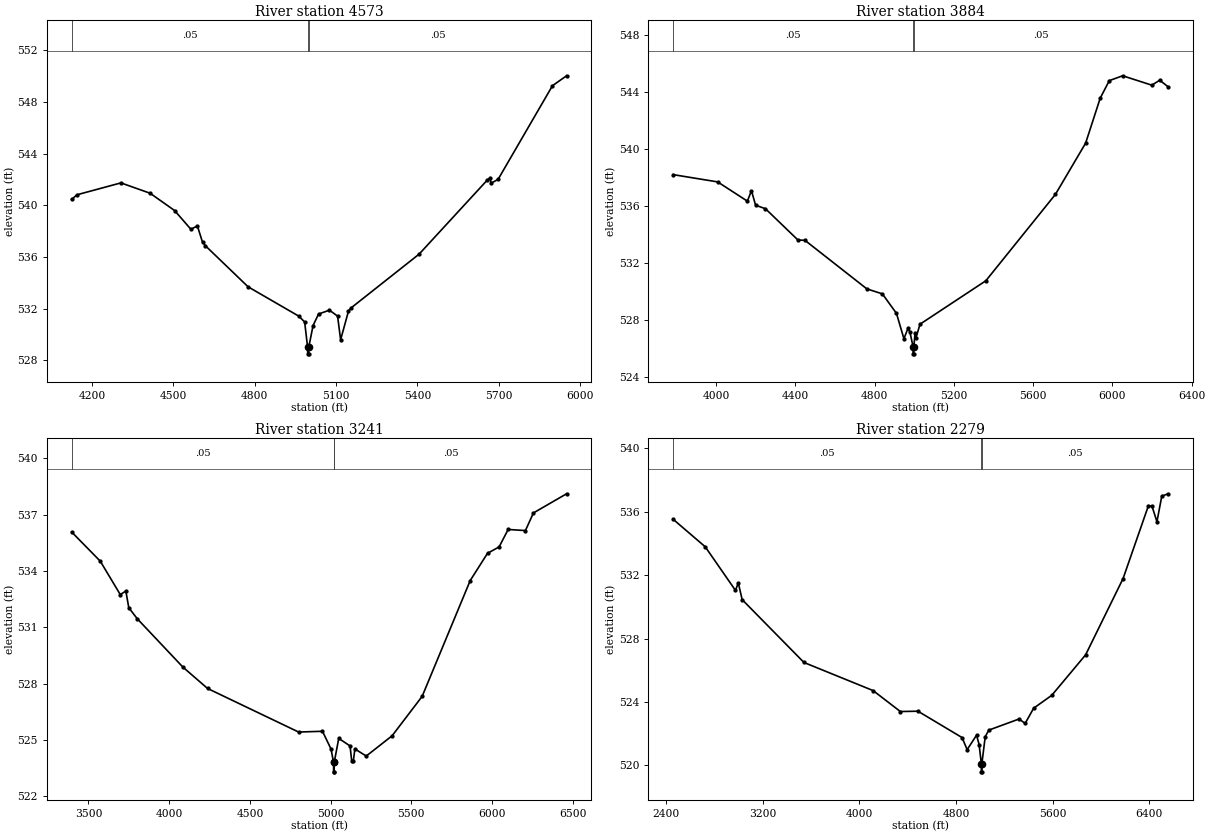
Type RM Length L Ch R = 1,4573,689,689,689
BEGIN DESCRIPTION:
Berry Creek Trib 3 9.0
END DESCRIPTION:
XS GIS Cut Line= 3
      2634334.65      7004164.78      2633521.50      7003844.10
      2632574.14      7003776.08
#Sta/Elev= 30
  4125.9  540.45  4145.2  540.81  4307.2  541.73  4414.7  540.93  4505.1  539.59
  4565.2  538.14  4589.0  538.40  4608.0  537.14  4618.9  536.86  4775.8  533.69
  4962.6  531.42  4984.4  530.97  4995.4  529.00  4995.7  528.50  4999.2  528.50
  4999.4  529.00  5015.5  530.69  5035.6  531.58  5075.7  531.88  5105.8  531.42
  5117.0  529.59  5145.9  531.80  5155.9  532.06  5406.5  536.22  5657.2  541.94
  5666.9  542.10  5672.0  541.71  5697.3  542.00  5897.8  549.25  5949.8  550.02
#Mann=3,-1,0
  4125.9    0.05       0  4995.4   0.035       0  4999.4    0.05       0
Bank Sta=4995.4,4999.4
Exp/Cntr=0.3,0.1

Type RM Length L Ch R = 1,3884,643,643,643
BEGIN DESCRIPTION:
Mapping XS 76a04d5c
END DESCRIPTION:
XS GIS Cut Line= 4
      2634394.06      7004068.74      2633676.14      7003204.49
      2633584.69      7003204.49      2632350.51      7003547.31
#Sta/Elev= 30
  3784.7  538.18  4008.9  537.67  4158.7  536.32  4179.5  537.05  4200.3  536.03
  4249.8  535.79  4413.9  533.59  4449.0  533.57  4761.5  530.16  4839.7  529.81
  4910.8  528.44  4948.4  526.66  4968.4  527.38  4978.4  527.15  4994.5  526.10
  4994.8  525.60  4998.3  525.60  4998.5  526.10  5004.4  527.04  5009.6  526.74
  5029.5  527.68  5361.6  530.73  5712.3  536.79  5864.8  540.39  5938.5  543.55
  5984.3  544.78  6051.6  545.12  6199.0  544.46  6238.5  544.81  6280.6  544.35
#Mann=3,-1,0
  3784.7    0.05       0  4994.5   0.035       0  4998.5    0.05       0
Bank Sta=4994.5,4998.5
Exp/Cntr=0.3,0.1

Type RM Length L Ch R = 1,3241,962,962,962
BEGIN DESCRIPTION:
Mapping XS 389c4b6c
END DESCRIPTION:
XS GIS Cut Line= 5
      2634369.97      7003899.01      2633821.34      7002603.85
      2633626.90      7002576.07      2633175.51      7002548.29
      2632392.22      7003186.02
#Sta/Elev= 30
  3396.1  536.07  3573.0  534.52  3696.9  532.74  3731.4  532.93  3749.6  532.04
  3802.4  531.45  4084.6  528.88  4237.6  527.74  4801.5  525.42  4949.5  525.46
  5002.6  524.51  5018.0  523.80  5018.3  523.30  5021.8  523.30  5022.0  523.80
  5050.1  525.08  5120.2  524.68  5130.2  523.90  5140.3  523.87  5150.3  524.52
  5220.4  524.14  5380.7  525.22  5566.8  527.32  5864.6  533.49  5971.7  534.94
  6043.5  535.28  6099.5  536.21  6206.5  536.15  6256.1  537.09  6461.4  538.11
#Mann=3,-1,0
  3396.1    0.05       0  5018.0   0.035       0  5022.0    0.05       0
Bank Sta=5018,5022
Exp/Cntr=0.3,0.1

Type RM Length L Ch R = 1,2279,0,0,0
BEGIN DESCRIPTION:
Berry Creek Trib 3 7.0
END DESCRIPTION:
XS GIS Cut Line= 4
      2634554.12      7004055.05      2633801.38      7002057.41
      2633508.92      7001777.33      2631954.12      7001843.44
#Sta/Elev= 30
  2460.3  535.51  2725.4  533.78  2975.9  531.03  2999.0  531.51  3031.0  530.45
  3542.7  526.49  4114.8  524.72  4340.5  523.40  4486.2  523.42  4851.1  521.76
  4893.3  521.00  4971.2  521.91  4992.3  521.32  5010.9  520.10  5011.2  519.60
  5014.7  519.60  5014.9  520.10  5043.0  521.82  5073.0  522.23  5323.2  522.93
  5373.3  522.65  5443.9  523.61  5593.5  524.42  5873.7  526.97  6184.0  531.78
  6394.2  536.38  6424.2  536.32  6464.2  535.36  6504.3  536.97  6556.2  537.12
#Mann=3,-1,0
  2460.3    0.05       0  5010.9   0.035       0  5014.9    0.05       0
Bank Sta=5010.9,5014.9
Exp/Cntr=0.3,0.1

Chan Stop Cuts=-1