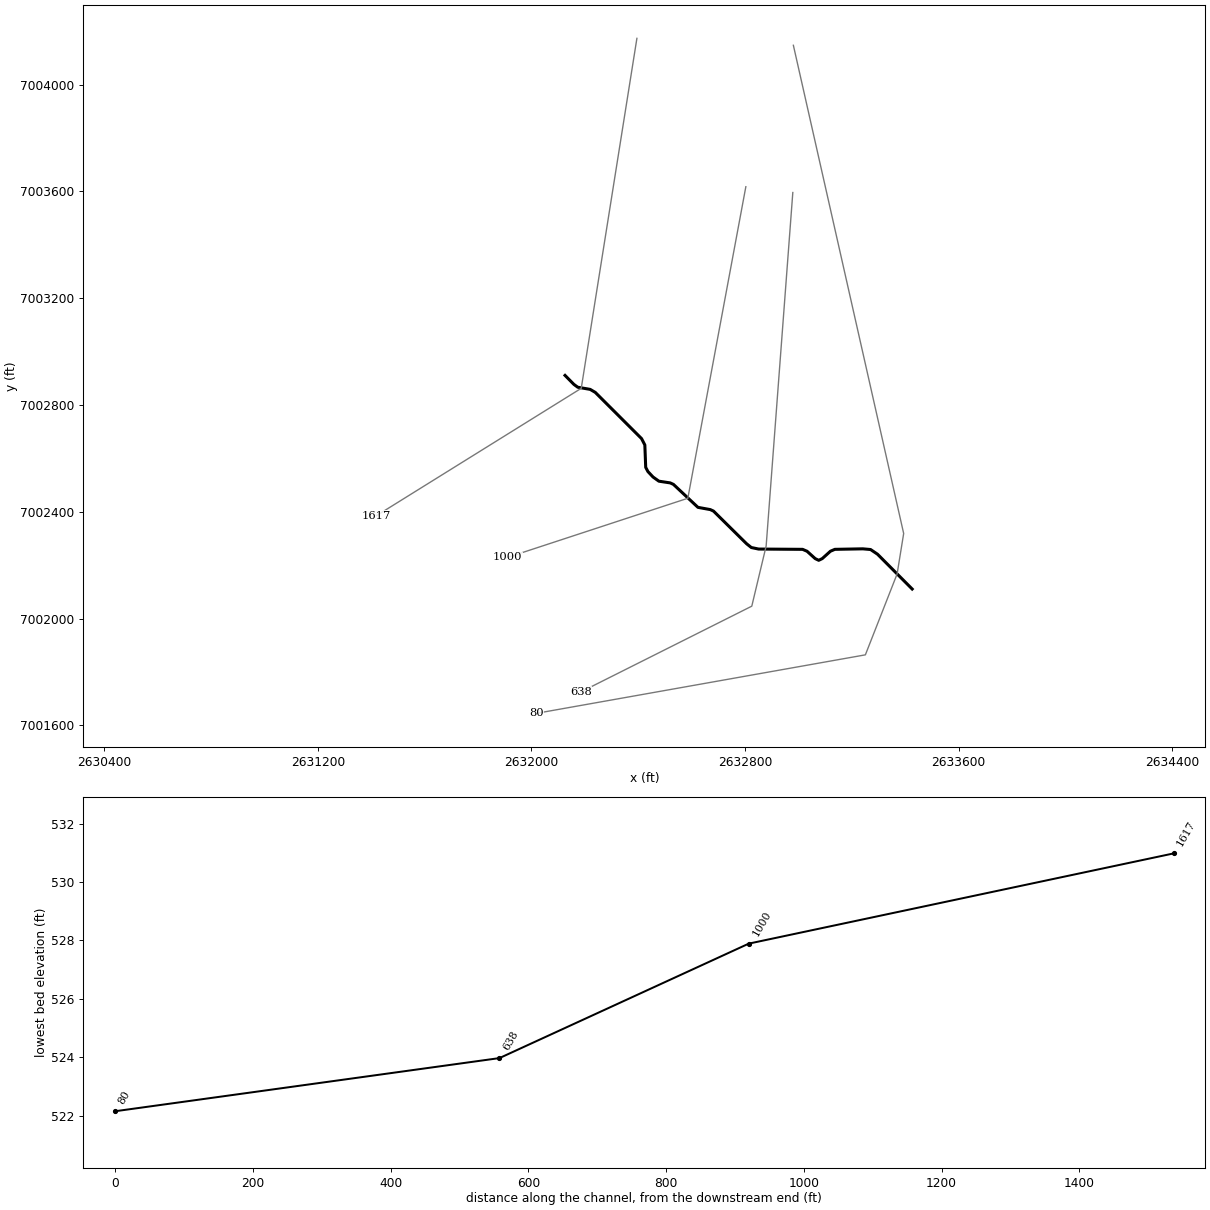
--- Berry Creek Trib 4.prj (project) ---

Proj Title=Berry Creek Trib 4 Base Level Engineering
Current Plan=p01
Default Exp/Contr=0.3,0.1
English Units
Geom File=g01
Flow File=f01
Plan File=p01
Y Axis Title=Elevation
X Axis Title(PF)=Main Channel Distance
X Axis Title(XS)=Station
BEGIN DESCRIPTION:
Berry Creek Trib 4
END DESCRIPTION:
DSS Export Rating Curves= 0
DSS Export Rating Curve Sorted= 0
DSS Export Volume Flow Curves= 0
DXF OffsetX= 0
DXF OffsetY= 0
DXF ScaleX= 1
DXF ScaleY= 10

--- Berry Creek Trib 4.p01 (plan) ---

Plan Title=Multiple Run
Short Identifier=Multiple
Geom File=g01
Flow File=f01
Subcritical Flow
K Sum by GR= 0
Std Step Tol= 0.01
Critical Tol= 0.01
Num of Std Step Trials= 20
Max Error Tol= 0.3
Flow Tol Ratio= 0.001
Split Flow NTrial= 30
Split Flow Tol= 0.02
Split Flow Ratio= 0.02
Log Output Level= 0
Friction Slope Method= 1
Unsteady Friction Slope Method= 2
Unsteady Bridges Friction Slope Method= 1
Parabolic Critical Depth
Global Vel Dist=  1 , 1 , 1
Global Log Level= 0
CheckData=True
Encroach Param= -1, 0, 0, 0
BEGIN DESCRIPTION:
Multiple Run
END DESCRIPTION:

--- Berry Creek Trib 4.f01 (steady flow) ---

Flow Title=Multiple
Program Version=4.10
Number of Profiles= 7
Profile Names=10-year,25-year,50-year,1pct_min,100-year,1pct_plu,500-year
River Rch & RM=Berry Creek Trib,Reach-1         ,1617
     213     268     311     180     358     715     475
Boundary for River Rch & Prof#=Berry Creek Trib,Reach-1         , 1
Up Type= 0
Dn Type= 3
Dn Slope=0.00324
Boundary for River Rch & Prof#=Berry Creek Trib,Reach-1         , 2
Up Type= 0
Dn Type= 3
Dn Slope=0.00324
Boundary for River Rch & Prof#=Berry Creek Trib,Reach-1         , 3
Up Type= 0
Dn Type= 3
Dn Slope=0.00324
Boundary for River Rch & Prof#=Berry Creek Trib,Reach-1         , 4
Up Type= 0
Dn Type= 3
Dn Slope=0.00324
Boundary for River Rch & Prof#=Berry Creek Trib,Reach-1         , 5
Up Type= 0
Dn Type= 3
Dn Slope=0.00324
Boundary for River Rch & Prof#=Berry Creek Trib,Reach-1         , 6
Up Type= 0
Dn Type= 3
Dn Slope=0.00324
Boundary for River Rch & Prof#=Berry Creek Trib,Reach-1         , 7
Up Type= 0
Dn Type= 3
Dn Slope=0.00324
DSS Import GetInterval= 0
DSS Import GetPeak= 0
DSS Import FillOption= 0

--- Berry Creek Trib 4.g01 (geometry) ---

Geom Title=Existing Conditions

River Reach=Berry Creek Trib,Reach-1
Reach XY= 30
      2632126.00      7002911.00      2632159.08      7002877.42
      2632173.65      7002866.71      2632220.03      7002858.66
      2632239.23      7002847.43      2632412.59      7002674.30
      2632424.83      7002650.51      2632428.08      7002566.71
      2632436.39      7002550.90      2632455.43      7002530.59
      2632477.40      7002514.87      2632519.91      7002508.44
      2632532.02      7002502.81      2632623.72      7002416.87
      2632669.95      7002408.47      2632682.05      7002402.84
      2632805.84      7002280.61      2632823.55      7002266.46
      2632850.88      7002260.71      2633015.56      7002259.62
      2633032.18      7002252.55      2633062.79      7002224.95
      2633076.00      7002218.56      2633089.21      7002224.95
      2633119.82      7002252.55      2633136.44      7002259.63
      2633241.19      7002261.53      2633270.15      7002258.96
      2633296.17      7002241.41      2633426.00      7002111.00

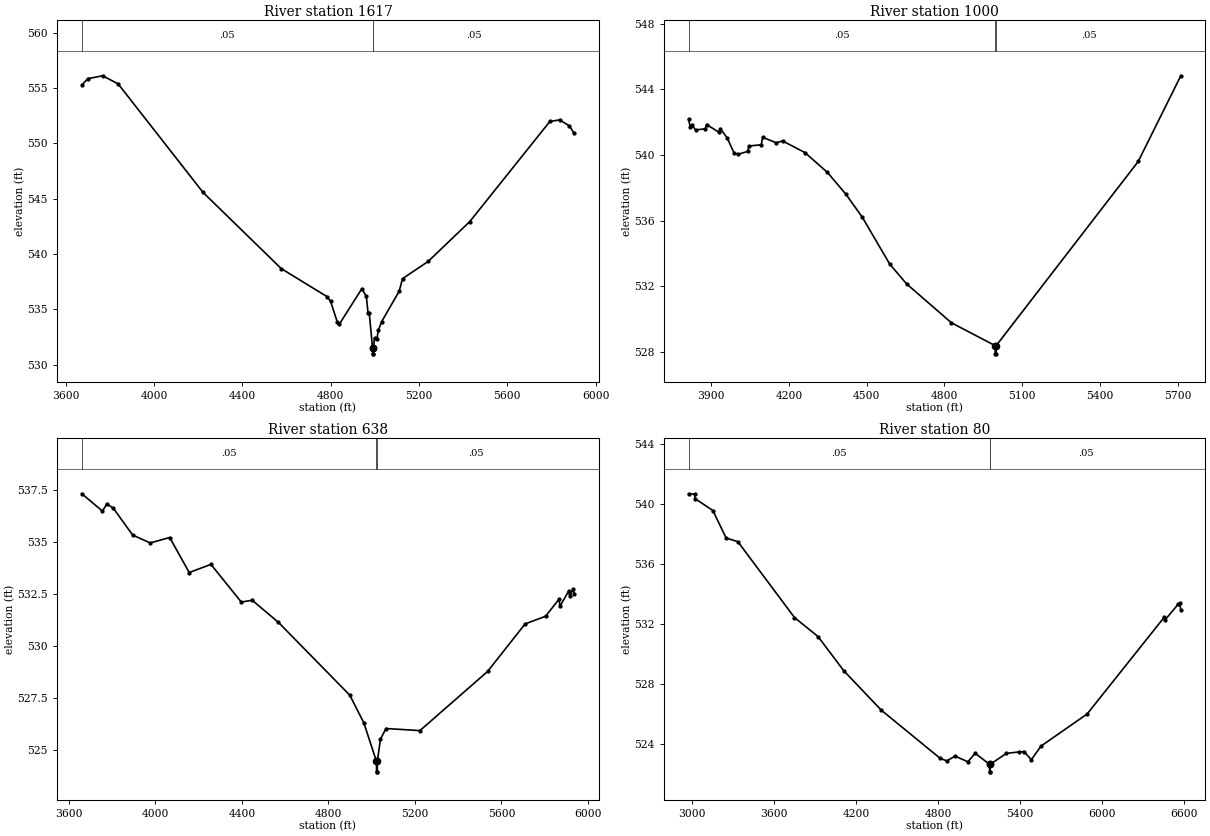
Type RM Length L Ch R = 1,1617,617,617,617
BEGIN DESCRIPTION:
Berry Creek Trib 4 3.0
END DESCRIPTION:
XS GIS Cut Line= 3
      2632395.14      7004173.28      2632186.69      7002862.66
      2631420.52      7002386.26
#Sta/Elev= 30
  3672.9  555.28  3699.9  555.86  3767.2  556.12  3837.2  555.39  4222.0  545.57
  4576.4  538.68  4782.8  536.16  4799.2  535.74  4829.5  533.87  4839.7  533.68
  4940.9  536.87  4961.2  536.17  4969.4  534.63  4974.4  534.68  4989.6  531.48
  4989.8  530.98  4993.3  530.98  4993.6  531.48  4998.3  532.42  5009.6  532.36
  5015.5  533.10  5030.9  533.90  5110.0  536.64  5125.3  537.78  5241.0  539.33
  5429.9  542.94  5792.4  551.99  5836.9  552.13  5880.9  551.59  5902.2  550.92
#Mann=3,-1,0
  3672.9    0.05       0  4989.6   0.035       0  4993.6    0.05       0
Bank Sta=4989.6,4993.6
Exp/Cntr=0.3,0.1

Type RM Length L Ch R = 1,1000,362,362,362
BEGIN DESCRIPTION:
Berry Creek Trib 4 2.0
END DESCRIPTION:
XS GIS Cut Line= 3
      2632803.12      7003617.68      2632585.86      7002450.93
      2631910.02      7002229.13
#Sta/Elev= 30
  3813.2  542.18  3819.8  541.71  3824.9  541.86  3840.3  541.53  3877.7  541.60
  3882.8  541.86  3930.4  541.39  3935.5  541.61  3962.4  541.04  3988.2  540.14
  4003.1  540.04  4041.0  540.22  4046.1  540.55  4093.7  540.63  4098.8  541.08
  4151.6  540.75  4176.0  540.86  4262.1  540.15  4348.9  538.94  4420.1  537.61
  4483.3  536.21  4588.8  533.36  4654.1  532.15  4827.0  529.78  4995.4  528.39
  4995.7  527.89  4999.2  527.89  4999.4  528.39  5547.1  539.61  5711.3  544.83
#Mann=3,-1,0
  3813.2    0.05       0  4995.4   0.035       0  4999.4    0.05       0
Bank Sta=4995.4,4999.4
Exp/Cntr=0.3,0.1

Type RM Length L Ch R = 1,638,558,558,558
BEGIN DESCRIPTION:
Mapping XS 165c5b16
END DESCRIPTION:
XS GIS Cut Line= 4
      2632978.98      7003595.89      2632879.15      7002272.11
      2632825.37      7002046.83      2632185.53      7001725.82
#Sta/Elev= 30
  3660.6  537.32  3755.8  536.49  3775.8  536.83  3805.9  536.63  3895.4  535.34
  3976.4  534.96  4066.6  535.22  4156.9  533.54  4257.2  533.93  4397.6  532.12
  4447.7  532.21  4568.8  531.15  4899.0  527.65  4963.9  526.32  5022.3  524.47
  5022.5  523.97  5026.0  523.97  5026.3  524.47  5040.7  525.54  5066.3  526.05
  5223.1  525.95  5535.9  528.79  5709.0  531.07  5803.9  531.44  5865.3  532.25
  5870.9  531.93  5910.0  532.64  5915.6  532.40  5932.3  532.77  5935.6  532.49
#Mann=3,-1,0
  3660.6    0.05       0  5022.3   0.035       0  5026.3    0.05       0
Bank Sta=5022.3,5026.3
Exp/Cntr=0.3,0.1

Type RM Length L Ch R = 1,80,0,0,0
BEGIN DESCRIPTION:
Berry Creek Trib 4 1.0
END DESCRIPTION:
XS GIS Cut Line= 5
      2632981.07      7004147.23      2633394.13      7002318.98
      2633369.58      7002167.48      2633250.72      7001864.54
      2632018.08      7001645.35
#Sta/Elev= 30
  2972.2  540.71  3015.9  540.69  3021.0  540.38  3150.6  539.59  3247.2  537.76
  3333.6  537.51  3748.0  532.45  3920.7  531.18  4108.9  528.90  4383.4  526.27
  4813.7  523.06  4862.9  522.88  4924.5  523.20  5017.7  522.82  5071.4  523.39
  5176.8  522.65  5177.1  522.15  5180.6  522.15  5180.8  522.65  5299.8  523.38
  5391.2  523.48  5429.0  523.50  5482.6  522.96  5553.7  523.87  5891.1  526.01
  6456.0  532.47  6461.1  532.28  6559.2  533.35  6569.0  533.39  6577.4  532.98
#Mann=3,-1,0
  2972.2    0.05       0  5176.8   0.035       0  5180.8    0.05       0
Bank Sta=5176.8,5180.8
Exp/Cntr=0.3,0.1

Chan Stop Cuts=-1