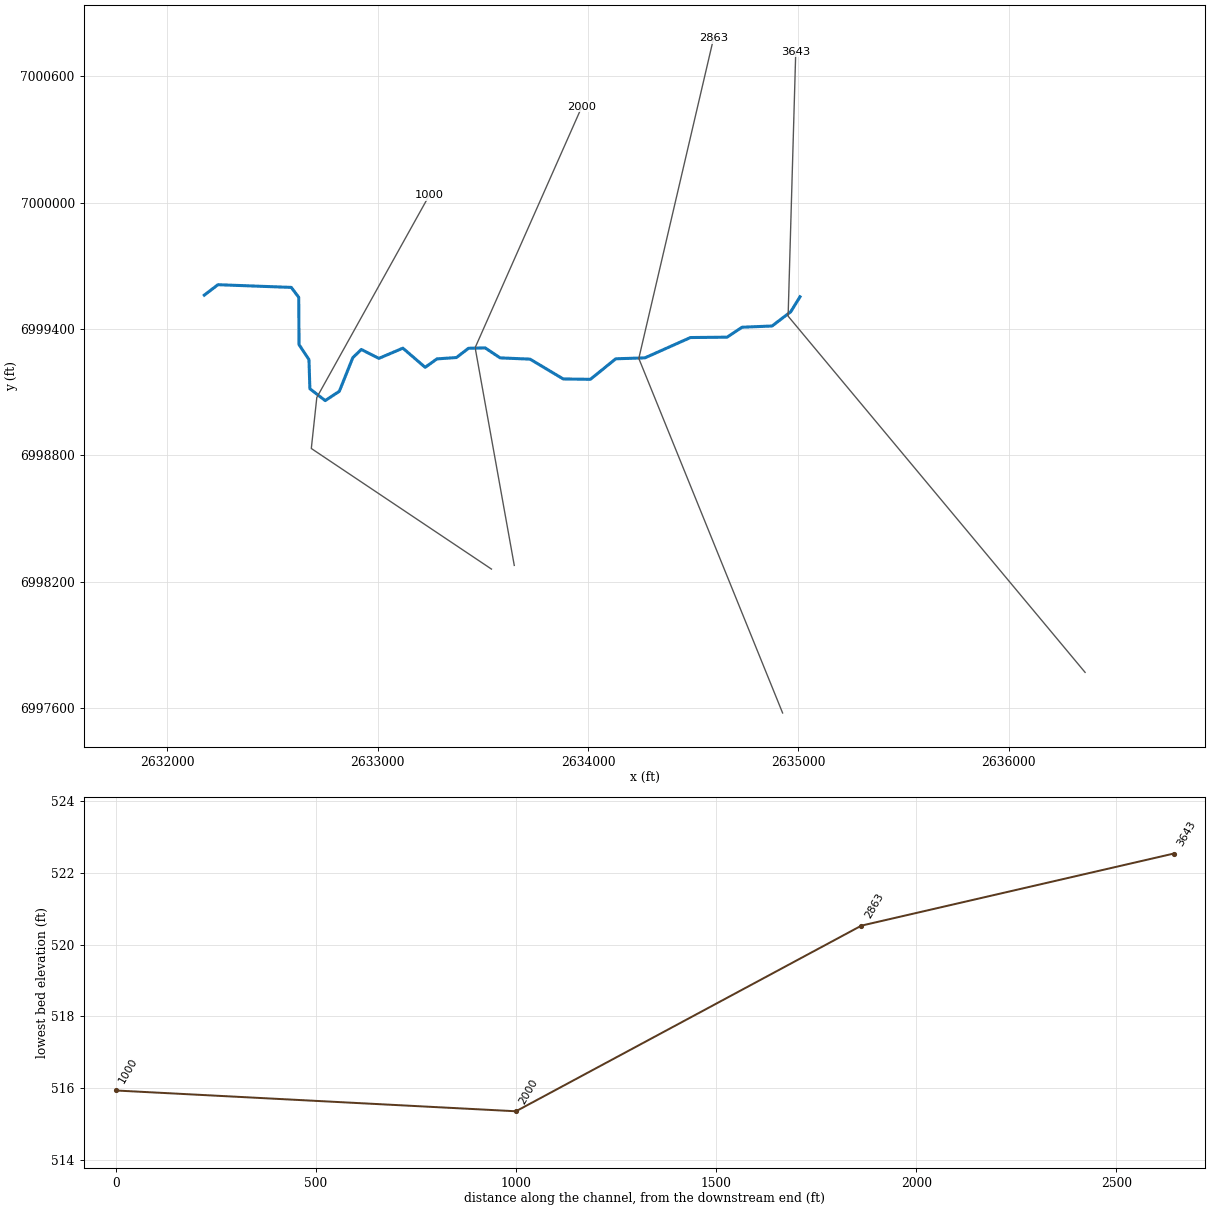
--- Berry Creek Trib 5.prj (project) ---

Proj Title=Berry Creek Trib 5 Base Level Engineering
Current Plan=p01
Default Exp/Contr=0.3,0.1
English Units
Geom File=g01
Flow File=f01
Plan File=p01
BEGIN DESCRIPTION:
Berry Creek Trib 5
END DESCRIPTION:

--- Berry Creek Trib 5.p01 (plan) ---

Plan Title=Multiple Run
Short Identifier=Multiple
Geom File=g01
Flow File=f01
Subcritical Flow
K Sum by GR= 0
Std Step Tol= 0.01
Critical Tol= 0.01
Num of Std Step Trials= 20
Max Error Tol= 0.3
Flow Tol Ratio= 0.001
Split Flow NTrial= 30
Split Flow Tol= 0.02
Split Flow Ratio= 0.02
Log Output Level= 0
Friction Slope Method= 1
Unsteady Friction Slope Method= 2
Unsteady Bridges Friction Slope Method= 1
Parabolic Critical Depth
Global Vel Dist=  1 , 1 , 1
Global Log Level= 0
CheckData=True
Encroach Param= -1, 0, 0, 0
BEGIN DESCRIPTION:
Multiple Run
END DESCRIPTION:

--- Berry Creek Trib 5.f01 (steady flow) ---

Flow Title=Multiple
Number of Profiles=7
Profile Names=10-year,25-year,50-year,1pct_min,100-year,1pct_plu,500-year
River Rch & RM= Berry Creek Trib,Reach-1,3643
     391     508     600     352     703    1403     962
Boundary for River Rch & Prof#=Berry Creek Trib,Reach-1,1
Up Type=0
Dn Type=3
Dn Slope=0.005
Boundary for River Rch & Prof#=Berry Creek Trib,Reach-1,2
Up Type=0
Dn Type=3
Dn Slope=0.005
Boundary for River Rch & Prof#=Berry Creek Trib,Reach-1,3
Up Type=0
Dn Type=3
Dn Slope=0.005
Boundary for River Rch & Prof#=Berry Creek Trib,Reach-1,4
Up Type=0
Dn Type=3
Dn Slope=0.005
Boundary for River Rch & Prof#=Berry Creek Trib,Reach-1,5
Up Type=0
Dn Type=3
Dn Slope=0.005
Boundary for River Rch & Prof#=Berry Creek Trib,Reach-1,6
Up Type=0
Dn Type=3
Dn Slope=0.005
Boundary for River Rch & Prof#=Berry Creek Trib,Reach-1,7
Up Type=0
Dn Type=3
Dn Slope=0.005

--- Berry Creek Trib 5.g01 (geometry) ---

Geom Title=Existing Conditions

River Reach=Berry Creek Trib,Reach-1
Reach XY= 30
      2635007.27      6999553.31      2634962.83      6999481.78
      2634874.50      6999414.61      2634731.94      6999408.73
      2634660.78      6999361.52      2634486.50      6999359.78
      2634270.06      6999263.27      2634131.86      6999258.92
      2634010.83      6999161.37      2633881.93      6999163.23
      2633724.44      6999257.24      2633581.94      6999263.27
      2633510.73      6999310.62      2633431.97      6999308.83
      2633374.40      6999264.86      2633281.89      6999258.44
      2633225.90      6999218.33      2633119.96      6999309.36
      2633005.79      6999260.81      2632922.34      6999303.28
      2632881.83      6999263.86      2632817.97      6999104.56
      2632750.99      6999060.33      2632677.99      6999116.62
      2632673.73      6999255.06      2632626.52      6999326.22
      2632625.02      6999550.74      2632589.74      6999597.81
      2632241.15      6999610.64      2632176.00      6999561.00

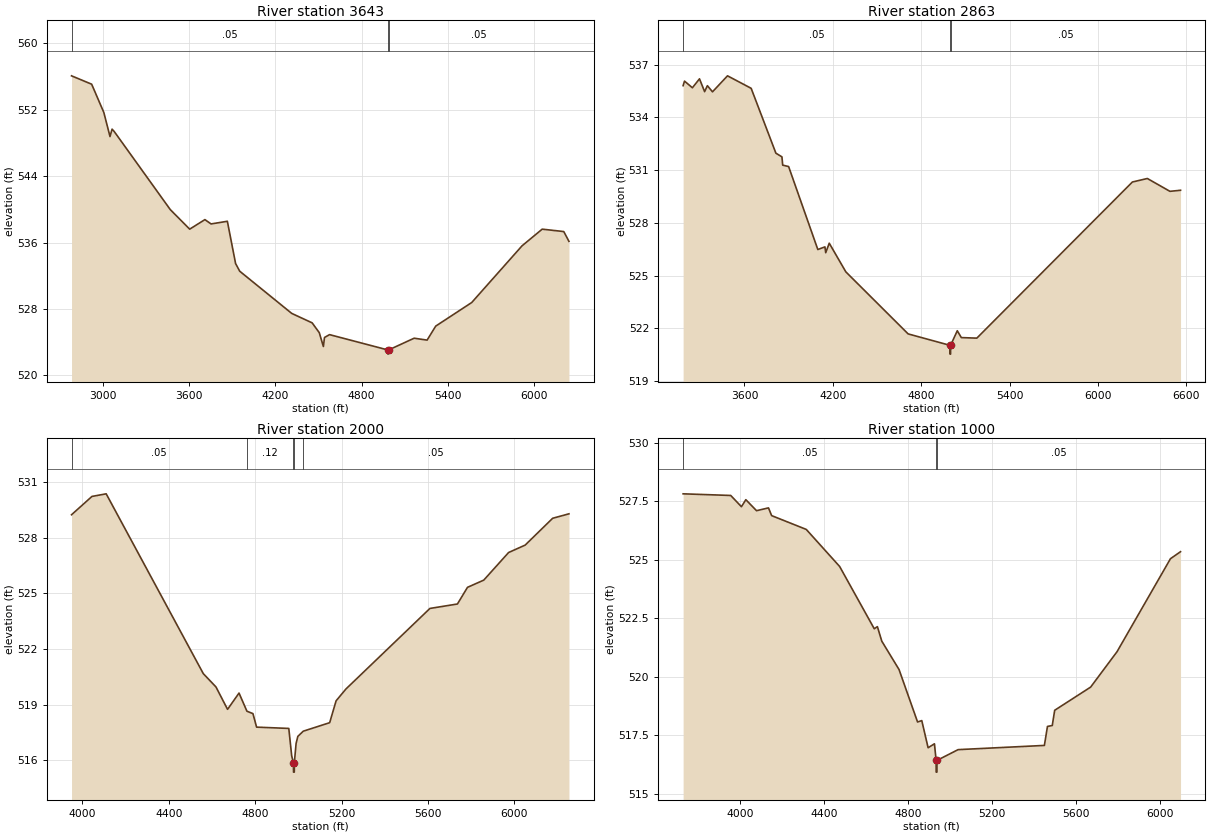
Type RM Length L Ch R = 1,3643,780,780,780
BEGIN DESCRIPTION:
Berry Creek Trib 5 7.0
END DESCRIPTION:
XS GIS Cut Line= 3
      2636362.01      6997770.09      2634950.69      6999461.27
      2634987.00      7000717.04
#Sta/Elev= 30
  2783.4  556.10  2923.4  555.09  3008.0  551.68  3050.9  548.78  3065.3  549.67
  3079.6  549.40  3470.0  539.97  3605.1  537.61  3710.8  538.76  3753.8  538.24
  3867.0  538.56  3924.3  533.46  3952.9  532.54  4314.7  527.45  4456.6  526.31
  4506.1  525.13  4534.7  523.46  4542.5  524.55  4577.7  524.89  4983.9  523.04
  4984.1  522.54  4987.9  523.04  5165.9  524.46  5256.0  524.23  5316.0  525.92
  5566.1  528.76  5916.2  535.60  6056.3  537.61  6206.3  537.32  6242.4  536.14
#Mann=3,-1,0
  2783.4    0.05       0  4983.9   0.035       0  4987.9    0.05       0
Bank Sta=4983.9,4987.9
Exp/Cntr=0.3,0.1

Type RM Length L Ch R = 1,2863,863,863,863
BEGIN DESCRIPTION:
Berry Creek Trib 5 6.0
END DESCRIPTION:
XS GIS Cut Line= 3
      2634924.53      6997577.34      2634241.16      6999260.61
      2634596.39      7000780.45
#Sta/Elev= 30
  3183.3  535.80  3192.7  536.06  3246.2  535.68  3294.4  536.19  3329.3  535.46
  3348.0  535.80  3382.8  535.45  3484.6  536.36  3645.3  535.65  3813.2  531.96
  3854.2  531.75  3859.5  531.28  3899.6  531.20  4097.9  526.48  4146.1  526.63
  4151.5  526.30  4175.5  526.84  4288.1  525.21  4711.2  521.68  4995.5  521.03
  4995.8  520.53  4999.3  520.53  4999.5  521.03  5044.9  521.86  5072.3  521.47
  5177.6  521.44  6233.7  530.32  6335.4  530.52  6488.8  529.79  6560.8  529.85
#Mann=3,-1,0
  3183.3    0.05       0  4995.5   0.035       0  4999.5    0.05       0
Bank Sta=4995.5,4999.5
Exp/Cntr=0.3,0.1

Type RM Length L Ch R = 1,2000,1000,1000,1000
BEGIN DESCRIPTION:
Berry Creek Trib 5 4.0
END DESCRIPTION:
XS GIS Cut Line= 3
      2633649.34      6998277.92      2633463.40      6999311.73
      2633970.87      7000456.38
#Sta/Elev= 30
  3949.6  529.25  4044.2  530.24  4110.0  530.38  4559.5  520.67  4618.2  519.95
  4671.8  518.74  4724.9  519.62  4761.5  518.64  4789.3  518.51  4806.2  517.78
  4955.3  517.71  4968.8  516.22  4976.9  515.85  4977.2  515.35  4980.7  515.35
  4980.9  515.85  4989.1  516.90  4997.1  517.28  5022.1  517.56  5144.5  518.02
  5174.2  519.20  5219.8  519.84  5608.6  524.19  5735.9  524.43  5782.5  525.33
  5857.8  525.72  5972.7  527.21  6049.3  527.61  6176.8  529.06  6252.1  529.30
#Mann=5,-1,0
  3949.6    0.05       0  4761.5    0.12       0  4976.9    0.07       0
  4980.9    0.12       0  5022.1    0.05       0
Bank Sta=4976.9,4980.9
Exp/Cntr=0.3,0.1

Type RM Length L Ch R = 1,1000,0,0,0
BEGIN DESCRIPTION:
Berry Creek Trib 5 2.0
END DESCRIPTION:
XS GIS Cut Line= 4
      2633540.87      6998260.51      2632684.82      6998833.08
      2632710.94      6999075.19      2633245.69      7000035.66
#Sta/Elev= 30
  3726.6  527.81  3953.7  527.74  4004.7  527.26  4025.7  527.56  4076.8  527.09
  4133.8  527.21  4148.8  526.88  4314.0  526.29  4473.1  524.71  4638.3  522.05
  4653.3  522.14  4674.3  521.52  4756.5  520.31  4844.9  518.07  4865.0  518.13
  4895.2  516.97  4925.4  517.14  4933.4  516.43  4933.7  515.93  4937.2  515.93
  4937.4  516.43  5038.2  516.89  5449.8  517.07  5464.5  517.88  5487.4  517.92
  5499.0  518.57  5670.5  519.56  5796.3  521.07  6051.2  525.04  6099.3  525.34
#Mann=3,-1,0
  3726.6    0.05       0  4933.4    0.03       0  4937.4    0.05       0
Bank Sta=4933.4,4937.4
Exp/Cntr=0.3,0.1

Chan Stop Cuts=-1