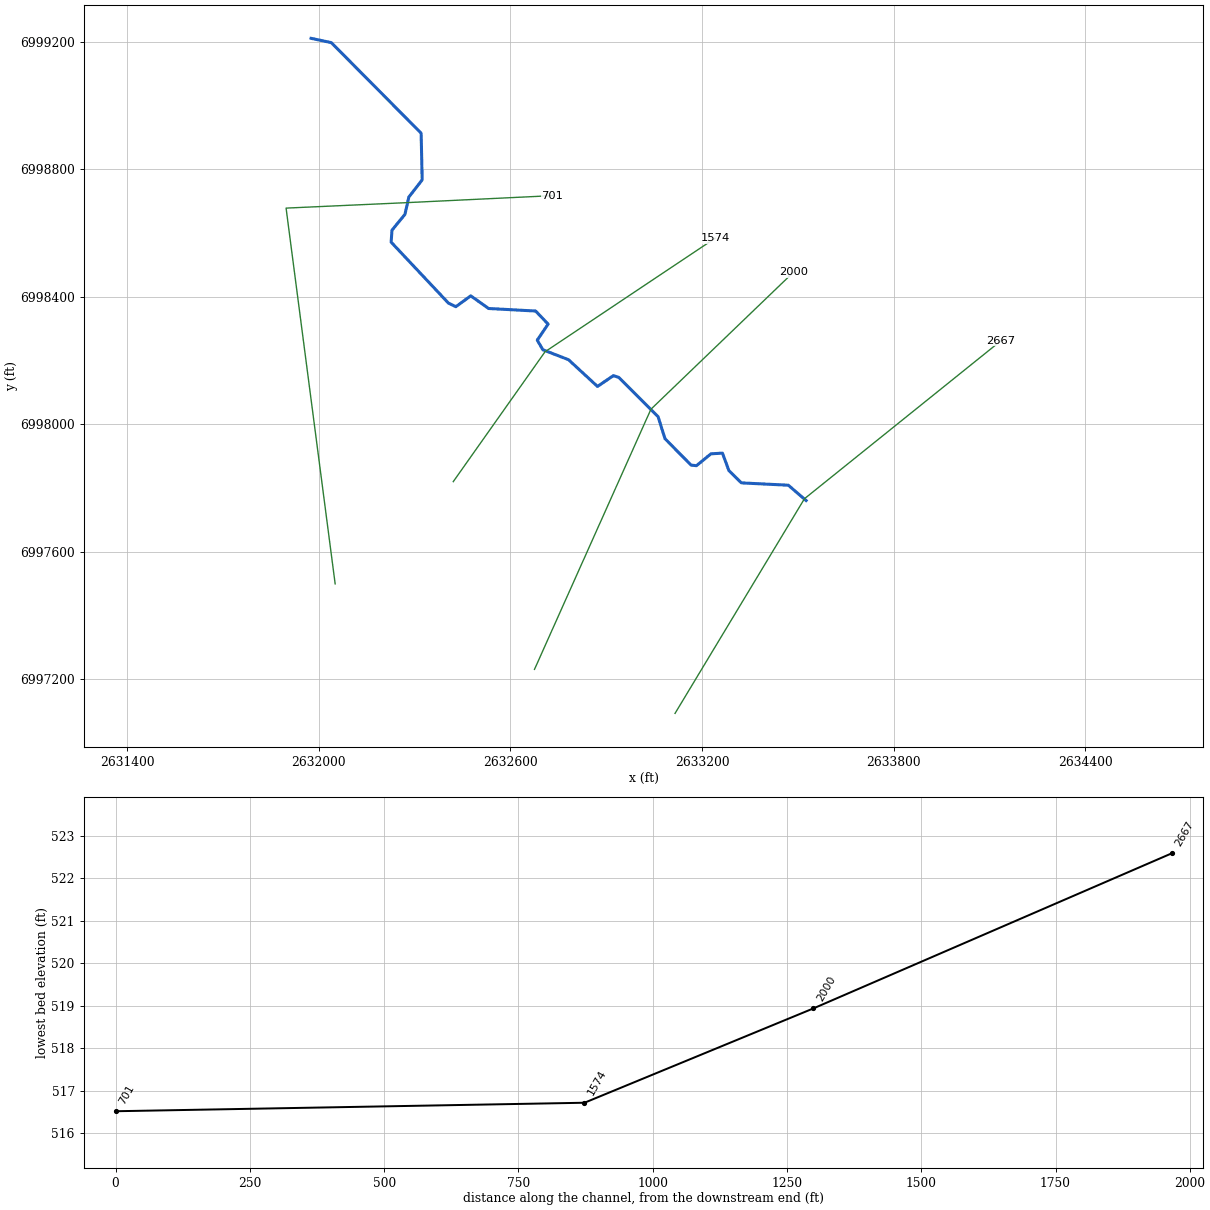
--- Berry Creek Trib 6.prj (project) ---

Proj Title=Berry Creek Trib 6 Base Level Engineering
Current Plan=p01
Default Exp/Contr=0.3,0.1
English Units
Geom File=g01
Flow File=f01
Plan File=p01
BEGIN DESCRIPTION:
Berry Creek Trib 6
END DESCRIPTION:

--- Berry Creek Trib 6.p01 (plan) ---

Plan Title=Multiple Run
Short Identifier=Multiple
Geom File=g01
Flow File=f01
Subcritical Flow
K Sum by GR= 0
Std Step Tol= 0.01
Critical Tol= 0.01
Num of Std Step Trials= 20
Max Error Tol= 0.3
Flow Tol Ratio= 0.001
Split Flow NTrial= 30
Split Flow Tol= 0.02
Split Flow Ratio= 0.02
Log Output Level= 0
Friction Slope Method= 1
Unsteady Friction Slope Method= 2
Unsteady Bridges Friction Slope Method= 1
Parabolic Critical Depth
Global Vel Dist=  1 , 1 , 1
Global Log Level= 0
CheckData=True
Encroach Param= -1, 0, 0, 0
BEGIN DESCRIPTION:
Multiple Run
END DESCRIPTION:

--- Berry Creek Trib 6.f01 (steady flow) ---

Flow Title=Multiple
Number of Profiles=7
Profile Names=10-year,25-year,50-year,1pct_min,100-year,1pct_plu,500-year
River Rch & RM= Berry Creek Trib,Reach-1,2667
     194     241     275     157     313     624     402
Boundary for River Rch & Prof#=Berry Creek Trib,Reach-1,1
Up Type=0
Dn Type=3
Dn Slope=0.005
Boundary for River Rch & Prof#=Berry Creek Trib,Reach-1,2
Up Type=0
Dn Type=3
Dn Slope=0.005
Boundary for River Rch & Prof#=Berry Creek Trib,Reach-1,3
Up Type=0
Dn Type=3
Dn Slope=0.005
Boundary for River Rch & Prof#=Berry Creek Trib,Reach-1,4
Up Type=0
Dn Type=3
Dn Slope=0.005
Boundary for River Rch & Prof#=Berry Creek Trib,Reach-1,5
Up Type=0
Dn Type=3
Dn Slope=0.005
Boundary for River Rch & Prof#=Berry Creek Trib,Reach-1,6
Up Type=0
Dn Type=3
Dn Slope=0.005
Boundary for River Rch & Prof#=Berry Creek Trib,Reach-1,7
Up Type=0
Dn Type=3
Dn Slope=0.005

--- Berry Creek Trib 6.g01 (geometry) ---

Geom Title=Existing Conditions

River Reach=Berry Creek Trib,Reach-1
Reach XY= 30
      2633526.00      6997761.00      2633470.21      6997809.09
      2633323.32      6997816.40      2633284.15      6997855.02
      2633263.96      6997909.76      2633228.01      6997907.56
      2633182.59      6997870.35      2633165.94      6997872.11
      2633084.16      6997954.91      2633062.37      6998024.21
      2632939.33      6998147.35      2632922.67      6998152.84
      2632872.67      6998119.02      2632782.01      6998202.80
      2632701.64      6998234.02      2632684.09      6998264.17
      2632718.11      6998314.61      2632678.99      6998355.53
      2632531.86      6998363.46      2632475.90      6998403.19
      2632429.33      6998369.14      2632406.00      6998380.37
      2632226.59      6998571.62      2632229.31      6998609.26
      2632269.84      6998658.80      2632282.11      6998713.18
      2632323.77      6998766.93      2632320.55      6998913.45
      2632039.27      6999197.53      2631976.00      6999211.00

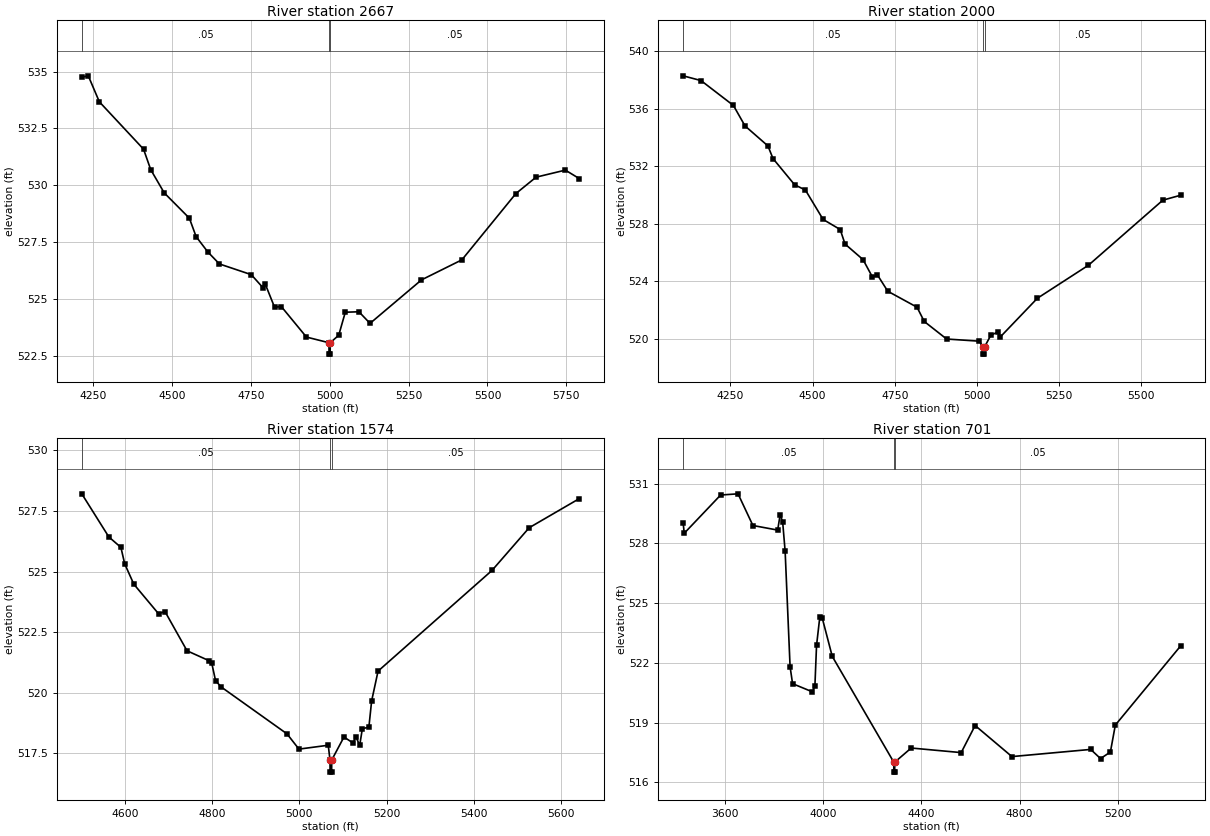
Type RM Length L Ch R = 1,2667,667,667,667
BEGIN DESCRIPTION:
Berry Creek Trib 6 5.0
END DESCRIPTION:
XS GIS Cut Line= 3
      2633115.57      6997093.32      2633520.63      6997766.55
      2634136.39      6998262.59
#Sta/Elev= 30
  4214.3  534.75  4234.9  534.81  4269.9  533.67  4410.0  531.59  4432.8  530.69
  4475.6  529.67  4555.2  528.56  4576.6  527.75  4613.5  527.08  4650.4  526.55
  4751.4  526.08  4788.3  525.51  4795.1  525.69  4825.2  524.65  4846.6  524.68
  4926.2  523.34  4997.7  523.09  4997.9  522.59  5001.4  522.59  5001.7  523.09
  5028.6  523.42  5049.4  524.43  5092.6  524.45  5127.8  523.94  5290.9  525.85
  5418.9  526.73  5590.0  529.64  5654.0  530.36  5746.8  530.67  5790.7  530.30
#Mann=3,-1,0
  4214.3    0.05       0  4997.7    0.04       0  5001.7    0.05       0
Bank Sta=4997.7,5001.7
Exp/Cntr=0.3,0.1

Type RM Length L Ch R = 1,2000,426,426,426
BEGIN DESCRIPTION:
Berry Creek Trib 6 4.0
END DESCRIPTION:
XS GIS Cut Line= 3
      2632675.47      6997231.35      2633040.02      6998047.42
      2633485.97      6998477.00
#Sta/Elev= 30
  4106.2  538.28  4160.6  537.95  4259.2  536.22  4294.4  534.80  4364.1  533.41
  4379.6  532.53  4445.3  530.71  4478.2  530.34  4532.0  528.30  4583.9  527.60
  4598.7  526.59  4653.4  525.51  4682.2  524.29  4697.3  524.44  4728.7  523.31
  4817.7  522.20  4839.6  521.21  4907.6  519.99  5006.9  519.84  5019.0  519.44
  5019.3  518.94  5022.8  518.94  5023.0  519.44  5042.1  520.25  5063.5  520.48
  5070.4  520.12  5183.6  522.82  5339.2  525.12  5565.4  529.64  5619.2  529.98
#Mann=3,-1,0
  4106.2    0.05       0  5019.0    0.04       0  5023.0    0.05       0
Bank Sta=5019,5023
Exp/Cntr=0.3,0.1

Type RM Length L Ch R = 1,1574,873,873,873
BEGIN DESCRIPTION:
Berry Creek Trib 6 3.0
END DESCRIPTION:
XS GIS Cut Line= 3
      2632421.12      6997820.31      2632708.47      6998227.65
      2633241.24      6998584.08
#Sta/Elev= 30
  4501.5  528.21  4563.5  526.43  4591.1  526.00  4599.8  525.32  4620.7  524.48
  4677.3  523.26  4692.1  523.35  4742.6  521.73  4793.1  521.32  4799.2  521.22
  4807.9  520.50  4820.5  520.24  4971.6  518.30  4999.0  517.67  5066.1  517.83
  5070.1  517.22  5070.3  516.72  5073.8  516.72  5074.1  517.22  5102.1  518.17
  5123.1  517.92  5129.4  518.19  5138.1  517.82  5144.2  518.51  5159.2  518.58
  5165.5  519.66  5180.2  520.89  5441.4  525.05  5526.4  526.81  5641.0  528.01
#Mann=3,-1,0
  4501.5    0.05       0  5070.1    0.04       0  5074.1    0.05       0
Bank Sta=5070.1,5074.1
Exp/Cntr=0.3,0.1

Type RM Length L Ch R = 1,701,0,0,0
BEGIN DESCRIPTION:
Berry Creek Trib 6 2.0
END DESCRIPTION:
XS GIS Cut Line= 4
      2632051.33      6997499.62      2631897.69      6998678.40
      2632276.95      6998695.60      2632731.02      6998717.46
#Sta/Elev= 30
  3431.6  529.04  3436.1  528.51  3584.1  530.43  3654.9  530.49  3715.4  528.90
  3816.1  528.67  3826.3  529.45  3836.4  529.08  3846.5  527.60  3866.6  521.81
  3876.7  520.96  3957.4  520.55  3967.5  520.84  3974.2  522.88  3987.6  524.32
  3997.7  524.24  4038.1  522.33  4288.3  517.02  4288.5  516.52  4292.0  516.52
  4292.3  517.02  4359.2  517.73  4562.5  517.50  4619.1  518.86  4768.8  517.30
  5089.2  517.66  5129.2  517.20  5169.3  517.53  5189.3  518.88  5454.6  522.85
#Mann=3,-1,0
  3431.6    0.05       0  4288.3    0.03       0  4292.3    0.05       0
Bank Sta=4288.3,4292.3
Exp/Cntr=0.3,0.1

Chan Stop Cuts=-1