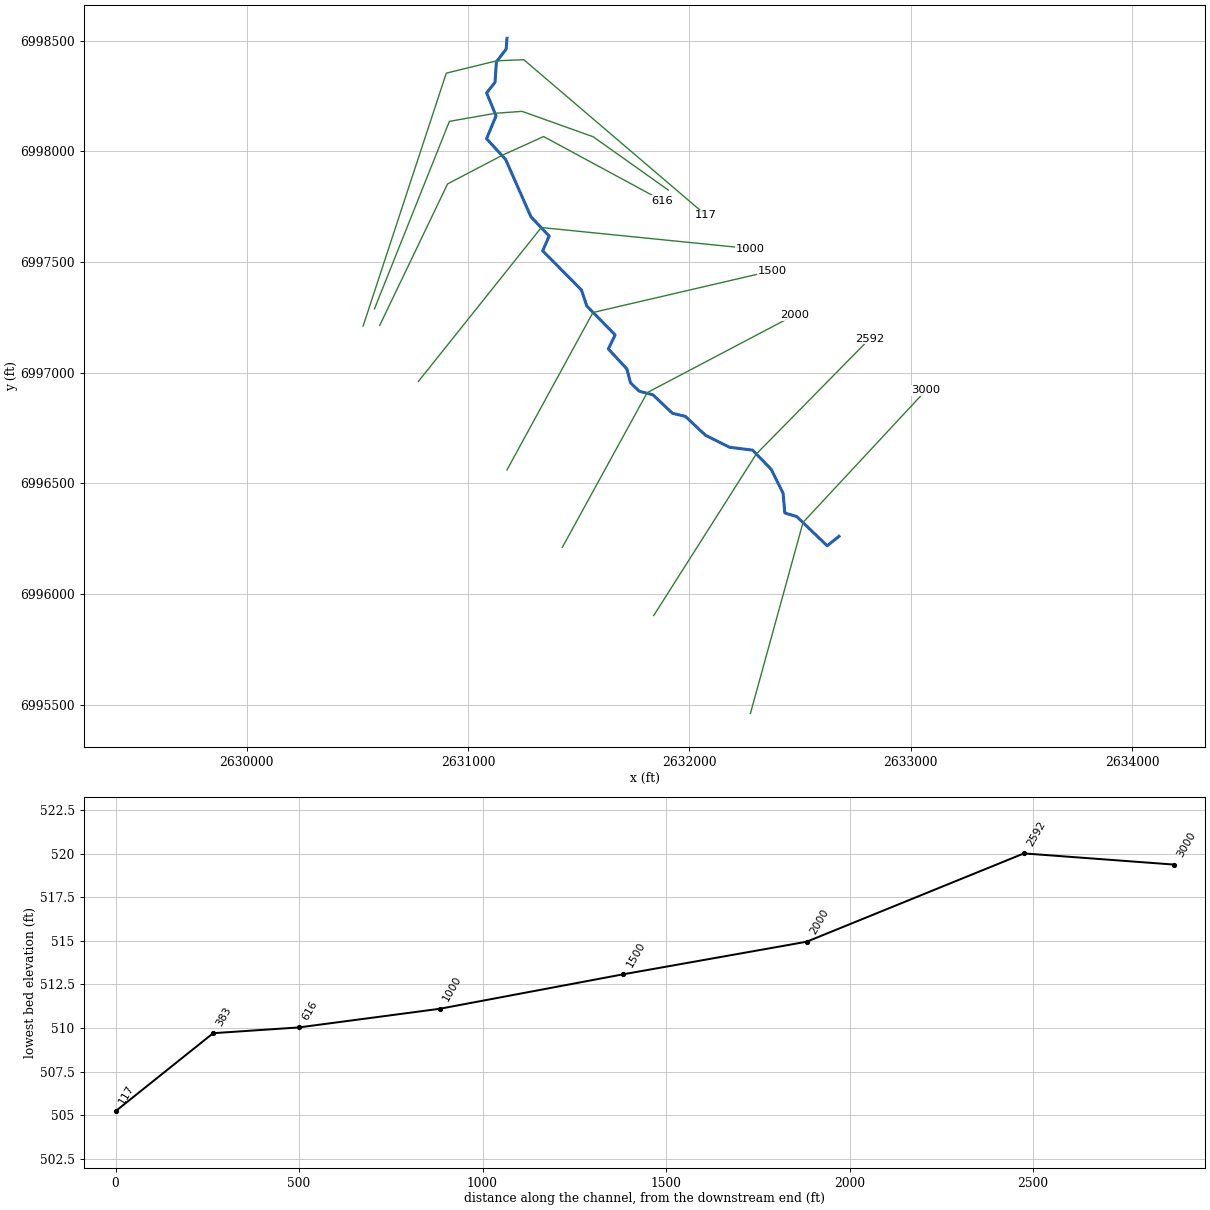
--- Berry Creek Trib 7.prj (project) ---

Proj Title=Berry Creek Trib 7 Base Level Engineering
Current Plan=p01
Default Exp/Contr=0.3,0.1
English Units
Geom File=g01
Flow File=f01
Plan File=p01
BEGIN DESCRIPTION:
Berry Creek Trib 7
END DESCRIPTION:

--- Berry Creek Trib 7.p01 (plan) ---

Plan Title=Multiple Run
Short Identifier=Multiple
Geom File=g01
Flow File=f01
Subcritical Flow
K Sum by GR= 0
Std Step Tol= 0.01
Critical Tol= 0.01
Num of Std Step Trials= 20
Max Error Tol= 0.3
Flow Tol Ratio= 0.001
Split Flow NTrial= 30
Split Flow Tol= 0.02
Split Flow Ratio= 0.02
Log Output Level= 0
Friction Slope Method= 1
Unsteady Friction Slope Method= 2
Unsteady Bridges Friction Slope Method= 1
Parabolic Critical Depth
Global Vel Dist=  1 , 1 , 1
Global Log Level= 0
CheckData=True
Encroach Param= -1, 0, 0, 0
BEGIN DESCRIPTION:
Multiple Run
END DESCRIPTION:

--- Berry Creek Trib 7.f01 (steady flow) ---

Flow Title=Multiple
Number of Profiles=7
Profile Names=10-year,25-year,50-year,1pct_min,100-year,1pct_plu,500-year
River Rch & RM= Berry Creek Trib,Reach-1,3000
     271     344     399     230     460     917     609
Boundary for River Rch & Prof#=Berry Creek Trib,Reach-1,1
Up Type=0
Dn Type=3
Dn Slope=0.005
Boundary for River Rch & Prof#=Berry Creek Trib,Reach-1,2
Up Type=0
Dn Type=3
Dn Slope=0.005
Boundary for River Rch & Prof#=Berry Creek Trib,Reach-1,3
Up Type=0
Dn Type=3
Dn Slope=0.005
Boundary for River Rch & Prof#=Berry Creek Trib,Reach-1,4
Up Type=0
Dn Type=3
Dn Slope=0.005
Boundary for River Rch & Prof#=Berry Creek Trib,Reach-1,5
Up Type=0
Dn Type=3
Dn Slope=0.005
Boundary for River Rch & Prof#=Berry Creek Trib,Reach-1,6
Up Type=0
Dn Type=3
Dn Slope=0.005
Boundary for River Rch & Prof#=Berry Creek Trib,Reach-1,7
Up Type=0
Dn Type=3
Dn Slope=0.005

--- Berry Creek Trib 7.g01 (geometry) ---

Geom Title=Existing Conditions

River Reach=Berry Creek Trib,Reach-1
Reach XY= 30
      2632676.00      6996261.00      2632622.67      6996218.25
      2632485.38      6996350.10      2632431.26      6996366.47
      2632423.63      6996454.95      2632370.18      6996563.31
      2632285.81      6996650.49      2632181.97      6996663.33
      2632073.71      6996716.84      2631982.04      6996802.82
      2631923.72      6996816.87      2631835.65      6996900.19
      2631773.46      6996916.75      2631734.04      6996954.67
      2631717.80      6997017.03      2631634.02      6997107.67
      2631664.76      6997171.00      2631536.78      6997301.32
      2631512.37      6997374.21      2631337.24      6997551.00
      2631366.68      6997617.66      2631284.18      6997704.94
      2631170.14      6997963.30      2631083.81      6998057.59
      2631126.75      6998161.00      2631084.08      6998264.30
      2631121.91      6998312.50      2631128.22      6998405.08
      2631172.36      6998462.51      2631176.00      6998511.00

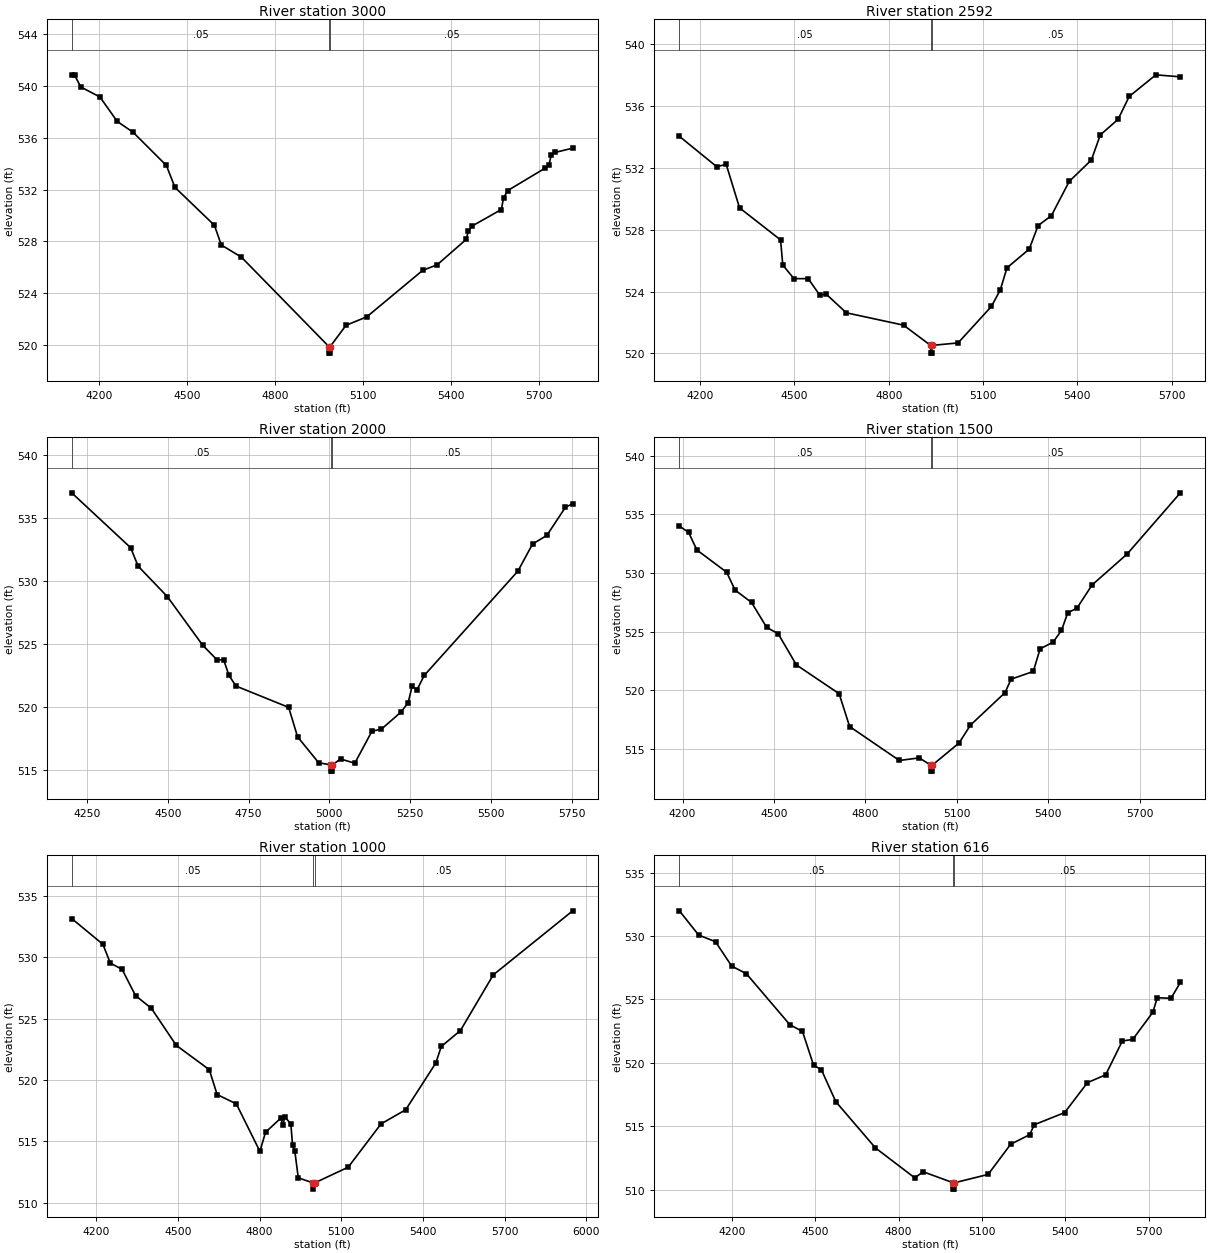
Type RM Length L Ch R = 1,3000,408,408,408
BEGIN DESCRIPTION:
Berry Creek Trib 7 6.0
END DESCRIPTION:
XS GIS Cut Line= 3
      2632276.01      6995461.03      2632513.61      6996323.71
      2633069.64      6996921.48
#Sta/Elev= 30
  4105.2  540.87  4115.5  540.82  4136.3  539.93  4201.5  539.16  4260.8  537.27
  4315.1  536.43  4428.6  533.87  4457.8  532.18  4592.7  529.25  4616.1  527.73
  4684.9  526.79  4983.9  519.88  4984.2  519.38  4987.7  519.38  4987.9  519.88
  5042.2  521.53  5113.0  522.18  5304.0  525.77  5353.4  526.20  5452.6  528.16
  5459.9  528.82  5474.1  529.21  5572.8  530.47  5580.1  531.36  5594.3  531.93
  5721.3  533.65  5735.5  533.91  5742.8  534.66  5757.0  534.88  5816.4  535.21
#Mann=3,-1,0
  4105.2    0.05       0  4983.9    0.04       0  4987.9    0.05       0
Bank Sta=4983.9,4987.9
Exp/Cntr=0.3,0.1

Type RM Length L Ch R = 1,2592,592,592,592
BEGIN DESCRIPTION:
Mapping XS de8763fd
END DESCRIPTION:
XS GIS Cut Line= 3
      2631839.15      6995903.26      2632302.06      6996632.34
      2632814.15      6997153.12
#Sta/Elev= 30
  4134.0  534.05  4252.5  532.09  4283.0  532.23  4325.4  529.42  4455.8  527.35
  4463.0  525.72  4498.5  524.84  4543.9  524.84  4580.4  523.78  4601.5  523.83
  4665.1  522.63  4847.2  521.83  4933.3  520.52  4933.5  520.02  4937.0  520.02
  4937.3  520.52  5020.7  520.68  5126.7  523.04  5155.0  524.11  5176.3  525.54
  5247.0  526.75  5275.3  528.27  5317.7  528.92  5374.3  531.13  5444.9  532.52
  5473.2  534.14  5529.8  535.15  5565.2  536.63  5650.0  538.03  5728.0  537.90
#Mann=3,-1,0
  4134.0    0.05       0  4933.3    0.04       0  4937.3    0.05       0
Bank Sta=4933.3,4937.3
Exp/Cntr=0.3,0.1

Type RM Length L Ch R = 1,2000,500,500,500
BEGIN DESCRIPTION:
Berry Creek Trib 7 4.0
END DESCRIPTION:
XS GIS Cut Line= 3
      2631425.98      6996210.96      2631809.46      6996910.21
      2632475.99      6997260.99
#Sta/Elev= 30
  4202.5  537.00  4385.0  532.65  4407.8  531.20  4498.7  528.77  4607.8  524.93
  4651.4  523.79  4673.2  523.74  4689.3  522.53  4711.1  521.69  4874.1  520.00
  4901.6  517.67  4967.0  515.61  5005.1  515.45  5005.3  514.95  5008.8  514.95
  5009.1  515.45  5034.8  515.91  5078.8  515.58  5131.7  518.11  5161.3  518.28
  5221.8  519.63  5243.8  520.37  5256.0  521.66  5271.5  521.40  5293.6  522.53
  5583.7  530.80  5628.9  532.94  5673.3  533.63  5730.6  535.85  5753.2  536.14
#Mann=3,-1,0
  4202.5    0.05       0  5005.1    0.03       0  5009.1    0.05       0
Bank Sta=5005.1,5009.1
Exp/Cntr=0.3,0.1

Type RM Length L Ch R = 1,1500,500,500,500
BEGIN DESCRIPTION:
Berry Creek Trib 7 3.0
END DESCRIPTION:
XS GIS Cut Line= 3
      2631176.02      6996561.04      2631564.35      6997272.22
      2632375.99      6997461.00
#Sta/Elev= 30
  4189.7  533.99  4219.6  533.48  4247.1  531.96  4344.8  530.06  4372.3  528.54
  4426.4  527.48  4475.8  525.36  4513.7  524.81  4573.5  522.15  4713.8  519.69
  4748.1  516.89  4911.3  513.99  4976.8  514.21  5014.9  513.58  5015.1  513.08
  5018.6  513.08  5018.9  513.58  5107.2  515.48  5144.7  517.01  5258.4  519.79
  5277.7  520.93  5350.8  521.59  5373.1  523.52  5415.7  524.09  5443.2  525.09
  5463.7  526.59  5494.5  527.01  5543.5  528.97  5658.8  531.62  5833.3  536.84
#Mann=3,-1,0
  4189.7    0.05       0  5014.9    0.03       0  5018.9    0.05       0
Bank Sta=5014.9,5018.9
Exp/Cntr=0.3,0.1

Type RM Length L Ch R = 1,1000,384,384,384
BEGIN DESCRIPTION:
Berry Creek Trib 7 2.0
END DESCRIPTION:
XS GIS Cut Line= 3
      2630776.02      6996961.02      2631331.13      6997656.18
      2632276.05      6997561.00
#Sta/Elev= 30
  4110.4  533.16  4224.9  531.06  4252.1  529.53  4295.3  529.02  4344.9  526.87
  4402.6  525.85  4494.3  522.82  4615.5  520.84  4644.3  518.81  4714.8  518.05
  4801.3  514.18  4822.1  515.74  4878.2  516.89  4886.1  516.29  4892.5  517.01
  4914.9  516.41  4921.3  514.67  4929.3  514.24  4942.2  512.02  4997.8  511.60
  4998.0  511.10  5001.8  511.60  5125.5  512.89  5246.1  516.42  5336.6  517.57
  5447.1  521.38  5467.2  522.73  5537.6  524.03  5658.2  528.57  5949.7  533.79
#Mann=3,-1,0
  4110.4    0.05       0  4997.8    0.03       0  5001.8    0.05       0
Bank Sta=4997.8,5001.8
Exp/Cntr=0.3,0.1

Type RM Length L Ch R = 1,616,233,233,233
BEGIN DESCRIPTION:
Mapping XS 3eb6fc89
END DESCRIPTION:
XS GIS Cut Line= 5
      2630600.93      6997213.87      2630907.59      6997853.22
      2631156.39      6997983.41      2631341.55      6998067.31
      2631876.79      6997777.99
#Sta/Elev= 30
  4012.0  531.99  4081.2  530.08  4141.9  529.55  4200.0  527.63  4252.8  527.03
  4409.4  523.00  4454.7  522.47  4494.5  519.81  4522.7  519.45  4574.5  516.93
  4717.1  513.28  4858.4  510.92  4888.6  511.40  4996.9  510.53  4997.1  510.03
  5000.6  510.03  5000.9  510.53  5122.2  511.19  5203.3  513.57  5271.9  514.33
  5288.1  515.11  5397.5  516.07  5479.3  518.43  5545.0  519.05  5604.9  521.72
  5642.2  521.84  5714.4  523.98  5730.6  525.13  5780.0  525.09  5813.6  526.34
#Mann=3,-1,0
  4012.0    0.05       0  4996.9    0.03       0  5000.9    0.05       0
Bank Sta=4996.9,5000.9
Exp/Cntr=0.3,0.1

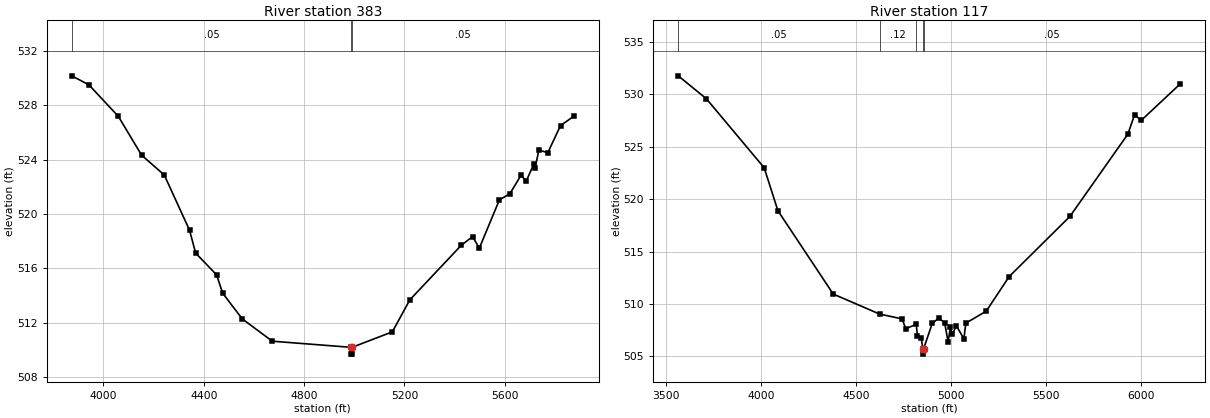
Type RM Length L Ch R = 1,383,266,266,266
BEGIN DESCRIPTION:
Mapping XS 1baa392d
END DESCRIPTION:
XS GIS Cut Line= 6
      2630577.29      6997288.66      2630915.85      6998135.93
      2631124.18      6998172.38      2631243.97      6998181.06
      2631565.15      6998066.48      2631904.88      6997825.55
#Sta/Elev= 30
  3873.6  530.16  3941.8  529.50  4059.2  527.18  4151.9  524.33  4242.3  522.87
  4343.1  518.81  4367.4  517.13  4450.9  515.53  4475.1  514.18  4553.3  512.29
  4673.0  510.65  4987.2  510.20  4987.4  509.70  4990.9  509.70  4991.2  510.20
  5151.6  511.34  5221.3  513.69  5426.3  517.70  5471.3  518.34  5498.3  517.49
  5578.3  521.04  5620.1  521.49  5664.4  522.85  5685.3  522.42  5714.9  523.65
  5721.0  523.42  5735.8  524.70  5771.4  524.51  5821.9  526.50  5875.1  527.19
#Mann=3,-1,0
  3873.6    0.05       0  4987.2    0.03       0  4991.2    0.05       0
Bank Sta=4987.2,4991.2
Exp/Cntr=0.3,0.1

Type RM Length L Ch R = 1,117,0,0,0
BEGIN DESCRIPTION:
Berry Creek Trib 7 1.0
END DESCRIPTION:
XS GIS Cut Line= 5
      2630526.01      6997211.03      2630901.80      6998353.72
      2631129.68      6998409.47      2631251.87      6998414.48
      2632075.98      6997711.02
#Sta/Elev= 30
  3562.5  531.76  3710.8  529.57  4015.1  522.99  4087.1  518.90  4378.5  510.95
  4622.5  509.04  4741.5  508.58  4760.0  507.64  4815.5  508.06  4821.7  506.97
  4841.8  506.78  4850.1  505.72  4850.3  505.22  4854.1  505.72  4899.8  508.15
  4934.4  508.66  4965.3  508.20  4983.1  506.40  4995.5  507.78  5006.3  507.10
  5026.3  507.94  5066.4  506.68  5076.4  508.17  5184.2  509.32  5305.0  512.62
  5624.5  518.35  5929.7  526.20  5964.8  528.04  6000.0  527.51  6205.8  531.00
#Mann=5,-1,0
  3562.5    0.05       0  4622.5    0.12       0  4815.5    0.05       0
  4850.1    0.03       0  4854.1    0.05       0
Bank Sta=4850.1,4854.1
Exp/Cntr=0.3,0.1

Chan Stop Cuts=-1