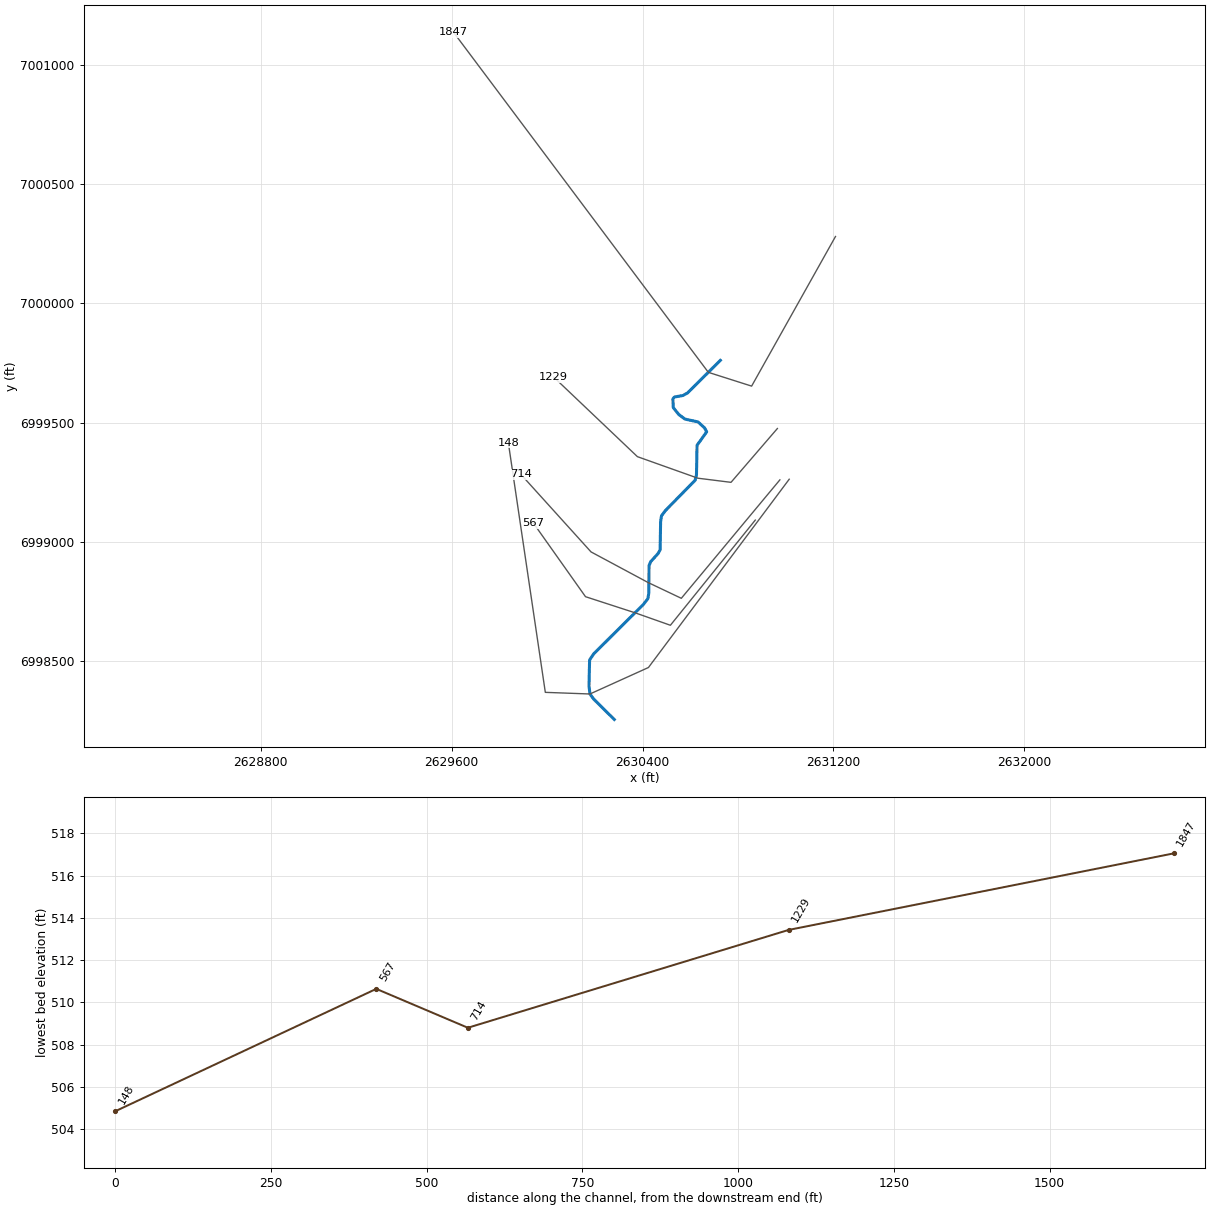
--- Berry Creek Trib 8.prj (project) ---

Proj Title=Berry Creek Trib 8 Base Level Engineering
Current Plan=p01
Default Exp/Contr=0.3,0.1
English Units
Geom File=g01
Flow File=f01
Plan File=p01
Y Axis Title=Elevation
X Axis Title(PF)=Main Channel Distance
X Axis Title(XS)=Station
BEGIN DESCRIPTION:
Berry Creek Trib 8
END DESCRIPTION:
DSS Export Rating Curves= 0
DSS Export Rating Curve Sorted= 0
DSS Export Volume Flow Curves= 0
DXF OffsetX= 0
DXF OffsetY= 0
DXF ScaleX= 1
DXF ScaleY= 10

--- Berry Creek Trib 8.p01 (plan) ---

Plan Title=Multiple Run
Short Identifier=Multiple
Geom File=g01
Flow File=f01
Subcritical Flow
K Sum by GR= 0
Std Step Tol= 0.01
Critical Tol= 0.01
Num of Std Step Trials= 20
Max Error Tol= 0.3
Flow Tol Ratio= 0.001
Split Flow NTrial= 30
Split Flow Tol= 0.02
Split Flow Ratio= 0.02
Log Output Level= 0
Friction Slope Method= 1
Unsteady Friction Slope Method= 2
Unsteady Bridges Friction Slope Method= 1
Parabolic Critical Depth
Global Vel Dist=  1 , 1 , 1
Global Log Level= 0
CheckData=True
Encroach Param= -1, 0, 0, 0
BEGIN DESCRIPTION:
Multiple Run
END DESCRIPTION:

--- Berry Creek Trib 8.f01 (steady flow) ---

Flow Title=Multiple
Program Version=4.10
Number of Profiles= 7
Profile Names=10-year,25-year,50-year,1pct_min,100-year,1pct_plu,500-year
River Rch & RM=Berry Creek Trib,Reach-1         ,1847
     214     267     307     176     352     702     459
Boundary for River Rch & Prof#=Berry Creek Trib,Reach-1         , 1
Up Type= 0
Dn Type= 3
Dn Slope=0.01382
Boundary for River Rch & Prof#=Berry Creek Trib,Reach-1         , 2
Up Type= 0
Dn Type= 3
Dn Slope=0.01382
Boundary for River Rch & Prof#=Berry Creek Trib,Reach-1         , 3
Up Type= 0
Dn Type= 3
Dn Slope=0.01382
Boundary for River Rch & Prof#=Berry Creek Trib,Reach-1         , 4
Up Type= 0
Dn Type= 3
Dn Slope=0.01382
Boundary for River Rch & Prof#=Berry Creek Trib,Reach-1         , 5
Up Type= 0
Dn Type= 3
Dn Slope=0.01382
Boundary for River Rch & Prof#=Berry Creek Trib,Reach-1         , 6
Up Type= 0
Dn Type= 3
Dn Slope=0.01382
Boundary for River Rch & Prof#=Berry Creek Trib,Reach-1         , 7
Up Type= 0
Dn Type= 3
Dn Slope=0.01382
DSS Import GetInterval= 0
DSS Import GetPeak= 0
DSS Import FillOption= 0

--- Berry Creek Trib 8.g01 (geometry) ---

Geom Title=Existing Conditions

River Reach=Berry Creek Trib,Reach-1
Reach XY= 30
      2630726.00      6999761.00      2630588.91      6999624.72
      2630569.37      6999613.69      2630533.70      6999607.43
      2630527.11      6999598.92      2630528.86      6999562.79
      2630551.87      6999533.98      2630577.42      6999514.92
      2630632.67      6999502.84      2630659.86      6999478.08
      2630668.77      6999461.31      2630628.48      6999405.15
      2630626.02      6999280.99      2630620.53      6999258.55
      2630495.61      6999131.16      2630479.54      6999109.53
      2630475.73      6999086.11      2630473.73      6998966.94
      2630465.14      6998951.35      2630434.15      6998917.05
      2630427.23      6998900.49      2630426.27      6998785.89
      2630422.46      6998762.47      2630403.14      6998737.47
      2630195.60      6998531.16      2630178.05      6998505.14
      2630175.47      6998395.81      2630179.48      6998362.45
      2630195.49      6998340.79      2630281.62      6998255.44

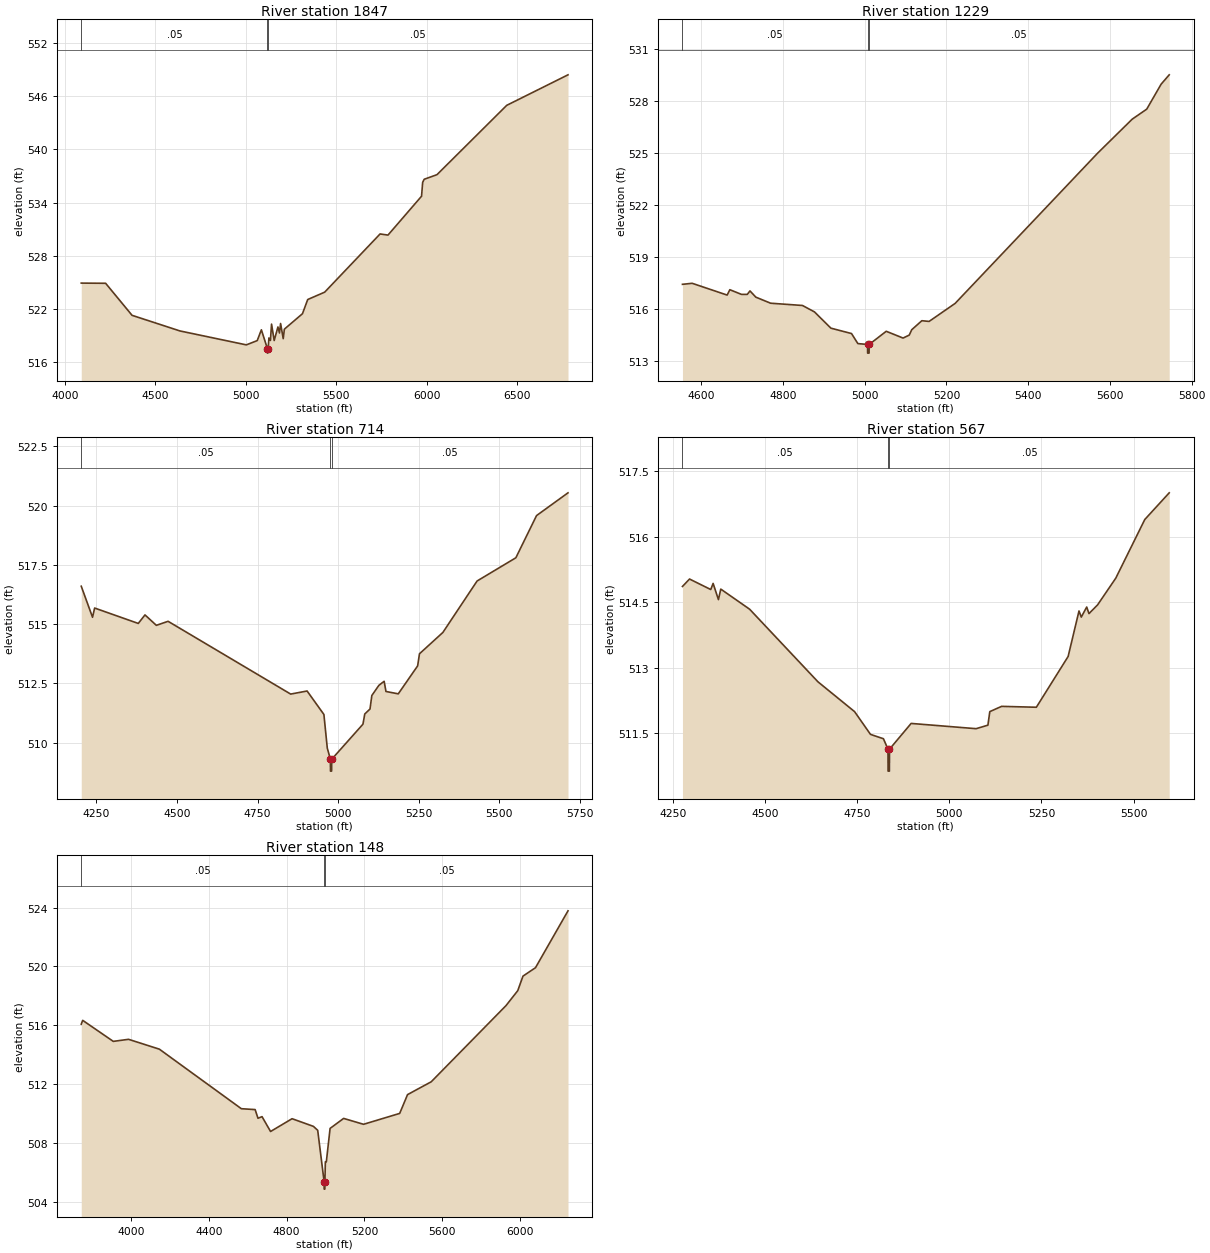
Type RM Length L Ch R = 1,1847,618,618,618
BEGIN DESCRIPTION:
Berry Creek Trib 8 3.0
END DESCRIPTION:
XS GIS Cut Line= 4
      2631208.81      7000280.24      2630857.23      6999653.04
      2630675.81      6999710.76      2629607.35      7001136.67
#Sta/Elev= 30
  4090.6  524.94  4225.4  524.92  4371.5  521.31  4636.3  519.55  5003.3  517.98
  5063.5  518.46  5086.5  519.68  5119.9  517.55  5120.1  517.05  5123.9  517.55
  5128.1  518.76  5136.5  518.48  5142.7  520.32  5157.3  518.47  5178.1  520.00
  5186.5  519.32  5192.7  520.39  5207.3  518.68  5213.6  519.75  5313.6  521.49
  5342.7  523.09  5436.5  523.92  5742.8  530.48  5786.5  530.35  5972.0  534.73
  5978.2  536.29  5986.6  536.64  6057.4  537.16  6442.9  544.97  6781.8  548.41
#Mann=3,-1,0
  4090.6    0.05       0  5119.9    0.03       0  5123.9    0.05       0
Bank Sta=5119.9,5123.9
Exp/Cntr=0.3,0.1

Type RM Length L Ch R = 1,1229,515,515,515
BEGIN DESCRIPTION:
Mapping XS 3840d68f
END DESCRIPTION:
XS GIS Cut Line= 5
      2630965.26      6999475.34      2630770.84      6999249.67
      2630631.95      6999267.03      2630378.48      6999357.31
      2630027.75      6999690.67
#Sta/Elev= 30
  4554.3  517.40  4578.0  517.46  4663.6  516.78  4670.2  517.09  4698.7  516.82
  4712.9  516.82  4719.5  517.02  4733.8  516.66  4770.0  516.31  4847.9  516.18
  4877.2  515.81  4917.5  514.87  4967.9  514.56  4983.4  513.98  5007.1  513.93
  5007.3  513.43  5010.8  513.43  5011.1  513.93  5052.8  514.69  5094.0  514.30
  5109.1  514.47  5115.2  514.78  5139.9  515.30  5157.7  515.26  5221.4  516.30
  5569.6  524.96  5654.5  526.93  5690.1  527.51  5725.3  528.95  5745.1  529.49
#Mann=3,-1,0
  4554.3    0.05       0  5007.1    0.03       0  5011.1    0.05       0
Bank Sta=5007.1,5011.1
Exp/Cntr=0.3,0.1

Type RM Length L Ch R = 1,714,147,147,147
BEGIN DESCRIPTION:
Mapping XS 9636c243
END DESCRIPTION:
XS GIS Cut Line= 5
      2630975.72      6999260.12      2630562.50      6998763.56
      2630423.61      6998829.53      2630184.03      6998958.00
      2629889.94      6999283.23
#Sta/Elev= 30
  4203.0  516.60  4238.0  515.29  4244.5  515.68  4379.9  515.03  4400.7  515.39
  4436.0  514.95  4472.4  515.12  4852.7  512.05  4903.7  512.18  4955.8  511.19
  4966.3  509.77  4976.0  509.30  4976.2  508.80  4979.7  508.80  4980.0  509.30
  5076.9  510.78  5082.6  511.21  5098.8  511.42  5104.5  511.99  5126.4  512.42
  5142.7  512.59  5148.3  512.16  5186.5  512.06  5246.6  513.24  5252.3  513.75
  5324.9  514.65  5431.0  516.82  5551.3  517.80  5615.5  519.58  5713.1  520.54
#Mann=3,-1,0
  4203.0    0.05       0  4976.0    0.03       0  4980.0    0.05       0
Bank Sta=4976,4980
Exp/Cntr=0.3,0.1

Type RM Length L Ch R = 1,567,419,419,419
BEGIN DESCRIPTION:
Mapping XS 8060694d
END DESCRIPTION:
XS GIS Cut Line= 5
      2630872.62      6999091.49      2630516.72      6998650.53
      2630369.16      6998702.61      2630160.82      6998770.32
      2629942.09      6999079.32
#Sta/Elev= 30
  4275.8  514.86  4295.0  515.03  4352.6  514.79  4359.0  514.93  4373.4  514.56
  4379.8  514.80  4458.1  514.34  4643.6  512.68  4742.8  512.00  4786.0  511.48
  4821.2  511.38  4833.5  511.14  4833.8  510.64  4837.3  510.64  4837.5  511.14
  4896.3  511.73  5072.6  511.61  5104.6  511.69  5109.8  512.00  5141.8  512.12
  5236.1  512.10  5322.3  513.26  5351.8  514.30  5358.0  514.16  5372.7  514.39
  5378.9  514.24  5402.3  514.44  5451.6  515.05  5530.3  516.39  5596.6  517.00
#Mann=3,-1,0
  4275.8    0.05       0  4833.5    0.03       0  4837.5    0.05       0
Bank Sta=4833.5,4837.5
Exp/Cntr=0.3,0.1

Type RM Length L Ch R = 1,148,0,0,0
BEGIN DESCRIPTION:
Berry Creek Trib 8 1.0
END DESCRIPTION:
XS GIS Cut Line= 5
      2631014.82      6999262.75      2630424.71      6998473.44
      2630179.48      6998362.45      2629992.42      6998369.28
      2629837.32      6999416.27
#Sta/Elev= 30
  3745.3  516.07  3752.7  516.33  3909.8  514.90  3988.2  515.04  4146.6  514.37
  4567.7  510.32  4638.5  510.26  4653.1  509.67  4673.9  509.78  4717.7  508.77
  4828.2  509.64  4937.7  509.12  4959.9  508.85  4992.9  505.35  4993.1  504.85
  4996.6  504.85  4996.9  505.35  4999.2  506.71  5004.2  506.71  5023.5  508.98
  5093.0  509.66  5195.4  509.26  5381.0  510.00  5421.4  511.28  5542.9  512.15
  5926.9  517.33  5987.5  518.35  6014.3  519.34  6078.5  519.91  6245.6  523.78
#Mann=3,-1,0
  3745.3    0.05       0  4992.9    0.03       0  4996.9    0.05       0
Bank Sta=4992.9,4996.9
Exp/Cntr=0.3,0.1

Chan Stop Cuts=-1