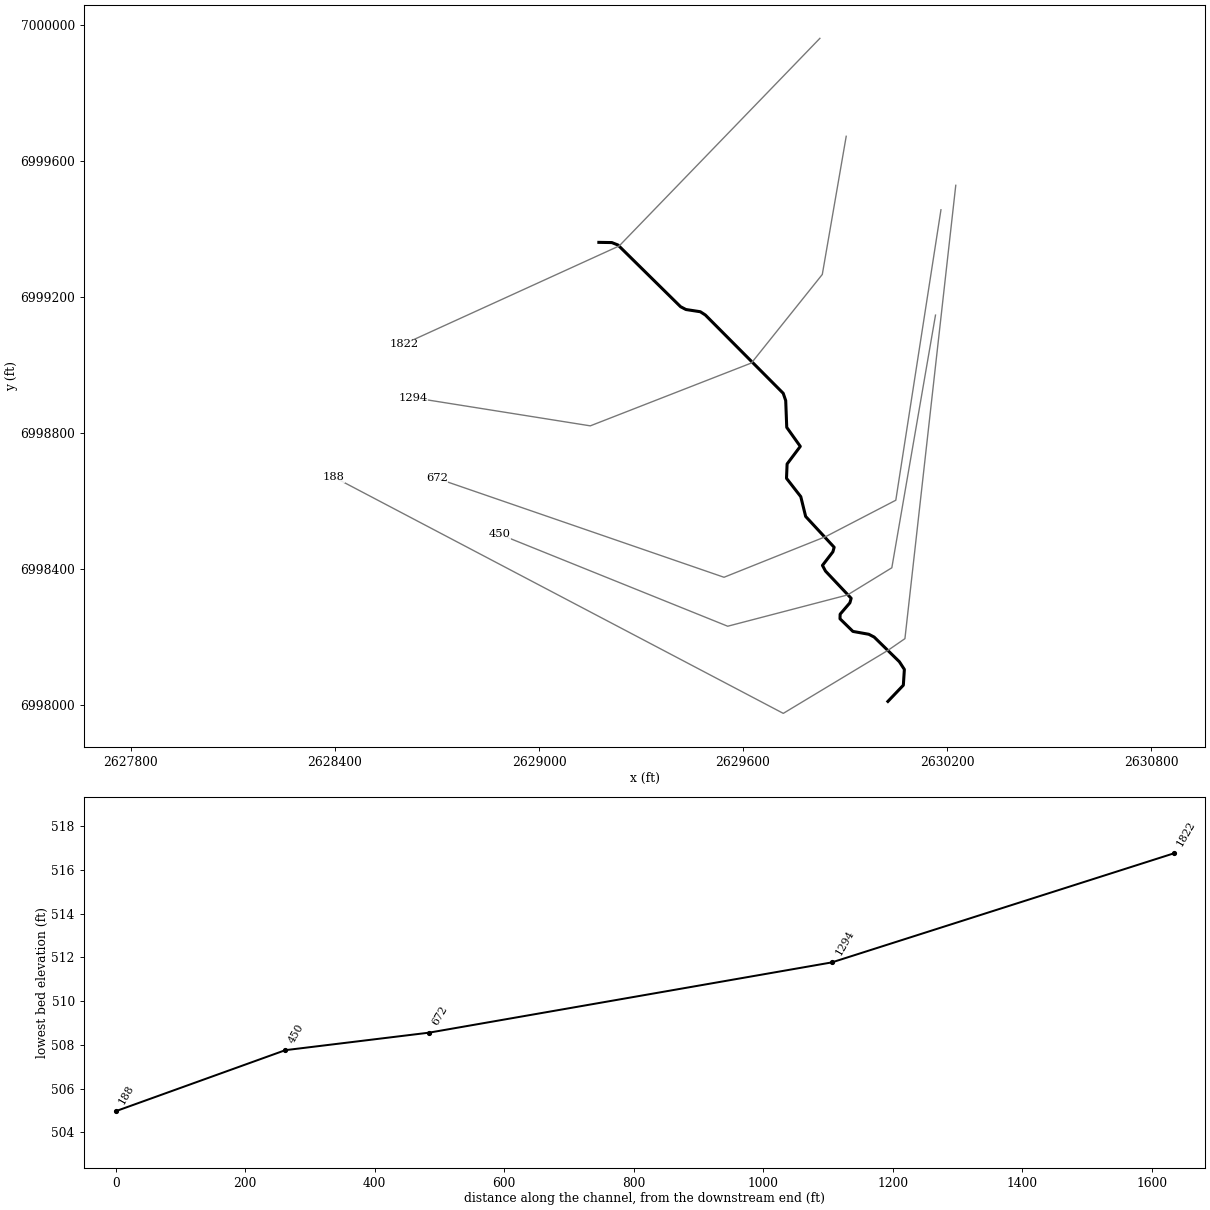
--- Berry Creek Trib 9.prj (project) ---

Proj Title=Berry Creek Trib 9 Base Level Engineering
Current Plan=p01
Default Exp/Contr=0.3,0.1
English Units
Geom File=g01
Flow File=f01
Plan File=p01
Y Axis Title=Elevation
X Axis Title(PF)=Main Channel Distance
X Axis Title(XS)=Station
BEGIN DESCRIPTION:
Berry Creek Trib 9
END DESCRIPTION:
DSS Export Rating Curves= 0
DSS Export Rating Curve Sorted= 0
DSS Export Volume Flow Curves= 0
DXF OffsetX= 0
DXF OffsetY= 0
DXF ScaleX= 1
DXF ScaleY= 10

--- Berry Creek Trib 9.p01 (plan) ---

Plan Title=Multiple Run
Short Identifier=Multiple
Geom File=g01
Flow File=f01
Subcritical Flow
K Sum by GR= 0
Std Step Tol= 0.01
Critical Tol= 0.01
Num of Std Step Trials= 20
Max Error Tol= 0.3
Flow Tol Ratio= 0.001
Split Flow NTrial= 30
Split Flow Tol= 0.02
Split Flow Ratio= 0.02
Log Output Level= 0
Friction Slope Method= 1
Unsteady Friction Slope Method= 2
Unsteady Bridges Friction Slope Method= 1
Parabolic Critical Depth
Global Vel Dist=  1 , 1 , 1
Global Log Level= 0
CheckData=True
Encroach Param= -1, 0, 0, 0
BEGIN DESCRIPTION:
Multiple Run
END DESCRIPTION:

--- Berry Creek Trib 9.f01 (steady flow) ---

Flow Title=Multiple
Program Version=4.10
Number of Profiles= 7
Profile Names=10-year,25-year,50-year,1pct_min,100-year,1pct_plu,500-year
River Rch & RM=Berry Creek Trib,Reach-1         ,1822
     209     261     300     172     343     685     447
Boundary for River Rch & Prof#=Berry Creek Trib,Reach-1         , 1
Up Type= 0
Dn Type= 3
Dn Slope=0.01073
Boundary for River Rch & Prof#=Berry Creek Trib,Reach-1         , 2
Up Type= 0
Dn Type= 3
Dn Slope=0.01073
Boundary for River Rch & Prof#=Berry Creek Trib,Reach-1         , 3
Up Type= 0
Dn Type= 3
Dn Slope=0.01073
Boundary for River Rch & Prof#=Berry Creek Trib,Reach-1         , 4
Up Type= 0
Dn Type= 3
Dn Slope=0.01073
Boundary for River Rch & Prof#=Berry Creek Trib,Reach-1         , 5
Up Type= 0
Dn Type= 3
Dn Slope=0.01073
Boundary for River Rch & Prof#=Berry Creek Trib,Reach-1         , 6
Up Type= 0
Dn Type= 3
Dn Slope=0.01073
Boundary for River Rch & Prof#=Berry Creek Trib,Reach-1         , 7
Up Type= 0
Dn Type= 3
Dn Slope=0.01073
DSS Import GetInterval= 0
DSS Import GetPeak= 0
DSS Import FillOption= 0

--- Berry Creek Trib 9.g01 (geometry) ---

Geom Title=Existing Conditions

River Reach=Berry Creek Trib,Reach-1
Reach XY= 30
      2629176.00      6999361.00      2629214.16      6999360.41
      2629232.21      6999353.24      2629416.32      6999171.78
      2629432.05      6999163.53      2629474.35      6999157.02
      2629489.21      6999147.37      2629718.14      6998917.17
      2629725.49      6998895.78      2629728.55      6998816.90
      2629768.41      6998760.99      2629729.60      6998709.36
      2629727.84      6998667.12      2629769.82      6998613.19
      2629784.17      6998554.94      2629867.98      6998464.33
      2629864.29      6998451.00      2629833.58      6998411.00
      2629842.46      6998394.33      2629917.96      6998314.32
      2629914.27      6998300.98      2629885.55      6998267.51
      2629885.19      6998254.05      2629923.17      6998216.86
      2629969.88      6998208.47      2629985.67      6998200.23
      2630059.78      6998127.72      2630074.47      6998105.04
      2630071.43      6998058.65      2630026.00      6998011.00

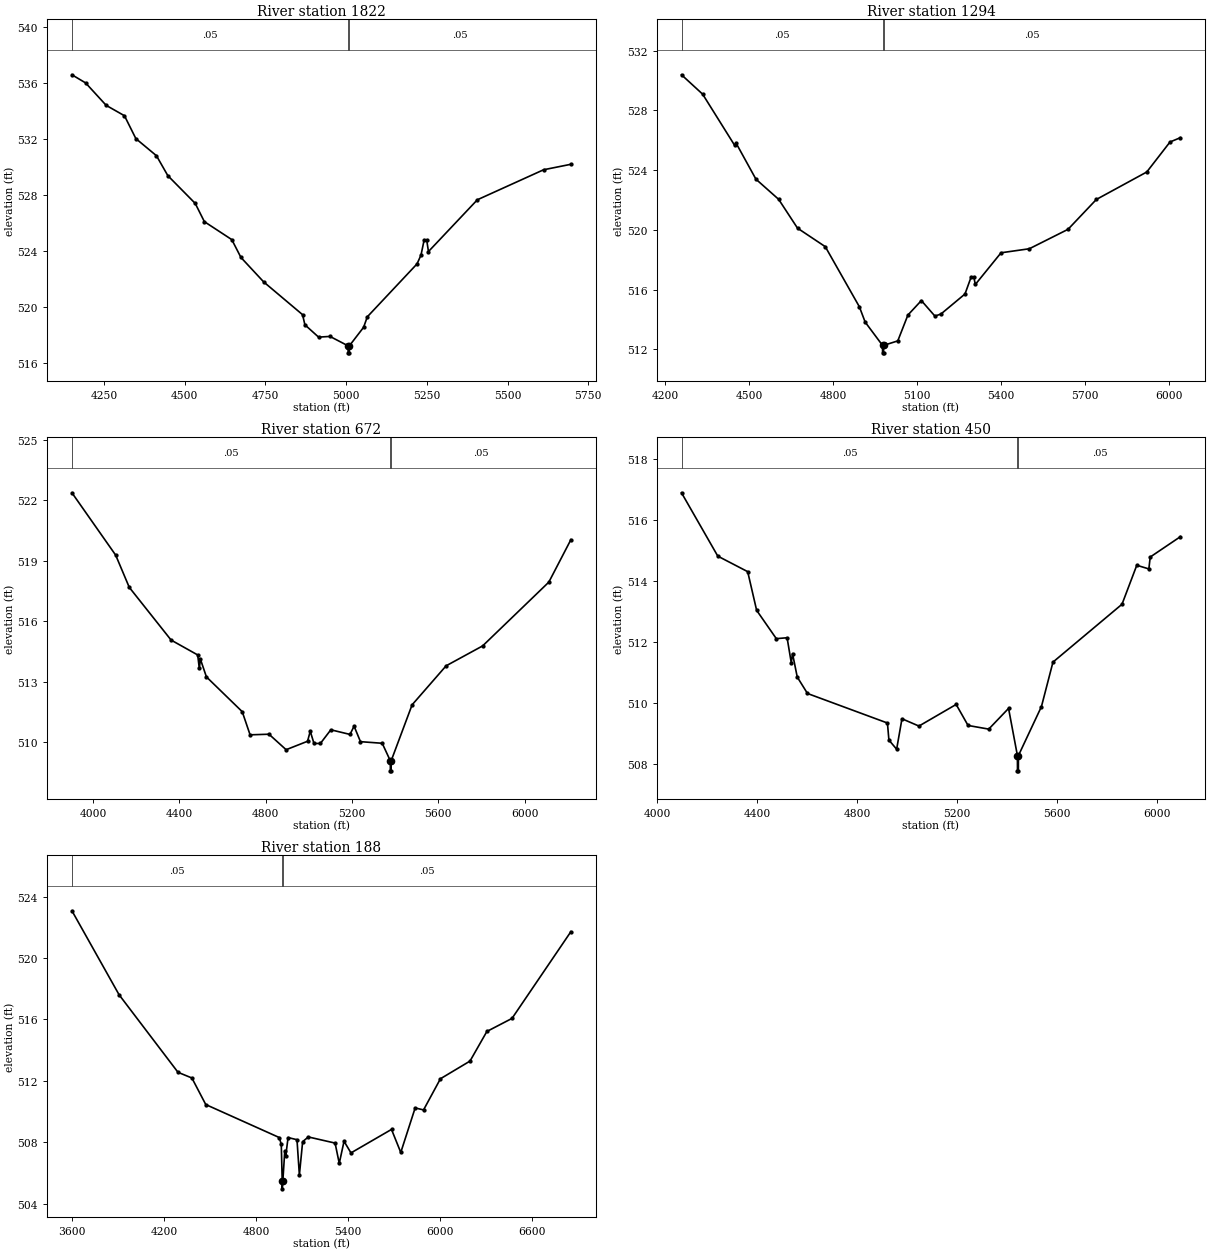
Type RM Length L Ch R = 1,1822,528,528,528
BEGIN DESCRIPTION:
Berry Creek Trib 9 2.0
END DESCRIPTION:
XS GIS Cut Line= 3
      2629826.02      6999961.03      2629235.79      6999350.48
      2628602.38      6999061.78
#Sta/Elev= 30
  4150.8  536.57  4193.2  535.99  4256.9  534.39  4313.5  533.65  4348.8  532.02
  4412.6  530.80  4447.8  529.38  4532.7  527.40  4561.0  526.10  4645.9  524.82
  4674.2  523.55  4744.9  521.80  4865.1  519.47  4872.3  518.75  4914.7  517.87
  4950.0  517.92  5006.0  517.25  5006.3  516.75  5009.8  516.75  5010.0  517.25
  5054.1  518.57  5065.7  519.32  5219.6  523.09  5231.9  523.72  5241.5  524.78
  5249.5  524.79  5255.0  523.97  5406.4  527.66  5611.6  529.80  5696.1  530.19
#Mann=3,-1,0
  4150.8    0.05       0  5006.0    0.03       0  5010.0    0.05       0
Bank Sta=5006,5010
Exp/Cntr=0.3,0.1

Type RM Length L Ch R = 1,1294,622,622,622
BEGIN DESCRIPTION:
Mapping XS 1febbb89
END DESCRIPTION:
XS GIS Cut Line= 5
      2629903.44      6999673.01      2629833.12      6999266.73
      2629624.79      6999006.31      2629150.83      6998821.41
      2628629.17      6998904.46
#Sta/Elev= 30
  4258.4  530.39  4334.0  529.09  4448.4  525.66  4453.5  525.81  4524.3  523.40
  4605.5  522.05  4672.9  520.12  4772.1  518.88  4893.8  514.86  4914.6  513.83
  4976.6  512.27  4976.9  511.77  4980.4  511.77  4980.6  512.27  5031.2  512.57
  5067.3  514.30  5115.4  515.27  5163.9  514.23  5185.4  514.37  5271.3  515.71
  5292.7  516.82  5302.9  516.83  5308.3  516.35  5400.1  518.47  5501.2  518.74
  5639.4  520.04  5740.6  522.04  5920.8  523.88  6003.9  525.89  6041.2  526.18
#Mann=3,-1,0
  4258.4    0.05       0  4976.6    0.03       0  4980.6    0.05       0
Bank Sta=4976.6,4980.6
Exp/Cntr=0.3,0.1

Type RM Length L Ch R = 1,672,222,222,222
BEGIN DESCRIPTION:
Mapping XS e5aac397
END DESCRIPTION:
XS GIS Cut Line= 5
      2630182.08      6999456.84      2630049.27      6998602.66
      2629843.54      6998495.89      2629544.06      6998376.10
      2628699.39      6998667.19
#Sta/Elev= 30
  3902.4  522.38  4105.2  519.28  4168.1  517.68  4361.9  515.06  4485.2  514.32
  4492.7  513.65  4497.8  514.11  4525.6  513.23  4691.6  511.50  4728.0  510.35
  4815.6  510.38  4895.0  509.61  4994.3  510.03  5006.8  510.53  5024.1  509.92
  5053.7  509.92  5102.2  510.60  5191.0  510.37  5209.9  510.78  5239.5  510.01
  5340.3  509.93  5377.8  509.06  5378.0  508.56  5381.5  508.56  5381.8  509.06
  5478.7  511.84  5636.4  513.78  5805.7  514.77  6112.4  517.94  6214.6  520.05
#Mann=3,-1,0
  3902.4    0.05       0  5377.8    0.03       0  5381.8    0.05       0
Bank Sta=5377.8,5381.8
Exp/Cntr=0.3,0.1

Type RM Length L Ch R = 1,450,262,262,262
BEGIN DESCRIPTION:
Mapping XS 3376d874
END DESCRIPTION:
XS GIS Cut Line= 5
      2630166.04      6999147.10      2630037.56      6998404.00
      2629907.35      6998324.14      2629554.92      6998232.12
      2628883.07      6998502.95
#Sta/Elev= 30
  4097.1  516.89  4242.2  514.81  4361.8  514.30  4397.6  513.03  4476.3  512.10
  4519.4  512.13  4536.1  511.31  4541.1  511.61  4560.0  510.84  4600.9  510.30
  4920.7  509.33  4926.6  508.77  4957.5  508.47  4978.8  509.47  5046.7  509.23
  5195.5  509.94  5243.1  509.25  5325.8  509.13  5405.1  509.81  5440.5  508.26
  5440.8  507.76  5444.3  507.76  5444.5  508.26  5536.6  509.87  5582.7  511.33
  5858.8  513.23  5917.9  514.51  5966.2  514.39  5971.6  514.78  6092.6  515.45
#Mann=3,-1,0
  4097.1    0.05       0  5440.5    0.03       0  5444.5    0.05       0
Bank Sta=5440.5,5444.5
Exp/Cntr=0.3,0.1

Type RM Length L Ch R = 1,188,0,0,0
BEGIN DESCRIPTION:
Berry Creek Trib 9 1.0
END DESCRIPTION:
XS GIS Cut Line= 5
      2630225.63      6999528.81      2630076.11      6998195.61
      2630026.35      6998161.30      2629718.36      6997975.84
      2628395.81      6998671.13
#Sta/Elev= 30
  3598.0  523.08  3905.7  517.61  4290.1  512.56  4380.7  512.19  4471.3  510.46
  4951.1  508.31  4964.0  507.86  4970.1  505.47  4970.3  504.97  4974.1  505.47
  4987.0  507.46  4993.0  507.10  5008.3  508.31  5066.5  508.17  5082.1  505.87
  5103.4  508.04  5140.3  508.35  5315.1  507.95  5342.3  506.63  5373.5  508.07
  5418.7  507.31  5683.2  508.84  5743.7  507.34  5837.5  510.24  5892.3  510.11
  6002.5  512.14  6195.3  513.29  6305.5  515.22  6469.4  516.07  6853.7  521.72
#Mann=3,-1,0
  3598.0    0.05       0  4970.1    0.03       0  4974.1    0.05       0
Bank Sta=4970.1,4974.1
Exp/Cntr=0.3,0.1

Chan Stop Cuts=-1