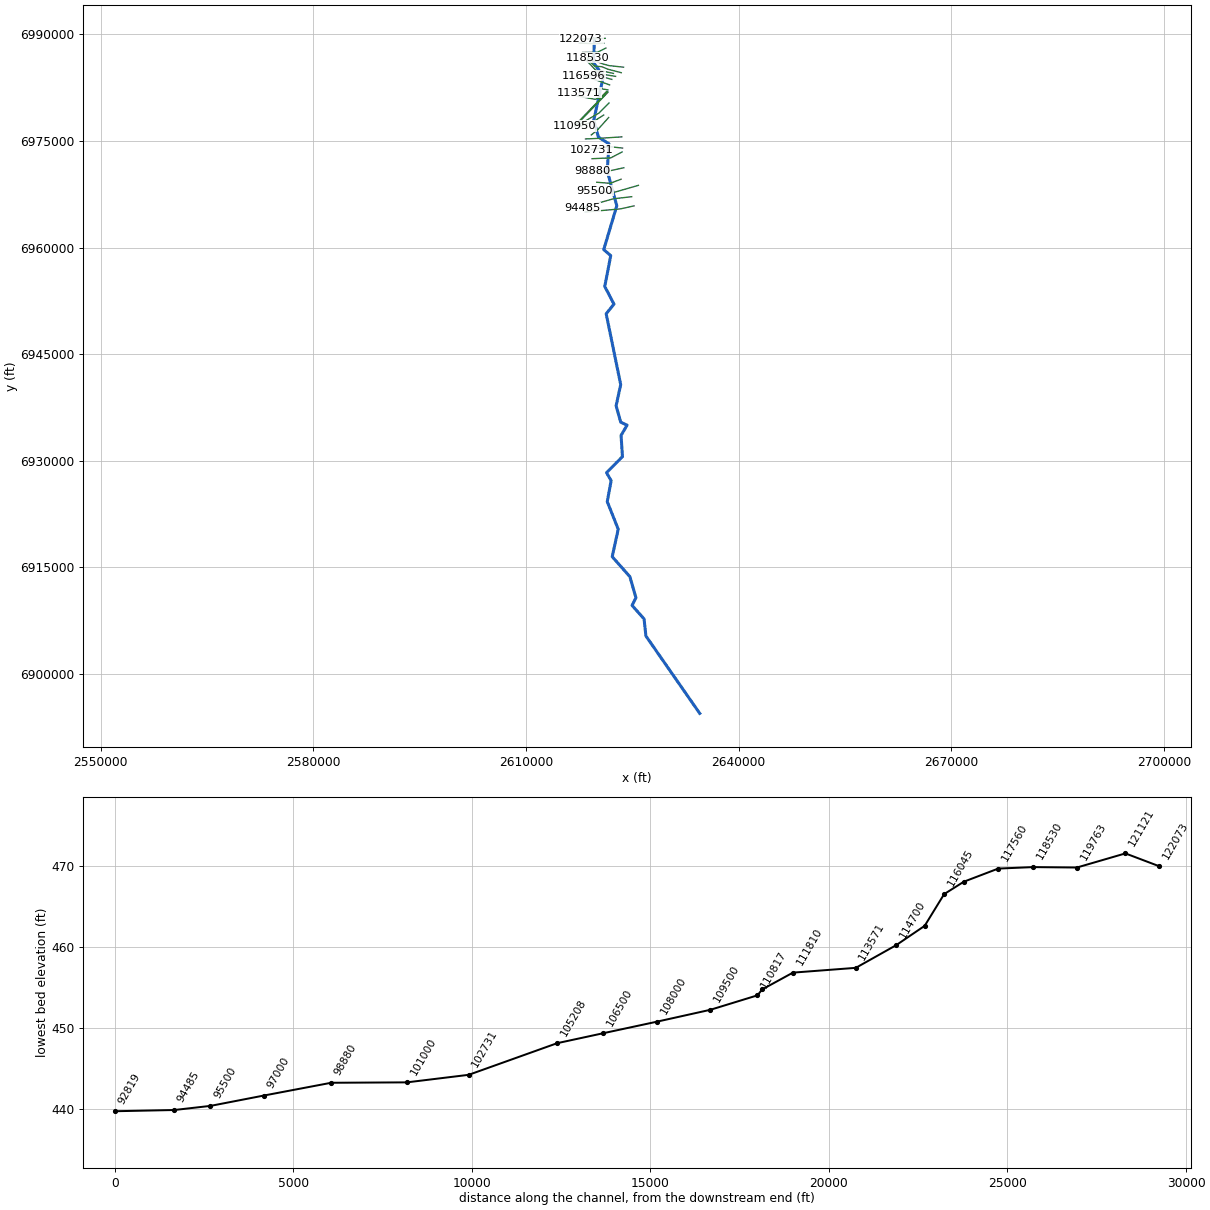
--- Big Brushy Creek.prj (project) ---

Proj Title=Big Brushy Creek Base Level Engineering
Current Plan=p01
Default Exp/Contr=0.3,0.1
English Units
Geom File=g01
Flow File=f01
Plan File=p01
Y Axis Title=Elevation
X Axis Title(PF)=Main Channel Distance
X Axis Title(XS)=Station
BEGIN DESCRIPTION:
Big Brushy Creek
END DESCRIPTION:
DSS Export Rating Curves= 0
DSS Export Rating Curve Sorted= 0
DSS Export Volume Flow Curves= 0
DXF OffsetX= 0
DXF OffsetY= 0
DXF ScaleX= 1
DXF ScaleY= 10

--- Big Brushy Creek.p01 (plan) ---

Plan Title=Multiple Run
Short Identifier=Multiple
Geom File=g01
Flow File=f01
Subcritical Flow
K Sum by GR= 0
Std Step Tol= 0.01
Critical Tol= 0.01
Num of Std Step Trials= 20
Max Error Tol= 0.3
Flow Tol Ratio= 0.001
Split Flow NTrial= 30
Split Flow Tol= 0.02
Split Flow Ratio= 0.02
Log Output Level= 0
Friction Slope Method= 1
Unsteady Friction Slope Method= 2
Unsteady Bridges Friction Slope Method= 1
Parabolic Critical Depth
Global Vel Dist=  1 , 1 , 1
Global Log Level= 0
CheckData=True
Encroach Param= -1, 0, 0, 0
BEGIN DESCRIPTION:
Multiple Run
END DESCRIPTION:

--- Big Brushy Creek.f01 (steady flow) ---

Flow Title=Multiple
Program Version=4.10
Number of Profiles= 7
Profile Names=10-year,25-year,50-year,1pct_min,100-year,1pct_plu,500-year
River Rch & RM=Big Brushy Creek,Reach-1         ,122073
    4186    6024    7608    4733    9443   18841   14555
River Rch & RM=Big Brushy Creek,Reach-1         ,115500
    4903    7095    8996    5615   11204   22356   17390
River Rch & RM=Big Brushy Creek,Reach-1         ,113571
    5132    7434    9432    5891   11754   23451   18262
River Rch & RM=Big Brushy Creek,Reach-1         ,111810
    5342    7743    9828    6140   12251   24443   19045
River Rch & RM=Big Brushy Creek,Reach-1         ,110950
    5741    8332   10586    6619   13206   26350   20561
River Rch & RM=Big Brushy Creek,Reach-1         ,105208
    6989   10176   12959    8117   16196   32316   25305
River Rch & RM=Big Brushy Creek,Reach-1         ,95500
    7807   11399   14544    9126   18208   36330   28542
River Rch & RM=Big Brushy Creek,Reach-1         ,94485
    7758   11307   14409    9030   18017   35948   28169
River Rch & RM=Big Brushy Creek,Reach-1         ,92819
    8522   12445   15881    9965   19883   39671   31161
River Rch & RM=Big Brushy Creek,Reach-1         ,82000
    8278   12101   15450    9699   19351   38611   30367
River Rch & RM=Big Brushy Creek,Reach-1         ,79500
    8735   12782   16332   10259   20469   40842   32161
River Rch & RM=Big Brushy Creek,Reach-1         ,77914
    8659   12654   16153   10136   20224   40353   31711
River Rch & RM=Big Brushy Creek,Reach-1         ,75000
    8688   12694   16203   10167   20285   40474   31802
River Rch & RM=Big Brushy Creek,Reach-1         ,71918
    8938   13066   16685   10473   20897   41694   32782
River Rch & RM=Big Brushy Creek,Reach-1         ,69344
    9032   13208   16868   10590   21130   42160   33159
River Rch & RM=Big Brushy Creek,Reach-1         ,68500
    9156   13406   17137   10769   21487   42871   33782
River Rch & RM=Big Brushy Creek,Reach-1         ,63000
    9282   13591   17374   10918   21784   43465   34248
River Rch & RM=Big Brushy Creek,Reach-1         ,62213
    9231   13507   17256   10838   21624   43145   33957
River Rch & RM=Big Brushy Creek,Reach-1         ,59466
   10260   15038   19239   12097   24136   48159   37986
River Rch & RM=Big Brushy Creek,Reach-1         ,57838
   10359   15184   19426   12214   24370   48625   38353
River Rch & RM=Big Brushy Creek,Reach-1         ,57021
   10284   15062   19259   12102   24147   48179   37957
River Rch & RM=Big Brushy Creek,Reach-1         ,51933
   10222   14950   19097   11989   23921   47728   37527
River Rch & RM=Big Brushy Creek,Reach-1         ,44520
    9874   14458   18479   11607   23159   46208   36383
River Rch & RM=Big Brushy Creek,Reach-1         ,42655
    9979   14594   18639   11698   23340   46569   36604
River Rch & RM=Big Brushy Creek,Reach-1         ,34000
    9978   14584   18619   11680   23304   46498   36516
River Rch & RM=Big Brushy Creek,Reach-1         ,28869
   10121   14791   18881   11843   23629   47147   37014
River Rch & RM=Big Brushy Creek,Reach-1         ,27500
   10247   14969   19104   11979   23900   47687   37415
River Rch & RM=Big Brushy Creek,Reach-1         ,23500
   10309   15057   19213   12045   24034   47954   37612
River Rch & RM=Big Brushy Creek,Reach-1         ,18500
   10343   15094   19249   12060   24064   48013   37611
River Rch & RM=Big Brushy Creek,Reach-1         ,15040
   10409   15190   19372   12138   24218   48322   37855
River Rch & RM=Big Brushy Creek,Reach-1         ,12032
   10437   15230   19422   12168   24278   48441   37942
River Rch & RM=Big Brushy Creek,Reach-1         ,10404
   10424   15208   19391   12147   24237   48359   37868
River Rch & RM=Big Brushy Creek,Reach-1         ,9125
   10442   15223   19402   12148   24238   48361   37831
Boundary for River Rch & Prof#=Big Brushy Creek,Reach-1         , 1
Up Type= 0
Dn Type= 3
Dn Slope=0.00063
Boundary for River Rch & Prof#=Big Brushy Creek,Reach-1         , 2
Up Type= 0
Dn Type= 3
Dn Slope=0.00063
Boundary for River Rch & Prof#=Big Brushy Creek,Reach-1         , 3
Up Type= 0
Dn Type= 3
Dn Slope=0.00063
Boundary for River Rch & Prof#=Big Brushy Creek,Reach-1         , 4
Up Type= 0
Dn Type= 3
Dn Slope=0.00063
Boundary for River Rch & Prof#=Big Brushy Creek,Reach-1         , 5
Up Type= 0
Dn Type= 3
Dn Slope=0.00063
Boundary for River Rch & Prof#=Big Brushy Creek,Reach-1         , 6
Up Type= 0
Dn Type= 3
Dn Slope=0.00063
Boundary for River Rch & Prof#=Big Brushy Creek,Reach-1         , 7
Up Type= 0
Dn Type= 3
Dn Slope=0.00063
DSS Import GetInterval= 0
DSS Import GetPeak= 0
DSS Import FillOption= 0

--- Big Brushy Creek.g01 (geometry) ---

Geom Title=Existing Conditions
Program Version=4.10

River Reach=Big Brushy Creek,Reach-1
Reach XY= 30
      2619674.65      6989409.72      2619534.04      6986057.68
      2620926.65      6984095.43      2619576.12      6977926.05
      2620233.88      6975554.84      2621723.77       6974605.1
      2621476.09      6970776.39      2622826.23      6965886.07
      2620983.06        6959711.      2621969.02       6958861.2
      2621127.22       6954521.5      2622426.21      6952036.09
      2621325.96      6950680.98      2623375.64      6940695.83
       2622727.1      6937721.47      2623381.05      6935408.74
       2624276.3      6934990.83      2623426.93      6933550.53
      2623622.69      6930562.73      2621376.18      6928295.78
       2622026.5      6927185.96      2621477.22       6924221.5
      2623026.04      6920341.02      2622177.22       6916471.5
      2624672.47      6913659.55      2625526.15      6910686.13
      2624977.68      6909617.14      2626672.47      6907709.54
      2626931.73      6905308.45        2634526.        6894411.

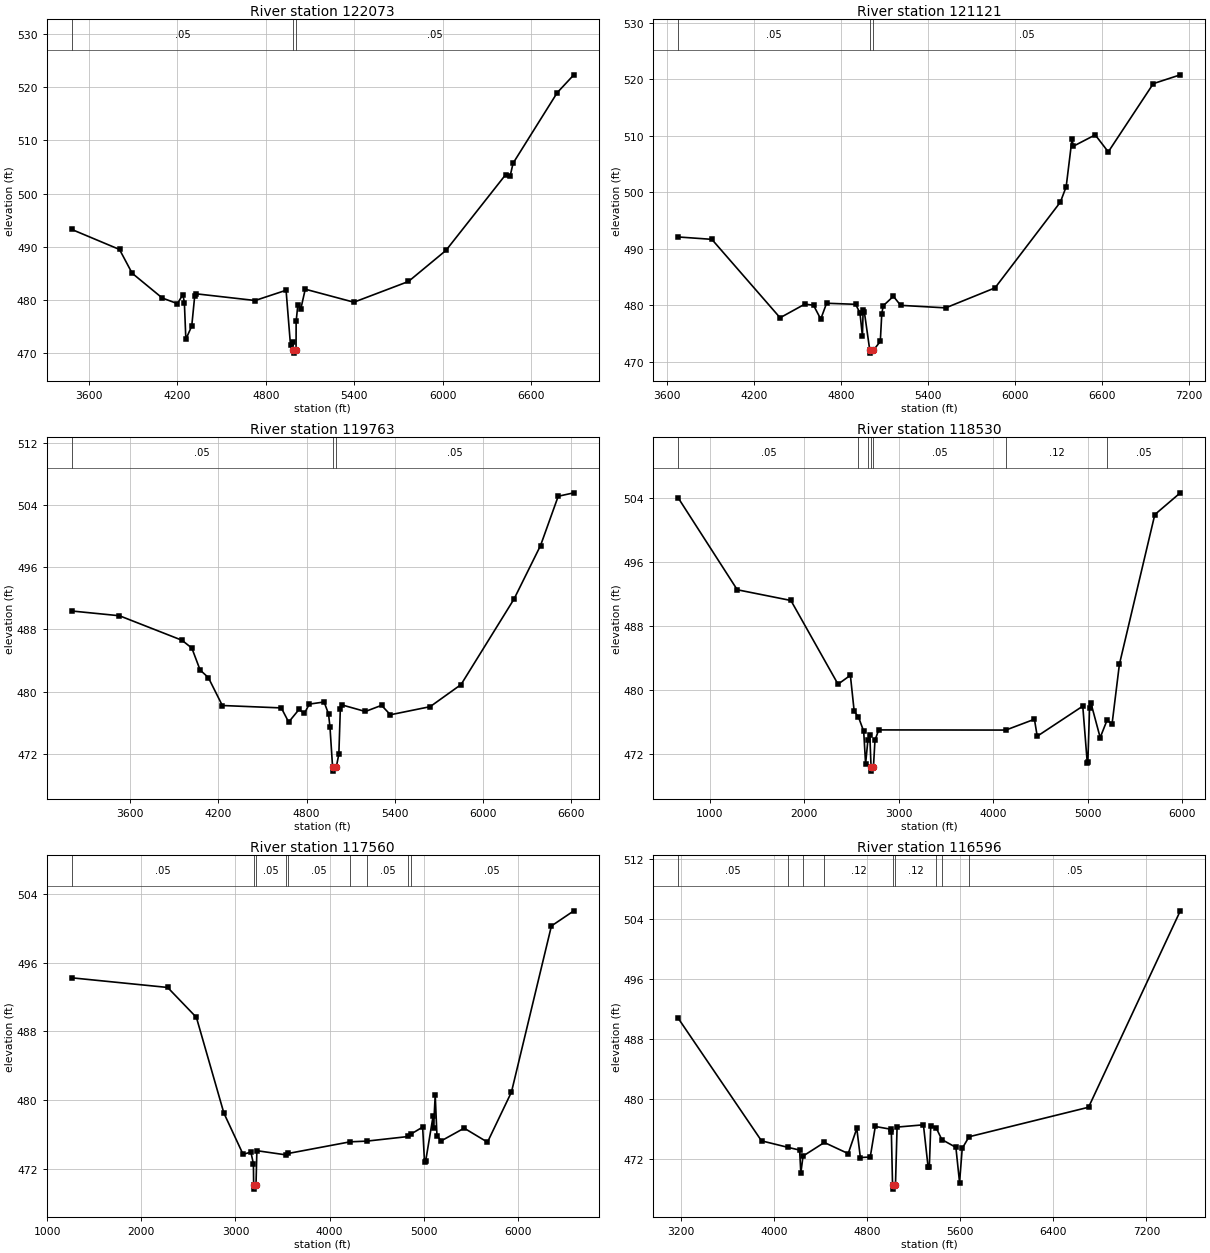
Type RM Length L Ch R = 1 ,122073  ,952,952,952
BEGIN DESCRIPTION:
Mapping XS 7233b47b
END DESCRIPTION:
XS GIS Cut Line= 6
      2621189.96      6989459.49      2619687.83      6989410.07
      2619673.86      6989408.82      2619664.72      6989409.31
      2619487.78      6989403.49      2617783.76      6989347.44
#Sta/Elev= 30
  3482.9  493.24    3807  489.47  3892.6     485  4097.2  480.33  4199.8  479.27
  4237.3  480.97  4247.3  479.45  4257.3  472.56  4297.3  475.05  4317.3  480.68
  4327.3  481.12  4727.5  479.86  4937.6  481.79  4967.7  471.42  4984.3  472.05
  4987.2  470.45  4989.2  469.95  5005.4  470.45  5005.9  475.91  5017.7  479.09
  5037.8   478.3  5067.8  481.99  5397.9  479.54  5768.1  483.44  6022.8  489.29
  6428.5  503.57  6458.5  503.29  6478.5  505.71  6778.7  519.02    6891  522.36
#Mann= 3 ,-1 , 0
  3482.9     .05       0  4987.2     .04       0  5005.4     .05       0
Bank Sta=4987.2,5005.4
XS Rating Curve= 0 ,0
Exp/Cntr=0.3,0.1

Type RM Length L Ch R = 1 ,121121  ,1358,1358,1358
BEGIN DESCRIPTION:
Mapping XS 096334fc
END DESCRIPTION:
XS GIS Cut Line= 3
      2620987.38      6988764.92      2619640.11      6988702.42
      2617529.96      6988792.65
#Sta/Elev= 30
  3679.4   492.1    3911  491.68  4381.5   477.8  4551.7  480.21  4611.8  480.02
  4661.8  477.56  4701.9  480.37  4902.1  480.18  4932.1  478.65    4949  474.53
    4954  479.24  4962.2  478.85  4999.7  472.04  5002.2  471.54  5024.7  472.04
  5072.3  473.62  5082.3  478.48  5092.3  479.92  5162.4   481.6  5212.4     480
  5522.7  479.55    5863  483.09  6313.4  498.27  6353.4  500.99  6393.5   509.4
  6403.5  508.17  6553.6  510.17  6643.7  507.16    6954  519.24  7140.2   520.8
#Mann= 3 ,-1 , 0
  3679.4     .05       0  4999.7     .04       0  5024.7     .05       0
Bank Sta=4999.7,5024.7
XS Rating Curve= 0 ,0
Exp/Cntr=0.3,0.1

Type RM Length L Ch R = 1 ,119763  ,1233,1233,1233
BEGIN DESCRIPTION:
Mapping XS 217dfb26
END DESCRIPTION:
XS GIS Cut Line= 4
      2621285.63       6988093.4      2620157.12      6987529.14
      2619618.92      6987490.08       2618009.8      6987477.07
#Sta/Elev= 30
  3205.5  490.37  3529.3  489.76  3954.2  486.61  4021.3   485.6  4077.2  482.79
  4133.1  481.82  4228.2  478.23  4628.8  477.92  4678.9   476.1  4749.1  477.72
  4785.5  477.22  4819.3  478.41  4919.5  478.68  4949.6  477.15  4959.6  475.42
  4977.2   470.3  4979.7   469.8  5002.2   470.3  5019.8  472.01  5029.8  477.84
  5039.8  478.31  5199.8  477.46  5309.8  478.25  5369.8  477.04  5639.8  478.08
  5849.8  480.92  6209.8  491.91  6389.8  498.78  6509.8  505.11    6616  505.55
#Mann= 3 ,-1 , 0
  3205.5     .05       0  4977.2     .04       0  5002.2     .05       0
Bank Sta=4977.2,5002.2
XS Rating Curve= 0 ,0
Exp/Cntr=0.3,0.1

Type RM Length L Ch R = 1 ,118530  ,970,970,970
BEGIN DESCRIPTION:
Mapping XS 232e2f9f
END DESCRIPTION:
XS GIS Cut Line= 4
      2623776.62      6985397.51      2621727.96      6985619.74
       2620811.3      6985869.74       2618680.2      6986737.45
#Sta/Elev= 30
   665.6  503.98  1289.9  492.51  1857.6  491.17  2356.1  480.71  2486.8  481.82
  2527.1  477.32  2572.4  476.61  2627.7  474.83  2647.8  470.76  2672.3  473.75
  2692.3  474.34  2705.7  470.35  2708.2  469.85  2730.7  470.35    2747  473.71
  2786.7     475  4131.4  474.98    4434  476.33  4463.5  474.21  4945.4  477.97
  4993.2  470.85  4999.4  471.03  5017.3  477.78  5031.8  478.36  5129.7  474.04
  5202.6  476.22  5255.4  475.75  5332.9  483.19  5707.5   501.9  5977.4  504.62
#Mann= 7 ,-1 , 0
   665.6     .05       0  2572.4     .12       0  2672.3     .05       0
  2705.7     .07       0  2730.7     .05       0  4131.4     .12       0
  5202.6     .05       0
Bank Sta=2705.7,2730.7
XS Rating Curve= 0 ,0
Exp/Cntr=0.3,0.1

Type RM Length L Ch R = 1 ,117560  ,964,964,964
BEGIN DESCRIPTION:
Mapping XS 518c781a
END DESCRIPTION:
XS GIS Cut Line= 6
      2623457.12      6984619.74      2621589.08      6985105.85
      2620707.13      6985466.96       2619856.9      6985531.08
      2619665.46      6985578.07       2618651.6      6986543.33
#Sta/Elev= 30
  1261.7  494.24    2280  493.12  2585.5  489.64  2877.4  478.51  3081.5  473.71
  3164.1  473.98    3191  472.61  3193.6  470.17  3196.1  469.67  3218.6  470.17
  3227.7  474.14  3538.6  473.65  3562.2  473.82    4218  475.17  4393.7  475.25
    4838  475.79  4860.8  476.05  4988.5  476.88  5008.8  472.78  5021.3  472.97
  5099.3  478.14  5104.4  476.81  5122.1  480.62  5140.8  475.86  5187.5  475.29
  5429.7  476.76  5677.2  475.13    5932  480.96  6356.3  500.27  6594.6  502.03
#Mann= 9 ,-1 , 0
  1261.7     .05       0  3193.6     .03       0  3218.6     .05       0
  3538.6     .12       0  3562.2     .05       0    4218     .12       0
  4393.7     .05       0    4838     .12       0  4860.8     .05       0
Bank Sta=3193.6,3218.6
XS Rating Curve= 0 ,0
Exp/Cntr=0.3,0.1

Type RM Length L Ch R = 1 ,116596  ,551,551,551
BEGIN DESCRIPTION:
Mapping XS 2b418808
END DESCRIPTION:
XS GIS Cut Line= 4
      2622355.03       6984518.4      2620572.68      6984914.34
      2619984.49      6984718.09      2618189.27      6984187.33
#Sta/Elev= 30
  3174.2  490.79  3890.3  474.48  4115.3  473.62  4218.1  473.25  4228.6  470.18
  4247.4  472.45  4430.5  474.26  4635.8  472.78  4709.8  476.13  4740.5  472.26
  4825.4  472.32  4868.9  476.39    5000  476.03    5007  475.67  5017.4  468.55
  5019.9  468.05  5042.4  468.55  5056.2  476.31  5282.8  476.61  5323.3  470.96
  5333.8  471.03    5346  476.51  5392.4   476.2  5441.1  474.65    5562  473.61
  5593.6  468.93  5616.6  473.48  5675.3  475.02    6703  478.95  7492.1   505.1
#Mann= 9 ,-1 , 0
  3174.2     .05       0  4115.3     .12       0  4247.4     .05       0
  4430.5     .12       0  5017.4     .07       0  5042.4     .12       0
  5392.4     .05       0  5441.1     .12       0  5675.3     .05       0
Bank Sta=5017.4,5042.4
XS Rating Curve= 0 ,0
Exp/Cntr=0.3,0.1

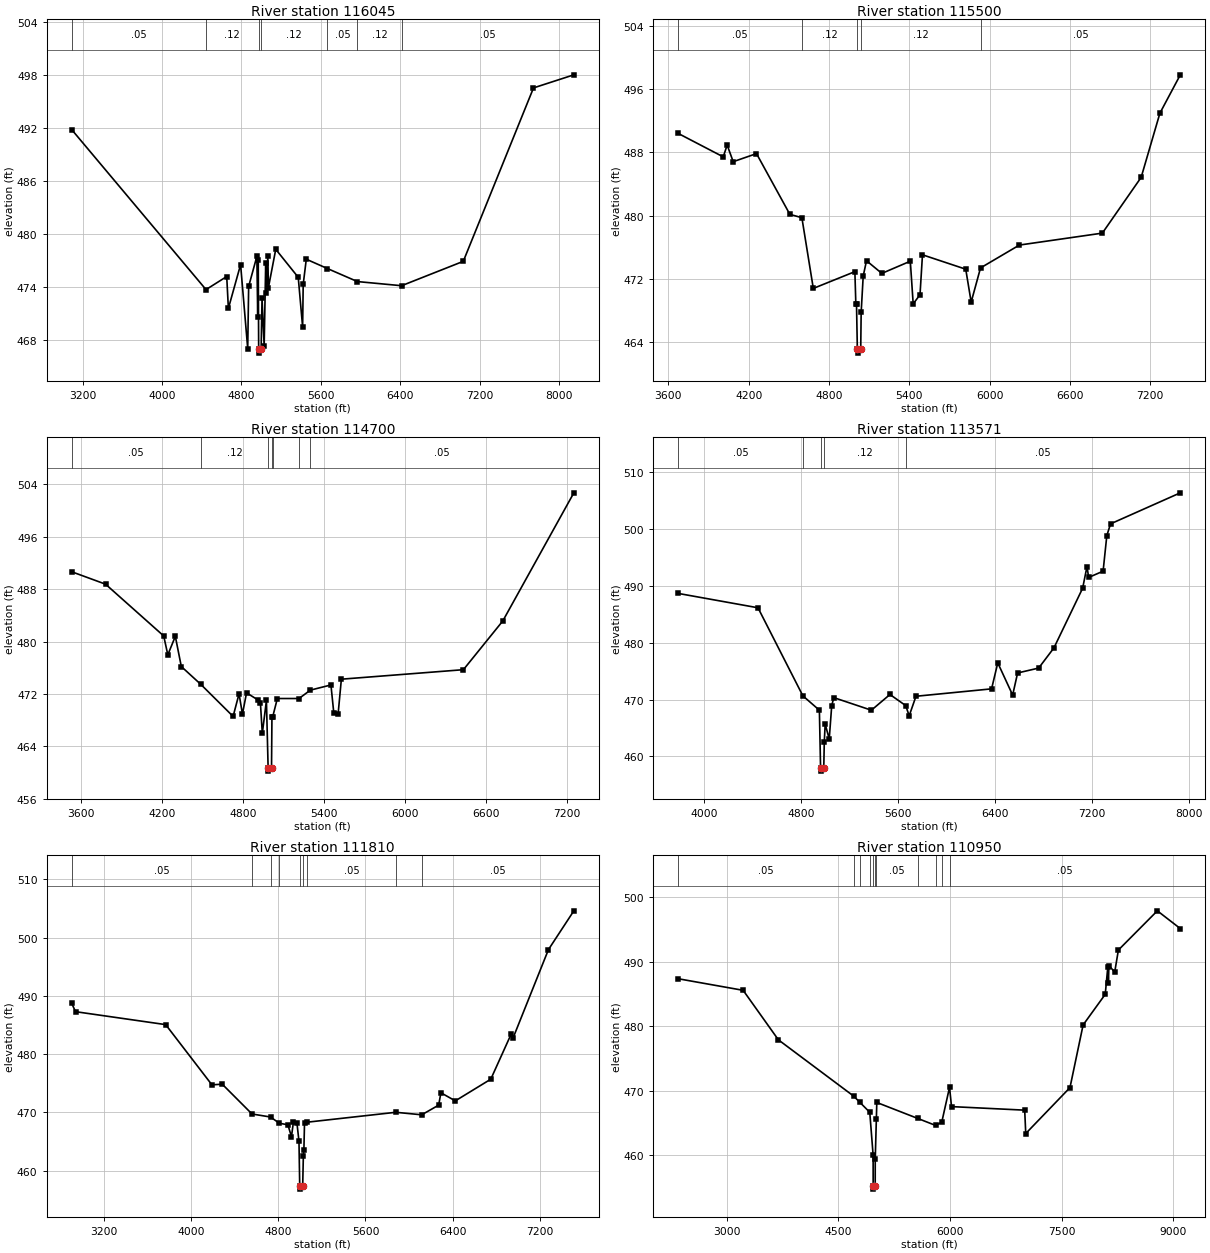
Type RM Length L Ch R = 1 ,116045  ,545,545,545
BEGIN DESCRIPTION:
Mapping XS 10ac7cec
END DESCRIPTION:
XS GIS Cut Line= 5
      2622653.03      6984105.85      2621164.31      6984344.57
      2620799.72      6984427.03      2619823.16      6985008.63
      2618409.76      6986479.56
#Sta/Elev= 30
  3090.5  491.81  4442.8  473.71  4651.5  475.19  4668.3  471.58  4791.3  476.54
  4863.1  467.03  4872.5  474.07  4955.3  477.47  4963.9  470.65    4969  477.02
  4973.4  467.02  4975.9  466.52  4998.4  467.02  5007.3  472.71  5028.7  467.32
  5044.3  476.68  5050.1  473.29  5065.7  477.53  5071.5  473.93  5145.5  478.27
  5372.1   475.1  5416.2  469.48    5422   474.3  5453.2  477.15  5666.7  476.09
  5967.9  474.62  6413.1  474.15  7034.8  476.91  7742.1  496.54  8148.6  498.02
#Mann= 7 ,-1 , 0
  3090.5     .05       0  4442.8     .12       0  4973.4     .07       0
  4998.4     .12       0  5666.7     .05       0  5967.9     .12       0
  6413.1     .05       0
Bank Sta=4973.4,4998.4
XS Rating Curve= 0 ,0
Exp/Cntr=0.3,0.1

Type RM Length L Ch R = 1 ,115500  ,800,800,800
BEGIN DESCRIPTION:
Mapping XS 784a262f
END DESCRIPTION:
XS GIS Cut Line= 3
      2622120.67      6983679.86      2620029.48      6984243.93
       2618443.5       6984200.7
#Sta/Elev= 30
  3673.5  490.38  4009.8  487.42  4039.2  488.91  4084.3  486.81  4258.4  487.83
  4507.8  480.15  4597.6  479.73    4683  470.79  4993.7  472.91  5000.8  468.88
  5005.9   468.8  5012.2  463.11  5014.7  462.61  5037.4  463.11  5040.7  467.76
  5055.9  472.35  5080.6  474.29  5195.2  472.69    5408  474.23  5429.5  468.84
  5480.5  469.99  5498.9  475.04  5822.3  473.22  5862.9  469.06  5932.7  473.38
  6223.1  476.27  6843.3  477.78  7133.4  484.83  7273.4  492.94    7426  497.79
#Mann= 5 ,-1 , 0
  3673.5     .05       0  4597.6     .12       0  5012.2     .07       0
  5037.4     .12       0  5932.7     .05       0
Bank Sta=5012.2,5037.4
XS Rating Curve= 0 ,0
Exp/Cntr=0.3,0.1

Type RM Length L Ch R = 1 ,114700  ,1129,1129,1129
BEGIN DESCRIPTION:
Mapping XS 1688a760
END DESCRIPTION:
XS GIS Cut Line= 3
      2621807.36       6982900.4      2619963.66      6983577.47
      2618281.41      6984072.25
#Sta/Elev= 30
  3531.3  490.64  3781.4  488.75    4212  480.85  4242.5  477.97  4298.1  480.79
  4342.4  476.18  4486.8  473.46  4725.9  468.57  4769.9  472.02    4795  468.93
  4825.5  472.17  4911.6  471.06  4928.3  470.57  4942.1  465.97  4972.6     471
  4985.2  460.72  4987.7  460.22  5010.4  460.72  5013.5  468.53  5018.8  468.48
  5053.4   471.3  5213.7   471.3  5297.9  472.58  5450.3  473.37  5471.6  469.07
  5503.4  468.95  5527.5  474.25  6431.1   475.7  6722.9  483.14  7248.9  502.69
#Mann= 7 ,-1 , 0
  3531.3     .05       0  4486.8     .12       0  4985.2     .07       0
  5010.4     .12       0  5018.8     .05       0  5213.7     .12       0
  5297.9     .05       0
Bank Sta=4985.2,5010.4
XS Rating Curve= 0 ,0
Exp/Cntr=0.3,0.1

Type RM Length L Ch R = 1 ,113571  ,1761,1761,1761
BEGIN DESCRIPTION:
Big Brushy Creek 227.0
END DESCRIPTION:
XS GIS Cut Line= 3
      2621575.46      6982203.75      2620376.45      6982400.81
      2617512.98      6981787.08
#Sta/Elev= 30
  3784.9  488.64  4443.1  486.12  4813.6  470.65  4949.8  468.13  4959.6  457.93
  4962.2  457.43  4985.9  457.93  4990.3  462.63  4997.7  465.68  5031.1  463.08
  5051.6  468.94  5068.8  470.34  5378.9  468.13  5532.3  470.89  5662.2  468.94
  5690.9  467.15    5747  470.58  6370.9  471.88    6422  476.44  6544.8  470.79
  6585.7  474.67  6759.5  475.53  6885.6  479.08  7122.5  489.56  7158.4  493.37
    7172  491.45  7291.3  492.55    7322   498.8  7352.7  500.86  7928.5  506.31
#Mann= 5 ,-1 , 0
  3784.9     .05       0  4813.6     .12       0  4959.6     .07       0
  4985.9     .12       0  5662.2     .05       0
Bank Sta=4959.6,4985.9
XS Rating Curve= 0 ,0
Exp/Cntr=0.3,0.1

Type RM Length L Ch R = 1 ,111810  ,860,860,860
BEGIN DESCRIPTION:
Mapping XS 8314e18b
END DESCRIPTION:
XS GIS Cut Line= 4
      2621401.87      6981993.91      2620447.02      6981026.05
      2619726.02      6980879.69      2617256.89      6981342.89
#Sta/Elev= 30
  2904.7  488.69  2939.2  487.28  3766.5  485.06  4190.8  474.73  4285.7  474.84
  4558.7  469.73  4728.6  469.21  4809.9  468.14  4887.8  467.88  4920.7  465.85
  4938.8  468.34  4971.4  468.12  4989.8  465.04  4996.6  457.34  4999.2  456.84
  5023.8  457.34  5029.8  462.47  5034.9  463.63  5040.7  468.25  5063.8  468.32
  5878.4  470.02  6116.2  469.59  6271.8  471.25  6292.2  473.37  6424.4  471.98
    6750   475.7  6935.4  483.37  6953.5  482.72  7279.1  497.93  7512.2  504.58
#Mann= 9 ,-1 , 0
  2904.7     .05       0  4558.7     .12       0  4728.6     .05       0
  4809.9     .12       0  4996.6     .07       0  5023.8     .12       0
  5063.8     .05       0  5878.4     .12       0  6116.2     .05       0
Bank Sta=4996.6,5023.8
XS Rating Curve= 0 ,0
Exp/Cntr=0.3,0.1

Type RM Length L Ch R = 1 ,110950  ,133,133,133
BEGIN DESCRIPTION:
Mapping XS e25ea649
END DESCRIPTION:
XS GIS Cut Line= 4
      2621543.15      6981957.36      2619699.76      6980088.25
      2618962.41      6979333.75      2616846.06      6977114.58
#Sta/Elev= 30
    2347  487.35  3219.2  485.56    3693  477.89  4704.8  469.17  4783.4  468.26
  4920.7  466.67  4965.9  460.02  4966.4  455.27  4969.1  454.77  4993.7  455.27
  4994.2  459.36  5009.2   465.6  5015.3  468.19  5562.8  465.73  5806.6  464.63
  5888.4  465.15  5992.6  470.54  6019.4  467.55  7002.6     467  7016.7  463.38
  7610.9  470.49  7787.6   480.2  8084.9  484.94  8120.1  489.24  8127.3  486.72
  8134.2  489.38  8212.3  488.39  8261.6   491.8    8785  497.87  9093.7  495.12
#Mann= 11 ,-1 , 0
    2347     .05       0  4704.8     .12       0  4783.4     .05       0
  4920.7     .12       0  4966.4     .07       0  4993.7     .12       0
  5009.2     .05       0  5562.8     .12       0  5806.6     .05       0
  5888.4     .12       0  5992.6     .05       0
Bank Sta=4966.4,4993.7
XS Rating Curve= 0 ,0
Exp/Cntr=0.3,0.1

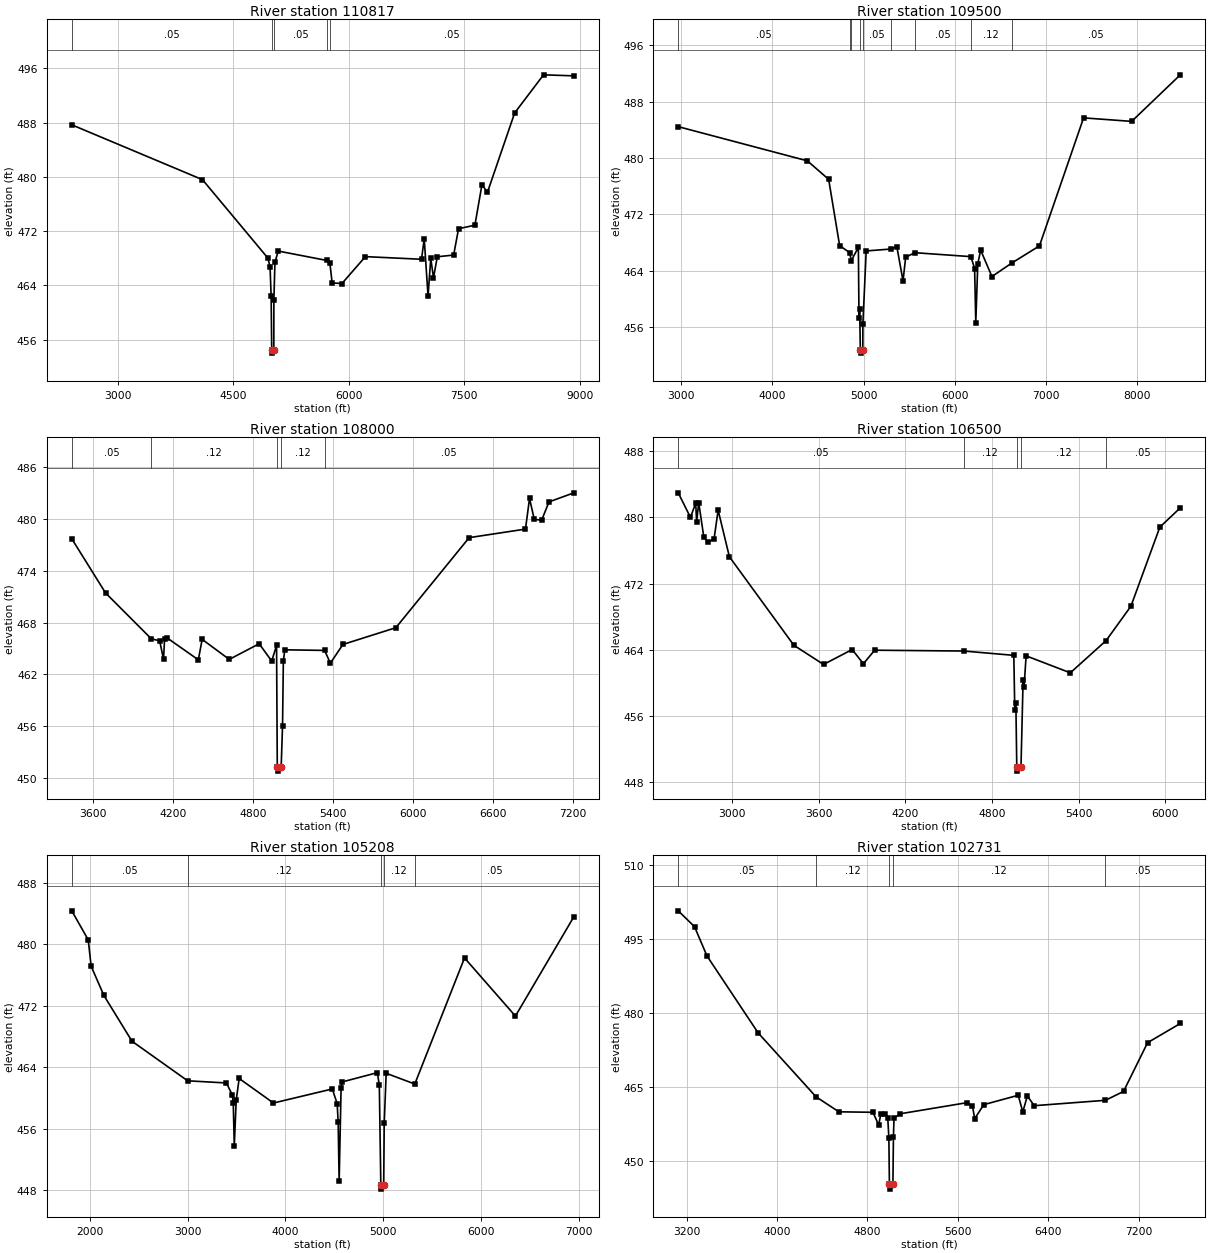
Type RM Length L Ch R = 1 ,110817  ,1317,1317,1317
BEGIN DESCRIPTION:
Mapping XS 38abbbdc
END DESCRIPTION:
XS GIS Cut Line= 5
      2621560.28      6981845.88       2620080.7       6980308.6
      2619759.22      6979977.68      2619166.64       6979371.1
      2617025.45      6977165.32
#Sta/Elev= 30
    2405  487.66  4101.8  479.58  4950.5  468.04  4978.8  466.77  4992.9   462.4
  5000.4  454.54  5003.1  454.04  5027.7  454.54  5028.2  461.83  5042.3   467.4
  5084.8  469.07    5719  467.68  5754.6  467.35  5784.9  464.38  5912.2  464.29
  6216.2  468.25  6944.7  467.86    6980  470.87  7029.6  462.44  7064.8  467.99
  7100.3  465.13  7149.7  468.23  7361.9  468.48  7425.5  472.36  7637.7  472.88
  7729.6  478.86  7800.3  477.71  8153.9  489.41  8528.7  495.02  8922.1  494.87
#Mann= 5 ,-1 , 0
    2405     .05       0  5000.4     .03       0  5027.7     .05       0
    5719     .12       0  5754.6     .05       0
Bank Sta=5000.4,5027.7
XS Rating Curve= 0 ,0
Exp/Cntr=0.3,0.1

Type RM Length L Ch R = 1 ,109500  ,1500,1500,1500
BEGIN DESCRIPTION:
Big Brushy Creek 219.0
END DESCRIPTION:
XS GIS Cut Line= 3
      2621725.97      6980360.97      2620290.81      6978925.29
      2617281.92      6977198.86
#Sta/Elev= 30
    2970  484.46  4384.2   479.6  4617.5  476.97  4737.7  467.55  4846.1  466.56
  4865.7  465.42  4942.8   467.3  4949.9  457.19  4956.9  458.47  4964.5  452.76
  4967.2  452.26  4991.8  452.76  4992.3  456.38  5028.6  466.79  5298.7  467.06
  5364.5  467.39  5432.1  462.53  5460.8  465.89  5560.2  466.54  6175.4  465.98
  6216.1  464.29  6228.8  456.57  6250.7  464.92    6282  466.91  6405.7  463.15
  6623.3  465.07  6926.3  467.51  7409.6  485.71    7936  485.21    8469  491.83
#Mann= 9 ,-1 , 0
    2970     .05       0  4846.1     .12       0  4865.7     .05       0
  4964.5     .03       0  4991.8     .05       0  5298.7     .12       0
  5560.2     .05       0  6175.4     .12       0  6623.3     .05       0
Bank Sta=4964.5,4991.8
XS Rating Curve= 0 ,0
Exp/Cntr=0.3,0.1

Type RM Length L Ch R = 1 ,108000  ,1500,1500,1500
BEGIN DESCRIPTION:
Big Brushy Creek 216.0
END DESCRIPTION:
XS GIS Cut Line= 3
      2620975.96      6978660.97      2619662.96      6977823.77
      2617596.33      6977050.97
#Sta/Elev= 30
  3442.8   477.7  3695.8  471.43  4038.7  466.12    4102  465.87  4130.6  463.74
  4138.4  466.06  4153.6  466.26  4391.5  463.68  4420.2  466.05  4623.3  463.73
  4847.6  465.54  4941.5  463.54  4977.9  465.34  4983.4  451.29  4986.2  450.79
  5012.5  451.29  5022.8  456.06  5028.8  463.51  5039.5  464.84  5338.1  464.77
  5381.1  463.29  5475.4  465.46  5872.2   467.4  6421.6  477.83  6843.8  478.82
  6874.2  482.37  6909.8  479.94  6965.1  479.86  7020.3  481.97  7206.4  483.02
#Mann= 5 ,-1 , 0
  3442.8     .05       0  4038.7     .12       0  4983.4     .07       0
  5012.5     .12       0  5338.1     .05       0
Bank Sta=4983.4,5012.5
XS Rating Curve= 0 ,0
Exp/Cntr=0.3,0.1

Type RM Length L Ch R = 1 ,106500  ,1292,1292,1292
BEGIN DESCRIPTION:
Big Brushy Creek 213.0
END DESCRIPTION:
XS GIS Cut Line= 3
      2621676.01      6978311.01      2620088.55      6976549.34
      2619226.03      6975861.02
#Sta/Elev= 30
  2628.6  482.95  2713.4  479.98  2749.3  481.72    2756  479.44  2770.2  481.78
  2805.4  477.64  2833.8  476.98  2876.4  477.38  2904.8  480.85  2982.5  475.24
  3428.7  464.56  3634.2  462.24  3832.3  464.04    3910  462.33  3988.2  463.96
  4605.9  463.86  4951.1  463.34  4957.8  456.77  4965.3  457.63  4971.7  449.87
  4974.5  449.37  5000.8  449.87  5015.5   460.4  5021.9   459.5  5036.3  463.28
  5342.2  461.23  5589.9  465.12  5761.7  469.27  5961.8  478.81  6103.5  481.14
#Mann= 5 ,-1 , 0
  2628.6     .05       0  4605.9     .12       0  4971.7     .07       0
  5000.8     .12       0  5589.9     .05       0
Bank Sta=4971.7,5000.8
XS Rating Curve= 0 ,0
Exp/Cntr=0.3,0.1

Type RM Length L Ch R = 1 ,105208  ,2477,2477,2477
BEGIN DESCRIPTION:
Big Brushy Creek 210.0
END DESCRIPTION:
XS GIS Cut Line= 3
      2623533.82      6975585.69      2620355.62      6975380.84
      2618409.45      6975291.96
#Sta/Elev= 30
  1815.2  484.34  1983.4  480.57  2013.4  477.13  2143.7  473.33  2430.8  467.38
    3000  462.23  3396.3  461.95  3456.4  460.39  3466.4  459.28  3476.5  453.74
  3496.5  459.73  3526.6  462.53  3877.3  459.34  4478.5  461.17  4528.6  459.26
  4538.7  456.83  4548.7  449.14  4568.7  461.34  4578.7  462.08  4939.5  463.29
  4959.5  461.63  4974.9  448.64  4977.8  448.14  5004.2  448.64  5009.6  456.74
  5029.6  463.21  5322.1  461.81  5830.5  478.21    6351  470.65  6948.2  483.57
#Mann= 5 ,-1 , 0
  1815.2     .05       0    3000     .12       0  4974.9     .07       0
  5004.2     .12       0  5322.1     .05       0
Bank Sta=4974.9,5004.2
XS Rating Curve= 0 ,0
Exp/Cntr=0.3,0.1

Type RM Length L Ch R = 1 ,102731  ,1731,1731,1731
BEGIN DESCRIPTION:
Big Brushy Creek 207.0
END DESCRIPTION:
XS GIS Cut Line= 3
      2623639.12      6974006.43      2621740.71      6974214.63
      2619240.08      6973806.57
#Sta/Elev= 30
  3125.8  500.64  3269.8  497.43  3380.4  491.49  3833.1   475.9  4345.5  462.95
  4547.4  459.91  4849.2  459.81  4899.5  457.23  4919.6  459.51  4955.6  459.42
    4980  458.73    4990  454.62  4994.7  445.24  4997.7  444.24  5025.7  445.24
  5030.3  454.81  5035.4  458.59  5092.6  459.52  5678.7  461.75  5729.4  461.14
  5749.6  458.52  5829.9  461.36  6134.6  463.26  6175.2  459.89  6215.7  463.12
  6276.5  461.15  6906.6  462.24  7066.8  464.04  7279.6  473.92  7569.3  477.81
#Mann= 5 ,-1 , 0
  3125.8     .05       0  4345.5     .12       0  4994.7     .07       0
  5025.7     .12       0  6906.6     .05       0
Bank Sta=4994.7,5025.7
XS Rating Curve= 0 ,0
Exp/Cntr=0.3,0.1

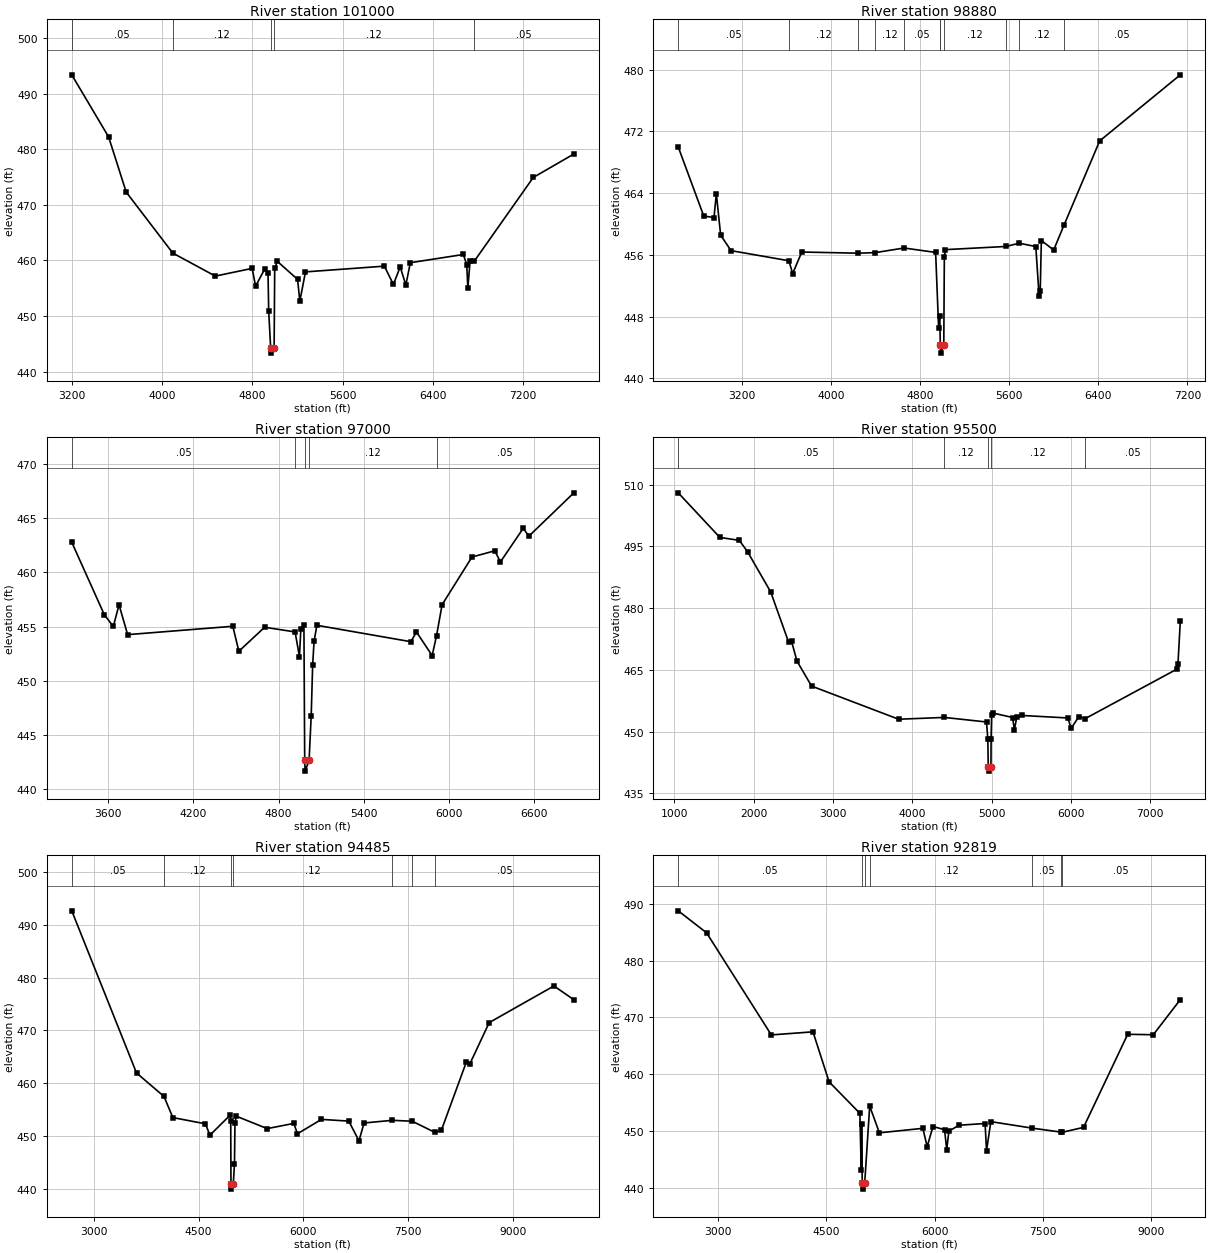
Type RM Length L Ch R = 1 ,101000  ,2120,2120,2120
BEGIN DESCRIPTION:
Big Brushy Creek 202.0
END DESCRIPTION:
XS GIS Cut Line= 3
        2623576.        6973461.      2621975.99      6972627.27
      2619326.04        6972511.
#Sta/Elev= 30
  3195.8  493.39  3522.8  482.22  3678.9  472.29  4092.8  461.31    4470  457.17
    4797  458.56  4827.4  455.35  4909.8   458.5  4937.9  457.72  4943.6  450.95
    4961  444.31    4964  443.31    4992  444.31  4997.2  458.56    5020  459.83
  5200.2  456.58  5220.2  452.66  5270.3  457.93  5970.9  458.96    6051  455.66
  6111.1  458.84  6161.1  455.56  6201.1  459.58  6671.6  461.06  6701.6  459.25
  6711.6  455.01  6731.7  459.94  6767.1  459.81  7292.2  474.92  7652.5  479.14
#Mann= 5 ,-1 , 0
  3195.8     .05       0  4092.8     .12       0    4961     .07       0
    4992     .12       0  6767.1     .05       0
Bank Sta=4961,4992
XS Rating Curve= 0 ,0
Exp/Cntr=0.3,0.1

Type RM Length L Ch R = 1 ,98880   ,1880,1880,1880
BEGIN DESCRIPTION:
Big Brushy Creek 199.0
END DESCRIPTION:
XS GIS Cut Line= 3
      2623819.56      6971237.88      2621152.58      6970656.34
      2619385.57      6970842.09
#Sta/Elev= 30
  2629.9  469.97  2858.7  461.03  2950.8  460.82  2971.9  463.91  3010.7  458.54
  3103.7  456.54  3622.9  455.23    3657  453.57  3738.9  456.36  4242.6  456.21
  4397.6  456.28  4656.7  456.88  4940.1  456.31  4967.1   446.5  4976.8  448.13
  4982.3  444.26  4985.3  443.26  5013.3  444.26  5018.3  455.72    5028  456.67
  5570.3  457.08  5690.5   457.5  5839.2  457.07  5868.9  450.63    5879  451.34
    5889  457.85  5999.6  456.62  6093.1  459.87  6412.7  470.76  7136.3  479.32
#Mann= 11 ,-1 , 0
  2629.9     .05       0  3622.9     .12       0  4242.6     .05       0
  4397.6     .12       0  4656.7     .05       0  4976.8     .12       0
  4982.3     .07       0  5013.3     .12       0  5570.3     .05       0
  5690.5     .12       0  6093.1     .05       0
Bank Sta=4982.3,5013.3
XS Rating Curve= 0 ,0
Exp/Cntr=0.3,0.1

Type RM Length L Ch R = 1 ,97000   ,1500,1500,1500
BEGIN DESCRIPTION:
Big Brushy Creek 194.0
END DESCRIPTION:
XS GIS Cut Line= 3
      2623430.54      6969623.05      2621876.14      6969045.87
      2620000.09      6969196.72
#Sta/Elev= 30
  3341.9  462.77  3570.8  456.11  3634.8  455.01  3675.1  457.01  3735.9  454.26
  4477.3  455.03  4520.1  452.73  4701.5  454.94  4916.6  454.51  4947.2  452.24
  4957.5  454.82  4978.8  455.12  4984.3  442.69  4987.3  441.69  5015.3  442.69
  5030.2   446.8  5040.3  451.42  5050.3  453.66  5070.4  455.12  5732.5  453.61
  5772.6   454.5    5883  452.33  5914.2  454.18  5953.2  457.02  6163.9  461.41
  6324.4  461.98  6364.5  460.96    6525  464.05  6565.2  463.33  6882.1  467.32
#Mann= 5 ,-1 , 0
  3341.9     .05       0  4916.6     .12       0  4984.3     .07       0
  5015.3     .12       0  5914.2     .05       0
Bank Sta=4984.3,5015.3
XS Rating Curve= 0 ,0
Exp/Cntr=0.3,0.1

Type RM Length L Ch R = 1 ,95500   ,1015,1015,1015
BEGIN DESCRIPTION:
Big Brushy Creek 191.0
END DESCRIPTION:
XS GIS Cut Line= 3
      2625875.96      6968760.99      2622078.09       6967667.7
      2619726.01        6968011.
#Sta/Elev= 30
  1047.9  507.98  1572.7  497.15  1817.9  496.44    1922  493.67  2213.3  483.92
  2438.3  471.79  2477.2  471.89  2544.6  467.13  2728.6  461.06  3826.3  453.01
    4402  453.45  4934.2  452.34  4950.1  448.22  4956.3  441.41  4959.9  440.41
  4989.9  441.41  4991.8  448.17  4998.5  454.02  5012.2  454.52  5262.5  453.43
  5285.1  450.46  5315.4  453.49  5386.1  453.92  5957.4  453.32  6002.6  450.82
  6097.3  453.65  6179.1  453.17  7336.6   465.2  7347.1  466.33    7377  476.86
#Mann= 5 ,-1 , 0
  1047.9     .05       0    4402     .12       0  4956.3     .07       0
  4989.9     .12       0  6179.1     .05       0
Bank Sta=4956.3,4989.9
XS Rating Curve= 0 ,0
Exp/Cntr=0.3,0.1

Type RM Length L Ch R = 1 ,94485   ,1666,1666,1666
BEGIN DESCRIPTION:
Big Brushy Creek 190.0
END DESCRIPTION:
XS GIS Cut Line= 3
      2624925.96        6967161.      2622315.83      6966861.79
      2617931.78       6965615.8
#Sta/Elev= 30
  2684.4  492.65  3610.9  461.92  4003.8  457.47    4131  453.46  4596.8  452.28
  4661.1  450.12  4949.1   453.9  4959.2  452.74  4962.5   440.9  4966.1   439.9
  4996.1   440.9  5012.9  444.73  5019.6  452.49  5039.7  453.72  5481.1  451.37
  5862.4  452.36  5913.6  450.39  6257.5  453.12  6648.5  452.79  6794.4  449.05
  6867.4  452.44  7271.9  452.94  7556.3  452.77  7880.3  450.66  7972.8  451.03
  8331.9  464.03  8378.3  463.55  8657.6  471.46  9584.2  478.41  9869.3   475.8
#Mann= 7 ,-1 , 0
  2684.4     .05       0  4003.8     .12       0  4962.5     .07       0
  4996.1     .12       0  7271.9     .05       0  7556.3     .12       0
  7880.3     .05       0
Bank Sta=4962.5,4996.1
XS Rating Curve= 0 ,0
Exp/Cntr=0.3,0.1

Type RM Length L Ch R = 1 ,92819   ,2081,2081,2081
BEGIN DESCRIPTION:
Big Brushy Creek 187.0
END DESCRIPTION:
XS GIS Cut Line= 3
      2625266.29      6965870.72      2623366.22      6965449.01
      2618369.13      6965002.53
#Sta/Elev= 30
  2445.7  488.78  2838.5  484.91  3736.7  466.92  4314.5  467.46    4538  458.65
  4964.5  453.11  4983.6  443.19  4988.6  451.21  4997.8  440.75  5001.4  439.75
  5031.5  440.75    5101  454.38  5235.6  449.67    5838  450.46  5898.2  447.25
  5978.5  450.78  6139.2  450.23  6169.3  446.71  6199.4  449.97  6340.5  451.01
  6701.4  451.31  6721.5  446.53  6781.1  451.64  7357.1  450.49  7757.4  449.79
  7770.8  449.76  8066.8  450.63  8679.2  467.03  9034.3  466.95    9409  473.14
#Mann= 7 ,-1 , 0
  2445.7     .05       0  4997.8     .03       0  5031.5     .05       0
    5101     .12       0  7357.1     .05       0  7757.4     .12       0
  7770.8     .05       0
Bank Sta=4997.8,5031.5
XS Rating Curve= 0 ,0
Exp/Cntr=0.3,0.1