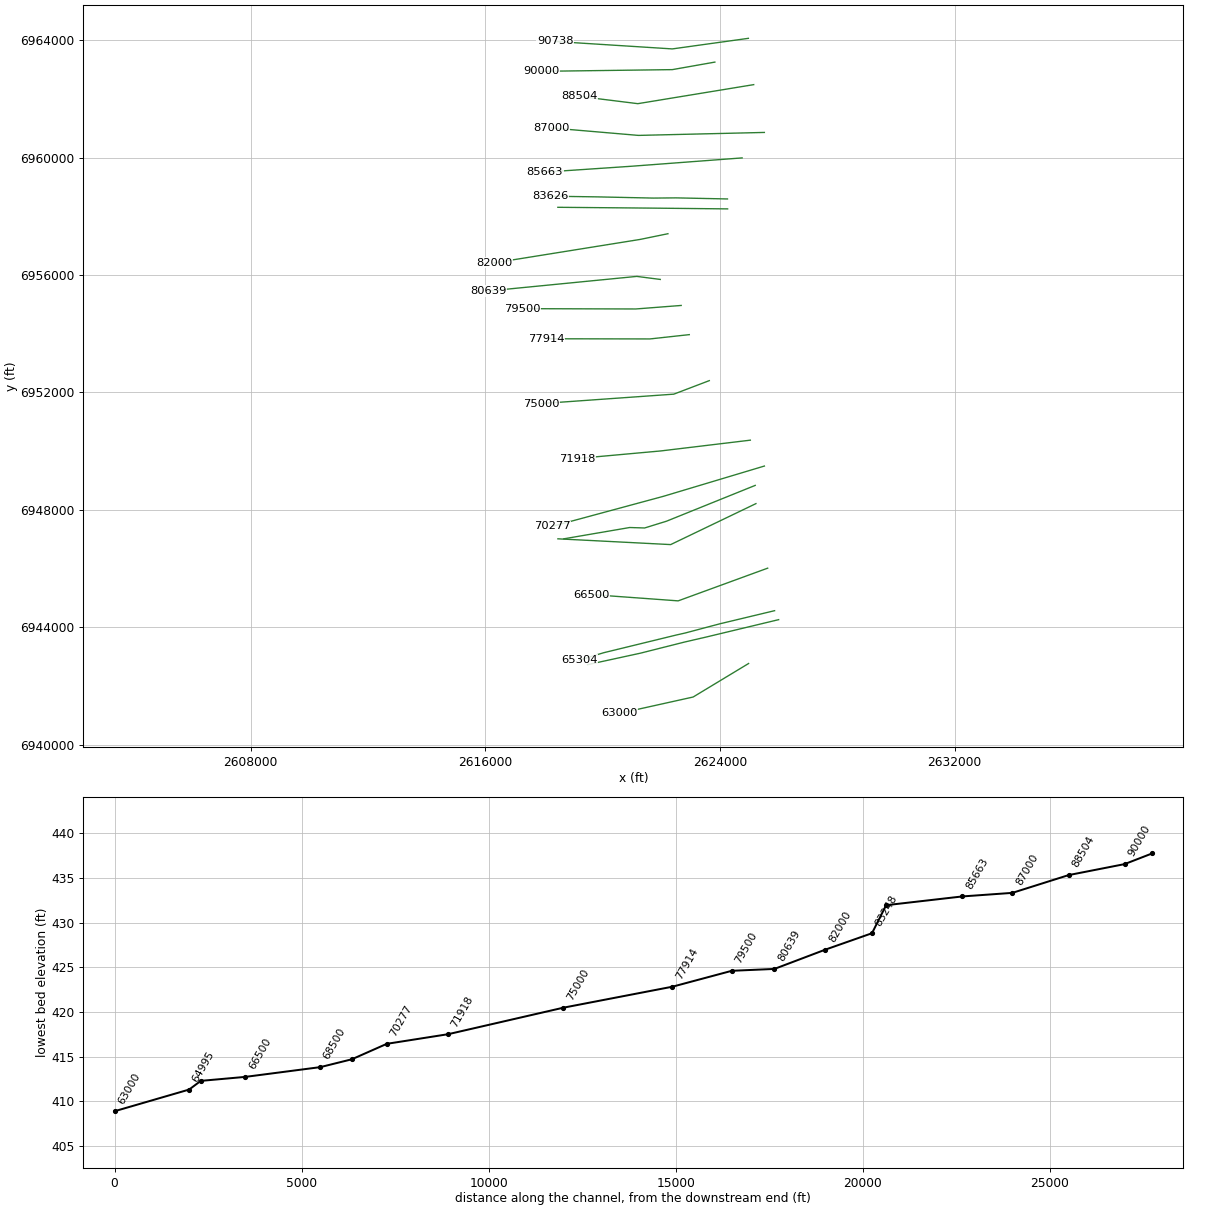
HEC-RAS study Big Brushy Creek.prj: Big Brushy Creek Base Level Engineering

--- Big Brushy Creek.g01 (geometry) --- (continued)

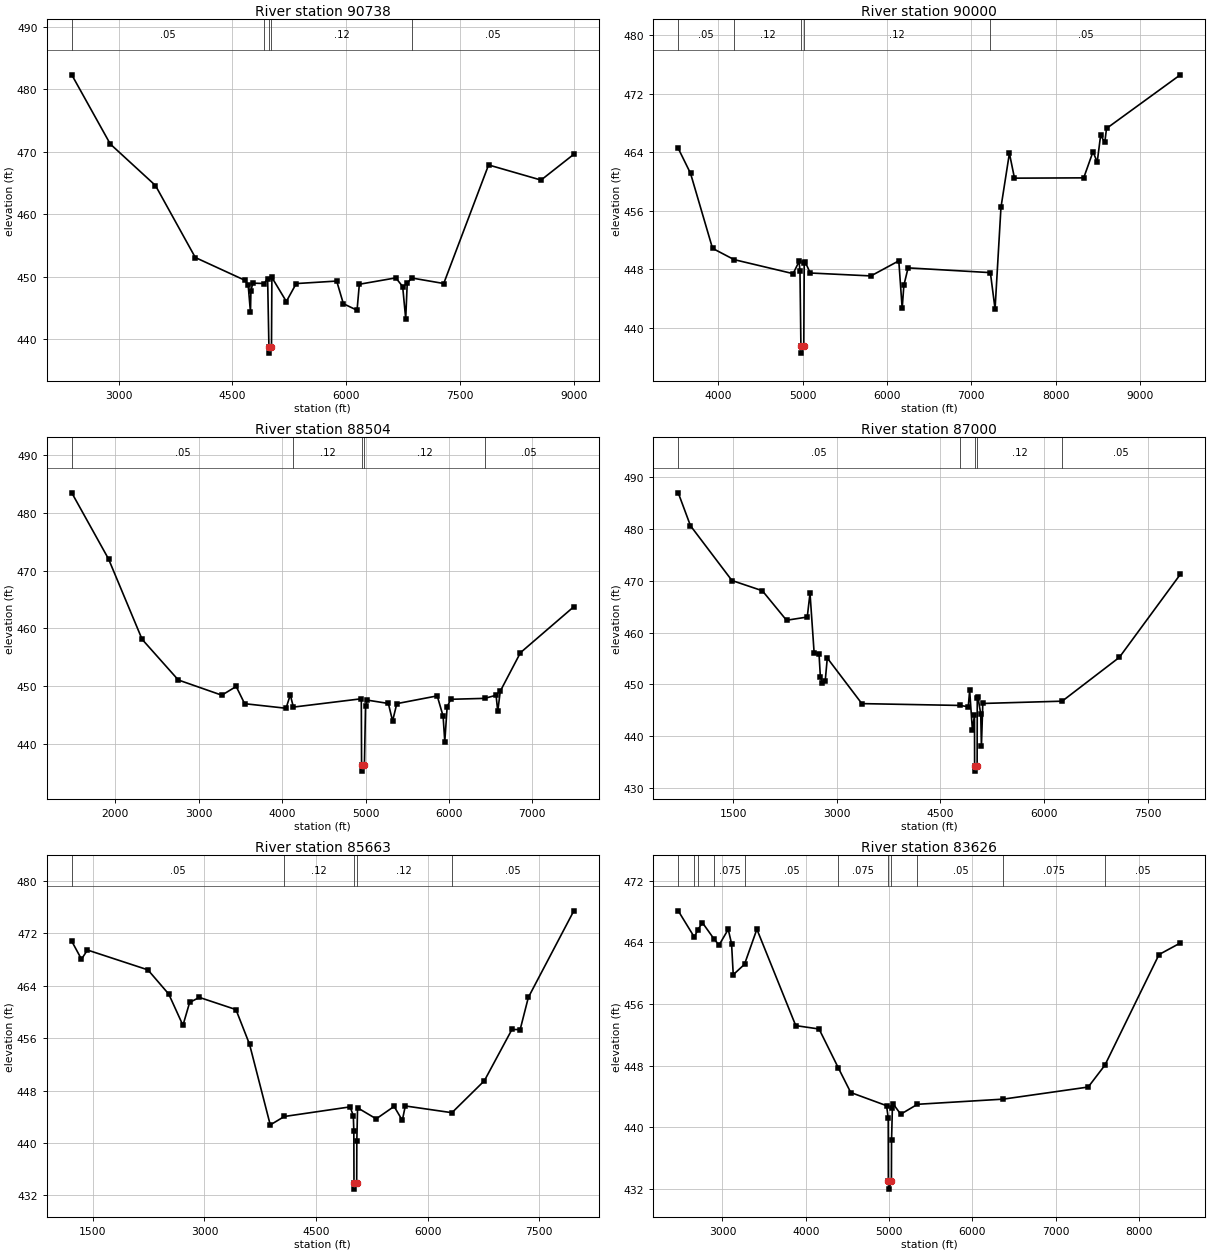
Type RM Length L Ch R = 1 ,90738   ,738,738,738
BEGIN DESCRIPTION:
Big Brushy Creek 184.0
END DESCRIPTION:
XS GIS Cut Line= 3
      2624968.57      6964071.27       2622375.6      6963710.83
      2618384.53      6963964.16
#Sta/Elev= 30
  2382.1  482.28  2889.5  471.21  3485.2  464.57  4010.2  453.05  4666.4  449.39
  4706.8  448.65  4737.1  444.31  4743.4  447.71  4767.4  448.95  4916.4  448.89
  4963.4  449.66  4980.4  438.75    4984  437.75  5014.2  438.75  5019.6  449.86
    5210  446.01  5340.3  448.88  5873.6  449.28  5961.5  445.66  6141.9  444.61
    6172  448.77  6652.9  449.79  6743.1   448.4  6783.2  443.23  6803.2  448.96
  6863.6  449.77  7284.2  448.89  7875.4  467.86  8566.8  465.44  8999.1  469.57
#Mann= 5 ,-1 , 0
  2382.1     .05       0  4916.4     .12       0  4980.4     .07       0
  5014.2     .12       0  6863.6     .05       0
Bank Sta=4980.4,5014.2
XS Rating Curve= 0 ,0
Exp/Cntr=0.3,0.1

Type RM Length L Ch R = 1 ,90000   ,1496,1496,1496
BEGIN DESCRIPTION:
Big Brushy Creek 180.0
END DESCRIPTION:
XS GIS Cut Line= 3
      2623826.03      6963261.01      2622376.11      6963004.69
      2617901.88       6962946.8
#Sta/Elev= 30
  3527.6  464.53  3673.1  461.12  3933.8  450.87  4188.8  449.33  4888.4  447.41
  4959.5  449.09  4969.6  447.71  4980.6  437.55  4984.2  436.55  5014.5  437.55
  5020.1  448.82  5030.1  449.06  5090.1   447.5  5810.2   447.1  6140.2  449.16
  6180.2  442.65  6200.2  445.82  6250.2   448.2  7224.9  447.55  7280.3  442.58
  7350.3  456.47  7450.3  463.86  7510.3  460.46  8330.4   460.5  8440.4  464.07
  8490.4  462.65  8530.4   466.3  8580.4  465.37  8600.4  467.25  9474.6  474.58
#Mann= 5 ,-1 , 0
  3527.6     .05       0  4188.8     .12       0  4980.6     .07       0
  5014.5     .12       0  7224.9     .05       0
Bank Sta=4980.6,5014.5
XS Rating Curve= 0 ,0
Exp/Cntr=0.3,0.1

Type RM Length L Ch R = 1 ,88504   ,1504,1504,1504
BEGIN DESCRIPTION:
Big Brushy Creek 176.0
END DESCRIPTION:
XS GIS Cut Line= 3
      2625150.65      6962492.94      2621200.62      6961844.42
      2619200.81      6962092.92
#Sta/Elev= 30
  1478.7  483.44  1919.2  472.01  2321.7  458.11  2755.6  451.08  3277.1  448.45
  3449.4  449.96  3550.7  446.98  4047.2  446.19    4098  448.52  4134.8  446.39
  4949.2  447.83  4952.5  436.32  4956.2  435.32  4986.4  436.32  4999.9   446.6
  5020.1   447.6  5273.5  447.02  5324.2  443.99  5374.8  446.99  5859.1  448.33
  5929.7  444.83  5949.8  440.41    5978   446.4  6020.3  447.74  6427.7   447.9
  6564.5  448.44  6584.7  445.65  6614.9  449.14  6856.7   455.8  7496.8  463.75
#Mann= 5 ,-1 , 0
  1478.7     .05       0  4134.8     .12       0  4952.5     .07       0
  4986.4     .12       0  6427.7     .05       0
Bank Sta=4952.5,4986.4
XS Rating Curve= 0 ,0
Exp/Cntr=0.3,0.1

Type RM Length L Ch R = 1 ,87000   ,1337,1337,1337
BEGIN DESCRIPTION:
Big Brushy Creek 174.0
END DESCRIPTION:
XS GIS Cut Line= 3
        2625513.      6960863.47      2621220.88      6960762.58
      2618257.51      6961016.12
#Sta/Elev= 30
   706.7  486.88   883.7  480.55  1483.9  470.01    1924  468.04  2274.1  462.36
  2574.2  462.98  2614.2  467.57  2674.2     456  2744.3  455.93  2764.3  451.41
  2794.3  450.25  2834.3  450.71  2864.3  455.09  3364.4  446.32  4783.8  445.97
  4904.9  445.72  4924.9  448.85  4964.9  441.21  4994.9  444.13  4996.8  434.33
  5000.9  433.33  5033.1  434.33    5035  447.31  5045.1  447.58  5085.2  444.34
  5095.2  438.12  5115.3  446.35    6264  446.79  7092.5  455.23  7974.2  471.19
#Mann= 5 ,-1 , 0
   706.7     .05       0  4783.8     .12       0  4996.8     .07       0
  5033.1     .12       0    6264     .05       0
Bank Sta=4996.8,5033.1
XS Rating Curve= 0 ,0
Exp/Cntr=0.3,0.1

Type RM Length L Ch R = 1 ,85663   ,2037,2037,2037
BEGIN DESCRIPTION:
Big Brushy Creek 171.0
END DESCRIPTION:
XS GIS Cut Line= 3
      2624756.06      6959995.41      2620983.06        6959711.
      2618026.02        6959511.
#Sta/Elev= 30
  1216.3  470.81  1346.7  468.07    1427  469.47  2239.3  466.44    2520  462.73
  2710.6  457.96  2800.4  461.46  2931.2  462.23  3422.6  460.37  3605.6  455.06
  3883.9  442.74  4072.8  444.03  4956.9   445.5    5000  444.15  5007.1  441.79
    5009  433.93  5013.1  432.93  5045.3  433.93  5047.2  440.23  5057.2  445.36
  5307.8  443.67  5548.3  445.57  5658.6  443.44  5698.7  445.64  6325.4  444.61
  6761.1  449.49  7131.9  457.33  7242.2  457.31  7352.4  462.23  7963.8  475.46
#Mann= 5 ,-1 , 0
  1216.3     .05       0  4072.8     .12       0    5009     .07       0
  5045.3     .12       0  6325.4     .05       0
Bank Sta=5009,5045.3
XS Rating Curve= 0 ,0
Exp/Cntr=0.3,0.1

Type RM Length L Ch R = 1 ,83626   ,378,378,378
BEGIN DESCRIPTION:
Big Brushy Creek 167.0
END DESCRIPTION:
XS GIS Cut Line= 5
      2624256.05      6958596.11      2622512.49       6958632.9
      2621725.77      6958626.08      2619793.31      6958667.63
      2618230.48      6958689.85
#Sta/Elev= 30
  2469.3   468.1    2662  464.69    2705  465.64  2759.4  466.56  2903.2  464.38
  2959.5  463.66  3069.5  465.69  3109.5  463.82  3129.5   459.8  3264.7  461.15
  3413.3  465.71  3879.7  453.19  4159.7  452.75  4389.5  447.73  4539.8   444.5
  4969.8  442.79  4989.8   441.2  4991.5  432.95  4995.8  431.95    5028  432.95
  5029.8  438.29  5039.8   442.5  5049.8  443.01  5139.8  441.68  5340.9  442.97
  6370.9  443.64  7390.3  445.21  7590.7  448.05  8240.4  462.42  8495.9  463.92
#Mann= 11 ,-1 , 0
  2469.3     .05       0    2662    .075       0    2705     .05       0
  2903.2    .075       0  3264.7     .05       0  4389.5    .075       0
  4991.5     .07       0    5028    .075       0  5340.9     .05       0
  6370.9    .075       0  7590.7     .05       0
Bank Sta=4991.5,5028
XS Rating Curve= 0 ,0
Exp/Cntr=0.3,0.1

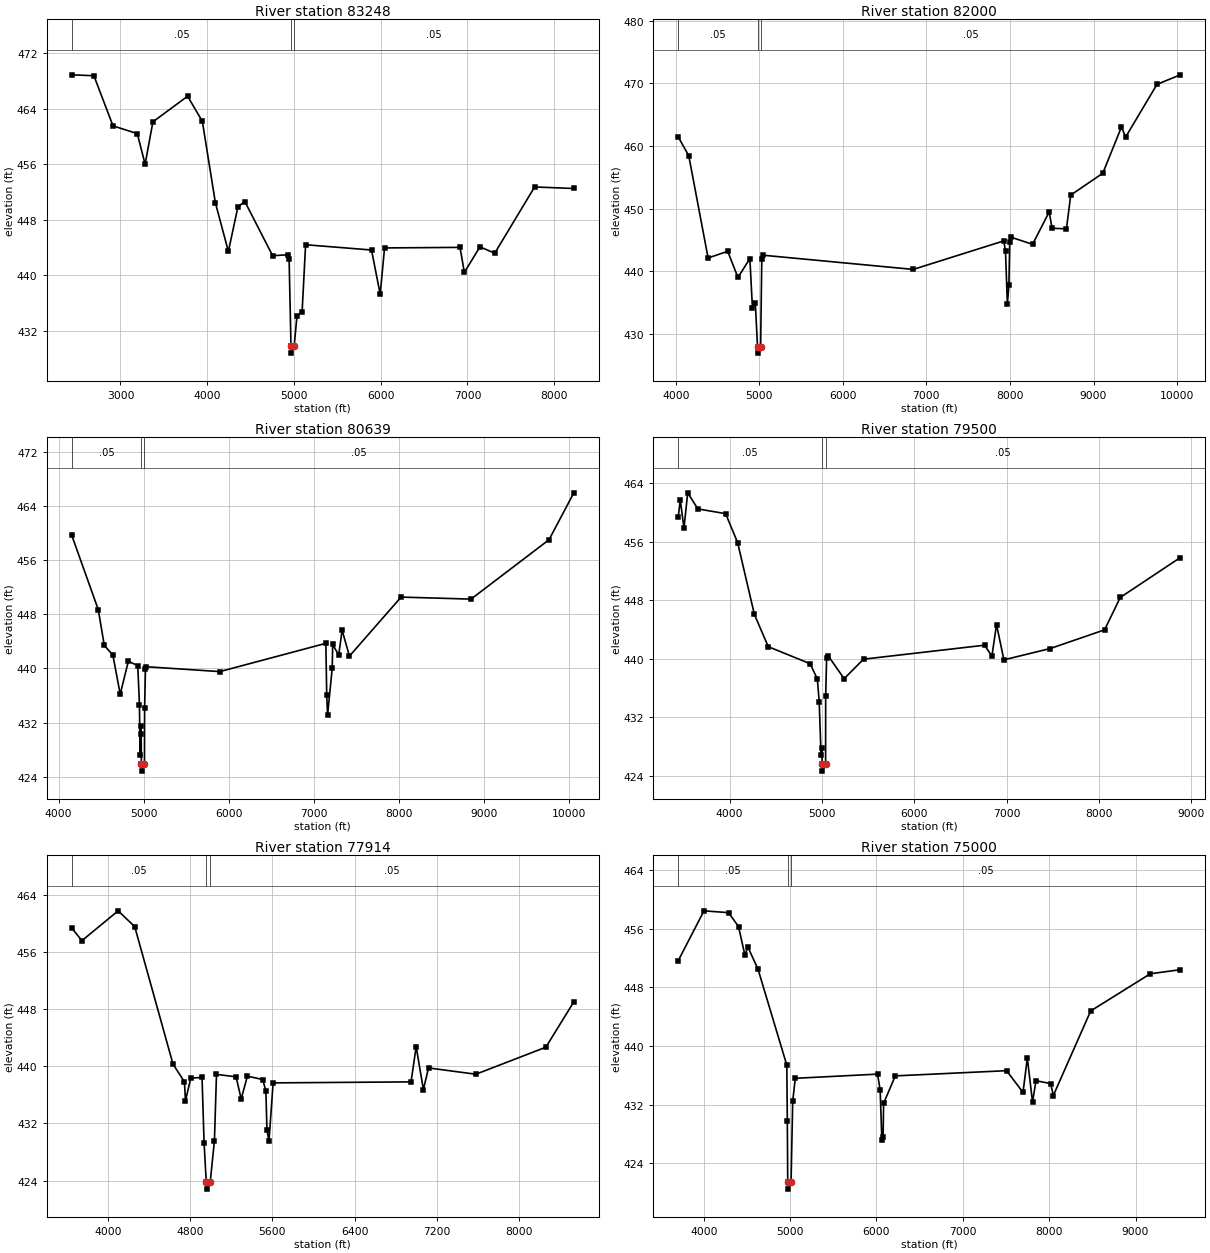
Type RM Length L Ch R = 1 ,83248   ,1248,1248,1248
BEGIN DESCRIPTION:
Big Brushy Creek 166.0
END DESCRIPTION:
XS GIS Cut Line= 3
      2624261.23      6958257.57      2621699.97      6958283.81
      2618473.89      6958311.72
#Sta/Elev= 30
  2438.6  468.89  2693.8  468.76  2913.9  461.54  3193.9  460.42  3283.9  456.02
  3373.9  462.12  3773.9  465.81  3943.9  462.19  4093.9  450.47  4243.9  443.45
  4353.9  449.88  4433.9  450.64    4754  442.84    4934  442.98    4944  442.31
  4965.7  429.81  4969.9  428.81  5002.3  429.81    5034  434.12    5094   434.8
    5134  444.42    5894  443.66    5994  437.28    6044  443.96    6914  444.04
    6964  440.44    7144  444.12  7314.1   443.2  7774.1  452.74  8226.2  452.52
#Mann= 3 ,-1 , 0
  2438.6     .05       0  4965.7     .05       0  5002.3     .05       0
Bank Sta=4965.7,5002.3
XS Rating Curve= 0 ,0
Exp/Cntr=0.3,0.1

Type RM Length L Ch R = 1 ,82000   ,1361,1361,1361
BEGIN DESCRIPTION:
Big Brushy Creek 164.0
END DESCRIPTION:
XS GIS Cut Line= 3
        2622226.        6957411.      2621275.57      6957216.16
      2616300.28      6956417.42
#Sta/Elev= 30
  4029.8  461.44  4155.8  458.45  4387.1  442.14  4621.9  443.21  4744.4  439.04
  4887.3  442.04  4917.9  434.18  4952.3  434.96  4978.8  427.97  4983.1  426.97
  5015.6  427.97  5029.9  442.02  5040.1  442.59  6842.9  440.32  7926.6  444.87
  7946.8  443.19  7969.1  434.77  7987.3  437.78  7997.5  444.64  8007.6  445.48
  8270.9  444.32  8469.6  449.49  8503.9  446.88    8676  446.79  8727.4  452.17
  9111.5  455.66  9334.4  463.03    9385  461.43  9759.7  469.83   10039  471.35
#Mann= 3 ,-1 , 0
  4029.8     .05       0  4978.8     .03       0  5015.6     .05       0
Bank Sta=4978.8,5015.6
XS Rating Curve= 0 ,0
Exp/Cntr=0.3,0.1

Type RM Length L Ch R = 1 ,80639   ,1139,1139,1139
BEGIN DESCRIPTION:
Big Brushy Creek 162.0
END DESCRIPTION:
XS GIS Cut Line= 3
      2621965.07      6955852.84      2621164.59      6955956.43
      2616095.48      6955458.09
#Sta/Elev= 30
    4154  459.68  4465.6  448.69  4536.2   443.4  4637.1  441.97  4723.4  436.18
  4818.6  441.06  4929.5  440.42  4949.6  434.62  4956.3  427.24  4965.1  431.48
  4970.2  430.34  4971.5  425.81  4975.8  424.81  5008.3  425.81    5010  434.16
    5020  439.92  5030.1  440.25  5894.2  439.53  7140.2  443.71  7150.2   436.1
  7160.3  433.09  7214.9  440.03  7220.6  443.55  7290.9  441.97  7331.1  445.65
  7417.5  441.82  8024.4  450.55  8846.4  450.25  9762.8  459.03 10054.7  465.97
#Mann= 3 ,-1 , 0
    4154     .05       0  4971.5     .04       0  5008.3     .05       0
Bank Sta=4971.5,5008.3
XS Rating Curve= 0 ,0
Exp/Cntr=0.3,0.1

Type RM Length L Ch R = 1 ,79500   ,1586,1586,1586
BEGIN DESCRIPTION:
Big Brushy Creek 159.0
END DESCRIPTION:
XS GIS Cut Line= 3
      2622677.95       6954965.9      2621126.27      6954845.97
      2617245.69      6954856.52
#Sta/Elev= 30
  3443.7  459.34  3465.7   461.7  3505.8  457.81    3546  462.66  3656.3  460.46
  3956.8  459.81  4086.9  455.85  4268.1  446.04  4418.5  441.62  4872.3  439.29
  4950.1  437.19  4970.2  434.12  4990.2  426.77  4999.8   427.7    5001   425.6
  5005.7   424.6  5039.5   425.6  5040.3  434.85  5050.3  440.02  5070.3  440.32
  5240.3  437.24  5450.3  439.91  6760.3  441.82  6840.3  440.32  6890.3  444.64
  6970.3  439.82  7470.3  441.36  8060.3  443.92  8230.3  448.35  8880.6  453.81
#Mann= 3 ,-1 , 0
  3443.7     .05       0    5001     .04       0  5039.5     .05       0
Bank Sta=5001,5039.5
XS Rating Curve= 0 ,0
Exp/Cntr=0.3,0.1

Type RM Length L Ch R = 1 ,77914   ,2914,2914,2914
BEGIN DESCRIPTION:
Big Brushy Creek 154.0
END DESCRIPTION:
XS GIS Cut Line= 3
        2622954.      6953971.11      2621612.69      6953824.55
      2618084.19      6953830.48
#Sta/Elev= 30
  3650.7  459.31  3749.3  457.55  4101.4  461.72  4262.3  459.51  4634.5  440.28
  4745.2  437.83  4755.2  435.16  4806.5  438.34  4916.2  438.43  4936.3  429.26
  4957.2  423.82  4961.9  422.82  4995.8  423.82  5036.7   429.6  5056.7  438.86
  5246.7  438.52  5296.7  435.42  5356.7  438.61  5506.7  438.14  5536.7  436.48
  5546.7  431.14  5566.7   429.5  5606.7  437.67  6946.7  437.81  6996.7  442.73
  7066.7  436.74  7116.7  439.76  7576.7  438.88  8256.7  442.66  8528.5     449
#Mann= 3 ,-1 , 0
  3650.7     .05       0  4957.2     .03       0  4995.8     .05       0
Bank Sta=4957.2,4995.8
XS Rating Curve= 0 ,0
Exp/Cntr=0.3,0.1

Type RM Length L Ch R = 1 ,75000   ,3082,3082,3082
BEGIN DESCRIPTION:
Big Brushy Creek 150.0
END DESCRIPTION:
XS GIS Cut Line= 3
      2623636.29      6952403.41      2622426.08      6951942.22
      2617919.22      6951622.27
#Sta/Elev= 30
  3704.9  451.64    4003  458.44  4287.9  458.19  4402.9  456.29  4475.7  452.45
  4512.6  453.46  4627.6  450.51    4962  437.38    4968  429.73  4972.7  421.47
  4977.4  420.47  5011.4  421.47  5030.2  432.44  5060.2  435.59  6012.6  436.16
  6042.7  434.01  6062.7  427.21  6077.1  427.52  6082.8  432.17  6217.9  435.92
  7506.4  436.63  7696.9  433.67    7747  438.35  7807.1  432.35  7847.2  435.26
  8017.7  434.87  8047.7  433.24  8480.4  444.78  9170.6  449.85  9518.2  450.41
#Mann= 3 ,-1 , 0
  3704.9     .05       0  4972.7     .04       0  5011.4     .05       0
Bank Sta=4972.7,5011.4
XS Rating Curve= 0 ,0
Exp/Cntr=0.3,0.1

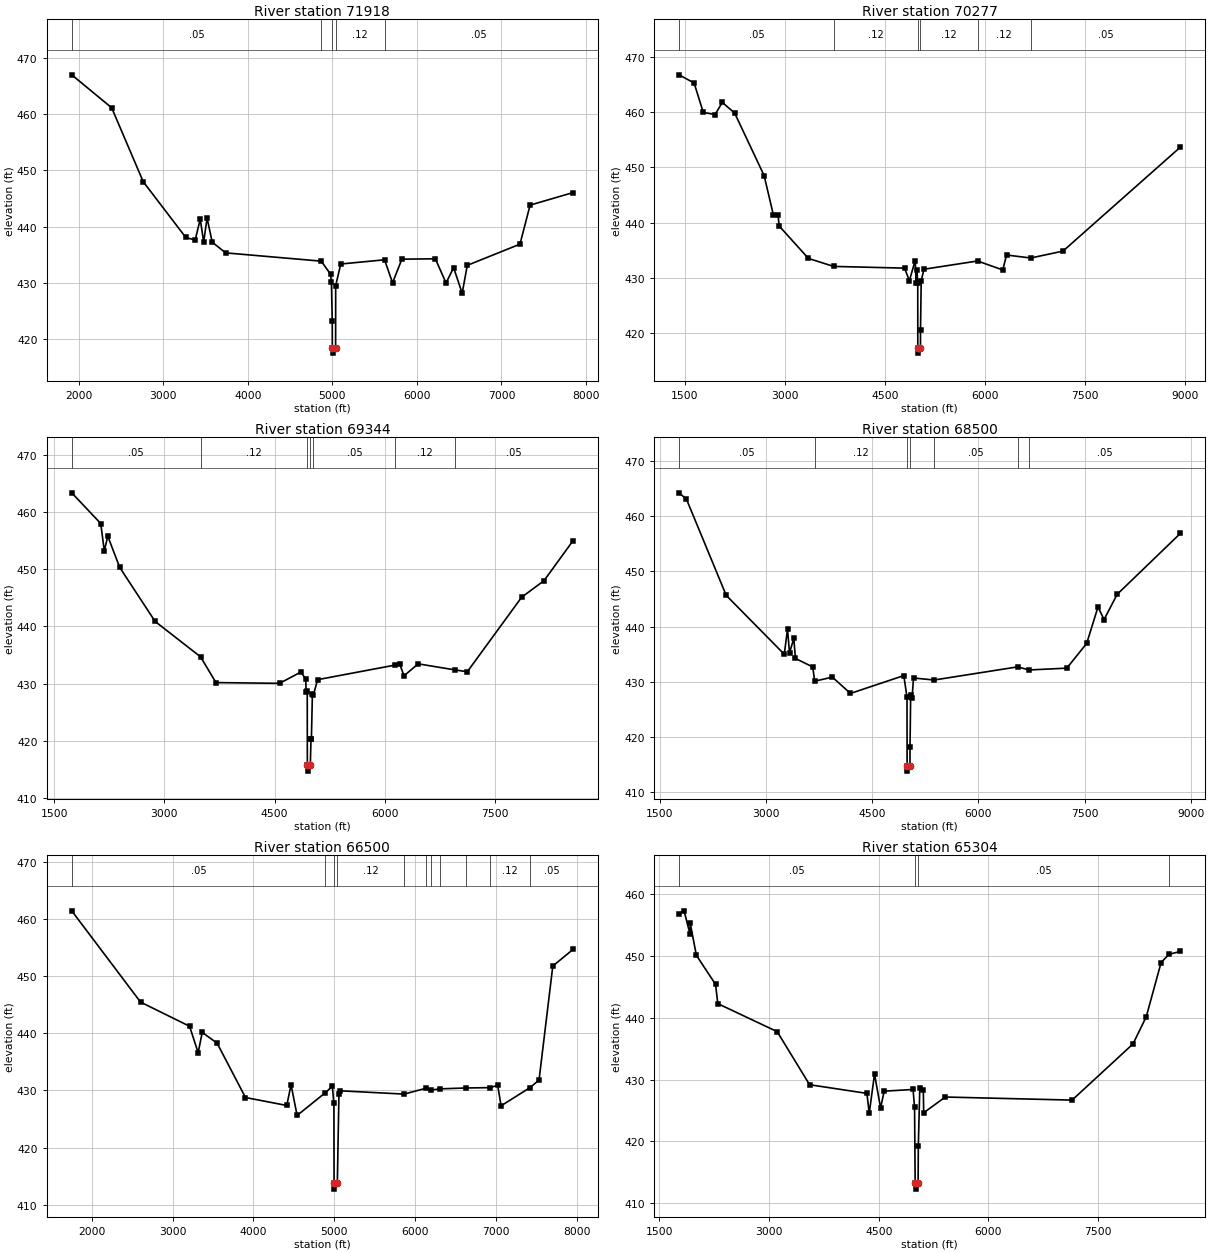
Type RM Length L Ch R = 1 ,71918   ,1641,1641,1641
BEGIN DESCRIPTION:
Big Brushy Creek 145.0
END DESCRIPTION:
XS GIS Cut Line= 3
      2625035.16      6950373.89      2621975.62      6950005.84
      2619140.13      6949748.96
#Sta/Elev= 30
  1918.4  466.97  2390.9  461.11  2763.6  447.98  3267.2  438.06    3378   437.6
  3438.4  441.32  3478.7  437.23    3519  441.51  3579.9  437.22  3739.2  435.32
  4869.2  433.85  4979.5  431.52  4989.5  430.07  4999.3  423.24  5000.3   418.5
    5005   417.5  5039.2   418.5  5039.8  429.49    5100  433.34  5617.9  434.09
  5712.5     430    5823   434.2  6218.5  434.27  6345.1  429.97  6434.8  432.69
  6535.9  428.14  6596.1   433.1  7219.3  436.87  7339.2  443.81  7847.1  446.04
#Mann= 5 ,-1 , 0
  1918.4     .05       0  4869.2     .12       0  5000.3     .07       0
  5039.2     .12       0  5617.9     .05       0
Bank Sta=5000.3,5039.2
XS Rating Curve= 0 ,0
Exp/Cntr=0.3,0.1

Type RM Length L Ch R = 1 ,70277   ,933,933,933
BEGIN DESCRIPTION:
Big Brushy Creek 140.0
END DESCRIPTION:
XS GIS Cut Line= 3
      2625514.28      6949491.93      2622076.02        6948461.
      2618285.14      6947436.39
#Sta/Elev= 30
  1410.5  466.71  1636.6  465.23  1774.1  459.92  1949.9  459.53  2059.5  461.72
  2243.9  459.81  2686.1  448.51  2823.6  441.47    2895  441.42    2912  439.39
  3350.9  433.53  3728.6  432.09  4791.2  431.78  4864.3  429.51  4950.4  433.14
  4968.7  429.18  4978.3  431.44  4989.6  429.07  4990.4  417.42  4995.4  416.42
  5030.3  417.42  5031.1  420.57  5041.5  429.52  5082.9  431.58  5886.6  433.07
  6263.8  431.45  6321.5  434.15  6684.7  433.61  7167.8  434.86  8926.9  453.64
#Mann= 6 ,-1 , 0
  1410.5     .05       0  3728.6     .12       0  4990.4     .07       0
  5030.3     .12       0  5886.6     .12       0  6684.7     .05       0
Bank Sta=4990.4,5030.3
XS Rating Curve= 0 ,0
Exp/Cntr=0.3,0.1

Type RM Length L Ch R = 1 ,69344   ,844,844,844
BEGIN DESCRIPTION:
Big Brushy Creek 138.0
END DESCRIPTION:
XS GIS Cut Line= 5
      2625201.82      6948832.22      2622176.07      6947611.03
      2621430.97      6947380.83      2620923.75      6947396.34
      2618676.04      6947011.01
#Sta/Elev= 30
  1737.1  463.38  2132.4  458.01  2180.7  453.24  2228.6  455.79    2390  450.35
  2873.1  440.88  3492.1  434.69  3702.4  430.18  4568.7  430.05  4859.9  432.03
  4924.6   430.8  4931.6  428.57  4946.2  428.74  4947.6  415.69  4952.6  414.69
  4987.9  415.69  4997.3  420.33  5002.7  420.33  5016.4  428.21  5031.1  428.06
  5086.9  430.69  6145.5  433.25    6205  433.46    6265  431.37  6457.5  433.46
  6962.6  432.39  7127.1  432.08  7867.8  445.12  8172.2  448.01  8567.8  455.01
#Mann= 7 ,-1 , 0
  1737.1     .05       0  3492.1     .12       0  4947.6     .07       0
  4987.9     .12       0  5031.1     .05       0  6145.5     .12       0
  6962.6     .05       0
Bank Sta=4947.6,4987.9
XS Rating Curve= 0 ,0
Exp/Cntr=0.3,0.1

Type RM Length L Ch R = 1 ,68500   ,2000,2000,2000
BEGIN DESCRIPTION:
Big Brushy Creek 137.0
END DESCRIPTION:
XS GIS Cut Line= 3
      2625226.02      6948211.01      2622319.54      6946814.45
      2618475.96        6947011.
#Sta/Elev= 30
  1775.4  464.21  1880.1  463.06  2441.1  445.64  3260.6  434.97  3305.9   439.5
  3334.1  435.25  3395.2  437.83  3417.4  434.22  3662.1  432.67  3689.4   430.1
  3939.3  430.83    4194  427.88  4946.6  431.11  4991.8  427.21  4993.4  414.81
  4998.4  413.81  5033.7  414.81  5034.5  418.15  5043.6  427.63  5063.6  427.01
  5083.6  430.68  5373.8  430.31  6552.1  432.69  6716.7  432.13  7246.5  432.46
  7526.8  436.93    7687  443.55  7771.9  441.26  7957.4  445.83  8848.6  456.86
#Mann= 7 ,-1 , 0
  1775.4     .05       0  3689.4     .12       0  4993.4     .07       0
  5033.7     .12       0  5373.8     .05       0  6552.1     .12       0
  6716.7     .05       0
Bank Sta=4993.4,5033.7
XS Rating Curve= 0 ,0
Exp/Cntr=0.3,0.1

Type RM Length L Ch R = 1 ,66500   ,1196,1196,1196
BEGIN DESCRIPTION:
Big Brushy Creek 133.0
END DESCRIPTION:
XS GIS Cut Line= 3
      2625626.01        6946011.      2622575.41      6944896.23
      2619626.02        6945111.
#Sta/Elev= 30
  1752.1  461.42  2603.8  445.45  3210.7  441.22  3317.2  436.58  3367.1  440.15
  3551.4  438.26  3902.8  428.75  4413.2  427.36    4467  430.98  4541.6  425.61
    4891  429.59  4978.1  430.73    4997  427.71  4999.3  413.72  5004.3  412.72
  5039.6  413.72  5059.6  429.41  5069.6  429.93  5866.7  429.35  6130.9  430.35
    6199  430.06  6316.4  430.27    6632  430.42  6925.5  430.48  7024.8  430.87
  7066.1   427.3  7425.1  430.49  7536.1   431.8  7706.6  451.76  7957.2  454.67
#Mann= 11 ,-1 , 0
  1752.1     .05       0    4891     .12       0  4999.3     .07       0
  5039.6     .12       0  5866.7     .05       0  6130.9     .12       0
    6199     .05       0  6316.4     .12       0    6632     .05       0
  6925.5     .12       0  7425.1     .05       0
Bank Sta=4999.3,5039.6
XS Rating Curve= 0 ,0
Exp/Cntr=0.3,0.1

Type RM Length L Ch R = 1 ,65304   ,309,309,309
BEGIN DESCRIPTION:
Mapping XS be645454
END DESCRIPTION:
XS GIS Cut Line= 6
      2625861.51      6944561.38       2623987.1      6944112.03
      2622820.44      6943802.14      2622500.12      6943729.22
      2620033.98      6943127.66       2619215.7      6942880.83
#Sta/Elev= 30
  1768.5  456.86  1837.7  457.32  1916.6  453.63  1921.8  455.28  2005.8  450.12
  2268.2  445.41  2298.6   442.3    3111  437.76  3554.3  429.17  4338.1  427.77
  4369.7  424.54  4442.1  430.89  4524.9  425.41    4574  428.13  4969.2   428.4
  4989.7  425.49  4997.9  413.27  5002.9  412.27  5038.3  413.27    5041  419.18
  5061.2  428.66  5109.3  428.37  5114.5  424.63  5409.6  427.18  7144.2  426.68
  7976.9  435.77  8158.2  440.16  8361.3  448.94    8468  450.27  8624.8  450.75
#Mann= 4 ,-1 , 0
  1768.5     .05       0  4997.9     .03       0  5038.3     .05       0
    8468    .075       0
Bank Sta=4997.9,5038.3
XS Rating Curve= 0 ,0
Exp/Cntr=0.3,0.1

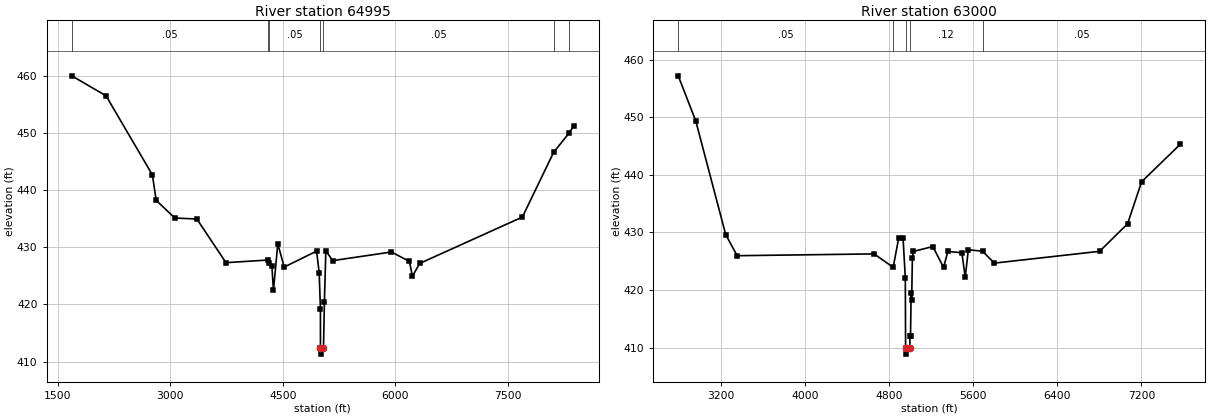
Type RM Length L Ch R = 1 ,64995   ,1995,1995,1995
BEGIN DESCRIPTION:
Mapping XS 141289f7
END DESCRIPTION:
XS GIS Cut Line= 5
      2626000.39      6944255.82      2623542.08      6943665.55
      2622792.08      6943491.94      2621283.98      6943112.03
      2619486.53      6942721.11
#Sta/Elev= 30
  1685.5  460.05  2142.5  456.55  2760.1   442.7    2811  438.23  3059.1  435.14
    3353  434.97  3741.2  427.32  4295.7  427.78  4314.3  427.33  4353.4  426.66
  4373.9  422.46  4431.9  430.62  4517.3  426.55  4948.7  429.34  4983.5  425.57
  5000.1  419.22  5000.5   412.3  5005.5   411.3  5040.9   412.3  5052.8  420.37
  5072.3  429.37  5165.1  427.68  5946.5  429.19    6186  427.54  6227.3  424.93
  6321.5  427.18  7692.2  435.31  8108.9  446.65  8313.8  450.01  8378.2  451.33
#Mann= 7 ,-1 , 0
  1685.5     .05       0  4295.7    .075       0  4314.3     .05       0
  5000.5     .03       0  5040.9     .05       0  8108.9    .075       0
  8313.8     .05       0
Bank Sta=5000.5,5040.9
XS Rating Curve= 0 ,0
Exp/Cntr=0.3,0.1

Type RM Length L Ch R = 1 ,63000   ,787,787,787
BEGIN DESCRIPTION:
Big Brushy Creek 126.0
END DESCRIPTION:
XS GIS Cut Line= 3
      2624975.98      6942760.99      2623085.59      6941618.71
      2620576.01        6941061.
#Sta/Elev= 30
  2791.3  457.19  2958.2  449.35  3243.4  429.61  3352.1  425.96    4656  426.27
  4837.6  423.94  4888.9  428.95  4931.6  428.97  4952.9  422.12  4955.7  409.87
  4960.6  408.87  4996.7  409.87  4996.8  411.96  5002.4  411.96  5008.6  419.48
  5013.7  418.33  5020.1  425.62  5030.3   426.7  5214.7  427.55  5317.1  423.93
  5358.1   426.7  5491.3  426.47  5523.4  422.21  5552.8  426.99  5688.4  426.74
  5799.9  424.67  6802.5  426.72  7068.9   431.5    7202  438.79  7570.8  445.31
#Mann= 5 ,-1 , 0
  2791.3     .05       0  4837.6     .12       0  4955.7     .07       0
  4996.7     .12       0  5688.4     .05       0
Bank Sta=4955.7,4996.7
XS Rating Curve= 0 ,0
Exp/Cntr=0.3,0.1