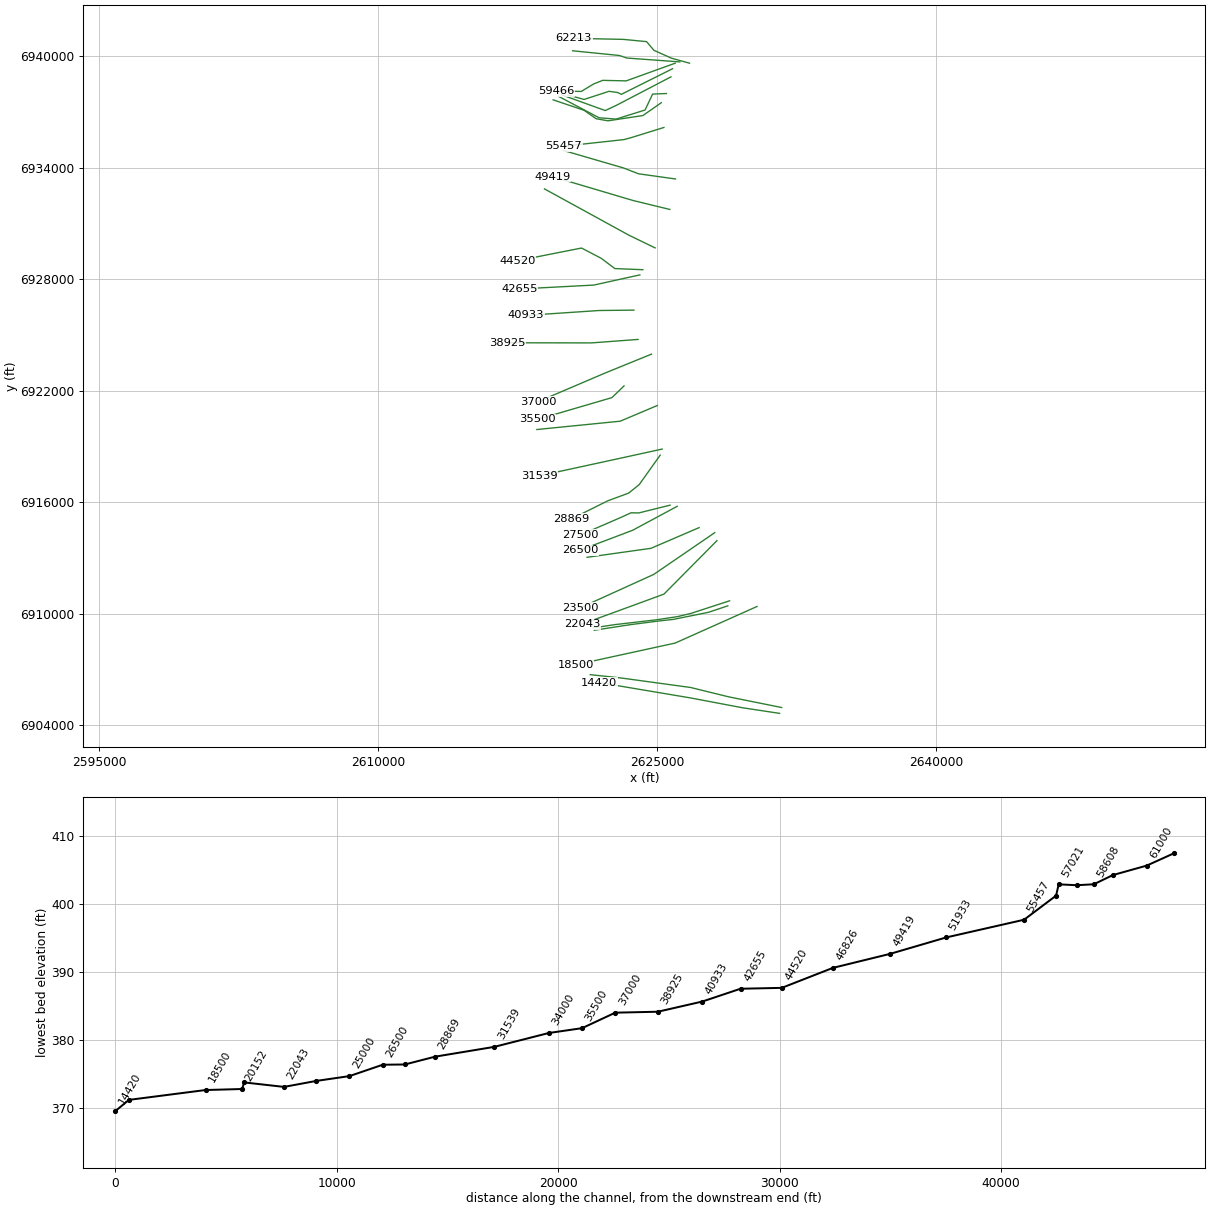
HEC-RAS study Big Brushy Creek.prj: Big Brushy Creek Base Level Engineering

--- Big Brushy Creek.g01 (geometry) --- (continued)

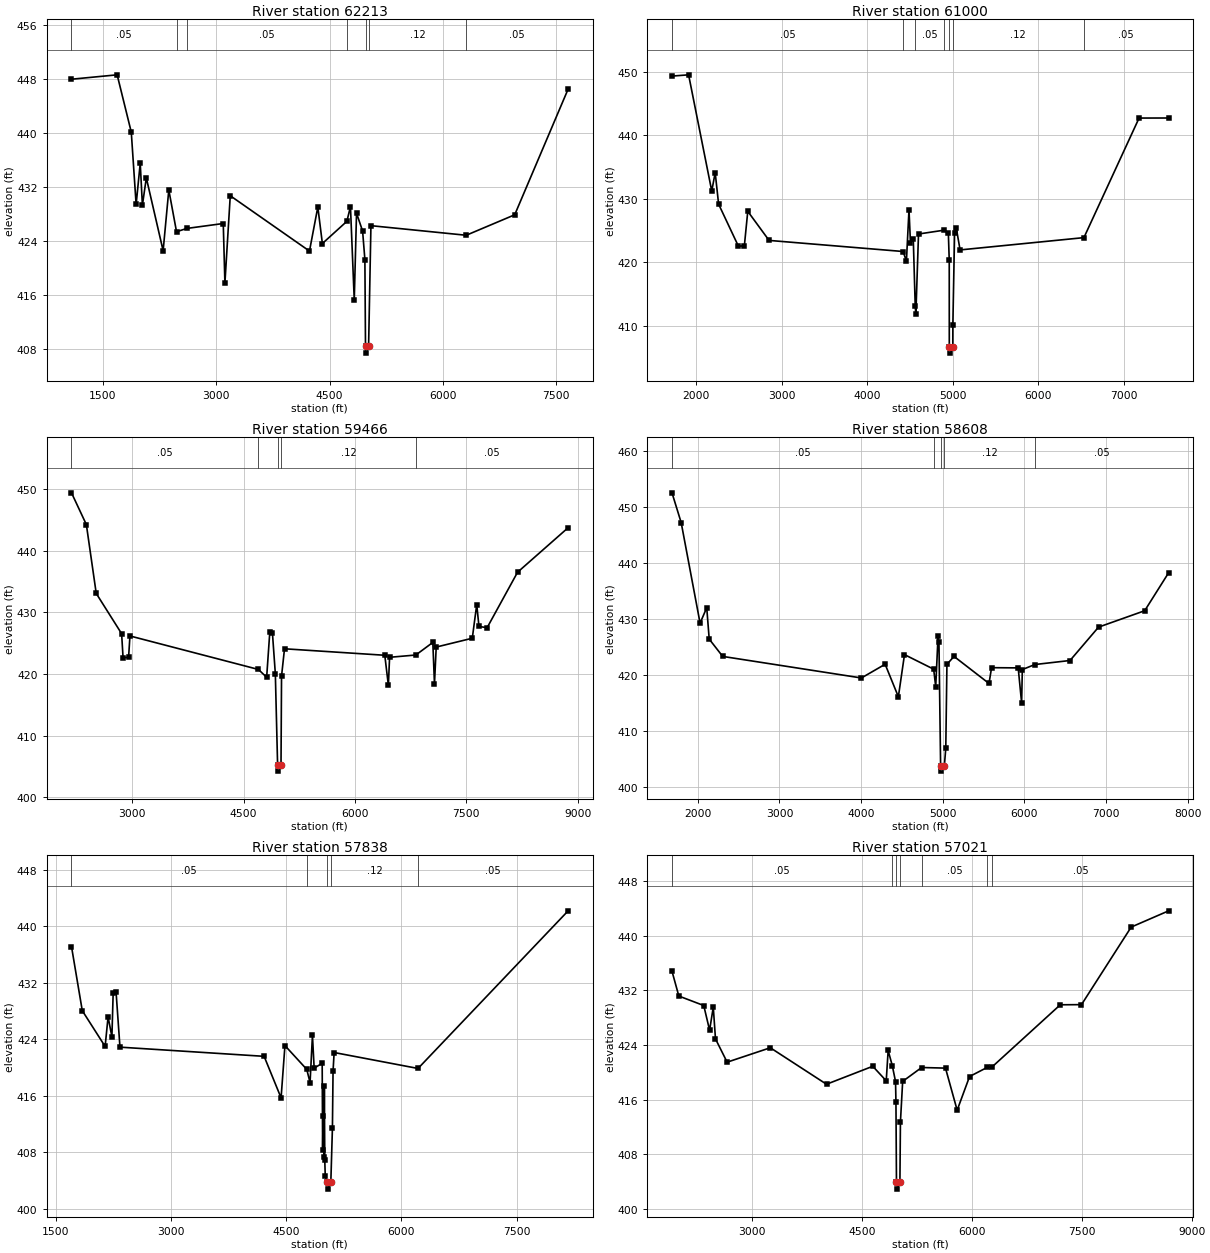
Type RM Length L Ch R = 1 ,62213   ,1213,1213,1213
BEGIN DESCRIPTION:
Big Brushy Creek 124.0
END DESCRIPTION:
XS GIS Cut Line= 6
      2626750.42      6939623.88      2625774.38      6939894.23
      2624833.82      6940317.23      2624437.92      6940783.61
      2623183.81      6940904.81        2620526.        6940961.
#Sta/Elev= 30
  1084.2  447.97  1688.5  448.62  1875.5  440.14  1939.7  429.44    1994  435.54
  2022.7  429.33  2074.6  433.37  2297.2  422.59  2372.2  431.59  2474.5   425.4
    2610  425.89    3093  426.62  3114.9  417.81  3185.7  430.73  4234.3  422.54
  4344.8  429.06  4405.1  423.66  4729.1  426.94  4776.8  429.12    4827   415.3
  4857.1  428.15  4937.5  425.51  4967.7  421.29  4975.9  408.44  4980.8  407.44
  5016.9  408.44  5047.8   426.3  6309.2  424.88    6951  427.91  7658.4  446.52
#Mann= 7 ,-1 , 0
  1084.2     .05       0  2474.5     .12       0    2610     .05       0
  4729.1     .12       0  4975.9     .07       0  5016.9     .12       0
  6309.2     .05       0
Bank Sta=4975.9,5016.9
XS Rating Curve= 0 ,0
Exp/Cntr=0.3,0.1

Type RM Length L Ch R = 1 ,61000   ,1534,1534,1534
BEGIN DESCRIPTION:
Big Brushy Creek 122.0
END DESCRIPTION:
XS GIS Cut Line= 4
      2626229.55      6939693.33      2623375.14      6939901.23
      2622975.98      6940037.65      2620465.69      6940290.55
#Sta/Elev= 30
  1716.2  449.35  1910.3  449.55    2181  431.22  2221.1  434.12  2261.2  429.15
  2491.8  422.54    2562  422.55  2602.1  428.02    2851  423.43  4418.4  421.68
    4457  420.15  4487.1  428.29  4504.2  423.07  4537.2  423.66  4560.1  413.02
  4567.3  411.77  4598.4  424.44  4895.3  425.04  4947.1  424.64  4957.7  420.28
  4958.3  406.65  4963.2  405.65  4999.4  406.65    5000  410.14  5020.1  424.65
  5040.2  425.37  5084.4  421.93  6532.4  423.87  7177.1  442.73    7523  442.74
#Mann= 7 ,-1 , 0
  1716.2     .05       0  4418.4     .12       0  4560.1     .05       0
  4895.3     .12       0  4958.3     .07       0  4999.4     .12       0
  6532.4     .05       0
Bank Sta=4958.3,4999.4
XS Rating Curve= 0 ,0
Exp/Cntr=0.3,0.1

Type RM Length L Ch R = 1 ,59466   ,858,858,858
BEGIN DESCRIPTION:
Mapping XS ecfd3179
END DESCRIPTION:
XS GIS Cut Line= 6
      2625979.55      6939623.87       2623340.7       6938672.5
      2622076.81      6938700.27       2621590.7      6938505.83
      2620924.03      6938103.05      2619604.58      6938130.83
#Sta/Elev= 30
    2181  449.36  2381.3  444.21  2514.3  433.05  2856.3  426.53  2875.7  422.64
  2950.1  422.69  2968.5  426.16  4699.4  420.73  4810.4  419.46  4852.7   426.8
  4888.7  426.56  4927.3  420.04  4957.8  405.25  4962.1  404.25  5003.8  405.25
  5010.8  419.63  5050.8  424.08    6402  423.03  6450.4  418.16  6466.6   422.7
  6820.1  423.07  7049.1  425.11  7071.4  418.38  7094.8  424.36  7580.8  425.79
  7640.8  431.25  7670.8   427.7  7780.8   427.5  8190.9  436.49  8872.5  443.71
#Mann= 5 ,-1 , 0
    2181     .05       0  4699.4     .12       0  4957.8     .07       0
  5003.8     .12       0  6820.1     .05       0
Bank Sta=4957.8,5003.8
XS Rating Curve= 0 ,0
Exp/Cntr=0.3,0.1

Type RM Length L Ch R = 1 ,58608   ,770,770,770
BEGIN DESCRIPTION:
Mapping XS bb99db70
END DESCRIPTION:
XS GIS Cut Line= 6
      2625833.78      6939325.29      2623083.75      6937950.27
      2622875.42       6938047.5      2622417.08        6938110.
      2621076.81       6937672.5      2620201.81      6937915.55
#Sta/Elev= 30
  1683.7  452.61  1796.3  447.28  2027.8  429.33  2109.3   432.1  2139.6  426.48
    2305  423.39  4004.4  419.54  4295.1  421.99  4457.2  416.18  4532.2  423.71
  4889.7  421.11  4914.8  417.99  4943.4  426.97  4954.5  425.88  4974.7   403.9
  4979.1   402.9  5020.8   403.9  5038.1  406.96  5052.2  421.97    5139  423.39
  5567.7  418.56  5599.2  421.38  5925.3  421.34  5967.4  415.08    5976  421.04
  6129.1  421.94  6560.5  422.66  6909.7  428.62  7475.3  431.55  7768.8  438.34
#Mann= 5 ,-1 , 0
  1683.7     .05       0  4889.7     .12       0  4974.7     .07       0
  5020.8     .12       0  6129.1     .05       0
Bank Sta=4974.7,5020.8
XS Rating Curve= 0 ,0
Exp/Cntr=0.3,0.1

Type RM Length L Ch R = 1 ,57838   ,817,817,817
BEGIN DESCRIPTION:
Mapping XS d039b748
END DESCRIPTION:
XS GIS Cut Line= 4
      2625750.37      6938887.75      2622819.86        6937360.
       2622215.7      6937075.27      2619869.77      6937922.03
#Sta/Elev= 30
  1705.1  437.14  1845.4  428.05  2142.9  422.98  2181.4  427.17  2231.2  424.35
  2247.7  430.59  2285.2  430.74  2336.1  422.88  4213.1  421.58    4434  415.69
  4484.3   423.1  4768.5  419.73  4811.3  417.85  4842.5  424.55  4864.6   419.9
  4969.2   420.6  4975.1  408.37  4980.7  413.08  4991.5  407.35  4997.2  417.44
    5003  406.85  5009.3  404.56  5035.1  403.76  5039.4  402.76  5081.8  403.76
  5102.6  411.44  5110.7  419.49  5124.8  422.12  6217.2  419.86  8171.9   442.2
#Mann= 5 ,-1 , 0
  1705.1     .05       0  4768.5     .12       0  5035.1     .07       0
  5081.8     .12       0  6217.2     .05       0
Bank Sta=5035.1,5081.8
XS Rating Curve= 0 ,0
Exp/Cntr=0.3,0.1

Type RM Length L Ch R = 1 ,57021   ,116,116,116
BEGIN DESCRIPTION:
Mapping XS cea1ed01
END DESCRIPTION:
XS GIS Cut Line= 6
      2625509.12      6937991.94      2624763.14      6937962.73
      2624356.89      6937105.09      2622800.76      6936616.94
      2621882.94      6936686.69      2619690.41      6937845.72
#Sta/Elev= 30
  1904.4  434.78  1997.6  431.15  2337.8  429.76  2417.9  426.14  2467.9  429.53
    2498  424.88  2657.1  421.47  3246.6  423.58  4013.9  418.24  4645.5  420.87
  4829.2  418.74  4855.4  423.18    4912  420.96  4956.3  418.63  4961.9  415.62
    4969  403.89  4973.3  402.89    5016  403.89  5023.1  412.73  5053.6  418.66
  5312.7  420.69  5638.4   420.6  5797.6  414.44  5966.9  419.37  6210.4  420.72
  6273.8  420.77  7205.6  429.87  7494.9  429.89  8173.3  441.24    8685  443.62
#Mann= 7 ,-1 , 0
  1904.4     .05       0    4912    .075       0    4969     .07       0
    5016    .075       0  5312.7     .05       0  6210.4    .075       0
  6273.8     .05       0
Bank Sta=4969,5016
XS Rating Curve= 0 ,0
Exp/Cntr=0.3,0.1

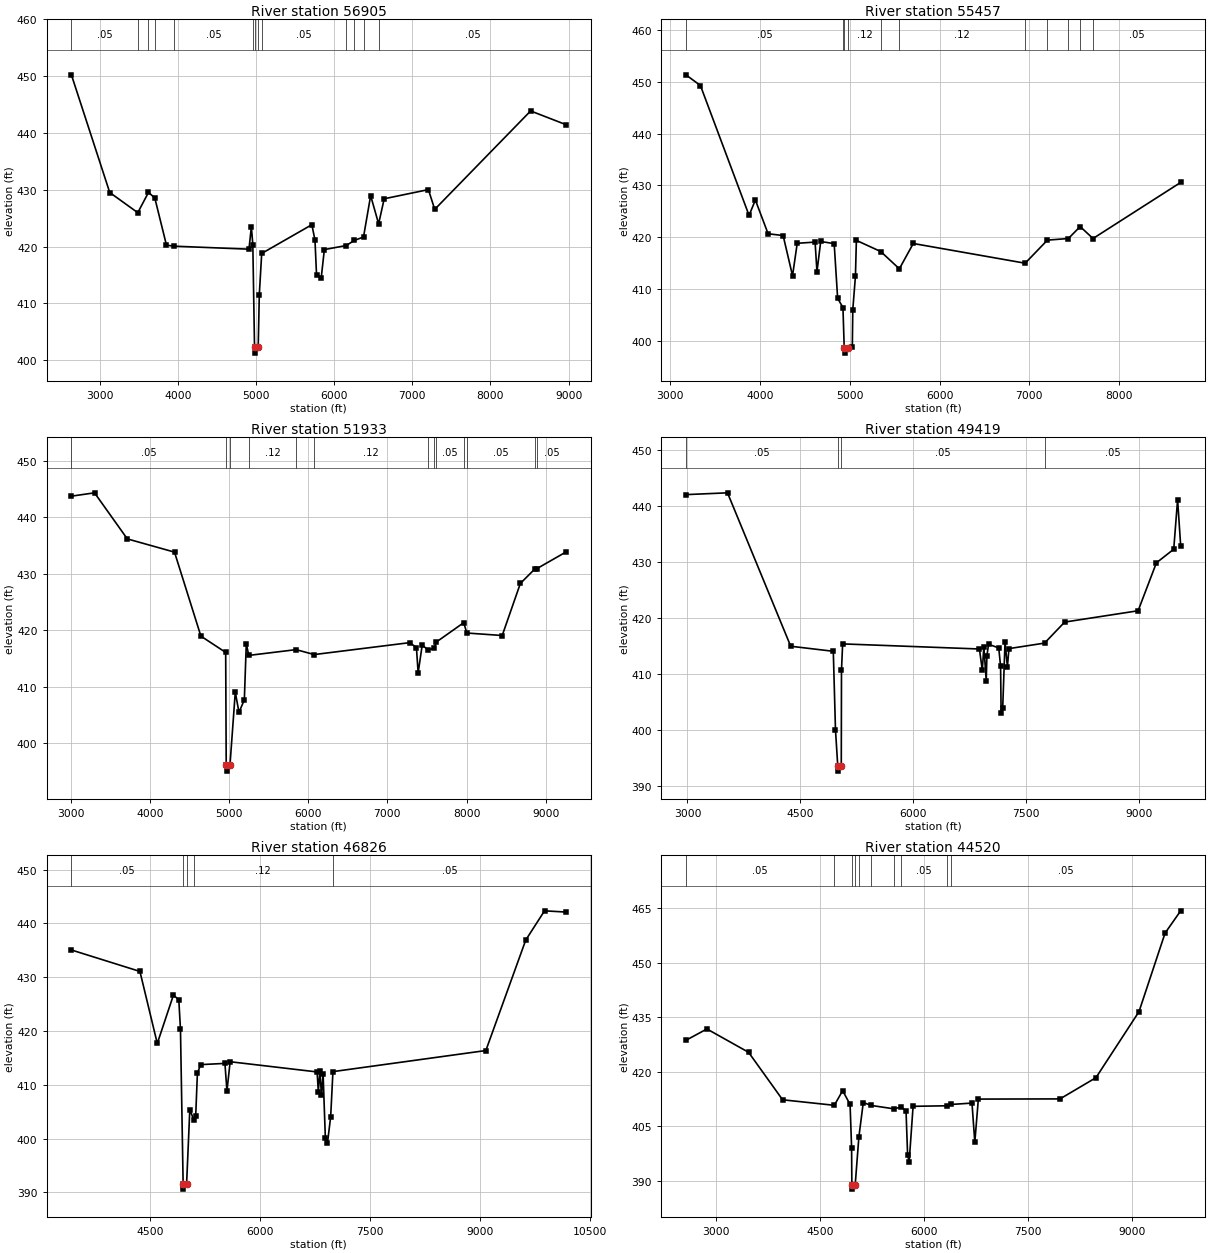
Type RM Length L Ch R = 1 ,56905   ,1448,1448,1448
BEGIN DESCRIPTION:
Mapping XS 98959174
END DESCRIPTION:
XS GIS Cut Line= 6
      2625231.29      6937498.87      2624241.27      6936807.35
      2622365.57      6936523.49      2621723.21      6936636.34
      2621078.54      6937089.16      2619411.83      6937651.68
#Sta/Elev= 30
  2635.8  450.25  3126.5  429.52  3485.4  425.97  3622.5  429.54  3703.1  428.57
  3852.6  420.25  3946.7  420.07  4908.7  419.54  4939.3  423.48    4958  420.36
  4979.9  402.23  4984.2  401.23  5026.9  402.23  5040.9  411.52  5071.7  418.79
  5713.6  423.85  5753.6  421.15  5773.6  415.02  5834.1  414.55  5873.7  419.47
  6153.2  420.18  6257.7  421.08  6375.1  421.69  6466.3  428.97  6568.5     424
  6639.6  428.42  7205.6  430.03  7286.5  426.55  8514.2  443.89  8968.9  441.46
#Mann= 13 ,-1 , 0
  2635.8     .05       0  3485.4    .075       0  3622.5     .05       0
  3703.1    .075       0  3946.7     .05       0    4958    .075       0
  4979.9     .07       0  5026.9    .075       0  5071.7     .05       0
  6153.2    .075       0  6257.7     .05       0  6375.1    .075       0
  6568.5     .05       0
Bank Sta=4979.9,5026.9
XS Rating Curve= 0 ,0
Exp/Cntr=0.3,0.1

Type RM Length L Ch R = 1 ,55457   ,3524,3524,3524
BEGIN DESCRIPTION:
Mapping XS 3d382e1f
END DESCRIPTION:
XS GIS Cut Line= 4
      2625370.18      6936165.54      2623627.15      6935623.89
      2623217.43      6935512.77      2619974.38      6935158.61
#Sta/Elev= 30
  3174.6  451.32  3336.1  449.26    3878  424.23  3948.4  427.19    4090  420.69
  4257.6  420.34  4362.3   412.6  4414.6  418.85  4613.6  419.08  4634.5  413.38
  4676.4   419.2  4826.3  418.78  4864.9  408.24    4924  406.47  4938.2  398.68
  4942.5  397.68  4985.2  398.68  5028.5  398.95  5033.6  406.04  5063.1  412.48
  5073.6  419.41  5345.1  417.26  5552.4  413.93  5707.5  418.81    6954  415.01
  7201.9  419.46  7435.4  419.77    7567  422.07    7710  419.77  8686.7  430.58
#Mann= 11 ,-1 , 0
  3174.6     .05       0    4924     .12       0  4938.2     .07       0
  4985.2     .12       0  5345.1     .05       0  5552.4     .12       0
    6954     .05       0  7201.9     .12       0  7435.4     .05       0
    7567    .075       0    7710     .05       0
Bank Sta=4938.2,4985.2
XS Rating Curve= 0 ,0
Exp/Cntr=0.3,0.1

Type RM Length L Ch R = 1 ,51933   ,2514,2514,2514
BEGIN DESCRIPTION:
Mapping XS b772e4c5
END DESCRIPTION:
XS GIS Cut Line= 4
      2625995.23      6933394.72       2624009.1       6933672.5
      2623182.71      6933991.94      2619960.75      6934929.36
#Sta/Elev= 30
  3010.5  443.71  3302.5   444.3  3716.5  436.15  4312.3  433.81  4645.5  418.95
  4958.5  416.07  4965.2  396.07  4969.5  395.07  5012.3  396.07  5079.7  409.05
  5126.5  405.46  5194.1   407.7  5218.7   417.6  5249.9  415.54  5846.9  416.56
  6077.1  415.69  7283.7   417.8    7367  416.93  7388.6  412.45  7439.9  417.37
  7513.9  416.51  7592.7  416.83  7617.7   417.9  7963.9  421.33  8003.6   419.5
  8450.1  419.06  8679.2  428.27    8864  430.86  8886.7  430.88  9257.5  433.85
#Mann= 13 ,-1 , 0
  3010.5     .05       0  4965.2     .03       0  5012.3     .05       0
  5249.9     .12       0  5846.9     .05       0  6077.1     .12       0
  7513.9     .05       0  7592.7     .12       0  7617.7     .05       0
  7963.9    .075       0  8003.6     .05       0    8864    .075       0
  8886.7     .05       0
Bank Sta=4965.2,5012.3
XS Rating Curve= 0 ,0
Exp/Cntr=0.3,0.1

Type RM Length L Ch R = 1 ,49419   ,2593,2593,2593
BEGIN DESCRIPTION:
Mapping XS 423abd46
END DESCRIPTION:
XS GIS Cut Line= 3
      2625689.61      6931755.84      2623717.43        6932235.
       2619357.4      6933526.34
#Sta/Elev= 30
  2979.5  441.98  3532.3   442.3  4372.5  414.94  4938.5  414.04  4967.6  400.02
  4997.4  393.67  5001.7  392.67  5044.6  393.67  5047.4  410.64  5062.7  415.36
  6880.8  414.45  6919.2  410.69    6940  414.87  6971.3  408.81  6980.5  413.26
  7002.6  415.29  7138.1  414.64  7162.4  411.34  7169.4  402.99  7190.3  403.92
  7221.6  415.74  7252.9  411.26  7273.7  414.52  7746.5   415.5  8014.2  419.25
  8990.5  421.27  9233.7  429.82  9463.9  432.24  9515.3  441.09  9556.3  432.85
#Mann= 4 ,-1 , 0
  2979.5     .05       0  4997.4     .03       0  5044.6     .05       0
  7746.5     .05       0
Bank Sta=4997.4,5044.6
XS Rating Curve= 0 ,0
Exp/Cntr=0.3,0.1

Type RM Length L Ch R = 1 ,46826   ,2306,2306,2306
BEGIN DESCRIPTION:
Mapping XS 93763d92
END DESCRIPTION:
XS GIS Cut Line= 3
      2624897.95       6929686.4      2623495.21      6930366.94
      2618946.62      6932859.98
#Sta/Elev= 30
  3431.3  435.07  4365.6  431.08  4602.4  417.69  4822.6  426.69  4895.8   425.8
  4918.4  420.32  4954.8   391.6    4959   390.6  5002.1   391.6  5045.8   405.4
    5099   403.5  5126.3  404.29  5149.2  412.12  5192.8  413.75  5524.6  413.98
  5552.1  408.84  5595.7  414.29  6781.7  412.39  6797.8  408.75  6819.6  412.48
  6841.4  408.07  6863.2  412.03  6893.9  400.16  6922.9  399.19  6966.5  404.07
  6997.3  412.45  9082.4  416.37  9626.6  436.92  9882.6  442.35 10177.4  442.12
#Mann= 5 ,-1 , 0
  3431.3     .05       0  4954.8     .05       0  5002.1     .05       0
    5099     .12       0  6997.3     .05       0
Bank Sta=4954.8,5002.1
XS Rating Curve= 0 ,0
Exp/Cntr=0.3,0.1

Type RM Length L Ch R = 1 ,44520   ,1865,1865,1865
BEGIN DESCRIPTION:
Mapping XS edbbf690
END DESCRIPTION:
XS GIS Cut Line= 5
      2624238.22      6928512.78      2622731.32      6928575.27
      2622002.15      6929123.89      2620939.65      6929679.44
      2617495.21      6928998.89
#Sta/Elev= 30
  2569.3   428.6  2871.8  431.72  3472.3   425.3  3962.7  412.24  4707.8  410.72
    4828  414.74  4935.1  410.97  4957.1  399.08  4960.8  388.66    4965  387.66
  5008.2  388.66  5062.1  402.04  5125.4  411.48  5240.3  410.68  5569.8  409.74
  5674.4  410.28  5741.7  409.11  5764.3  397.09  5786.9  395.21  5843.3  410.44
  6334.5  410.59  6395.6  410.96  6692.2  411.33  6732.9  400.57  6783.9  412.43
    7961  412.48  8478.9  418.32  9099.3  436.49  9474.9  458.09    9700  464.22
#Mann= 10 ,-1 , 0
  2569.3     .05       0  4707.8     .12       0  4960.8     .03       0
  5008.2     .12       0  5062.1     .12       0  5240.3     .05       0
  5569.8     .12       0  5674.4     .05       0  6334.5     .12       0
  6395.6     .05       0
Bank Sta=4960.8,5008.2
XS Rating Curve= 0 ,0
Exp/Cntr=0.3,0.1

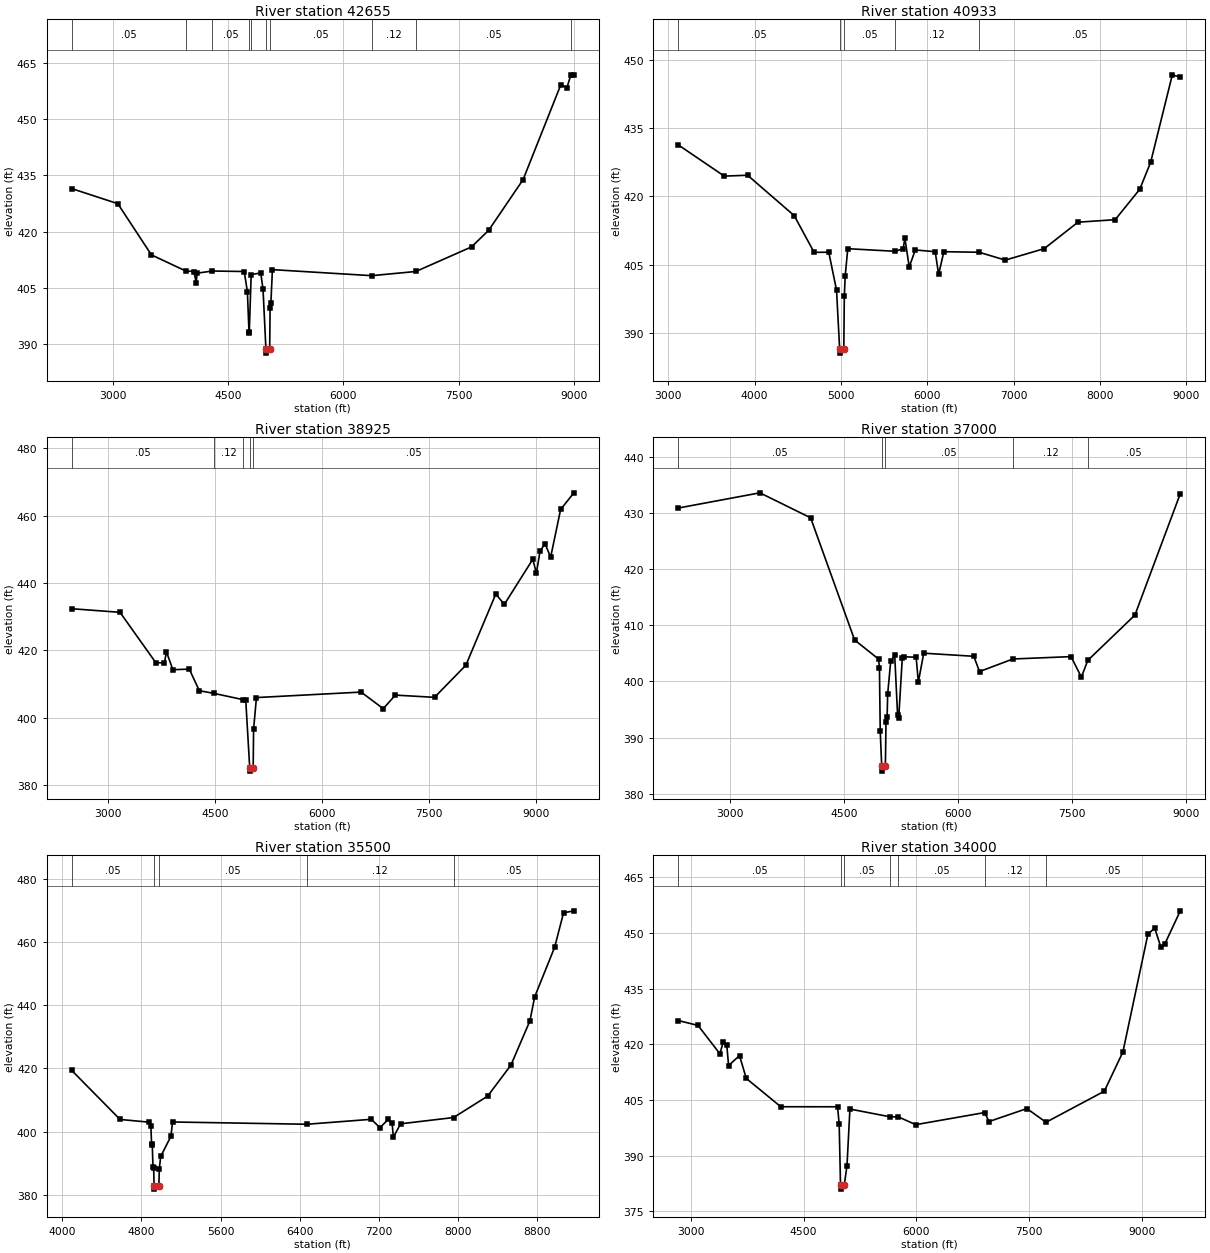
Type RM Length L Ch R = 1 ,42655   ,1722,1722,1722
BEGIN DESCRIPTION:
Mapping XS 83b3c599
END DESCRIPTION:
XS GIS Cut Line= 3
      2624078.55        6928235.      2621599.38      6927686.39
      2617606.35      6927478.05
#Sta/Elev= 30
  2461.8  431.45  3061.2  427.43  3498.8  413.76  3945.2  409.47  4051.9  409.32
  4082.6  406.32  4092.9  408.88  4293.6  409.45  4707.4  409.32  4748.4  403.96
  4769.6  393.13  4772.6  392.88    4798  408.49  4922.5  408.94  4952.3  404.57
  4990.1  388.53  4994.3  387.53  5038.5  388.53  5044.4  399.71  5054.4  400.88
  5074.4  409.82  6367.5  408.21  6942.9  409.33  7667.9   415.9  7890.3  420.32
  8338.9  433.87  8829.5  459.17  8909.6  458.38  8960.7  461.83  8999.4  461.66
#Mann= 10 ,-1 , 0
  2461.8     .05       0  3945.2     .12       0  4293.6     .05       0
  4769.6     .12       0    4798     .05       0  4990.1     .03       0
  5038.5     .05       0  6367.5     .12       0  6942.9     .05       0
  8960.7    .075       0
Bank Sta=4990.1,5038.5
XS Rating Curve= 0 ,0
Exp/Cntr=0.3,0.1

Type RM Length L Ch R = 1 ,40933   ,2008,2008,2008
BEGIN DESCRIPTION:
Mapping XS 11123bdb
END DESCRIPTION:
XS GIS Cut Line= 3
      2623759.11      6926339.16       2621884.1      6926318.33
      2617953.57      6926054.44
#Sta/Elev= 30
  3116.7   431.3  3649.8  424.45  3919.9  424.64  4459.9  415.79  4689.9  407.74
  4859.9  407.77  4949.9  399.46  4985.7  386.65  4989.9  385.65  5034.2  386.65
    5040  398.08  5050.1  402.55  5080.1  408.54  5629.1  407.97  5721.6  408.55
  5741.6  410.84  5791.7  404.53  5861.9  408.26  6092.4  407.89  6132.5  402.91
  6192.6  407.88    6601  407.76  6904.2  406.04  7355.2  408.55  7746.1  414.35
  8177.1   414.9  8461.4  421.56    8588   427.5  8838.6  446.65  8931.2  446.14
#Mann= 5 ,-1 , 0
  3116.7     .05       0  4985.7     .03       0  5034.2     .05       0
  5629.1     .12       0    6601     .05       0
Bank Sta=4985.7,5034.2
XS Rating Curve= 0 ,0
Exp/Cntr=0.3,0.1

Type RM Length L Ch R = 1 ,38925   ,1925,1925,1925
BEGIN DESCRIPTION:
Mapping XS 3281fe0c
END DESCRIPTION:
XS GIS Cut Line= 3
      2623981.31      6924762.77      2621474.38      6924575.27
      2616940.32      6924582.22
#Sta/Elev= 30
  2487.2  432.37  3164.4   431.3  3665.8  416.38  3787.9  416.27  3816.2  419.58
  3906.5  414.26  4137.1  414.44  4277.5  408.03  4481.6  407.24  4894.1  405.36
  4929.3  405.27  4985.2  385.15  4989.4  384.15  5033.8  385.15  5039.5  396.55
  5079.5  405.99  6549.5  407.62  6859.5  402.69  7029.5  406.72  7579.5  406.06
  8019.5   415.6  8439.5  436.73  8559.5  433.66  8959.5  447.06  9009.5  442.88
  9059.5  449.36  9129.5  451.73  9209.5  447.68  9349.5  461.83  9535.2  466.78
#Mann= 5 ,-1 , 0
  2487.2     .05       0  4481.6     .12       0  4894.1     .05       0
  4985.2     .03       0  5033.8     .05       0
Bank Sta=4985.2,5033.8
XS Rating Curve= 0 ,0
Exp/Cntr=0.3,0.1

Type RM Length L Ch R = 1 ,37000   ,1500,1500,1500
BEGIN DESCRIPTION:
Big Brushy Creek 74.0
END DESCRIPTION:
XS GIS Cut Line= 3
      2624703.52       6923971.1       2622226.4      6922962.46
      2618620.61      6921422.67
#Sta/Elev= 30
  2325.4  430.88  3398.3  433.59  4064.5  429.14  4642.3  407.37  4957.2  403.97
  4968.8  402.31  4978.8  391.16  4997.8  385.01    5002  384.01  5046.5  385.01
  5054.8   392.8  5069.2   393.6  5076.5  397.73  5116.5  403.59  5169.1  404.61
    5207  393.93  5221.7  393.55    5269   404.2  5292.6  404.37  5450.5  404.31
  5479.5  399.87  5550.4  405.02  6207.4  404.47  6283.5  401.75  6722.5  403.99
  7485.7  404.41    7621  400.75  7705.4  403.74  8324.5  411.81  8920.8  433.45
#Mann= 5 ,-1 , 0
  2325.4     .05       0  4997.8     .03       0  5046.5     .05       0
  6722.5     .12       0  7705.4     .05       0
Bank Sta=4997.8,5046.5
XS Rating Curve= 0 ,0
Exp/Cntr=0.3,0.1

Type RM Length L Ch R = 1 ,35500   ,1500,1500,1500
BEGIN DESCRIPTION:
Big Brushy Creek 71.0
END DESCRIPTION:
XS GIS Cut Line= 3
      2623226.02      6922261.02      2622575.99      6921632.64
      2618576.05      6920461.01
#Sta/Elev= 30
  4095.9  419.37  4583.8  403.83  4880.9  402.96  4895.1  401.78  4902.3  395.89
  4909.2  395.68  4916.4   388.8  4923.4  388.35  4927.3  382.73  4931.5  381.73
    4976  382.73    4980  388.07  4994.1  392.08  5096.9  398.44  5114.6  403.03
  6472.1  402.31  7121.5  403.88  7209.1  401.22  7292.4  403.83  7332.4  402.59
  7344.5  398.17  7417.5  402.45    7953  404.44  8297.2  411.23  8532.4  421.07
  8724.3  435.11  8772.1  442.71  8973.8  458.43  9063.8  469.36    9168  470.01
#Mann= 5 ,-1 , 0
  4095.9     .05       0  4927.3     .03       0    4976     .05       0
  6472.1     .12       0    7953     .05       0
Bank Sta=4927.3,4976
XS Rating Curve= 0 ,0
Exp/Cntr=0.3,0.1

Type RM Length L Ch R = 1 ,34000   ,2461,2461,2461
BEGIN DESCRIPTION:
Big Brushy Creek 68.0
END DESCRIPTION:
XS GIS Cut Line= 3
      2625016.01       6921207.2      2623020.68      6920363.17
      2618536.86      6919915.55
#Sta/Elev= 30
  2833.5  426.43  3096.4  425.11  3387.3  417.47  3431.5  420.68  3478.9  419.72
  3502.6   414.3  3647.8  416.99  3737.6  410.84  4196.6  403.21  4950.8   403.2
  4972.5  398.55  4990.3  382.02  4994.4  381.02  5039.1  382.02  5076.1   387.3
  5115.2  402.59  5642.9  400.52  5760.5  400.47  5989.6  398.38  6904.7  401.64
  6964.4  399.23  7466.9  402.72  7721.5  399.03  8495.9  407.39  8743.2  417.97
  9074.8  449.63  9165.3  451.37  9245.7   446.3  9300.6  447.07  9506.1  455.98
#Mann= 7 ,-1 , 0
  2833.5     .05       0  4990.3     .03       0  5039.1     .05       0
  5642.9     .12       0  5760.5     .05       0  6904.7     .12       0
  7721.5     .05       0
Bank Sta=4990.3,5039.1
XS Rating Curve= 0 ,0
Exp/Cntr=0.3,0.1

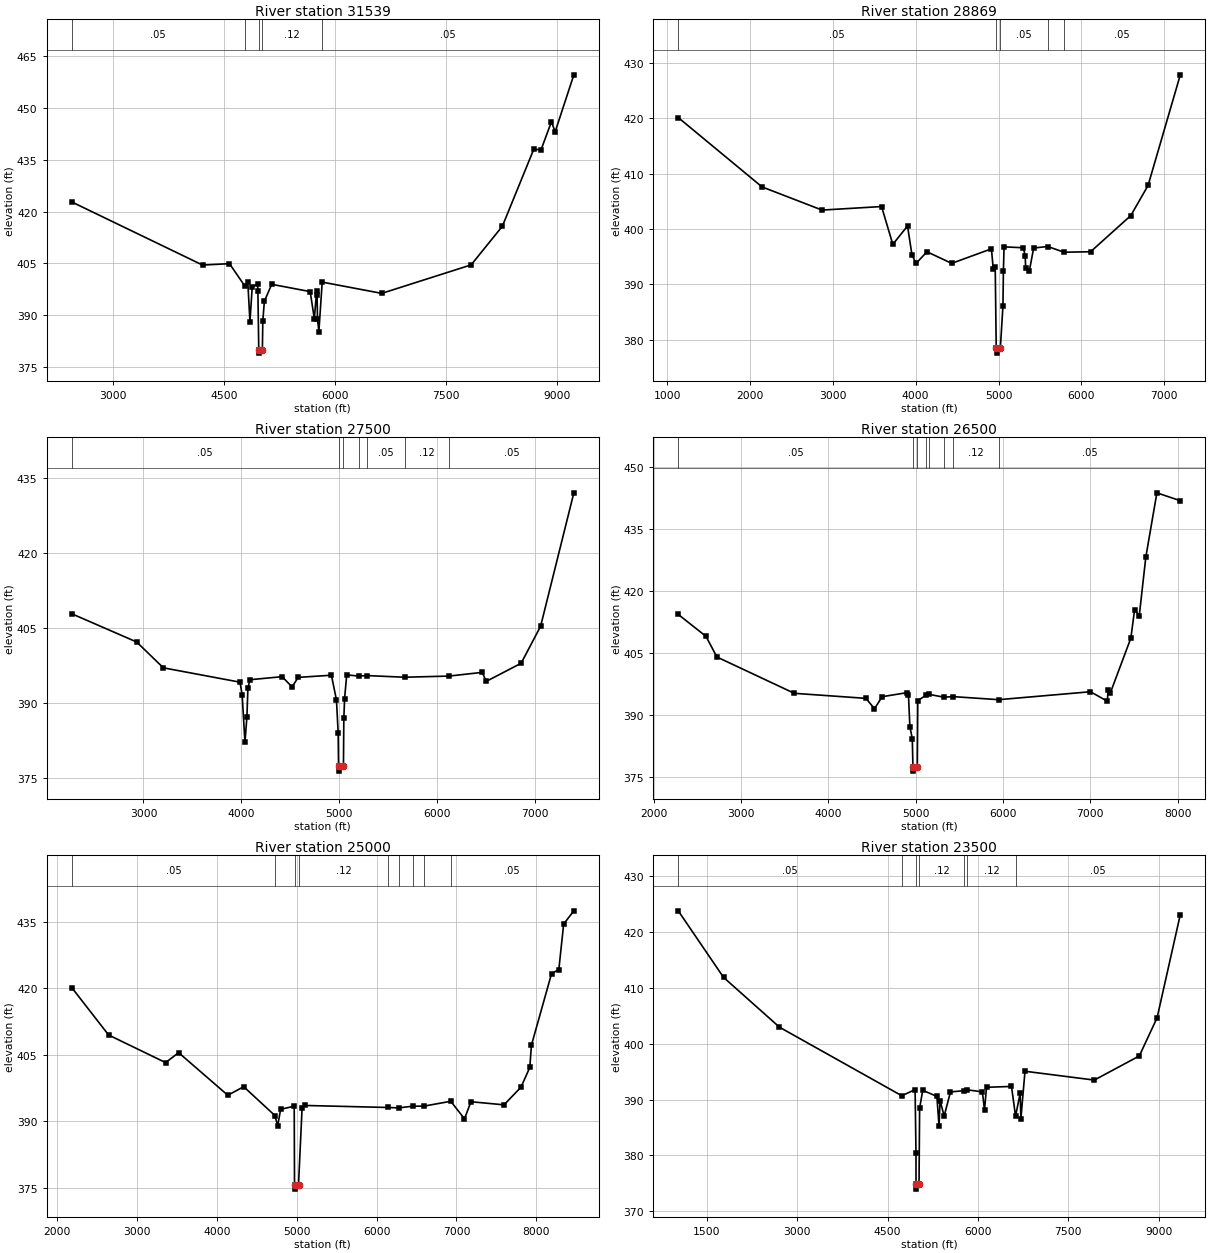
Type RM Length L Ch R = 1 ,31539   ,2670,2670,2670
BEGIN DESCRIPTION:
Big Brushy Creek 64.0
END DESCRIPTION:
XS GIS Cut Line= 3
      2625277.77       6918863.5      2622776.45      6918316.18
      2618649.49      6917420.68
#Sta/Elev= 30
  2439.5   422.8  4206.3  404.51  4570.5  404.91  4775.4   398.5  4817.5  399.74
  4846.9  388.06  4877.6   398.2  4949.1  399.06  4954.2  397.12  4965.8  379.98
  4969.9  378.98  5014.6  379.98  5020.9  388.35  5041.4  393.99  5140.5  398.93
  5660.8  396.81  5716.7  388.94  5747.4  396.89    5754  395.85  5759.1  388.98
  5778.1  385.24    5823  399.57  6627.5   396.3  7835.2  404.56  8257.2  415.76
  8684.3  438.23  8777.5  437.77  8919.8  446.03  8970.8  443.16    9223  459.65
#Mann= 5 ,-1 , 0
  2439.5     .05       0  4775.4     .12       0  4965.8     .07       0
  5014.6     .12       0    5823     .05       0
Bank Sta=4965.8,5014.6
XS Rating Curve= 0 ,0
Exp/Cntr=0.3,0.1

Type RM Length L Ch R = 1 ,28869   ,1369,1369,1369
BEGIN DESCRIPTION:
Big Brushy Creek 58.0
END DESCRIPTION:
XS GIS Cut Line= 5
      2625171.03       6918536.5      2624042.13      6916952.08
      2623477.68      6916496.57      2622356.05      6916081.34
      2620391.01      6915103.04
#Sta/Elev= 30
  1133.2  420.16  2145.3  407.61  2869.5  403.42    3588  404.06  3723.9  397.22
  3901.7  400.55  3955.1  395.31  4005.1  393.78  4136.3  395.88  4434.4  393.78
  4914.8  396.41  4936.1  392.78  4960.3  393.16  4972.4  378.54  4976.4  377.54
  5022.4  378.54  5053.6  386.04  5059.2  392.35  5067.1  396.77  5299.9   396.6
  5322.3  395.13  5327.9  392.96  5372.6  392.44  5424.6  396.56  5595.8  396.83
  5789.7   395.8  6111.5  395.88  6597.5  402.43  6805.6  407.87  7195.1  427.89
#Mann= 5 ,-1 , 0
  1133.2     .05       0  4972.4     .03       0  5022.4     .05       0
  5595.8     .12       0  5789.7     .05       0
Bank Sta=4972.4,5022.4
XS Rating Curve= 0 ,0
Exp/Cntr=0.3,0.1

Type RM Length L Ch R = 1 ,27500   ,1000,1000,1000
BEGIN DESCRIPTION:
Big Brushy Creek 55.0
END DESCRIPTION:
XS GIS Cut Line= 5
      2625703.56      6915846.11      2624018.21      6915427.64
      2623606.32      6915436.39      2623075.53      6915193.58
      2620877.16      6914241.94
#Sta/Elev= 30
  2267.8  407.81    2931  402.17  3202.9  397.02    3986  394.15  4007.9  391.61
  4036.5  382.16  4056.5  387.19  4066.5   392.9  4086.6  394.64  4416.3  395.25
  4517.3  393.21  4580.8  395.11  4919.5  395.54  4971.1   390.6  4988.5  384.02
  4992.5  377.39  4996.5  376.39  5042.5  377.39  5046.4   386.9    5054  390.87
  5075.8  395.61  5197.6  395.37    5281  395.47  5666.7  395.14  6121.3  395.37
  6459.6  396.11    6501  394.31    6857  397.93  7055.8   405.3  7395.5  431.96
#Mann= 7 ,-1 , 0
  2267.8     .05       0  4992.5     .03       0  5042.5     .05       0
  5197.6     .12       0    5281     .05       0  5666.7     .12       0
  6121.3     .05       0
Bank Sta=4992.5,5042.5
XS Rating Curve= 0 ,0
Exp/Cntr=0.3,0.1

Type RM Length L Ch R = 1 ,26500   ,1500,1500,1500
BEGIN DESCRIPTION:
Big Brushy Creek 53.0
END DESCRIPTION:
XS GIS Cut Line= 3
      2626085.44      6915783.59      2623691.46      6914495.95
      2620856.28      6913422.48
#Sta/Elev= 30
  2281.7  414.25    2599  408.96  2724.8  403.95  3610.9  395.17  4431.3  393.95
  4529.3  391.45  4617.2  394.35    4904  395.34  4918.3  394.79  4934.5  387.13
  4962.1  384.22  4969.5  377.35  4973.5  376.35  5019.5  377.35    5025  393.41
  5121.4  394.72    5148  394.94  5323.5  394.24  5429.8  394.37  5951.3  393.63
  7002.5  395.55  7197.6  393.24  7202.9  395.95  7227.8  395.13  7465.2  408.52
    7508  415.37  7561.4  413.92  7636.3  428.08  7763.4  443.66  8031.6  441.75
#Mann= 8 ,-1 , 0
  2281.7     .05       0  4969.5     .03       0  5019.5     .05       0
  5121.4     .05       0    5148     .12       0  5323.5     .05       0
  5429.8     .12       0  5951.3     .05       0
Bank Sta=4969.5,5019.5
XS Rating Curve= 0 ,0
Exp/Cntr=0.3,0.1

Type RM Length L Ch R = 1 ,25000   ,1500,1500,1500
BEGIN DESCRIPTION:
Big Brushy Creek 50.0
END DESCRIPTION:
XS GIS Cut Line= 3
      2627266.09      6914637.79      2624676.01      6913525.26
       2621239.6      6913040.74
#Sta/Elev= 30
  2181.1   420.1  2642.7  409.42  3356.6   403.2  3519.9  405.44  4135.7  395.84
    4335  397.77  4726.4  391.25  4760.6  388.95  4797.1  392.66  4967.4  393.38
  4971.4  375.68  4975.4  374.68  5021.4  375.68    5066  392.92    5101  393.54
  6145.8  393.08  6275.5  392.99  6454.5  393.38  6590.4  393.38  6928.5  394.48
  7100.6  390.53  7181.4  394.38  7595.4  393.68  7807.5  397.64  7918.6   402.1
  7938.8   407.1  8191.3  423.27  8282.2  424.15  8342.8  434.43  8470.4  437.41
#Mann= 9 ,-1 , 0
  2181.1     .05       0  4726.4     .12       0  4971.4     .07       0
  5021.4     .12       0  6145.8     .05       0  6275.5     .12       0
  6454.5     .05       0  6590.4     .12       0  6928.5     .05       0
Bank Sta=4971.4,5021.4
XS Rating Curve= 0 ,0
Exp/Cntr=0.3,0.1

Type RM Length L Ch R = 1 ,23500   ,1457,1457,1457
BEGIN DESCRIPTION:
Big Brushy Creek 47.0
END DESCRIPTION:
XS GIS Cut Line= 3
      2628106.36      6914366.97      2624826.06      6912121.04
       2620856.3      6910318.32
#Sta/Elev= 30
  1024.5  423.81  1776.3   411.9  2705.6  402.97  4736.6  390.69  4956.7   391.8
  4971.6  380.39    4972  374.97    4976  373.97    5022  374.97  5031.9  388.47
  5083.6  391.67  5318.6  390.57  5353.9  385.33  5371.5  389.82  5439.4  387.06
    5544  391.38  5771.3   391.6  5824.1  391.75  6073.6  391.39  6109.3  388.14
  6142.3  392.21  6557.1  392.36  6624.5  387.04    6701  391.15  6713.4  386.59
  6781.2  395.08  7932.5   393.5  8679.3  397.82  8974.4  404.66  9359.9  423.15
#Mann= 7 ,-1 , 0
  1024.5     .05       0  4736.6     .12       0    4972     .07       0
    5022     .12       0  5771.3      .1       0  5824.1     .12       0
  6624.5     .05       0
Bank Sta=4972,5022
XS Rating Curve= 0 ,0
Exp/Cntr=0.3,0.1

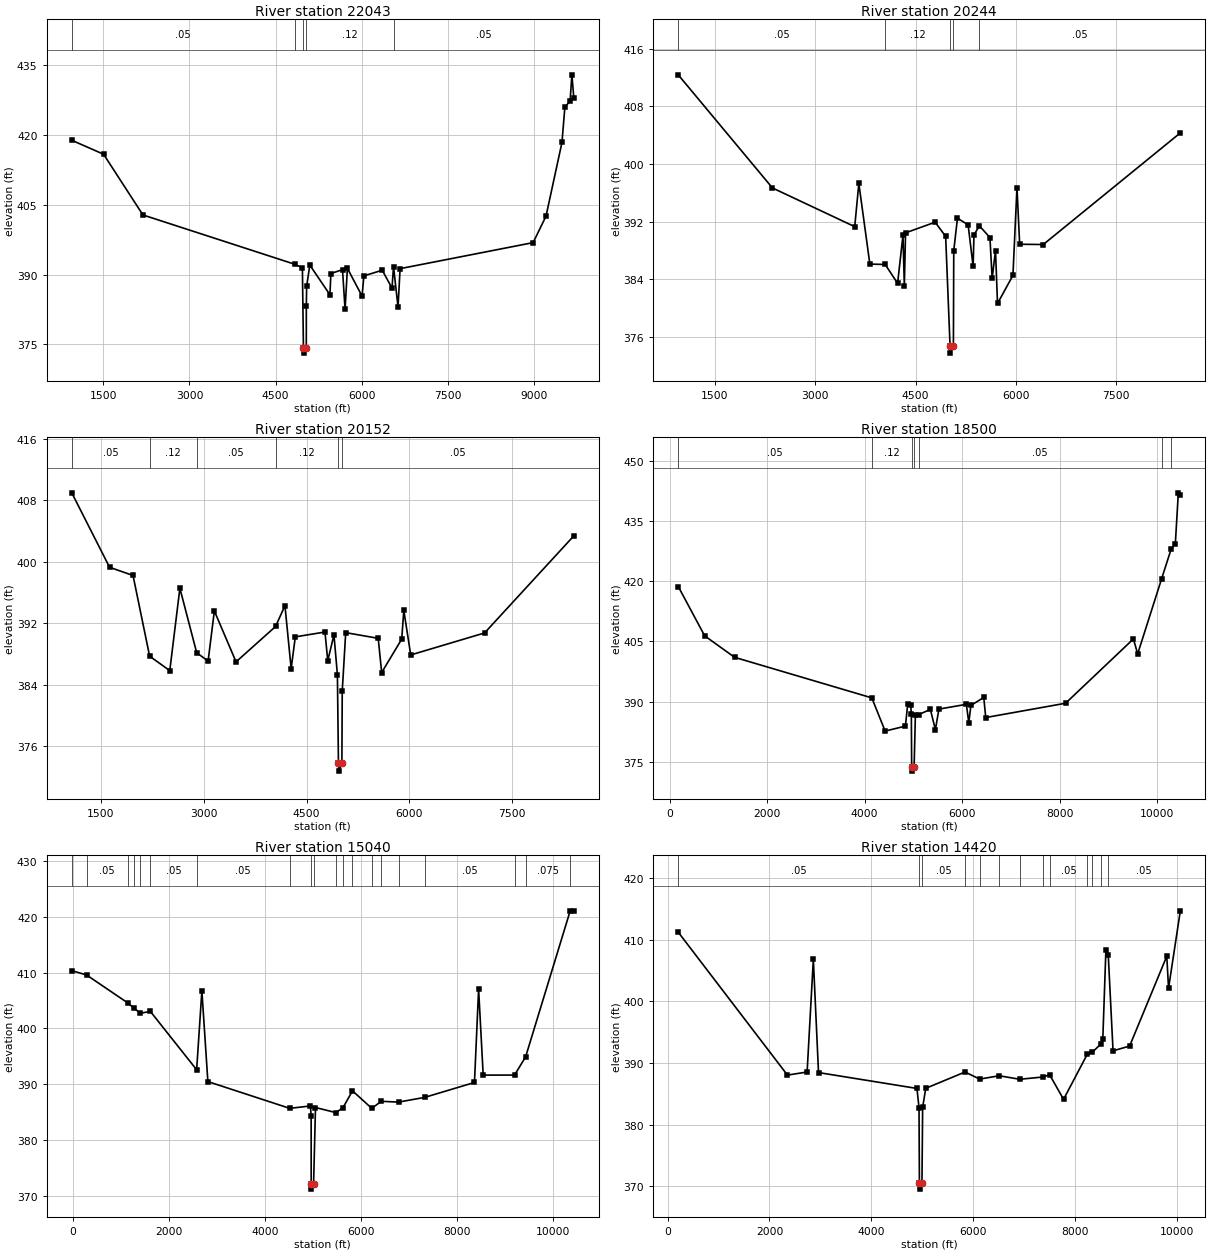
Type RM Length L Ch R = 1 ,22043   ,1799,1799,1799
BEGIN DESCRIPTION:
Big Brushy Creek 46.0
END DESCRIPTION:
XS GIS Cut Line= 3
      2628224.34      6913936.35      2625372.48      6911059.72
      2620960.73      6909443.42
#Sta/Elev= 30
   949.3  418.87  1503.5  415.87  2189.4  402.81  4831.5  392.22  4968.3  391.45
  4986.5  374.09  4990.5  373.09  5036.5  374.09  5036.7   383.2    5042  387.46
  5097.7  392.02  5447.9  385.65  5464.8  390.21  5667.2  391.05  5711.8  382.48
  5752.4  391.33    6008  385.35  6039.9  389.71  6359.4  390.92  6529.8  387.08
    6556   391.7  6634.9     383  6670.7  391.26    8989  396.86  9213.6  402.56
  9491.7  418.42  9542.1  425.99  9633.6  427.33  9664.1  432.95  9698.5  427.96
#Mann= 5 ,-1 , 0
   949.3     .05       0  4831.5     .12       0  4986.5     .07       0
  5036.5     .12       0    6556     .05       0
Bank Sta=4986.5,5036.5
XS Rating Curve= 0 ,0
Exp/Cntr=0.3,0.1

Type RM Length L Ch R = 1 ,20244   ,92,92,92
BEGIN DESCRIPTION:
Big Brushy Creek 43.0
END DESCRIPTION:
XS GIS Cut Line= 6
      2628905.56      6910701.56      2626837.72      6910026.94
      2626113.77      6909851.59      2624996.96      6909682.11
      2622731.82       6909419.3      2621565.33      6909243.24
#Sta/Elev= 30
   950.3  412.37  2359.6  396.67  3590.1   391.3  3651.8  397.29  3816.5  386.11
  4046.3  386.05  4231.4  383.44  4312.1  390.12  4332.3  383.06  4350.6  390.44
    4793  391.92  4950.3  389.95  5016.3  374.75  5020.3  373.75  5066.3  374.75
  5071.5  387.96    5127  392.48  5286.5  391.55  5361.2   385.8    5374  390.17
  5455.3  391.41  5612.8  389.79  5645.8  384.13    5696  387.99  5726.1  380.64
  5956.8  384.54  6017.1  396.73  6057.4  388.86  6410.2  388.82  8460.4  404.31
#Mann= 5 ,-1 , 0
   950.3     .05       0  4046.3     .12       0  5016.3     .07       0
  5066.3     .12       0  5455.3     .05       0
Bank Sta=5016.3,5066.3
XS Rating Curve= 0 ,0
Exp/Cntr=0.3,0.1

Type RM Length L Ch R = 1 ,20152   ,1652,1652,1652
BEGIN DESCRIPTION:
Big Brushy Creek 42.0
END DESCRIPTION:
XS GIS Cut Line= 6
      2628808.33      6910429.86      2627771.23       6910081.8
      2625885.81      6909701.59      2624986.52      6909601.21
      2623528.86      6909411.65      2621624.39      6909117.38
#Sta/Elev= 30
  1077.8  408.95  1629.1  399.27  1970.8  398.21  2212.8  387.72  2506.6  385.84
  2653.9  396.55  2899.1  388.16  3065.4  387.09  3156.4   393.6  3472.6  386.98
  4049.1  391.58  4185.5   394.3    4276  386.09  4336.4  390.23  4769.1  390.86
  4809.3  387.13  4899.9  390.49  4950.2  385.31  4965.5  373.78  4969.5  372.78
  5015.5  373.78  5020.7  383.17  5071.1  390.78  5545.1  390.04  5595.5  385.59
  5887.9  389.94  5918.2  393.67    6019  387.88  7095.7  390.74    8397  403.36
#Mann= 6 ,-1 , 0
  1077.8     .05       0  2212.8     .12       0  2899.1     .05       0
  4049.1     .12       0  4965.5     .03       0  5015.5     .05       0
Bank Sta=4965.5,5015.5
XS Rating Curve= 0 ,0
Exp/Cntr=0.3,0.1

Type RM Length L Ch R = 1 ,18500   ,3460,3460,3460
BEGIN DESCRIPTION:
Big Brushy Creek 37.0
END DESCRIPTION:
XS GIS Cut Line= 3
      2630381.07      6910395.26       2625976.2      6908427.04
      2620626.34      6907259.42
#Sta/Elev= 30
   175.4  418.73     718  406.41  1331.1  401.05    4147  390.92  4419.7  382.63
  4836.2  383.87  4882.6  389.28  4945.5  389.03  4957.7  386.78  4964.3  373.63
  4968.3  372.63  5014.3  373.63  5041.1  386.75  5110.8  386.75  5348.2  388.05
  5450.6  382.98    5524  388.12  6086.9  389.31  6136.3  384.72  6179.8  389.03
  6443.4  391.03  6484.3  386.01    8122  389.58    9514  405.64  9600.9   401.9
 10092.9  420.68 10288.1  428.08 10373.8  429.43 10435.2  442.12 10475.8   441.7
#Mann= 7 ,-1 , 0
   175.4     .05       0    4147     .12       0  4964.3     .07       0
  5014.3     .12       0  5110.8     .05       0 10092.9    .075       0
 10288.1     .05       0
Bank Sta=4964.3,5014.3
XS Rating Curve= 0 ,0
Exp/Cntr=0.3,0.1

Type RM Length L Ch R = 1 ,15040   ,620,620,620
BEGIN DESCRIPTION:
Mapping XS 4c634682
END DESCRIPTION:
XS GIS Cut Line= 5
      2631704.84      6904959.07      2628845.61      6905536.37
      2626803.78      6906037.68      2623081.72      6906546.79
      2621409.27      6906727.54
#Sta/Elev= 30
   -19.4  410.37   289.2  409.59  1147.3  404.58    1282  403.61    1409  402.72
  1616.3  403.07  2581.8  392.59  2690.8  406.75  2815.5  390.47  4521.1  385.67
  4951.2   386.1  4966.8  384.34  4967.8  372.18  4971.8  371.18  5017.8  372.18
  5057.3  385.82    5480  384.91  5627.3  385.75  5827.8  388.81  6228.8  385.68
  6429.3  386.93  6787.2  386.79  7328.2  387.63  8368.9  390.31  8455.2  407.06
  8550.5  391.63  9203.8  391.64  9434.3  394.91 10360.6  421.04 10438.9   421.1
#Mann= 20 ,-1 , 0
   -19.4    .075       0   289.2     .05       0  1147.3    .075       0
    1282     .05       0    1409      .1       0  1616.3     .05       0
  2581.8     .05       0  4521.1     .12       0  4967.8     .07       0
  5017.8     .12       0    5480     .05       0  5627.3    .075       0
  5827.8     .05       0  6228.8     .12       0  6429.3     .05       0
  6787.2     .12       0  7328.2     .05       0  9203.8     .05       0
  9434.3    .075       0 10360.6     .05       0
Bank Sta=4967.8,5017.8
XS Rating Curve= 0 ,0
Exp/Cntr=0.3,0.1

Type RM Length L Ch R = 1 ,14420   ,2388,2388,2388
BEGIN DESCRIPTION:
Mapping XS 9c40025c
END DESCRIPTION:
XS GIS Cut Line= 4
      2631596.37      6904644.39      2629602.55      6904946.09
      2626793.53      6905477.34      2621874.12      6906304.55
#Sta/Elev= 30
   208.2  411.26  2353.5  388.04  2740.2  388.54  2862.4  406.86  2964.1  388.45
  4897.8  385.87  4938.5  382.75  4946.4  370.51  4950.4  369.51  4996.4  370.51
  5009.8   382.8  5070.8  385.89  5842.3  388.54  6130.5  387.39  6514.5  387.93
  6918.1  387.36    7376  387.73  7504.5  388.09  7778.4   384.1  8243.2  391.41
  8341.3  391.74  8507.7  393.06    8549  393.84  8609.9  408.33    8656  407.63
  8750.4  391.98  9076.3  392.76  9806.4  407.36  9840.7  402.14   10072  414.73
#Mann= 13 ,-1 , 0
   208.2     .05       0  4946.4     .03       0  4996.4     .05       0
  5842.3    .075       0  6130.5     .05       0  6514.5    .075       0
  6918.1     .05       0    7376    .075       0  7504.5     .05       0
  8243.2    .075       0  8341.3     .05       0  8507.7    .075       0
    8656     .05       0
Bank Sta=4946.4,4996.4
XS Rating Curve= 0 ,0
Exp/Cntr=0.3,0.1