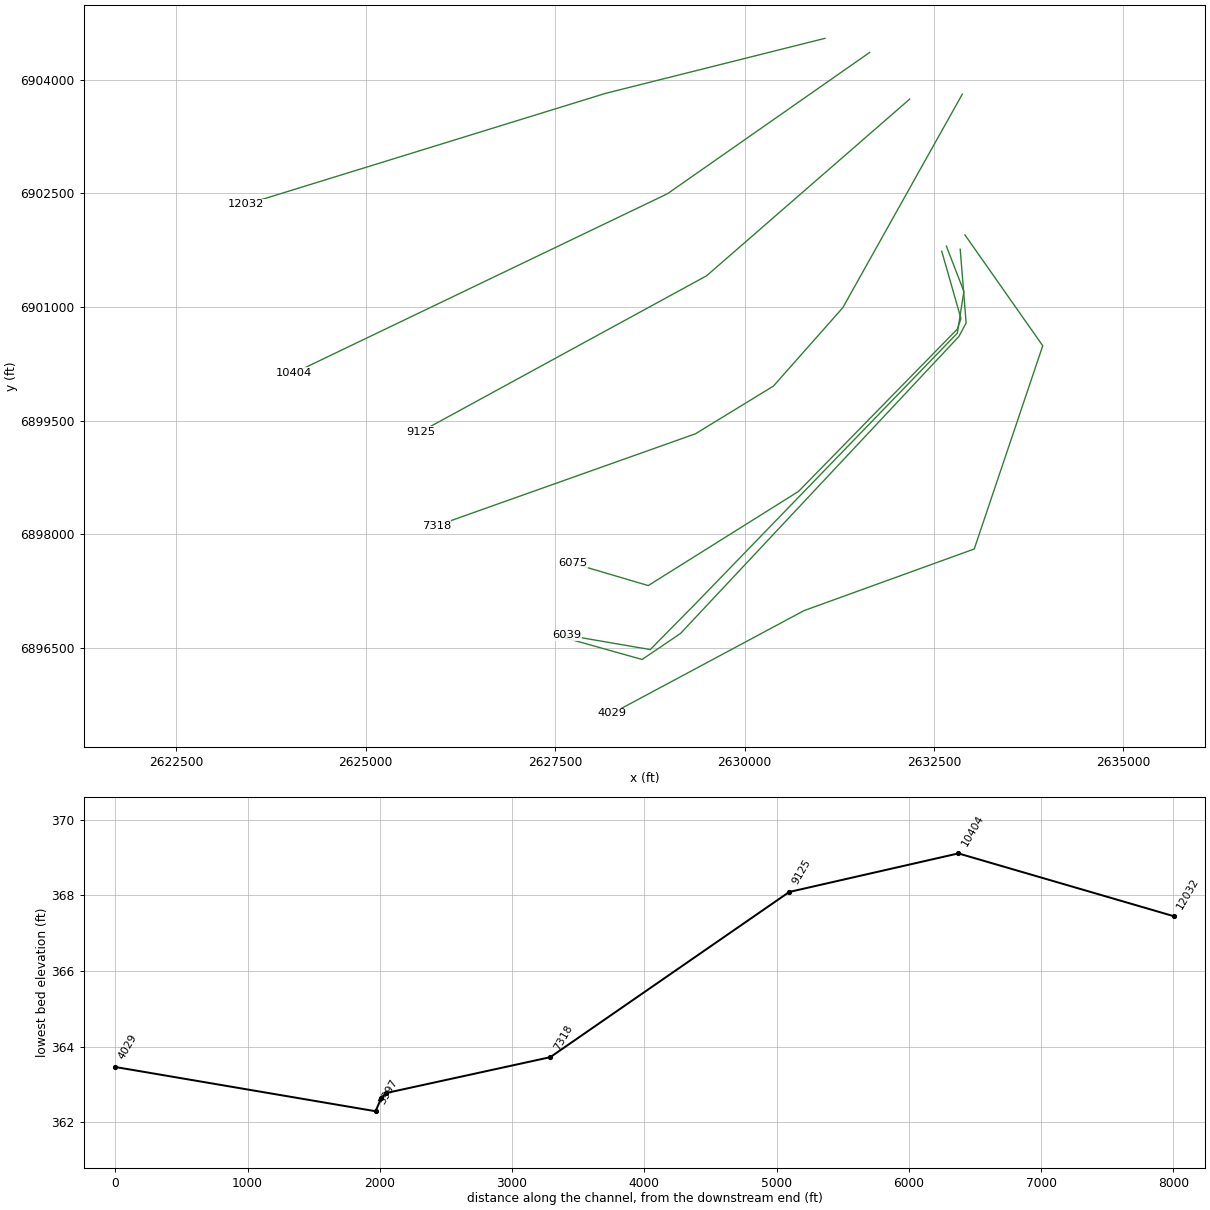
HEC-RAS study Big Brushy Creek.prj: Big Brushy Creek Base Level Engineering

--- Big Brushy Creek.g01 (geometry) --- (continued)

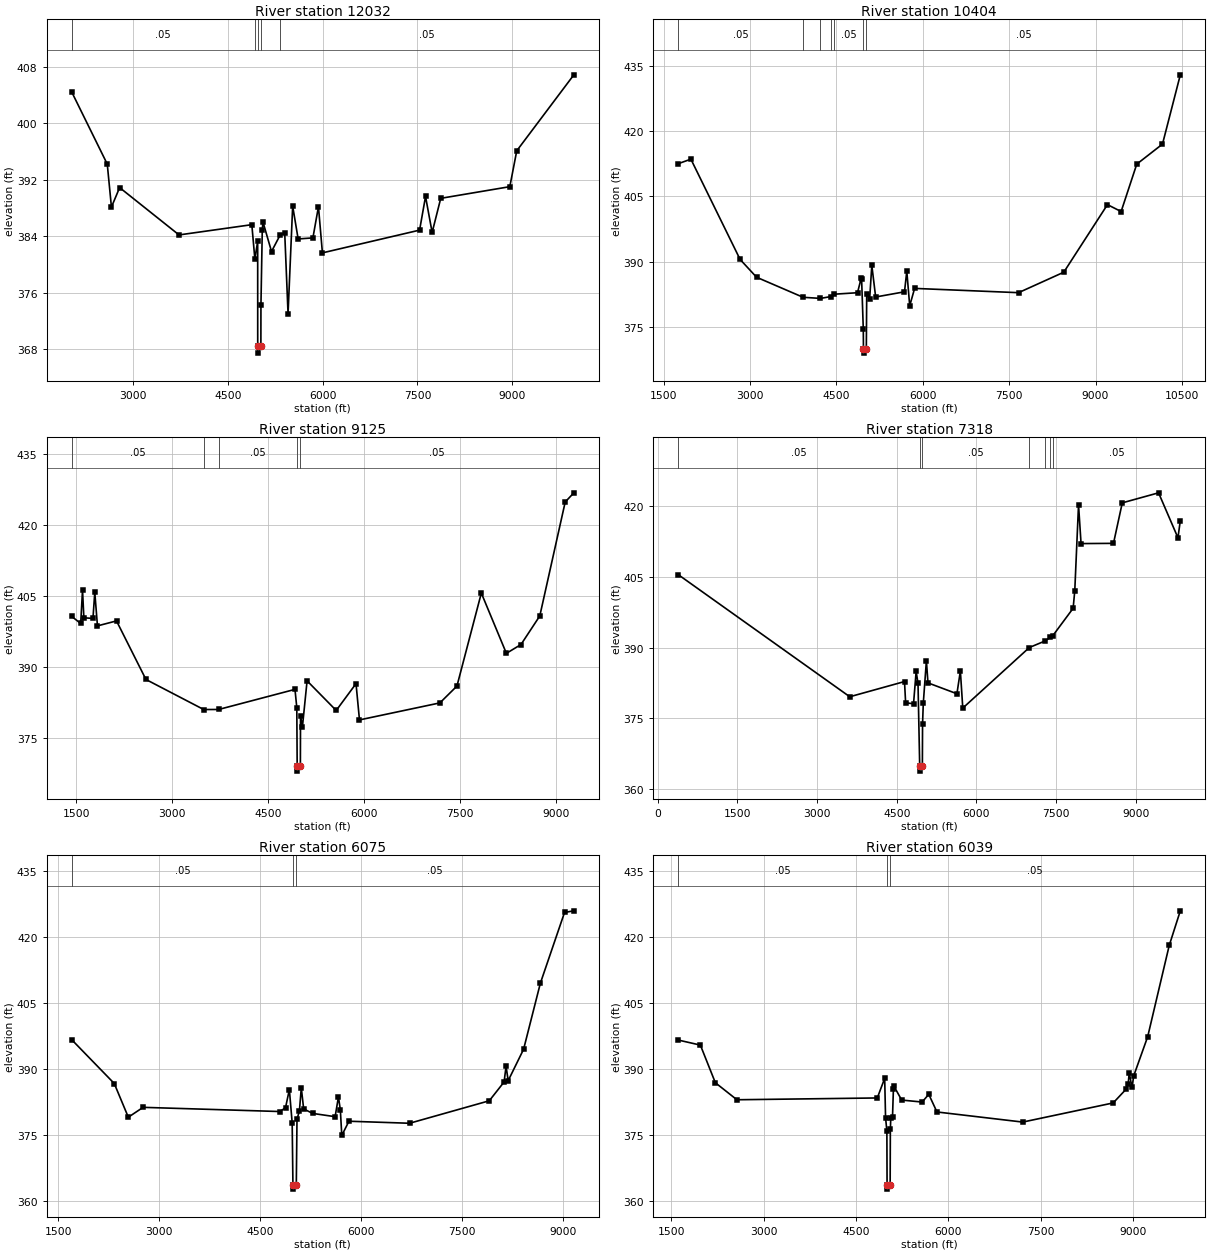
Type RM Length L Ch R = 1 ,12032   ,1628,1628,1628
BEGIN DESCRIPTION:
Mapping XS 52a63fbe
END DESCRIPTION:
XS GIS Cut Line= 3
      2631061.15      6904548.65      2628164.06      6903821.67
      2623422.28      6902356.81
#Sta/Elev= 30
  2026.7   404.4  2588.8   394.2  2654.8  388.12  2784.6  390.88  3725.1  384.18
  4877.6  385.63  4925.6  380.78  4970.4  383.28    4971  368.45    4975  367.45
    5021  368.45    5022  374.25    5043  384.82  5053.4  386.04  5189.5  381.83
  5327.4  384.19  5398.8  384.41  5451.2  373.03  5524.4  388.26  5611.1  383.61
  5844.8  383.76  5932.6  388.17  5995.4  381.64    7534  384.86  7628.2  389.62
  7732.8  384.53  7868.9  389.36  8962.7  391.01  9072.5  396.09  9976.5  406.84
#Mann= 5 ,-1 , 0
  2026.7     .05       0  4925.6     .12       0    4971     .07       0
    5021     .12       0  5327.4     .05       0
Bank Sta=4971,5021
XS Rating Curve= 0 ,0
Exp/Cntr=0.3,0.1

Type RM Length L Ch R = 1 ,10404   ,1279,1279,1279
BEGIN DESCRIPTION:
Mapping XS 65901f79
END DESCRIPTION:
XS GIS Cut Line= 3
      2631650.64       6904362.3      2628981.33      6902495.96
      2624055.08      6900130.48
#Sta/Elev= 30
  1750.9  412.51  1970.7  413.55  2825.3  390.58  3111.4   386.5  3920.4   381.9
  4222.1  381.65  4399.7  382.06  4459.7  382.61  4865.1  382.95    4929  386.27
  4936.6  385.99  4965.7  374.58  4968.3  370.11  4972.3  369.11  5018.3  370.11
    5025  382.63    5076  381.55  5113.7   389.2  5180.3  381.97  5681.4  383.16
  5721.2  387.89    5772  379.95  5856.9  383.94  7662.1  382.96  8448.6  387.65
    9207  403.13  9444.5  401.55  9716.2  412.41 10163.1     417 10472.7  432.87
#Mann= 7 ,-1 , 0
  1750.9     .05       0  3920.4     .12       0  4222.1     .05       0
  4399.7     .12       0  4459.7     .05       0  4968.3     .03       0
  5018.3     .05       0
Bank Sta=4968.3,5018.3
XS Rating Curve= 0 ,0
Exp/Cntr=0.3,0.1

Type RM Length L Ch R = 1 ,9125    ,1807,1807,1807
BEGIN DESCRIPTION:
Mapping XS e458dfff
END DESCRIPTION:
XS GIS Cut Line= 3
       2632178.8      6903745.69       2629498.7      6901412.81
      2625722.65      6899351.17
#Sta/Elev= 30
  1430.6   400.7  1570.4  399.23  1598.8  406.28  1619.9  400.42  1762.2   400.3
  1790.7  405.82  1832.4  398.72  2130.5  399.77    2591  387.42  3495.3  381.08
  3728.2  381.09  4922.9  385.33  4951.4  381.49  4957.3  369.09  4961.3  368.09
  5007.3  369.09  5009.7  379.81    5039  377.38  5112.2  387.13  5567.9  380.88
  5877.9  386.54    5932  378.89  7190.3  382.48    7457  386.03  7838.5  405.64
  8230.4  392.93  8459.1  394.79  8753.3  400.82  9150.9  424.85    9286  426.78
#Mann= 5 ,-1 , 0
  1430.6     .05       0  3495.3     .12       0  3728.2     .05       0
  4957.3     .03       0  5007.3     .05       0
Bank Sta=4957.3,5007.3
XS Rating Curve= 0 ,0
Exp/Cntr=0.3,0.1

Type RM Length L Ch R = 1 ,7318    ,1243,1243,1243
BEGIN DESCRIPTION:
Mapping XS 91ddd203
END DESCRIPTION:
XS GIS Cut Line= 5
      2632873.25      6903810.78      2631295.84      6900990.62
      2630380.84      6899956.15      2629351.12      6899325.74
      2625930.99      6898110.47
#Sta/Elev= 30
   387.6  405.49  3615.9  379.53  4646.2  382.76  4667.1  378.25    4816  378.04
  4865.3  384.92  4900.4  382.35  4932.3  364.72  4936.3  363.72  4982.3  364.72
  4985.8  373.73  4999.9  378.18  5058.1  387.19  5087.8  382.48  5632.6  380.17
  5697.5  385.01  5742.9  377.12  6994.9  389.99    7285  391.36  7389.2  392.13
  7434.8  392.47    7820  398.34  7850.9   402.1  7921.4  420.32    7969  412.09
  8579.4  412.14  8744.6  420.75  9427.7  422.88  9792.6  413.32    9837  416.98
#Mann= 7 ,-1 , 0
   387.6     .05       0  4932.3     .03       0  4982.3     .05       0
  6994.9      .1       0    7285     .05       0  7389.2      .1       0
  7434.8     .05       0
Bank Sta=4932.3,4982.3
XS Rating Curve= 0 ,0
Exp/Cntr=0.3,0.1

Type RM Length L Ch R = 1 ,6075    ,36,36,36
BEGIN DESCRIPTION:
Mapping XS 0b89d57d
END DESCRIPTION:
XS GIS Cut Line= 6
      2632601.99      6901737.65       2632855.9      6900847.88
      2632808.15      6900708.99       2630711.8      6898564.89
      2628728.29       6897321.4      2627731.41      6897616.13
#Sta/Elev= 30
  1702.1  396.65    2333  386.72  2541.4  379.08  2760.9  381.32  4789.7  380.37
  4874.6  381.23  4931.8  385.35  4973.5   377.8  4984.8  363.77  4988.8  362.77
  5034.8  363.77  5045.1  378.66  5080.6  380.44  5108.9  385.73  5144.1  380.96
  5278.4  379.94    5611   379.2  5660.3  383.69  5688.6  380.73    5710  374.94
    5816  378.17    6716  377.71  7899.2  382.81  8118.7  387.07  8148.5   390.6
  8179.8  387.37  8408.6   394.5  8657.2  409.46  9016.1  425.52  9154.4  425.89
#Mann= 3 ,-1 , 0
  1702.1     .05       0  4984.8     .07       0  5034.8     .05       0
Bank Sta=4984.8,5034.8
XS Rating Curve= 0 ,0
Exp/Cntr=0.3,0.1

Type RM Length L Ch R = 1 ,6039    ,42,42,42
BEGIN DESCRIPTION:
Mapping XS 271e67bf
END DESCRIPTION:
XS GIS Cut Line= 6
      2632663.19      6901805.34      2632894.34      6901205.35
      2632807.53      6900654.57      2629369.94      6897100.43
      2628755.36      6896476.47      2627651.66      6896666.12
#Sta/Elev= 30
  1611.2  396.56  1970.8  395.41  2213.8  386.85  2564.3  382.97  4844.5  383.38
  4964.6  387.85  4978.8  378.87  5000.1  375.89  5003.3  363.63  5007.3  362.63
  5053.3  363.63  5056.6  376.22  5063.6  378.83  5091.9  379.14  5106.1  385.37
  5113.2   386.1  5240.5   382.9  5572.9  382.45  5680.6  384.21  5813.5  380.19
  7206.9  377.89  8676.3  382.25  8882.1  385.32  8919.8  386.63    8937  389.12
  8980.7  385.78  9011.1  388.47  9236.8  397.34  9586.5   418.1  9766.4  425.97
#Mann= 3 ,-1 , 0
  1611.2     .05       0  5003.3    .065       0  5053.3     .05       0
Bank Sta=5003.3,5053.3
XS Rating Curve= 0 ,0
Exp/Cntr=0.3,0.1

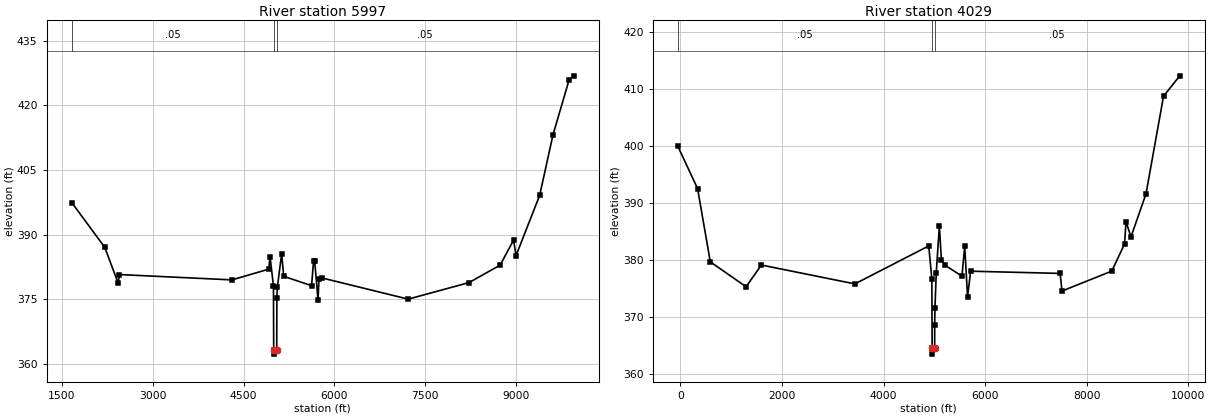
Type RM Length L Ch R = 1 ,5997    ,1968,1968,1968
BEGIN DESCRIPTION:
Mapping XS 2c0e9c35
END DESCRIPTION:
XS GIS Cut Line= 6
      2632845.92       6901763.2      2632924.04      6900789.28
      2632826.84      6900609.07      2629154.52      6896689.15
      2628647.69       6896345.4      2627571.26      6896647.49
#Sta/Elev= 30
    1661  397.43  2206.8  387.03  2427.8  378.75  2447.8  380.74  4307.5   379.5
  4915.5  381.99  4936.7  384.89  4993.1   378.1    4997  363.29    5001  362.29
    5047  363.29  5049.6   375.4  5057.1  377.75  5128.1  385.52  5163.2  380.32
  5623.1  378.16  5655.9  383.94  5673.5  383.94  5729.8  374.73  5744.5  379.61
    5794  379.95  7219.1  375.04  8222.7  378.87  8737.6  382.92  8959.4  388.71
  9000.9  385.14  9390.4  399.09  9610.5   413.1    9875  425.79    9951  426.81
#Mann= 3 ,-1 , 0
    1661     .05       0    4997     .03       0    5047     .05       0
Bank Sta=4997,5047
XS Rating Curve= 0 ,0
Exp/Cntr=0.3,0.1

Type RM Length L Ch R = 1 ,4029    ,0,0,0
BEGIN DESCRIPTION:
Mapping XS bd8553cf
END DESCRIPTION:
XS GIS Cut Line= 5
      2632908.25      6901952.35      2633935.26       6900488.7
      2633031.01      6897804.51      2630784.92      6896990.71
      2628251.87       6895633.6
#Sta/Elev= 30
   -48.7  399.87   338.4  392.47   588.6  379.64  1293.6  375.27  1594.3  379.08
  3435.8  375.77  4890.6  382.43  4951.8  376.62  4957.5  364.46  4961.5  363.46
  5007.5  364.46  5007.8  368.49  5013.1  371.52  5038.4   377.7  5099.7   385.9
  5140.8   379.9  5216.9  379.01    5545  377.13  5599.1  382.43  5655.1   373.5
  5716.3     378  7477.3  377.61  7515.4  374.52    8496  378.02  8747.8  382.79
  8775.4  386.69  8873.8  384.02  9169.5  391.56  9514.7  408.68  9834.4  412.25
#Mann= 3 ,-1 , 0
   -48.7     .05       0  4957.5     .03       0  5007.5     .05       0
Bank Sta=4957.5,5007.5
XS Rating Curve= 0 ,0
Exp/Cntr=0.3,0.1

Chan Stop Cuts=-1
Use User Specified Reach Order=0
Composite Channel Slope=5