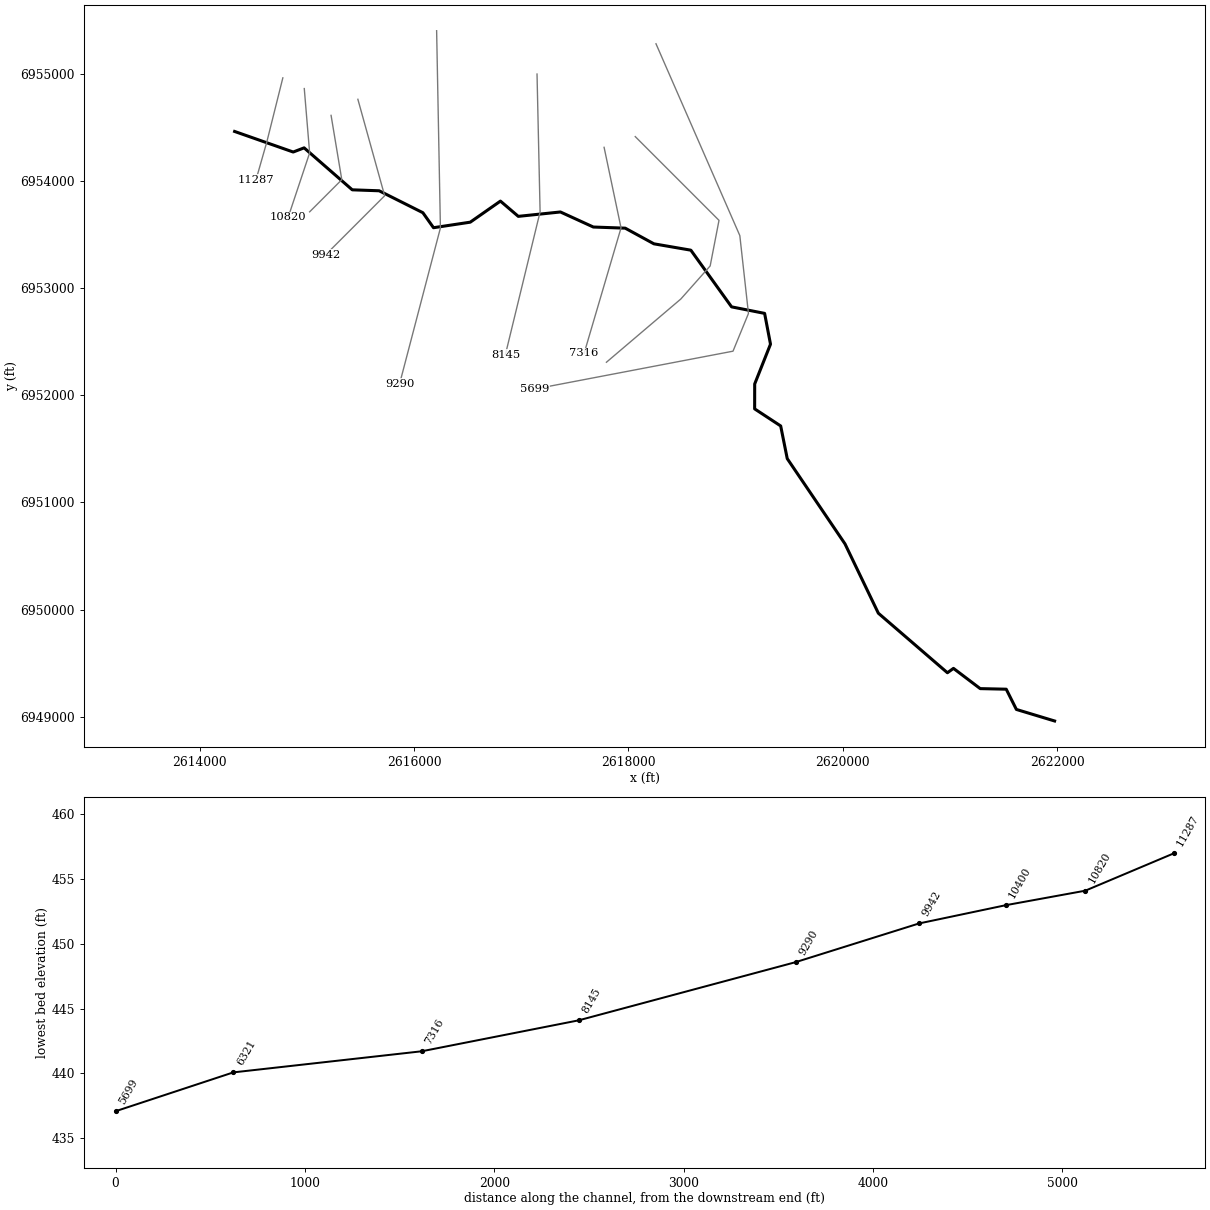
--- Big Brushy Creek Trib 1.prj (project) ---

Proj Title=Big Brushy Creek Trib 1 Base Level Engineering
Current Plan=p01
Default Exp/Contr=0.3,0.1
English Units
Geom File=g01
Flow File=f01
Plan File=p01
BEGIN DESCRIPTION:
Big Brushy Creek Trib 1
END DESCRIPTION:

--- Big Brushy Creek Trib 1.p01 (plan) ---

Plan Title=Multiple Run
Short Identifier=Multiple
Geom File=g01
Flow File=f01
Subcritical Flow
K Sum by GR= 0
Std Step Tol= 0.01
Critical Tol= 0.01
Num of Std Step Trials= 20
Max Error Tol= 0.3
Flow Tol Ratio= 0.001
Split Flow NTrial= 30
Split Flow Tol= 0.02
Split Flow Ratio= 0.02
Log Output Level= 0
Friction Slope Method= 1
Unsteady Friction Slope Method= 2
Unsteady Bridges Friction Slope Method= 1
Parabolic Critical Depth
Global Vel Dist=  1 , 1 , 1
Global Log Level= 0
CheckData=True
Encroach Param= -1, 0, 0, 0
BEGIN DESCRIPTION:
Multiple Run
END DESCRIPTION:

--- Big Brushy Creek Trib 1.f01 (steady flow) ---

Flow Title=Multiple
Number of Profiles=7
Profile Names=10-year,25-year,50-year,1pct_min,100-year,1pct_plu,500-year
River Rch & RM= Big Brushy Creek,Reach-1,11287
     563     756     911     546    1089    2172    1552
River Rch & RM= Big Brushy Creek,Reach-1,8145
     612     824     995     597    1191    2377    1705
River Rch & RM= Big Brushy Creek,Reach-1,7316
     656     886    1072     644    1285    2563    1843
Boundary for River Rch & Prof#=Big Brushy Creek,Reach-1,1
Up Type=0
Dn Type=3
Dn Slope=0.005
Boundary for River Rch & Prof#=Big Brushy Creek,Reach-1,2
Up Type=0
Dn Type=3
Dn Slope=0.005
Boundary for River Rch & Prof#=Big Brushy Creek,Reach-1,3
Up Type=0
Dn Type=3
Dn Slope=0.005
Boundary for River Rch & Prof#=Big Brushy Creek,Reach-1,4
Up Type=0
Dn Type=3
Dn Slope=0.005
Boundary for River Rch & Prof#=Big Brushy Creek,Reach-1,5
Up Type=0
Dn Type=3
Dn Slope=0.005
Boundary for River Rch & Prof#=Big Brushy Creek,Reach-1,6
Up Type=0
Dn Type=3
Dn Slope=0.005
Boundary for River Rch & Prof#=Big Brushy Creek,Reach-1,7
Up Type=0
Dn Type=3
Dn Slope=0.005

--- Big Brushy Creek Trib 1.g01 (geometry) ---

Geom Title=Existing Conditions

River Reach=Big Brushy Creek,Reach-1
Reach XY= 30
      2614326.00      6954461.00      2614872.69      6954269.07
      2614974.57      6954307.93      2615423.55      6953916.46
      2615674.53      6953907.45      2616082.34      6953702.97
      2616181.71      6953562.89      2616524.50      6953614.61
      2616805.94      6953811.22      2616972.59      6953668.82
      2617365.50      6953709.80      2617672.78      6953569.28
      2617970.06      6953558.74      2618237.84      6953412.66
      2618582.47      6953353.30      2618962.37      6952824.44
      2619270.58      6952763.75      2619325.50      6952476.22
      2619178.07      6952105.15      2619177.62      6951872.81
      2619420.54      6951713.46      2619481.76      6951408.64
      2620020.46      6950613.42      2620331.59      6949966.61
      2620976.00      6949411.00      2621032.51      6949451.86
      2621281.85      6949263.06      2621524.78      6949257.56
      2621619.50      6949068.73      2621976.00      6948961.00

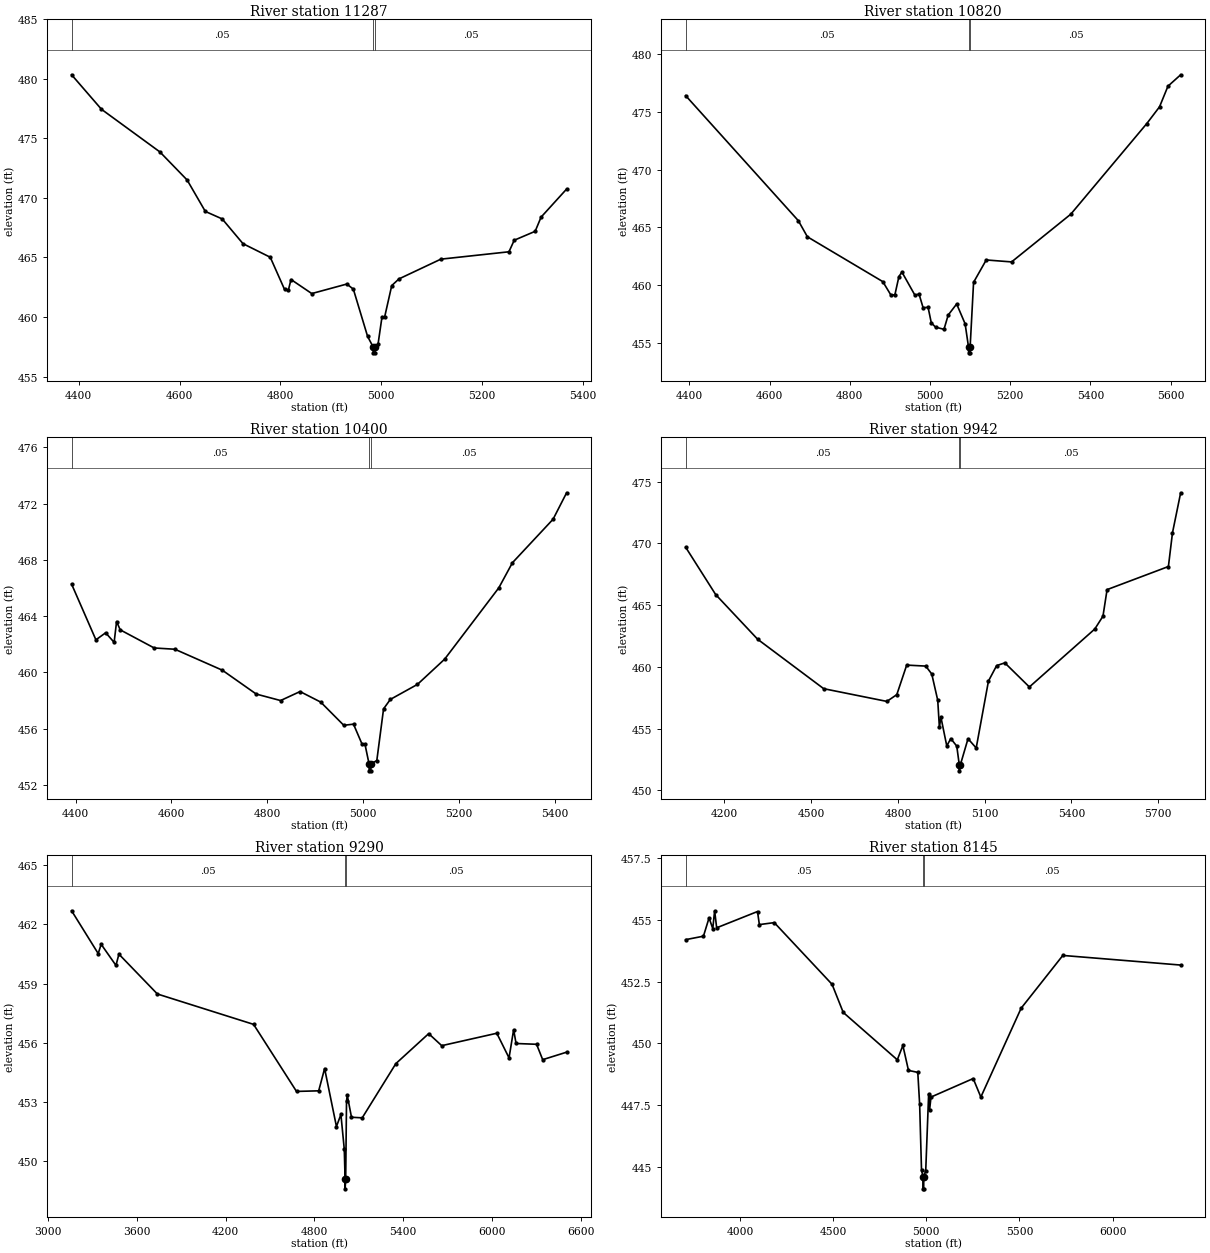
Type RM Length L Ch R = 1,11287,467,467,467
BEGIN DESCRIPTION:
Big Brushy Creek Trib 1 15.0
END DESCRIPTION:
XS GIS Cut Line= 3
      2614776.00      6954961.00      2614626.00      6954361.00
      2614525.99      6954010.97
#Sta/Elev= 30
  4385.8  480.35  4445.1  477.45  4561.0  473.87  4615.1  471.51  4651.2  468.87
  4684.7  468.24  4726.0  466.16  4780.1  465.02  4808.4  462.32  4816.1  462.27
  4821.3  463.15  4862.5  461.97  4932.1  462.77  4945.0  462.34  4973.3  458.37
  4984.2  457.49  4984.5  456.99  4988.0  456.99  4988.2  457.49  4994.0  457.71
  5001.7  459.96  5006.9  459.96  5021.2  462.64  5035.5  463.20  5118.7  464.86
  5253.9  465.48  5264.3  466.45  5305.9  467.20  5317.6  468.39  5368.3  470.75
#Mann=3,-1,0
  4385.8    0.05       0  4984.2    0.03       0  4988.2    0.05       0
Bank Sta=4984.2,4988.2
Exp/Cntr=0.3,0.1

Type RM Length L Ch R = 1,10820,420,420,420
BEGIN DESCRIPTION:
Big Brushy Creek Trib 1 14.0
END DESCRIPTION:
XS GIS Cut Line= 3
      2614976.00      6954861.03      2615026.00      6954261.00
      2614825.99      6953660.96
#Sta/Elev= 30
  4390.7  476.43  4671.7  465.58  4694.3  464.18  4882.4  460.29  4902.5  459.13
  4912.5  459.14  4922.6  460.73  4930.1  461.12  4962.7  459.10  4972.7  459.22
  4982.8  458.04  4995.4  458.05  5003.3  456.72  5013.9  456.34  5035.0  456.15
  5045.5  457.39  5066.6  458.35  5087.7  456.63  5096.2  454.61  5096.5  454.11
  5100.0  454.11  5100.2  454.61  5108.8  460.23  5140.4  462.17  5203.6  462.00
  5351.2  466.14  5540.9  474.01  5572.6  475.46  5593.6  477.25  5625.3  478.24
#Mann=3,-1,0
  4390.7    0.05       0  5096.2    0.03       0  5100.2    0.05       0
Bank Sta=5096.2,5100.2
Exp/Cntr=0.3,0.1

Type RM Length L Ch R = 1,10400,458,458,458
BEGIN DESCRIPTION:
Big Brushy Creek Trib 1 13.0
END DESCRIPTION:
XS GIS Cut Line= 3
      2615226.00      6954611.00      2615326.00      6954011.00
      2615026.03      6953711.03
#Sta/Elev= 30
  4391.7  466.27  4442.4  462.31  4462.7  462.81  4480.4  462.13  4485.5  463.61
  4493.1  463.02  4564.0  461.73  4607.1  461.64  4706.0  460.15  4776.9  458.45
  4827.6  457.99  4868.2  458.63  4911.3  457.88  4959.4  456.23  4979.7  456.31
  4997.4  454.90  5003.5  454.90  5012.1  453.49  5012.4  452.99  5015.9  452.99
  5016.1  453.49  5028.3  453.72  5042.4  457.40  5056.5  458.07  5113.1  459.14
  5169.7  460.93  5282.8  466.01  5311.1  467.79  5396.0  470.89  5424.2  472.77
#Mann=3,-1,0
  4391.7    0.05       0  5012.1   0.035       0  5016.1    0.05       0
Bank Sta=5012.1,5016.1
Exp/Cntr=0.3,0.1

Type RM Length L Ch R = 1,9942,652,652,652
BEGIN DESCRIPTION:
Big Brushy Creek Trib 1 12.0
END DESCRIPTION:
XS GIS Cut Line= 3
      2615476.00      6954761.02      2615726.00      6953861.00
      2615176.01      6953311.01
#Sta/Elev= 30
  4065.9  469.68  4169.7  465.85  4315.0  462.23  4543.3  458.23  4761.8  457.20
  4796.1  457.75  4830.3  460.14  4896.2  460.06  4917.0  459.42  4937.7  457.29
  4943.4  455.09  4948.6  455.93  4968.9  453.60  4982.9  454.19  5003.5  453.58
  5012.1  452.08  5012.4  451.58  5016.1  452.08  5042.4  454.18  5070.7  453.43
  5113.1  458.85  5141.4  460.10  5169.7  460.32  5254.6  458.37  5480.8  463.06
  5509.1  464.10  5523.3  466.25  5735.4  468.12  5749.5  470.85  5777.8  474.09
#Mann=3,-1,0
  4065.9    0.05       0  5012.1    0.03       0  5016.1    0.05       0
Bank Sta=5012.1,5016.1
Exp/Cntr=0.3,0.1

Type RM Length L Ch R = 1,9290,1145,1145,1145
BEGIN DESCRIPTION:
Big Brushy Creek Trib 1 11.0
END DESCRIPTION:
XS GIS Cut Line= 3
      2616210.73      6955400.72      2616246.06      6953560.46
      2615864.67      6952104.59
#Sta/Elev= 30
  3159.4  462.69  3339.2  460.52  3359.2  460.99  3459.2  459.92  3479.2  460.49
  3739.2  458.47  4389.3  456.93  4679.4  453.53  4829.4  453.56  4869.4  454.69
  4949.4  451.75  4979.5  452.36  5002.3  450.60  5007.8  449.09  5008.0  448.59
  5011.8  449.09  5017.5  453.05  5022.6  453.33  5051.1  452.22  5123.5  452.19
  5350.9  454.94  5572.8  456.46  5661.0  455.85  6033.2  456.48  6115.9  455.23
  6146.9  456.66  6163.4  455.96  6302.0  455.92  6343.3  455.14  6505.0  455.52
#Mann=3,-1,0
  3159.4    0.05       0  5007.8    0.04       0  5011.8    0.05       0
Bank Sta=5007.8,5011.8
Exp/Cntr=0.3,0.1

Type RM Length L Ch R = 1,8145,829,829,829
BEGIN DESCRIPTION:
Big Brushy Creek Trib 1 9.0
END DESCRIPTION:
XS GIS Cut Line= 3
      2617147.39      6954996.48      2617176.00      6953711.00
      2616852.27      6952378.98
#Sta/Elev= 30
  3708.6  454.20  3804.1  454.34  3834.1  455.08  3854.1  454.65  3864.1  455.37
  3875.0  454.68  4094.2  455.34  4104.2  454.81  4184.2  454.89  4494.3  452.39
  4554.3  451.25  4844.4  449.33  4874.4  449.91  4904.4  448.90  4954.4  448.82
  4964.4  447.52  4974.4  444.85  4982.4  444.60  4982.6  444.10  4986.1  444.10
  4986.4  444.60  4997.0  444.83  5012.7  447.95  5017.9  447.31  5025.3  447.82
  5251.7  448.57  5292.8  447.82  5509.0  451.42  5732.8  453.56  6365.2  453.17
#Mann=3,-1,0
  3708.6    0.05       0  4982.4    0.04       0  4986.4    0.05       0
Bank Sta=4982.4,4986.4
Exp/Cntr=0.3,0.1

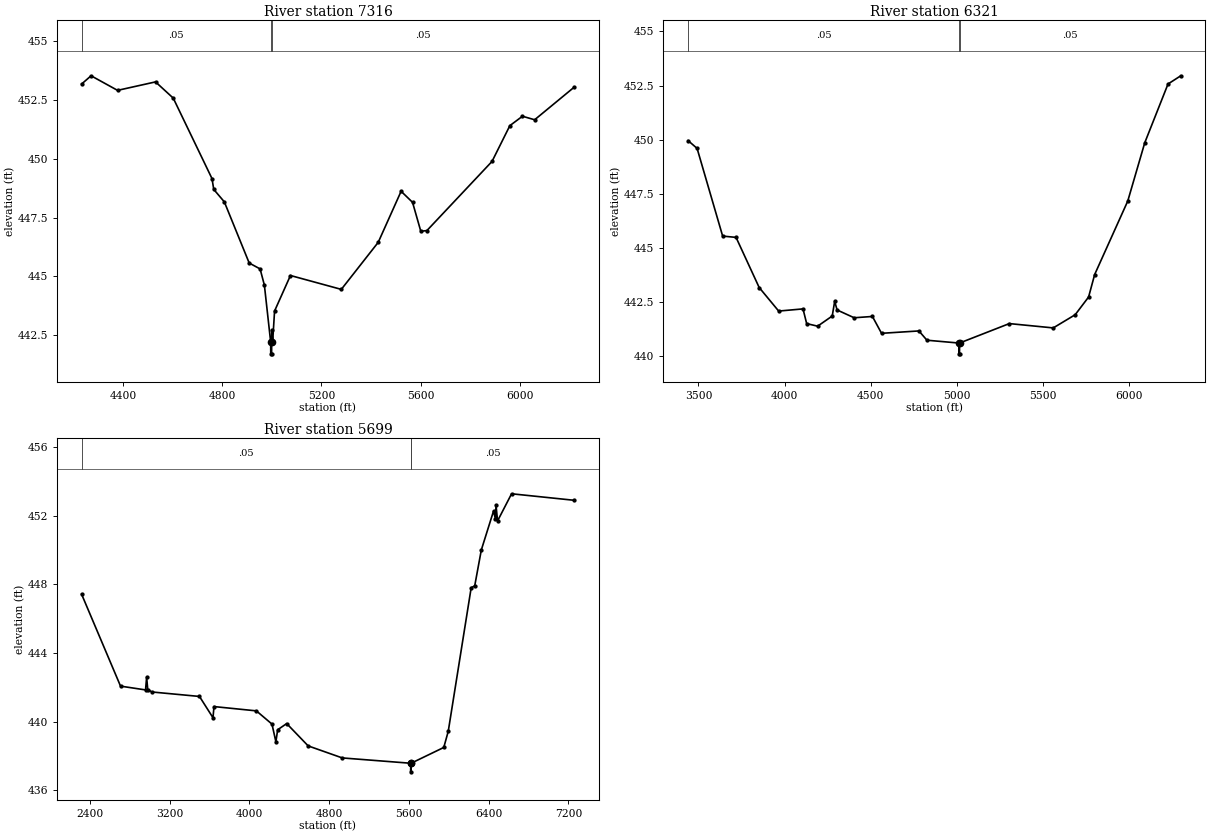
Type RM Length L Ch R = 1,7316,995,995,995
BEGIN DESCRIPTION:
Big Brushy Creek Trib 1 7.0
END DESCRIPTION:
XS GIS Cut Line= 3
      2617773.06      6954312.98      2617931.18      6953561.43
      2617586.41      6952390.22
#Sta/Elev= 30
  4232.0  453.18  4270.2  453.53  4377.1  452.91  4530.4  453.27  4601.9  452.58
  4758.3  449.16  4765.4  448.70  4808.1  448.17  4908.5  445.57  4952.5  445.32
  4969.8  444.63  4995.2  442.21  4995.5  441.71  4999.0  441.71  4999.2  442.21
  4999.6  442.71  5003.1  442.21  5010.9  443.53  5075.0  445.04  5280.3  444.45
  5429.3  446.45  5521.7  448.62  5567.9  448.15  5601.2  446.92  5625.9  446.95
  5888.8  449.89  5960.7  451.41  6011.6  451.81  6060.8  451.66  6220.9  453.05
#Mann=3,-1,0
  4232.0    0.05       0  4995.2    0.04       0  4999.2    0.05       0
Bank Sta=4995.2,4999.2
Exp/Cntr=0.3,0.1

Type RM Length L Ch R = 1,6321,622,622,622
BEGIN DESCRIPTION:
Mapping XS 52f57f26
END DESCRIPTION:
XS GIS Cut Line= 5
      2618063.84      6954412.84      2618845.10      6953631.58
      2618762.64      6953206.23      2618489.20      6952898.07
      2617794.78      6952307.82
#Sta/Elev= 30
  3439.9  449.95  3492.2  449.59  3640.7  445.53  3718.5  445.47  3852.8  443.15
  3966.0  442.06  4107.4  442.16  4128.6  441.48  4192.3  441.36  4277.1  441.83
  4291.3  442.51  4305.4  442.11  4404.4  441.75  4510.5  441.81  4563.5  441.03
  4780.6  441.14  4827.2  440.71  5012.5  440.58  5012.8  440.08  5016.3  440.08
  5016.5  440.58  5305.6  441.48  5560.7  441.28  5688.1  441.89  5766.0  442.71
  5801.2  443.75  5993.4  447.15  6092.2  449.85  6227.3  452.57  6301.4  452.95
#Mann=3,-1,0
  3439.9    0.05       0  5012.5    0.03       0  5016.5    0.05       0
Bank Sta=5012.5,5016.5
Exp/Cntr=0.3,0.1

Type RM Length L Ch R = 1,5699,0,0,0
BEGIN DESCRIPTION:
Big Brushy Creek Trib 1 6.0
END DESCRIPTION:
XS GIS Cut Line= 5
      2618257.24      6955278.84      2619039.39      6953489.29
      2619119.89      6952762.84      2618975.79      6952411.10
      2617129.57      6952058.52
#Sta/Elev= 30
  2316.1  447.42  2706.6  442.07  2957.6  441.85  2968.5  442.59  2979.8  441.87
  3021.1  441.73  3498.5  441.47  3634.3  440.23  3644.3  440.88  4069.4  440.63
  4226.1  439.86  4265.4  438.83  4283.1  439.53  4373.8  439.89  4589.3  438.59
  4931.4  437.89  5617.8  437.58  5618.1  437.08  5621.8  437.58  5950.0  438.50
  5994.8  439.44  6224.9  447.80  6260.4  447.91  6326.7  450.00  6448.9  452.26
  6468.8  451.79  6473.9  452.61  6489.6  451.69  6630.2  453.27  7259.7  452.89
#Mann=3,-1,0
  2316.1    0.05       0  5617.8    0.03       0  5621.8    0.05       0
Bank Sta=5617.8,5621.8
Exp/Cntr=0.3,0.1

Chan Stop Cuts=-1