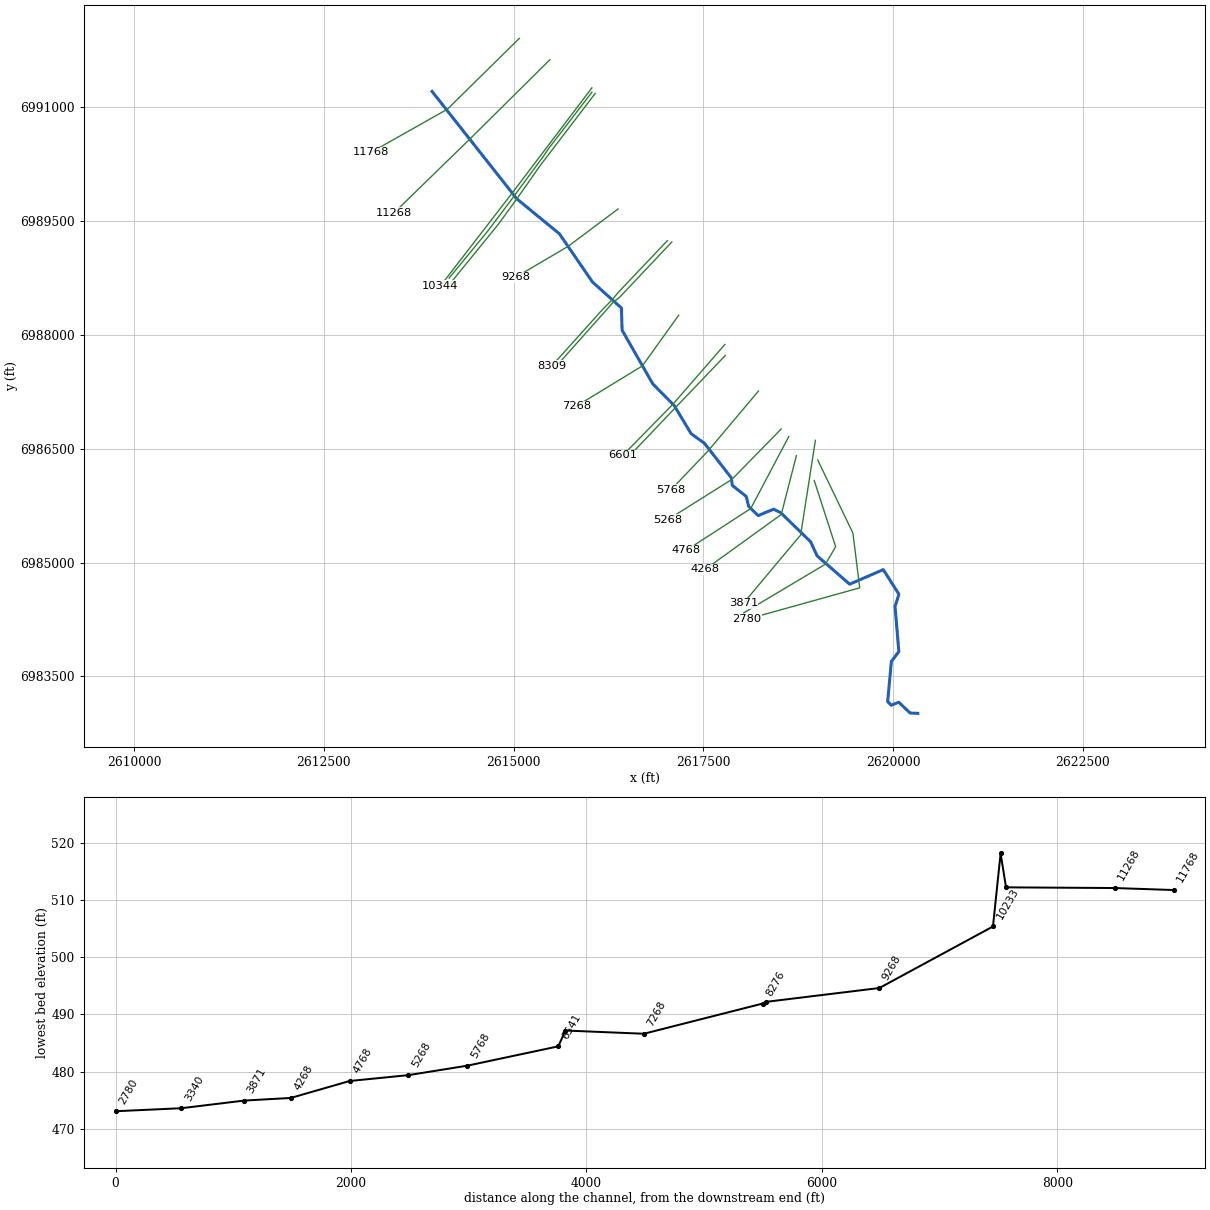
--- Big Brushy Creek Trib 10.prj (project) ---

Proj Title=Big Brushy Creek Trib 10 Base Level Engineering
Current Plan=p01
Default Exp/Contr=0.3,0.1
English Units
Geom File=g01
Flow File=f01
Plan File=p01
BEGIN DESCRIPTION:
Big Brushy Creek Trib 10
END DESCRIPTION:

--- Big Brushy Creek Trib 10.p01 (plan) ---

Plan Title=Multiple Run
Short Identifier=Multiple
Geom File=g01
Flow File=f01
Subcritical Flow
K Sum by GR= 0
Std Step Tol= 0.01
Critical Tol= 0.01
Num of Std Step Trials= 20
Max Error Tol= 0.3
Flow Tol Ratio= 0.001
Split Flow NTrial= 30
Split Flow Tol= 0.02
Split Flow Ratio= 0.02
Log Output Level= 0
Friction Slope Method= 1
Unsteady Friction Slope Method= 2
Unsteady Bridges Friction Slope Method= 1
Parabolic Critical Depth
Global Vel Dist=  1 , 1 , 1
Global Log Level= 0
CheckData=True
Encroach Param= -1, 0, 0, 0
BEGIN DESCRIPTION:
Multiple Run
END DESCRIPTION:

--- Big Brushy Creek Trib 10.f01 (steady flow) ---

Flow Title=Multiple
Number of Profiles=7
Profile Names=10-year,25-year,50-year,1pct_min,100-year,1pct_plu,500-year
River Rch & RM= Big Brushy Creek,Reach-1,11768
     719     976    1186     715    1426    2846    2062
River Rch & RM= Big Brushy Creek,Reach-1,9268
     892    1221    1491     903    1801    3593    2626
River Rch & RM= Big Brushy Creek,Reach-1,3340
     931    1275    1559     944    1883    3757    2748
Boundary for River Rch & Prof#=Big Brushy Creek,Reach-1,1
Up Type=0
Dn Type=3
Dn Slope=0.005
Boundary for River Rch & Prof#=Big Brushy Creek,Reach-1,2
Up Type=0
Dn Type=3
Dn Slope=0.005
Boundary for River Rch & Prof#=Big Brushy Creek,Reach-1,3
Up Type=0
Dn Type=3
Dn Slope=0.005
Boundary for River Rch & Prof#=Big Brushy Creek,Reach-1,4
Up Type=0
Dn Type=3
Dn Slope=0.005
Boundary for River Rch & Prof#=Big Brushy Creek,Reach-1,5
Up Type=0
Dn Type=3
Dn Slope=0.005
Boundary for River Rch & Prof#=Big Brushy Creek,Reach-1,6
Up Type=0
Dn Type=3
Dn Slope=0.005
Boundary for River Rch & Prof#=Big Brushy Creek,Reach-1,7
Up Type=0
Dn Type=3
Dn Slope=0.005

--- Big Brushy Creek Trib 10.g01 (geometry) ---

Geom Title=Existing Conditions

River Reach=Big Brushy Creek,Reach-1
Reach XY= 30
      2613926.00      6991211.00      2615042.65      6989794.33
      2615603.01      6989334.51      2616039.62      6988697.79
      2616420.82      6988355.56      2616429.75      6988062.55
      2616833.86      6987354.83      2617115.47      6987070.75
      2617339.62      6986697.76      2617515.35      6986571.00
      2617868.12      6986117.12      2617881.26      6986016.47
      2618065.48      6985870.79      2618095.63      6985740.84
      2618222.58      6985618.79      2618426.04      6985703.48
      2618520.38      6985655.44      2618912.39      6985274.24
      2618999.01      6985087.53      2619427.64      6984714.14
      2619870.39      6984906.23      2620076.67      6984581.08
      2620025.55      6984421.19      2620075.50      6983826.20
      2619976.92      6983695.06      2619928.05      6983166.45
      2619975.67      6983118.25      2620074.35      6983157.84
      2620223.50      6983016.35      2620326.00      6983011.00

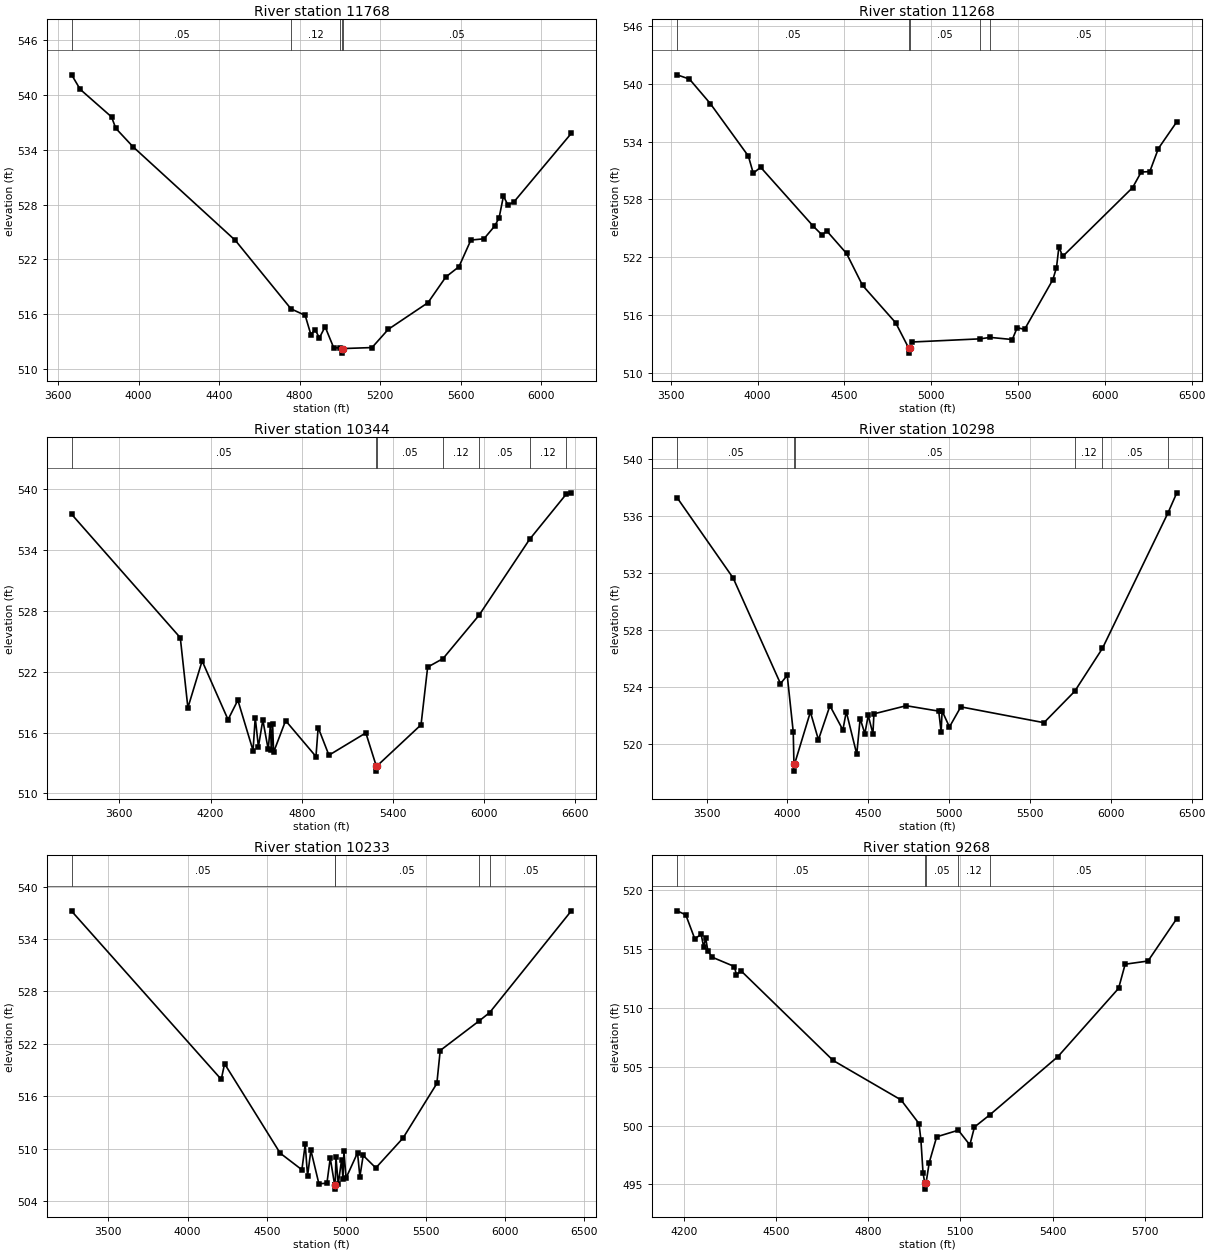
Type RM Length L Ch R = 1,11768,500,500,500
BEGIN DESCRIPTION:
Big Brushy Creek 252.0
END DESCRIPTION:
XS GIS Cut Line= 3
      2615076.00      6991911.00      2614126.93      6990975.96
      2613125.97      6990410.98
#Sta/Elev= 30
  3667.7  542.22  3710.1  540.63  3865.7  537.61  3886.9  536.36  3971.8  534.35
  4480.9  524.07  4757.2  516.57  4827.4  515.86  4855.7  513.76  4876.8  514.29
  4898.1  513.39  4926.4  514.61  4968.8  512.33  5002.3  512.27  5010.6  512.22
  5010.8  511.72  5014.6  512.22  5159.4  512.33  5240.3  514.33  5437.4  517.25
  5526.2  520.07  5591.2  521.19  5650.4  524.11  5715.4  524.25  5768.8  525.65
  5790.5  526.54  5812.2  528.93  5833.8  527.98  5862.3  528.24  6149.4  535.81
#Mann=5,-1,0
  3667.7    0.05       0  4757.2    0.12       0  5002.3    0.05       0
  5010.6    0.07       0  5014.6    0.05       0
Bank Sta=5010.6,5014.6
Exp/Cntr=0.3,0.1

Type RM Length L Ch R = 1,11268,924,924,924
BEGIN DESCRIPTION:
Big Brushy Creek 251.0
END DESCRIPTION:
XS GIS Cut Line= 3
      2615478.18      6991629.20      2614438.95      6990598.47
      2613426.02      6989611.02
#Sta/Elev= 30
  3536.3  540.92  3607.3  540.48  3727.5  537.94  3946.7  532.50  3975.0  530.72
  4017.4  531.34  4321.5  525.21  4370.9  524.33  4399.2  524.72  4512.4  522.40
  4604.3  519.10  4795.2  515.22  4871.0  512.57  4871.3  512.07  4875.0  512.57
  4887.2  513.22  5280.9  513.55  5340.2  513.70  5467.0  513.48  5495.3  514.71
  5537.7  514.53  5700.5  519.68  5721.6  520.94  5735.7  523.10  5757.0  522.09
  6160.1  529.23  6209.5  530.84  6259.1  530.89  6308.5  533.28  6414.6  536.05
#Mann=5,-1,0
  3536.3    0.05       0  4871.0    0.03       0  4875.0    0.05       0
  5280.9     0.1       0  5340.2    0.05       0
Bank Sta=4871,4875
Exp/Cntr=0.3,0.1

Type RM Length L Ch R = 1,10344,46,46,46
BEGIN DESCRIPTION:
Big Brushy Creek 250.0
END DESCRIPTION:
XS GIS Cut Line= 3
      2616031.26      6991257.60      2614996.38      6989891.16
      2614035.20      6988645.36
#Sta/Elev= 30
  3285.9  537.52  4000.7  525.35  4050.7  518.44  4144.3  523.06  4314.9  517.27
  4379.4  519.19  4479.3  514.22  4493.8  517.47  4514.6  514.59  4543.7  517.23
  4579.1  514.34  4593.7  516.73  4599.9  514.23  4608.2  516.80  4614.5  514.05
  4693.5  517.17  4893.3  513.63  4907.8  516.49  4978.6  513.76  5221.4  515.96
  5290.1  512.69  5290.3  512.19  5294.1  512.69  5584.6  516.76  5628.1  522.45
  5729.3  523.29  5966.9  527.58  6298.2  535.04  6538.2  539.48  6573.5  539.64
#Mann=7,-1,0
  3285.9    0.05       0  5290.1    0.03       0  5294.1    0.05       0
  5729.3    0.12       0  5966.9    0.05       0  6298.2    0.12       0
  6538.2    0.05       0
Bank Sta=5290.1,5294.1
Exp/Cntr=0.3,0.1

Type RM Length L Ch R = 1,10298,65,65,65
BEGIN DESCRIPTION:
Big Brushy Creek 249.0
END DESCRIPTION:
XS GIS Cut Line= 6
      2616032.10      6991201.14      2615462.64      6990459.44
      2615385.89      6990346.82      2614943.89      6989746.94
      2614652.22      6989360.70      2614150.56      6988750.24
#Sta/Elev= 30
  3317.5  537.31  3664.3  531.67  3957.0  524.26  3998.7  524.84  4035.9  520.87
  4040.2  518.62  4040.5  518.12  4044.2  518.62  4141.9  522.27  4191.7  520.32
  4262.8  522.71  4342.9  521.01  4363.9  522.29  4428.8  519.31  4449.7  521.81
  4478.8  520.75  4499.6  522.03  4528.7  520.74  4535.0  522.14  4734.7  522.71
  4935.7  522.33  4950.7  520.88  4956.7  522.34  5002.1  521.22  5072.4  522.63
  5586.7  521.52  5776.7  523.72  5948.6  526.74  6354.6  536.26  6408.3  537.65
#Mann=6,-1,0
  3317.5    0.05       0  4040.2    0.03       0  4044.2    0.05       0
  5776.7    0.12       0  5948.6    0.05       0  6354.6    0.12       0
Bank Sta=4040.2,4044.2
Exp/Cntr=0.3,0.1

Type RM Length L Ch R = 1,10233,965,965,965
BEGIN DESCRIPTION:
Big Brushy Creek 246.0
END DESCRIPTION:
XS GIS Cut Line= 5
      2616074.65      6991183.80      2615343.19      6990223.75
      2615042.65      6989794.33      2614796.32      6989456.18
      2614164.88      6988679.40
#Sta/Elev= 30
  3268.9  537.19  4212.2  517.92  4233.1  519.71  4583.6  509.47  4720.5  507.57
  4741.5  510.48  4756.3  506.87  4777.2  509.80  4827.8  505.96  4878.3  506.03
  4899.3  508.91  4926.9  505.85  4927.2  505.35  4930.9  505.85  4935.0  509.06
  4949.8  505.92  4970.8  508.72  4979.5  506.52  4985.6  509.68  4999.0  506.62
  5071.4  509.51  5086.1  506.77  5107.0  509.21  5186.6  507.78  5358.1  511.20
  5571.4  517.45  5592.6  521.23  5838.1  524.62  5904.2  525.57  6419.4  537.23
#Mann=5,-1,0
  3268.9    0.05       0  4926.9    0.03       0  4930.9    0.05       0
  5838.1    0.12       0  5904.2    0.05       0
Bank Sta=4926.9,4930.9
Exp/Cntr=0.3,0.1

Type RM Length L Ch R = 1,9268,959,959,959
BEGIN DESCRIPTION:
Big Brushy Creek 247.0
END DESCRIPTION:
XS GIS Cut Line= 3
      2616376.04      6989661.03      2615718.59      6989168.62
      2615026.04      6988761.02
#Sta/Elev= 30
  4178.6  518.22  4206.8  517.88  4236.0  515.85  4256.8  516.22  4265.1  515.15
  4271.4  515.92  4278.6  514.84  4292.2  514.29  4365.1  513.49  4371.4  512.78
  4386.0  513.14  4686.0  505.52  4906.9  502.17  4965.3  500.16  4971.5  498.76
  4978.3  496.01  4984.0  495.10  4984.3  494.60  4988.1  495.10  4998.5  496.85
  5022.7  499.04  5093.1  499.60  5130.6  498.35  5145.6  499.87  5196.2  500.92
  5417.1  505.85  5614.3  511.64  5635.7  513.69  5710.0  513.96  5803.6  517.56
#Mann=5,-1,0
  4178.6    0.05       0  4984.0    0.03       0  4988.1    0.05       0
  5093.1    0.12       0  5196.2    0.05       0
Bank Sta=4984,4988.1
Exp/Cntr=0.3,0.1

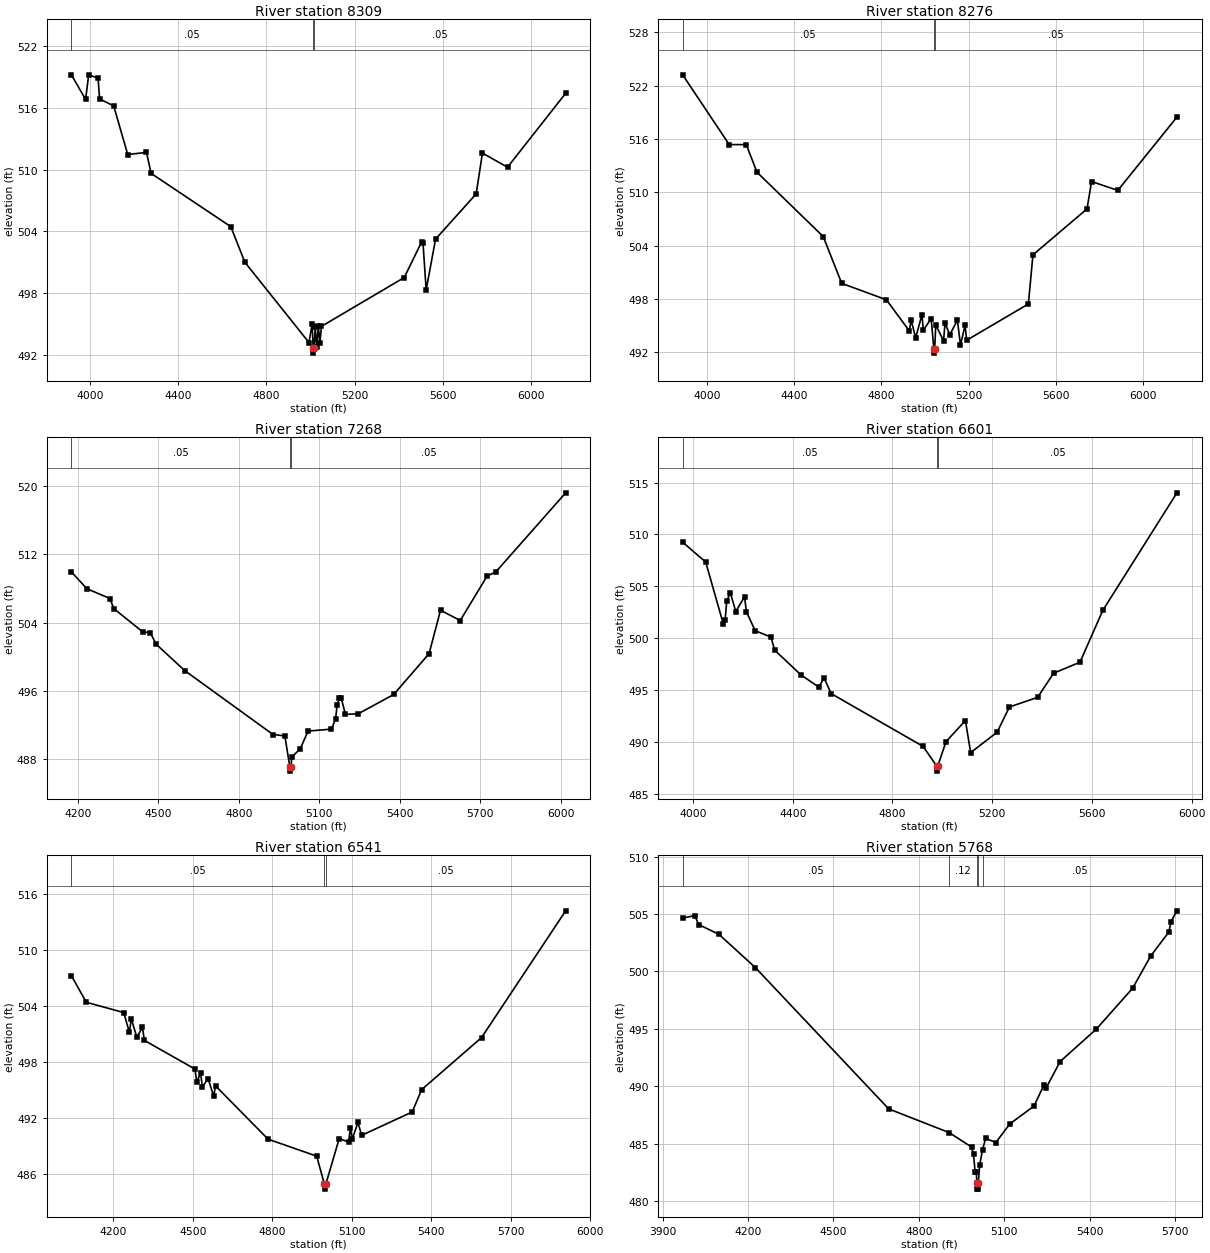
Type RM Length L Ch R = 1,8309,33,33,33
BEGIN DESCRIPTION:
Big Brushy Creek 245.0
END DESCRIPTION:
XS GIS Cut Line= 5
      2617025.14      6989242.79      2616385.52      6988568.49
      2616285.99      6988450.98      2616162.60      6988326.13
      2615507.77      6987596.94
#Sta/Elev= 30
  3916.6  519.21  3980.9  516.83  3995.1  519.20  4037.5  518.90  4044.4  516.87
  4108.3  516.19  4171.8  511.47  4256.8  511.68  4277.8  509.64  4638.7  504.47
  4702.5  501.01  4992.8  493.22  5007.1  494.99  5011.9  492.69  5012.3  492.19
  5016.2  492.69  5021.2  494.69  5028.2  492.79  5035.3  494.81  5042.4  493.21
  5049.5  494.79  5424.4  499.53  5502.7  502.96  5509.5  502.85  5523.7  498.33
  5566.3  503.26  5750.2  507.65  5778.6  511.61  5892.2  510.24  6155.6  517.42
#Mann=3,-1,0
  3916.6    0.05       0  5011.9    0.03       0  5016.2    0.05       0
Bank Sta=5011.9,5016.2
Exp/Cntr=0.3,0.1

Type RM Length L Ch R = 1,8276,1008,1008,1008
BEGIN DESCRIPTION:
Big Brushy Creek 244.0
END DESCRIPTION:
XS GIS Cut Line= 4
      2617084.22      6989225.48      2616396.46      6988496.71
      2616309.31      6988427.58      2615540.04      6987563.37
#Sta/Elev= 30
  3886.7  523.23  4100.7  515.37  4178.8  515.37  4228.1  512.26  4532.4  505.01
  4617.3  499.74  4822.4  497.89  4928.1  494.38  4936.1  495.62  4956.9  493.59
  4985.8  496.22  4992.1  494.46  5028.2  495.77  5040.3  492.38  5040.6  491.88
  5044.6  492.38  5049.1  495.05  5085.1  493.28  5091.8  495.28  5113.5  493.95
  5148.6  495.59  5162.8  492.80  5183.7  495.00  5191.3  493.33  5474.7  497.42
  5495.6  502.95  5744.0  508.13  5764.9  511.21  5885.3  510.21  6157.0  518.47
#Mann=3,-1,0
  3886.7    0.05       0  5040.3    0.03       0  5044.6    0.05       0
Bank Sta=5040.3,5044.6
Exp/Cntr=0.3,0.1

Type RM Length L Ch R = 1,7268,667,667,667
BEGIN DESCRIPTION:
Big Brushy Creek 243.0
END DESCRIPTION:
XS GIS Cut Line= 3
      2617175.98      6988260.98      2616695.59      6987591.13
      2615826.04      6987061.02
#Sta/Elev= 30
  4175.7  509.95  4233.4  507.98  4319.4  506.83  4334.1  505.64  4440.9  502.94
  4470.4  502.80  4491.3  501.49  4598.1  498.39  4927.3  490.90  4971.5  490.74
  4990.1  487.11  4990.6  486.61  4994.7  487.11  4997.0  488.25  5028.9  489.22
  5058.1  491.30  5145.1  491.53  5160.6  492.71  5166.4  494.36  5175.2  495.16
  5181.9  495.15  5197.4  493.25  5245.9  493.34  5377.5  495.59  5509.2  500.37
  5551.8  505.46  5625.4  504.25  5726.1  509.49  5757.0  509.91  6018.4  519.21
#Mann=3,-1,0
  4175.7    0.05       0  4990.1    0.04       0  4994.7    0.05       0
Bank Sta=4990.1,4994.7
Exp/Cntr=0.3,0.1

Type RM Length L Ch R = 1,6601,60,60,60
BEGIN DESCRIPTION:
Big Brushy Creek 242.0
END DESCRIPTION:
XS GIS Cut Line= 3
      2617782.94      6987874.29      2617099.81      6987087.85
      2616441.38      6986415.59
#Sta/Elev= 30
  3958.3  509.26  4050.8  507.34  4121.6  501.35  4128.6  501.72  4135.2  503.59
  4149.5  504.38  4171.4  502.57  4206.5  503.99  4214.1  502.54  4249.2  500.72
  4312.8  500.10  4327.1  498.85  4433.4  496.44  4504.7  495.28  4525.5  496.16
  4554.0  494.65  4922.5  489.56  4977.1  487.67  4977.6  487.17  4981.8  487.67
  5014.6  490.01  5092.5  492.05  5113.6  488.96  5219.6  490.92  5269.2  493.36
  5382.4  494.29  5445.9  496.61  5552.1  497.68  5643.9  502.69  5941.0  514.02
#Mann=3,-1,0
  3958.3    0.05       0  4977.1    0.03       0  4981.8    0.05       0
Bank Sta=4977.1,4981.8
Exp/Cntr=0.3,0.1

Type RM Length L Ch R = 1,6541,773,773,773
BEGIN DESCRIPTION:
Big Brushy Creek 241.0
END DESCRIPTION:
XS GIS Cut Line= 3
      2617788.15      6987728.46      2617126.01      6987035.85
      2616500.07      6986377.94
#Sta/Elev= 30
  4041.8  507.26  4098.1  504.41  4239.6  503.31  4260.7  501.19  4267.9  502.65
  4289.0  500.66  4310.3  501.73  4317.3  500.33  4508.5  497.26  4515.4  495.86
  4529.6  496.84  4536.5  495.34  4557.9  496.25  4578.9  494.38  4586.2  495.46
  4784.3  489.76  4968.0  487.94  4997.5  484.91  4998.0  484.41  5002.2  484.91
  5052.9  489.81  5088.5  489.46  5095.4  490.96  5102.6  489.79  5123.7  491.55
  5137.8  490.17  5328.7  492.67  5364.3  495.06  5590.4  500.63  5908.1  514.20
#Mann=3,-1,0
  4041.8    0.05       0  4997.5    0.03       0  5002.2    0.05       0
Bank Sta=4997.5,5002.2
Exp/Cntr=0.3,0.1

Type RM Length L Ch R = 1,5768,500,500,500
BEGIN DESCRIPTION:
Big Brushy Creek 240.0
END DESCRIPTION:
XS GIS Cut Line= 3
      2618226.03      6987261.03      2617563.77      6986472.95
      2617076.01      6985961.01
#Sta/Elev= 30
  3970.6  504.65  4012.9  504.86  4027.2  504.08  4098.7  503.22  4226.2  500.33
  4694.5  488.02  4907.4  485.95  4985.9  484.69  4992.4  484.05  4998.0  482.56
  5002.0  482.56  5004.4  481.53  5005.0  481.03  5008.7  481.03  5009.2  481.53
  5014.1  483.13  5024.3  484.48  5035.1  485.46  5070.7  485.09  5120.0  486.71
  5205.0  488.27  5240.2  490.12  5247.4  489.84  5296.8  492.15  5424.2  494.98
  5551.6  498.54  5615.1  501.35  5679.0  503.44  5685.9  504.33  5707.1  505.28
#Mann=5,-1,0
  3970.6    0.05       0  4907.4    0.12       0  5004.4    0.07       0
  5009.2    0.12       0  5024.3    0.05       0
Bank Sta=5004.4,5009.2
Exp/Cntr=0.3,0.1

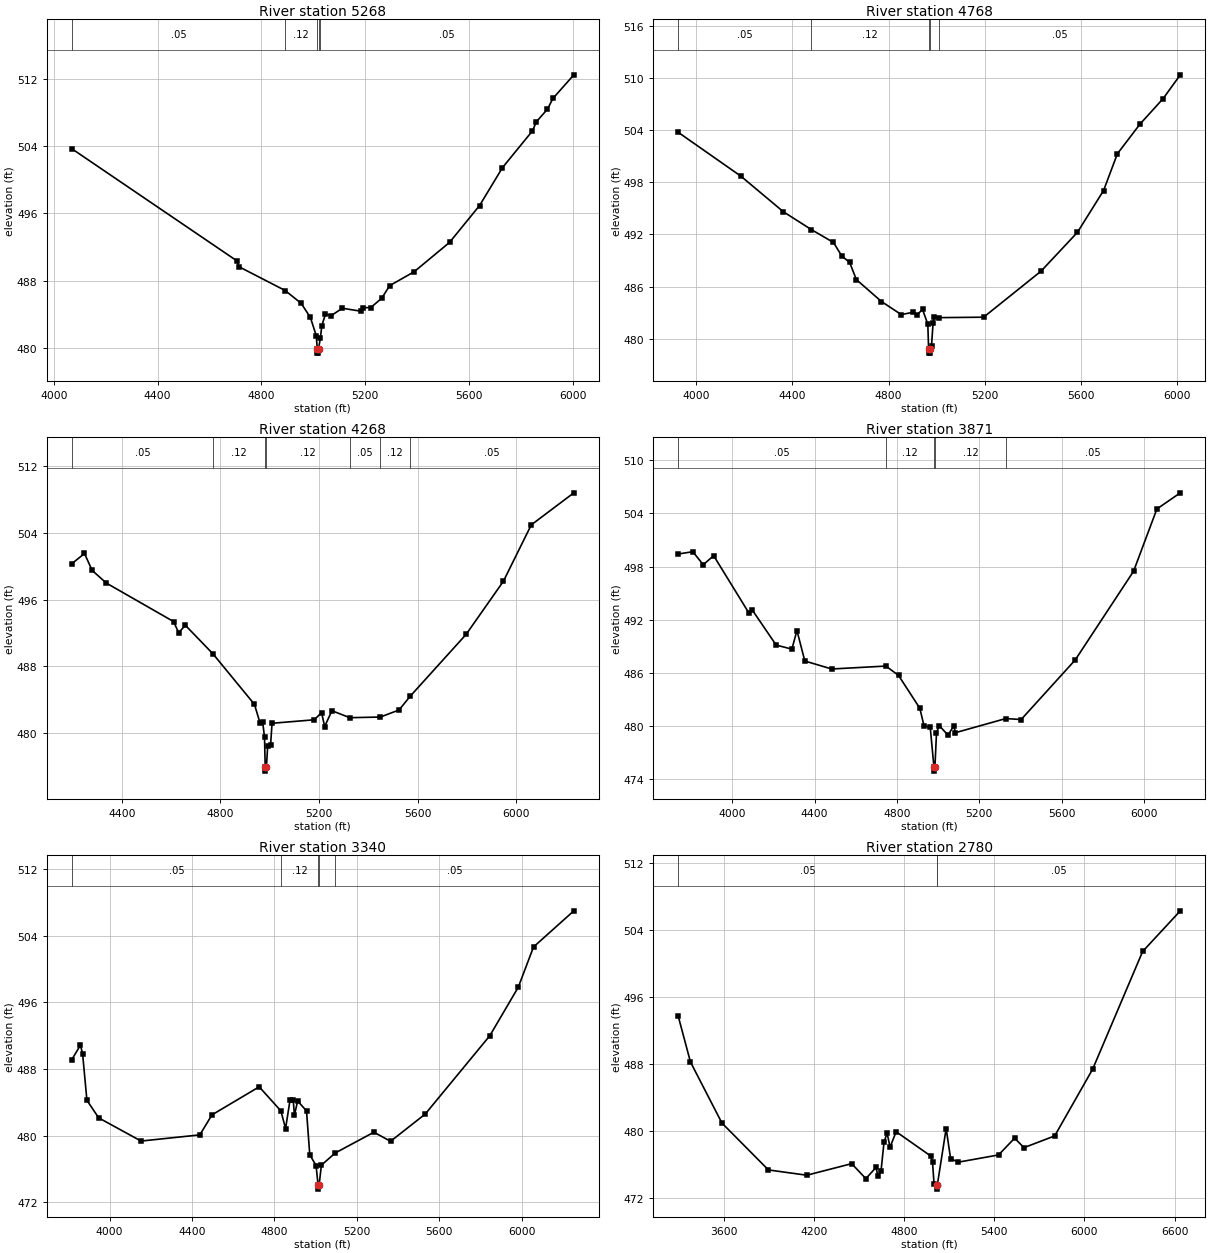
Type RM Length L Ch R = 1,5268,500,500,500
BEGIN DESCRIPTION:
Big Brushy Creek 239.0
END DESCRIPTION:
XS GIS Cut Line= 3
      2618526.03      6986761.03      2617875.44      6986095.34
      2617026.03      6985561.02
#Sta/Elev= 30
  4069.2  503.70  4705.7  490.35  4712.7  489.67  4891.3  486.83  4953.1  485.30
  4988.6  483.62  5011.2  481.44  5014.9  479.88  5015.5  479.38  5019.2  479.38
  5019.8  479.88  5026.9  481.16  5032.6  482.65  5046.6  484.02  5069.1  483.85
  5111.5  484.72  5184.5  484.36  5190.4  484.78  5221.0  484.80  5263.4  485.91
  5294.0  487.41  5388.2  489.06  5524.8  492.56  5640.3  496.94  5728.6  501.45
  5844.0  505.82  5859.3  506.91  5901.7  508.40  5922.9  509.68  6003.5  512.49
#Mann=5,-1,0
  4069.2    0.05       0  4891.3    0.12       0  5014.9    0.07       0
  5019.8    0.12       0  5026.9    0.05       0
Bank Sta=5014.9,5019.8
Exp/Cntr=0.3,0.1

Type RM Length L Ch R = 1,4768,500,500,500
BEGIN DESCRIPTION:
Big Brushy Creek 238.0
END DESCRIPTION:
XS GIS Cut Line= 3
      2618626.01      6986661.01      2618124.53      6985712.07
      2617275.97      6985160.98
#Sta/Elev= 30
  3926.7  503.73  4186.9  498.69  4363.8  494.59  4479.1  492.56  4571.4  491.07
  4605.9  489.52  4638.7  488.77  4666.3  486.81  4770.7  484.28  4853.1  482.78
  4902.8  483.05  4919.2  482.77  4941.2  483.37  4963.2  481.68  4966.4  478.85
  4967.0  478.35  4970.7  478.35  4971.3  478.85  4978.6  479.22  4985.2  481.87
  4990.9  482.49  5009.8  482.43  5194.9  482.48  5433.4  487.77  5584.4  492.23
  5693.1  497.04  5750.5  501.27  5844.8  504.69  5940.2  507.60  6011.8  510.34
#Mann=5,-1,0
  3926.7    0.05       0  4479.1    0.12       0  4966.4    0.07       0
  4971.3    0.12       0  5009.8    0.05       0
Bank Sta=4966.4,4971.3
Exp/Cntr=0.3,0.1

Type RM Length L Ch R = 1,4268,397,397,397
BEGIN DESCRIPTION:
Big Brushy Creek 237.0
END DESCRIPTION:
XS GIS Cut Line= 3
      2618726.00      6986411.01      2618526.34      6985633.02
      2617525.99      6984911.00
#Sta/Elev= 30
  4196.8  500.31  4248.4  501.54  4279.4  499.51  4336.9  497.99  4609.8  493.36
  4630.4  492.03  4657.8  492.91  4769.7  489.48  4938.0  483.41  4960.8  481.15
  4971.1  481.33  4978.8  479.46  4981.5  475.89  4982.1  475.39  4986.4  475.89
  4991.8  478.45  5003.3  478.49  5009.3  481.14  5181.1  481.56  5210.1  482.43
  5222.8  480.75  5252.2  482.65  5324.8  481.81  5448.9  481.89  5524.6  482.74
  5569.2  484.37  5796.9  491.83  5947.8  498.20  6061.0  504.98  6233.7  508.83
#Mann=7,-1,0
  4196.8    0.05       0  4769.7    0.12       0  4981.5    0.07       0
  4986.4    0.12       0  5324.8    0.05       0  5448.9    0.12       0
  5569.2    0.05       0
Bank Sta=4981.5,4986.4
Exp/Cntr=0.3,0.1

Type RM Length L Ch R = 1,3871,531,531,531
BEGIN DESCRIPTION:
Big Brushy Creek 236.0
END DESCRIPTION:
XS GIS Cut Line= 3
      2618976.01      6986611.05      2618781.87      6985363.46
      2618025.99      6984460.99
#Sta/Elev= 30
  3737.4  499.42  3808.3  499.68  3858.9  498.21  3909.5  499.23  4081.5  492.74
  4095.9  493.15  4213.1  489.15  4289.6  488.69  4314.3  490.79  4352.5  487.35
  4483.3  486.45  4746.5  486.78  4807.8  485.73  4911.4  482.02  4931.6  480.04
  4962.0  479.86  4979.8  475.43  4980.4  474.93  4984.8  475.43  4992.4  479.23
  5005.5  480.07  5048.5  478.98  5077.1  480.07  5083.6  479.26  5329.3  480.86
  5403.7  480.75  5666.5  487.47  5950.1  497.48  6063.4  504.50  6177.2  506.32
#Mann=5,-1,0
  3737.4    0.05       0  4746.5    0.12       0  4979.8    0.07       0
  4984.8    0.12       0  5329.3    0.05       0
Bank Sta=4979.8,4984.8
Exp/Cntr=0.3,0.1

Type RM Length L Ch R = 1,3340,560,560,560
BEGIN DESCRIPTION:
Mapping XS fb894ac4
END DESCRIPTION:
XS GIS Cut Line= 4
      2618960.90      6986080.95      2619243.03      6985208.51
      2619108.48      6984978.48      2618032.09      6984336.12
#Sta/Elev= 30
  3816.6  489.14  3858.6  490.87  3869.1  489.86  3890.1  484.26  3947.4  482.15
  4152.9  479.37  4438.2  480.11  4496.9  482.51  4726.3  485.88  4831.6  482.99
  4854.3  480.87  4875.8  484.26  4891.5  484.27  4897.3  482.50  4913.0  484.17
  4956.0  482.99  4971.7  477.73  5002.4  476.43  5012.0  474.10  5012.6  473.60
  5017.1  474.10  5028.2  476.48  5095.5  477.94  5283.1  480.43  5363.9  479.34
  5532.2  482.61  5845.6  492.01  5983.7  497.83  6057.7  502.66  6253.5  507.00
#Mann=5,-1,0
  3816.6    0.05       0  4831.6    0.12       0  5012.0    0.07       0
  5017.1    0.12       0  5095.5    0.05       0
Bank Sta=5012,5017.1
Exp/Cntr=0.3,0.1

Type RM Length L Ch R = 1,2780,0,0,0
BEGIN DESCRIPTION:
Mapping XS 41261e45
END DESCRIPTION:
XS GIS Cut Line= 4
      2619006.94      6986351.35      2619470.48      6985387.81
      2619559.87      6984665.98      2618074.66      6984252.40
#Sta/Elev= 30
  3299.0  493.70  3380.1  488.25  3589.3  480.96  3898.6  475.36  4153.9  474.73
  4452.3  476.11  4546.4  474.32  4614.2  475.66  4627.0  474.59  4647.2  475.22
  4667.3  478.67  4687.5  479.75  4707.6  478.08  4747.9  479.92  4979.7  477.00
  4989.8  476.27  4999.8  473.71  5016.6  473.57  5017.3  473.07  5021.7  473.57
  5080.4  480.30  5110.0  476.70  5161.9  476.29  5428.8  477.15  5535.6  479.15
  5597.9  478.02  5802.0  479.42  6054.6  487.39  6386.8  501.43  6637.3  506.28
#Mann=3,-1,0
  3299.0    0.05       0  5016.6    0.03       0  5021.7    0.05       0
Bank Sta=5016.6,5021.7
Exp/Cntr=0.3,0.1

Chan Stop Cuts=-1