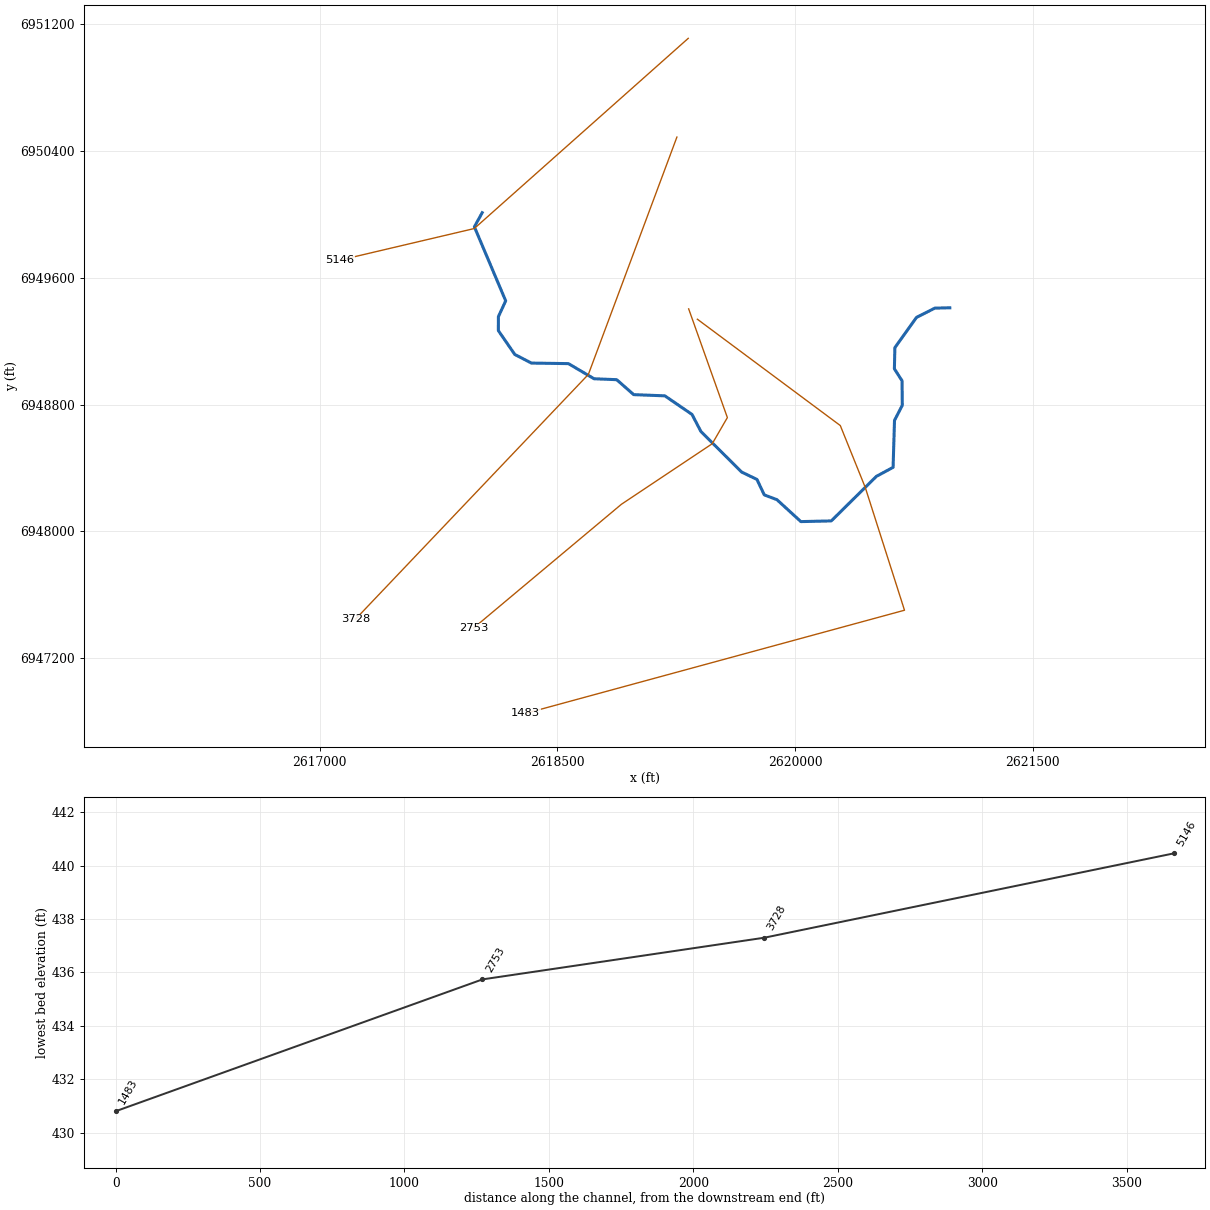
--- Big Brushy Creek Trib 1_1.prj (project) ---

Proj Title=Big Brushy Creek Trib 1_1 Base Level Engineering
Current Plan=p01
Default Exp/Contr=0.3,0.1
English Units
Geom File=g01
Flow File=f01
Plan File=p01
BEGIN DESCRIPTION:
Big Brushy Creek Trib 1_1
END DESCRIPTION:

--- Big Brushy Creek Trib 1_1.p01 (plan) ---

Plan Title=Multiple Run
Short Identifier=Multiple
Geom File=g01
Flow File=f01
Subcritical Flow
K Sum by GR= 0
Std Step Tol= 0.01
Critical Tol= 0.01
Num of Std Step Trials= 20
Max Error Tol= 0.3
Flow Tol Ratio= 0.001
Split Flow NTrial= 30
Split Flow Tol= 0.02
Split Flow Ratio= 0.02
Log Output Level= 0
Friction Slope Method= 1
Unsteady Friction Slope Method= 2
Unsteady Bridges Friction Slope Method= 1
Parabolic Critical Depth
Global Vel Dist=  1 , 1 , 1
Global Log Level= 0
CheckData=True
Encroach Param= -1, 0, 0, 0
BEGIN DESCRIPTION:
Multiple Run
END DESCRIPTION:

--- Big Brushy Creek Trib 1_1.f01 (steady flow) ---

Flow Title=Multiple
Number of Profiles=7
Profile Names=10-year,25-year,50-year,1pct_min,100-year,1pct_plu,500-year
River Rch & RM= Big Brushy Creek,Reach-1,5146
     650     880    1066     641    1279    2552    1841
River Rch & RM= Big Brushy Creek,Reach-1,3728
     682     923    1120     673    1344    2681    1935
River Rch & RM= Big Brushy Creek,Reach-1,1483
     680     919    1113     668    1333    2660    1913
Boundary for River Rch & Prof#=Big Brushy Creek,Reach-1,1
Up Type=0
Dn Type=3
Dn Slope=0.005
Boundary for River Rch & Prof#=Big Brushy Creek,Reach-1,2
Up Type=0
Dn Type=3
Dn Slope=0.005
Boundary for River Rch & Prof#=Big Brushy Creek,Reach-1,3
Up Type=0
Dn Type=3
Dn Slope=0.005
Boundary for River Rch & Prof#=Big Brushy Creek,Reach-1,4
Up Type=0
Dn Type=3
Dn Slope=0.005
Boundary for River Rch & Prof#=Big Brushy Creek,Reach-1,5
Up Type=0
Dn Type=3
Dn Slope=0.005
Boundary for River Rch & Prof#=Big Brushy Creek,Reach-1,6
Up Type=0
Dn Type=3
Dn Slope=0.005
Boundary for River Rch & Prof#=Big Brushy Creek,Reach-1,7
Up Type=0
Dn Type=3
Dn Slope=0.005

--- Big Brushy Creek Trib 1_1.g01 (geometry) ---

Geom Title=Existing Conditions

River Reach=Big Brushy Creek,Reach-1
Reach XY= 30
      2618026.00      6950011.00      2617976.68      6949921.63
      2618174.18      6949454.88      2618128.19      6949355.03
      2618127.97      6949266.89      2618231.61      6949116.59
      2618336.48      6949062.19      2618570.07      6949058.76
      2618731.93      6948963.25      2618874.53      6948957.44
      2618981.86      6948863.07      2619178.45      6948855.53
      2619349.84      6948738.14      2619405.62      6948630.84
      2619662.80      6948374.64      2619759.50      6948328.04
      2619805.53      6948230.64      2619885.66      6948200.21
      2620036.43      6948062.05      2620228.45      6948066.46
      2620512.80      6948347.36      2620618.31      6948404.52
      2620627.22      6948700.50      2620676.43      6948795.82
      2620674.78      6948950.49      2620626.51      6949026.22
      2620629.54      6949159.53      2620766.00      6949350.37
      2620881.86      6949408.93      2620976.00      6949411.00

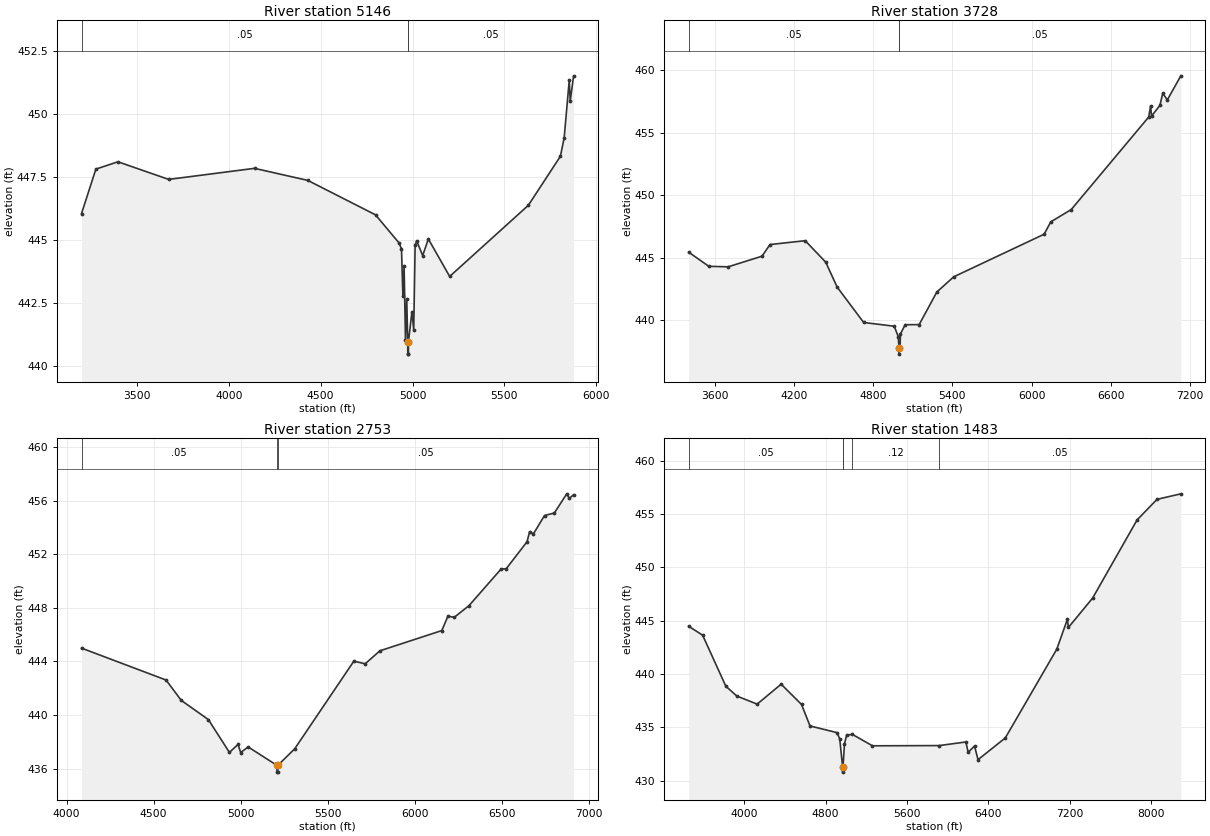
Type RM Length L Ch R = 1,5146,1418,1418,1418
BEGIN DESCRIPTION:
Big Brushy Creek Trib 1_1 3.0
END DESCRIPTION:
XS GIS Cut Line= 3
      2619325.97      6951110.97      2617976.00      6949911.00
      2617126.01      6949711.00
#Sta/Elev= 30
  3197.8  446.05  3275.9  447.82  3396.4  448.11  3672.3  447.41  4139.8  447.85
  4429.9  447.37  4798.7  446.00  4925.8  444.89  4940.0  444.65  4947.6  442.78
  4954.2  443.96  4961.8  441.02  4968.5  442.65  4974.0  440.96  4974.2  440.46
  4977.7  440.46  4978.0  440.96  4996.9  442.15  5006.6  441.43  5014.3  444.79
  5022.6  444.97  5055.4  444.38  5086.2  445.04  5202.4  443.55  5630.7  446.38
  5805.3  448.33  5825.8  449.07  5853.5  451.36  5858.6  450.53  5877.2  451.53
#Mann=3,-1,0
  3197.8    0.05       0  4974.0    0.04       0  4978.0    0.05       0
Bank Sta=4974,4978
Exp/Cntr=0.3,0.1

Type RM Length L Ch R = 1,3728,975,975,975
BEGIN DESCRIPTION:
Big Brushy Creek Trib 1_1 2.0
END DESCRIPTION:
XS GIS Cut Line= 3
      2619254.45      6950488.14      2618695.89      6948990.73
      2617226.66      6947446.49
#Sta/Elev= 30
  3401.8  445.45  3554.1  444.32  3700.4  444.28  3957.2  445.13  4017.8  446.06
  4284.6  446.37  4440.5  444.65  4526.2  442.67  4727.7  439.83  4959.6  439.53
  4989.9  438.70  4995.2  437.80  4995.4  437.30  4999.2  437.80  5003.3  437.80
  5006.8  438.91  5042.0  439.65  5148.4  439.66  5282.7  442.27  5410.1  443.48
  6096.1  446.89  6145.4  447.87  6301.1  448.86  6888.4  456.26  6902.6  457.15
  6909.5  456.33  6973.3  457.19  6994.4  458.15  7029.6  457.63  7131.5  459.55
#Mann=3,-1,0
  3401.8    0.05       0  4995.2    0.04       0  4999.2    0.05       0
Bank Sta=4995.2,4999.2
Exp/Cntr=0.3,0.1

Type RM Length L Ch R = 1,2753,1270,1270,1270
BEGIN DESCRIPTION:
Mapping XS b5ffaa42
END DESCRIPTION:
XS GIS Cut Line= 5
      2619328.67      6949404.11      2619572.75      6948718.29
      2619477.26      6948553.36      2618904.34      6948171.41
      2617971.20      6947390.17
#Sta/Elev= 30
  4086.1  444.99  4571.3  442.61  4658.5  441.09  4814.1  439.66  4934.8  437.21
  4984.3  437.81  4999.4  437.20  5042.2  437.62  5208.3  436.24  5208.6  435.74
  5212.1  435.74  5212.3  436.24  5309.5  437.48  5649.0  444.02  5713.9  443.82
  5798.5  444.79  6153.7  446.30  6188.8  447.37  6225.3  447.29  6309.8  448.16
  6494.6  450.90  6523.2  450.91  6643.1  452.93  6657.3  453.66  6679.4  453.51
  6743.1  454.88  6799.6  455.07  6870.7  456.50  6885.0  456.16  6910.2  456.43
#Mann=3,-1,0
  4086.1    0.05       0  5208.3    0.04       0  5212.3    0.05       0
Bank Sta=5208.3,5212.3
Exp/Cntr=0.3,0.1

Type RM Length L Ch R = 1,1483,0,0,0
BEGIN DESCRIPTION:
Big Brushy Creek Trib 1_1 1.0
END DESCRIPTION:
XS GIS Cut Line= 5
      2619383.34      6949339.03      2620285.23      6948668.03
      2620442.65      6948277.70      2620690.23      6947502.93
      2618299.88      6946852.20
#Sta/Elev= 30
  3455.0  444.48  3591.6  443.65  3819.8  438.86  3927.4  437.94  4127.7  437.18
  4363.3  439.05  4563.6  437.15  4647.0  435.13  4915.5  434.50  4939.6  433.87
  4967.1  431.30  4967.4  430.80  4971.2  431.30  4985.7  433.45  5007.0  434.28
  5063.5  434.34  5260.8  433.27  5915.7  433.29  6178.8  433.63  6201.2  432.66
  6263.6  433.25  6298.1  431.97  6566.1  434.01  7071.8  442.33  7176.4  445.14
  7185.8  444.37  7424.2  447.13  7861.0  454.46  8056.4  456.39  8290.7  456.91
#Mann=5,-1,0
  3455.0    0.05       0  4967.1    0.03       0  4971.2    0.05       0
  5063.5    0.12       0  5915.7    0.05       0
Bank Sta=4967.1,4971.2
Exp/Cntr=0.3,0.1

Chan Stop Cuts=-1