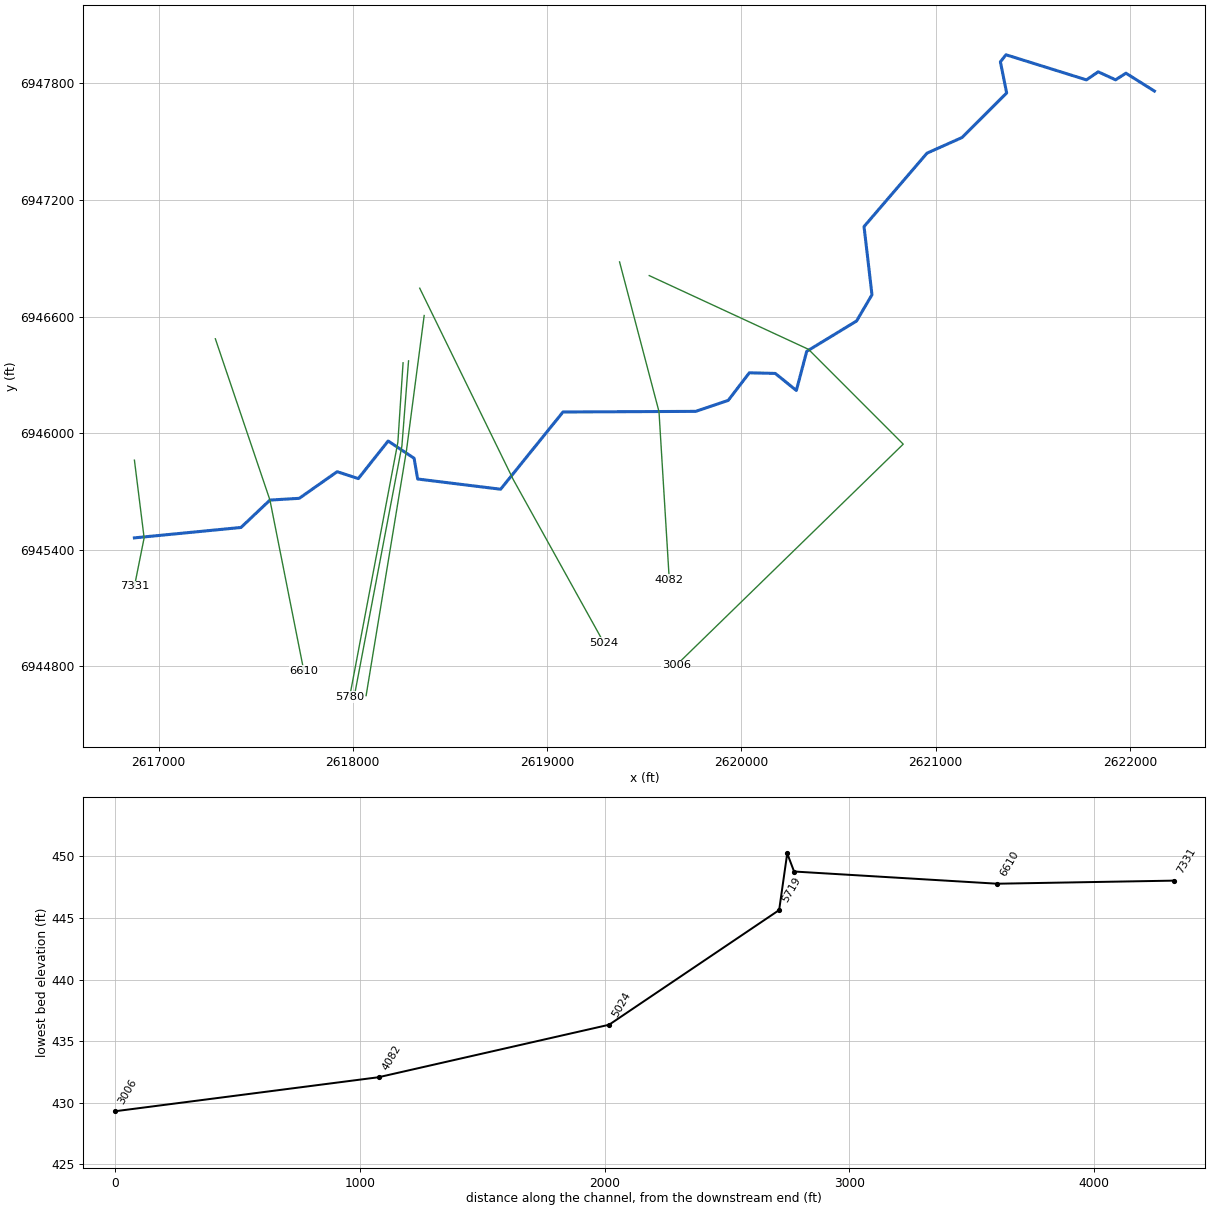
--- Big Brushy Creek Trib 2.prj (project) ---

Proj Title=Big Brushy Creek Trib 2 Base Level Engineering
Current Plan=p01
Default Exp/Contr=0.3,0.1
English Units
Geom File=g01
Flow File=f01
Plan File=p01
BEGIN DESCRIPTION:
Big Brushy Creek Trib 2
END DESCRIPTION:

--- Big Brushy Creek Trib 2.p01 (plan) ---

Plan Title=Multiple Run
Short Identifier=Multiple
Geom File=g01
Flow File=f01
Subcritical Flow
K Sum by GR= 0
Std Step Tol= 0.01
Critical Tol= 0.01
Num of Std Step Trials= 20
Max Error Tol= 0.3
Flow Tol Ratio= 0.001
Split Flow NTrial= 30
Split Flow Tol= 0.02
Split Flow Ratio= 0.02
Log Output Level= 0
Friction Slope Method= 1
Unsteady Friction Slope Method= 2
Unsteady Bridges Friction Slope Method= 1
Parabolic Critical Depth
Global Vel Dist=  1 , 1 , 1
Global Log Level= 0
CheckData=True
Encroach Param= -1, 0, 0, 0
BEGIN DESCRIPTION:
Multiple Run
END DESCRIPTION:

--- Big Brushy Creek Trib 2.f01 (steady flow) ---

Flow Title=Multiple
Number of Profiles=7
Profile Names=10-year,25-year,50-year,1pct_min,100-year,1pct_plu,500-year
River Rch & RM= Big Brushy Creek,Reach-1,7331
     534     712     855     509    1016    2027    1434
River Rch & RM= Big Brushy Creek,Reach-1,3006
     578     773     930     555    1107    2208    1568
Boundary for River Rch & Prof#=Big Brushy Creek,Reach-1,1
Up Type=0
Dn Type=3
Dn Slope=0.005
Boundary for River Rch & Prof#=Big Brushy Creek,Reach-1,2
Up Type=0
Dn Type=3
Dn Slope=0.005
Boundary for River Rch & Prof#=Big Brushy Creek,Reach-1,3
Up Type=0
Dn Type=3
Dn Slope=0.005
Boundary for River Rch & Prof#=Big Brushy Creek,Reach-1,4
Up Type=0
Dn Type=3
Dn Slope=0.005
Boundary for River Rch & Prof#=Big Brushy Creek,Reach-1,5
Up Type=0
Dn Type=3
Dn Slope=0.005
Boundary for River Rch & Prof#=Big Brushy Creek,Reach-1,6
Up Type=0
Dn Type=3
Dn Slope=0.005
Boundary for River Rch & Prof#=Big Brushy Creek,Reach-1,7
Up Type=0
Dn Type=3
Dn Slope=0.005

--- Big Brushy Creek Trib 2.g01 (geometry) ---

Geom Title=Existing Conditions

River Reach=Big Brushy Creek,Reach-1
Reach XY= 30
      2616876.00      6945461.00      2617424.54      6945514.54
      2617573.55      6945655.53      2617724.53      6945664.55
      2617919.39      6945801.57      2618028.30      6945766.11
      2618181.87      6945959.50      2618315.47      6945870.77
      2618333.97      6945763.93      2618760.84      6945711.36
      2619081.84      6946108.95      2619765.50      6946112.22
      2619932.45      6946168.75      2620041.04      6946310.69
      2620174.53      6946307.45      2620283.00      6946219.82
      2620336.35      6946421.12      2620593.05      6946577.49
      2620672.25      6946712.55      2620631.40      6947063.43
      2620955.53      6947441.38      2621135.68      6947521.76
      2621365.56      6947751.21      2621333.23      6947911.38
      2621361.97      6947947.90      2621776.01      6947818.59
      2621836.64      6947860.02      2621926.09      6947818.84
      2621979.33      6947853.02      2622126.00      6947761.00

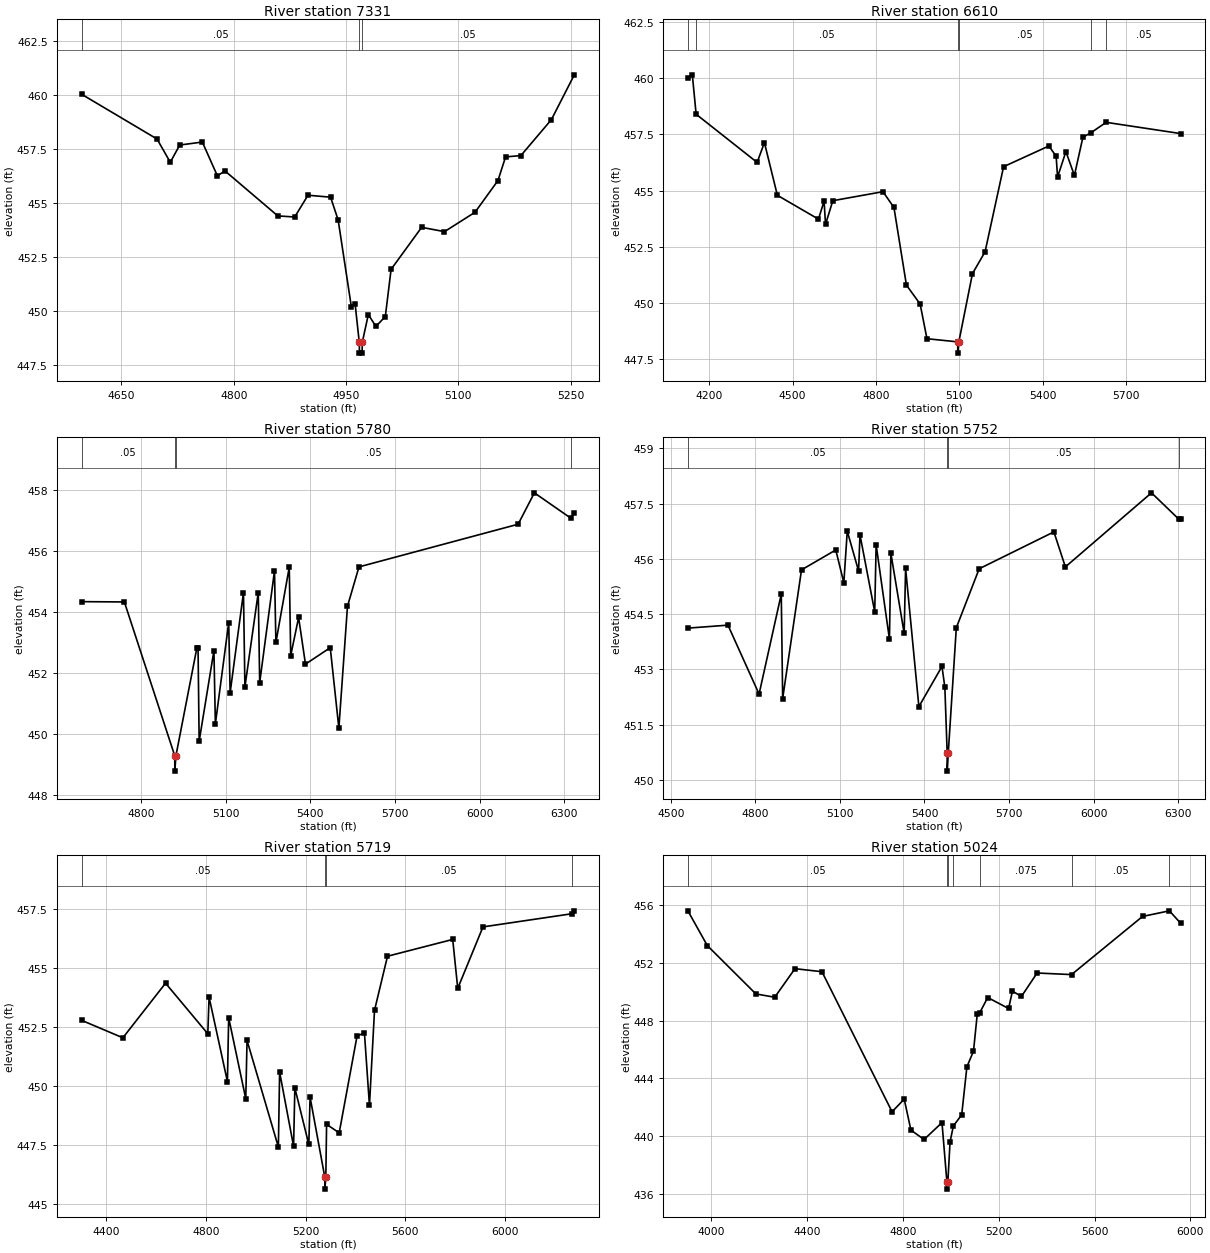
Type RM Length L Ch R = 1,7331,721,721,721
BEGIN DESCRIPTION:
Big Brushy Creek Trib 2 10.0
END DESCRIPTION:
XS GIS Cut Line= 3
      2616875.99      6945861.05      2616926.00      6945461.00
      2616876.00      6945211.01
#Sta/Elev= 30
  4596.8  460.05  4697.6  457.97  4715.3  456.89  4727.9  457.69  4758.1  457.83
  4778.2  456.26  4788.3  456.49  4858.9  454.40  4881.5  454.35  4899.2  455.36
  4929.4  455.27  4939.5  454.21  4957.1  450.19  4962.2  450.30  4967.7  448.53
  4968.0  448.03  4971.5  448.03  4971.7  448.53  4979.8  449.82  4989.9  449.27
  5002.5  449.73  5010.2  451.92  5051.0  453.87  5081.5  453.67  5122.3  454.57
  5152.9  456.04  5163.1  457.14  5183.5  457.20  5224.3  458.87  5254.9  460.95
#Mann=3,-1,0
  4596.8    0.05       0  4967.7    0.03       0  4971.7    0.05       0
Bank Sta=4967.7,4971.7
Exp/Cntr=0.3,0.1

Type RM Length L Ch R = 1,6610,830,830,830
BEGIN DESCRIPTION:
Big Brushy Creek Trib 2 9.0
END DESCRIPTION:
XS GIS Cut Line= 3
      2617292.57      6946485.67      2617573.55      6945655.53
      2617748.18      6944775.39
#Sta/Elev= 30
  4123.6  460.02  4139.1  460.14  4152.8  458.39  4372.4  456.25  4398.6  457.13
  4445.2  454.79  4593.1  453.73  4613.3  454.53  4618.6  453.50  4644.8  454.55
  4825.3  454.95  4864.8  454.25  4909.8  450.80  4959.1  449.96  4983.7  448.42
  5094.4  448.28  5094.6  447.78  5098.4  448.28  5147.4  451.31  5192.8  452.28
  5259.5  456.06  5422.6  456.98  5448.7  456.52  5453.8  455.60  5483.8  456.73
  5514.4  455.67  5545.0  457.37  5573.0  457.56  5628.7  458.03  5897.3  457.53
#Mann=6,-1,0
  4123.6   0.075       0  4152.8    0.05       0  5094.4    0.03       0
  5098.4    0.05       0  5573.0   0.075       0  5628.7    0.05       0
Bank Sta=5094.4,5098.4
Exp/Cntr=0.3,0.1

Type RM Length L Ch R = 1,5780,28,28,28
BEGIN DESCRIPTION:
Big Brushy Creek Trib 2 8.0
END DESCRIPTION:
XS GIS Cut Line= 3
      2618258.77      6946362.28      2618232.05      6945953.55
      2617983.73      6944642.06
#Sta/Elev= 30
  4590.4  454.33  4742.0  454.32  4920.4  449.27  4920.6  448.77  4924.4  449.27
  4998.8  452.82  5002.8  452.82  5006.7  449.75  5059.0  452.72  5064.1  450.32
  5111.3  453.64  5116.4  451.34  5163.6  454.63  5168.7  451.53  5215.9  454.63
  5221.0  451.67  5273.4  455.34  5278.4  452.99  5325.7  455.46  5330.8  452.56
  5358.8  453.81  5383.1  452.28  5470.8  452.82  5501.3  450.18  5531.8  454.18
  5572.5  455.47  6135.9  456.87  6193.4  457.90  6322.2  457.07  6334.8  457.24
#Mann=4,-1,0
  4590.4    0.05       0  4920.4    0.05       0  4924.4    0.05       0
  6322.2   0.075       0
Bank Sta=4920.4,4924.4
Exp/Cntr=0.3,0.1

Type RM Length L Ch R = 1,5752,33,33,33
BEGIN DESCRIPTION:
Big Brushy Creek Trib 2 6.0
END DESCRIPTION:
XS GIS Cut Line= 3
      2618286.98      6946372.27      2618252.88      6945934.99
      2618008.33      6944648.94
#Sta/Elev= 30
  4561.4  454.12  4703.1  454.20  4813.4  452.33  4892.1  455.04  4897.1  452.21
  4963.9  455.70  5085.5  456.24  5114.0  455.35  5126.2  456.75  5166.3  455.67
  5171.3  456.65  5223.6  454.56  5228.6  456.38  5275.8  453.82  5280.9  456.15
  5328.0  453.98  5333.1  455.74  5380.2  451.99  5462.1  453.08  5472.3  452.52
  5480.5  450.74  5480.7  450.24  5484.5  450.74  5513.0  454.13  5594.1  455.73
  5859.1  456.73  5899.8  455.78  6205.2  457.79  6302.9  457.07  6309.1  457.08
#Mann=4,-1,0
  4561.4    0.05       0  5480.5    0.05       0  5484.5    0.05       0
  6302.9   0.075       0
Bank Sta=5480.5,5484.5
Exp/Cntr=0.3,0.1

Type RM Length L Ch R = 1,5719,695,695,695
BEGIN DESCRIPTION:
Big Brushy Creek Trib 2 7.0
END DESCRIPTION:
XS GIS Cut Line= 3
      2618367.41      6946605.63      2618276.33      6945911.37
      2618068.55      6944648.96
#Sta/Elev= 30
  4299.8  452.78  4465.8  452.04  4637.3  454.35  4807.0  452.21  4812.1  453.76
  4885.8  450.19  4890.8  452.89  4959.5  449.46  4964.6  451.93  5090.5  447.42
  5095.5  450.59  5151.6  447.45  5156.7  449.92  5212.8  447.53  5217.9  449.53
  5277.1  446.14  5277.3  445.64  5281.1  446.14  5284.2  448.38  5334.8  448.02
  5406.5  452.11  5436.2  452.25  5456.4  449.18  5476.7  453.20  5528.9  455.49
  5790.9  456.20  5811.1  454.13  5912.5  456.73  6271.8  457.29  6279.4  457.41
#Mann=4,-1,0
  4299.8    0.05       0  5277.1    0.05       0  5281.1    0.05       0
  6271.8   0.075       0
Bank Sta=5277.1,5281.1
Exp/Cntr=0.3,0.1

Type RM Length L Ch R = 1,5024,942,942,942
BEGIN DESCRIPTION:
Big Brushy Creek Trib 2 5.0
END DESCRIPTION:
XS GIS Cut Line= 3
      2618344.51      6946746.15      2618826.00      6945761.00
      2619291.91      6944921.43
#Sta/Elev= 30
  3903.0  455.60  3983.6  453.21  4186.2  449.86  4264.9  449.63  4349.4  451.61
  4462.0  451.40  4754.7  441.69  4805.3  442.57  4833.4  440.42  4888.2  439.77
  4963.0  440.94  4983.5  436.83  4983.7  436.33  4987.5  436.83  4996.7  439.60
  5010.5  440.71  5045.3  441.48  5067.0  444.81  5094.5  445.89  5110.5  448.50
  5121.0  448.57  5154.0  449.61  5241.0  448.85  5257.0  450.05  5294.8  449.69
  5360.0  451.31  5503.7  451.20  5800.1  455.23  5912.1  455.62  5959.7  454.75
#Mann=7,-1,0
  3903.0    0.05       0  4983.5    0.03       0  4987.5    0.05       0
  5010.5    0.12       0  5121.0   0.075       0  5503.7    0.05       0
  5912.1   0.075       0
Bank Sta=4983.5,4987.5
Exp/Cntr=0.3,0.1

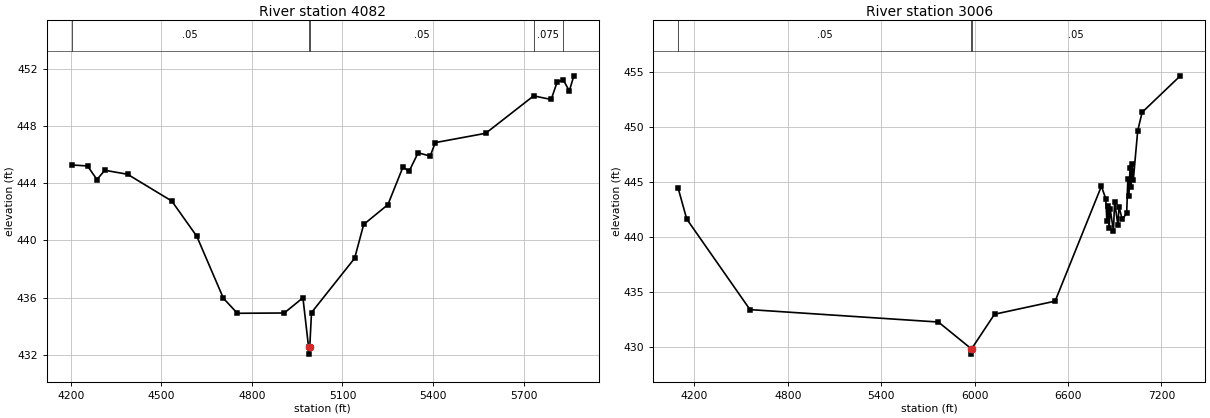
Type RM Length L Ch R = 1,4082,1076,1076,1076
BEGIN DESCRIPTION:
Big Brushy Creek Trib 2 3.0
END DESCRIPTION:
XS GIS Cut Line= 3
      2619373.07      6946881.62      2619576.00      6946111.00
      2619628.94      6945246.01
#Sta/Elev= 30
  4203.1  445.27  4255.4  445.20  4286.5  444.25  4312.6  444.90  4388.0  444.62
  4534.6  442.75  4617.4  440.29  4705.4  435.97  4751.8  434.92  4907.0  434.94
  4969.0  436.00  4987.6  432.57  4987.9  432.07  4991.6  432.57  4997.4  434.97
  5140.3  438.76  5170.3  441.12  5250.5  442.50  5300.5  445.13  5320.6  444.82
  5350.6  446.12  5390.7  445.89  5407.5  446.83  5574.5  447.48  5733.4  450.09
  5791.5  449.84  5811.5  451.07  5831.3  451.21  5851.6  450.44  5866.6  451.49
#Mann=5,-1,0
  4203.1    0.05       0  4987.6    0.04       0  4991.6    0.05       0
  5733.4   0.075       0  5831.3    0.05       0
Bank Sta=4987.6,4991.6
Exp/Cntr=0.3,0.1

Type RM Length L Ch R = 1,3006,0,0,0
BEGIN DESCRIPTION:
Big Brushy Creek Trib 2 2.0
END DESCRIPTION:
XS GIS Cut Line= 4
      2619526.03      6946810.98      2620345.45      6946431.55
      2620833.11      6945943.41      2619664.88      6944805.26
#Sta/Elev= 30
  4097.0  444.38  4151.5  441.60  4557.7  433.36  5767.5  432.23  5977.5  429.81
  5977.8  429.31  5981.5  429.81  6128.1  432.94  6517.1  434.13  6814.1  444.58
  6842.4  443.45  6849.4  441.45  6856.5  442.79  6863.5  440.75  6870.7  442.49
  6891.8  440.54  6899.0  443.17  6920.1  441.07  6927.3  442.70  6948.4  441.56
  6976.7  442.14  6983.9  445.20  6990.8  443.70  6998.0  446.21  7005.0  444.55
  7012.2  446.60  7019.1  445.14  7047.4  449.63  7075.7  451.31  7321.0  454.63
#Mann=3,-1,0
  4097.0    0.05       0  5977.5    0.03       0  5981.5    0.05       0
Bank Sta=5977.5,5981.5
Exp/Cntr=0.3,0.1

Chan Stop Cuts=-1