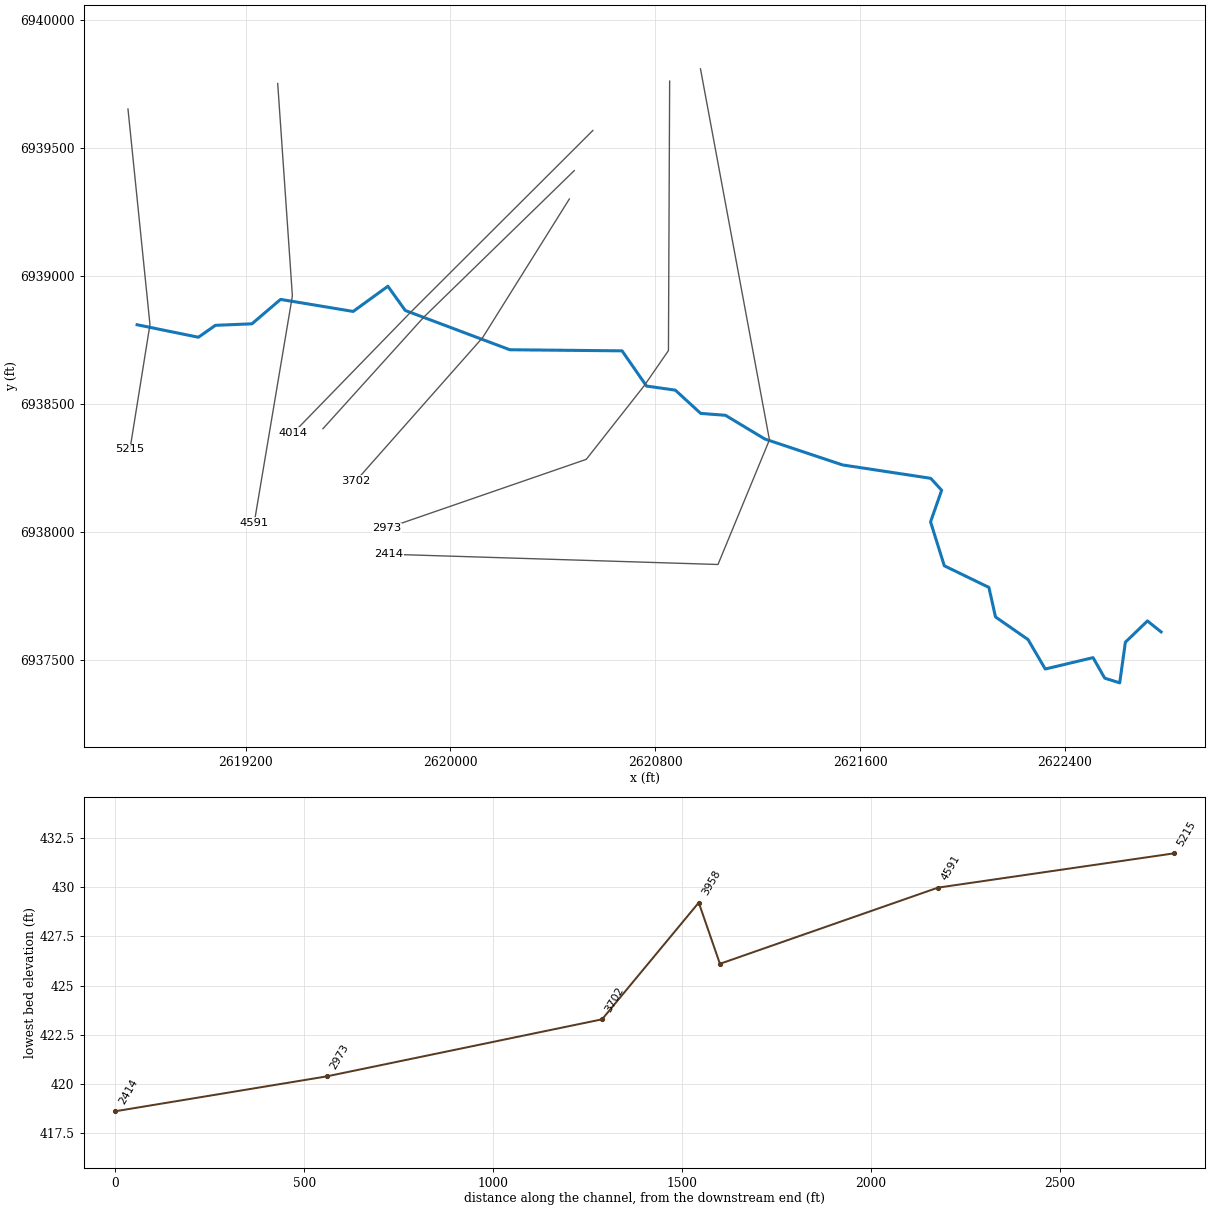
--- Big Bushy Creek Trib 3.prj (project) ---

Proj Title=Big Bushy Creek Trib 3 Base Level Engineering
Current Plan=p01
Default Exp/Contr=0.3,0.1
English Units
Geom File=g01
Flow File=f01
Plan File=p01
BEGIN DESCRIPTION:
Big Bushy Creek Trib 3
END DESCRIPTION:

--- Big Bushy Creek Trib 3.p01 (plan) ---

Plan Title=Multiple Run
Short Identifier=Multiple
Geom File=g01
Flow File=f01
Subcritical Flow
K Sum by GR= 0
Std Step Tol= 0.01
Critical Tol= 0.01
Num of Std Step Trials= 20
Max Error Tol= 0.3
Flow Tol Ratio= 0.001
Split Flow NTrial= 30
Split Flow Tol= 0.02
Split Flow Ratio= 0.02
Log Output Level= 0
Friction Slope Method= 1
Unsteady Friction Slope Method= 2
Unsteady Bridges Friction Slope Method= 1
Parabolic Critical Depth
Global Vel Dist=  1 , 1 , 1
Global Log Level= 0
CheckData=True
Encroach Param= -1, 0, 0, 0
BEGIN DESCRIPTION:
Multiple Run
END DESCRIPTION:

--- Big Bushy Creek Trib 3.f01 (steady flow) ---

Flow Title=Multiple
Number of Profiles=7
Profile Names=10-year,25-year,50-year,1pct_min,100-year,1pct_plu,500-year
River Rch & RM= Big Bushy Creek ,Reach-1,5215
     540     720     865     516    1029    2054    1456
River Rch & RM= Big Bushy Creek ,Reach-1,3702
     834    1142    1395     845    1685    3363    2460
Boundary for River Rch & Prof#=Big Bushy Creek ,Reach-1,1
Up Type=0
Dn Type=3
Dn Slope=0.005
Boundary for River Rch & Prof#=Big Bushy Creek ,Reach-1,2
Up Type=0
Dn Type=3
Dn Slope=0.005
Boundary for River Rch & Prof#=Big Bushy Creek ,Reach-1,3
Up Type=0
Dn Type=3
Dn Slope=0.005
Boundary for River Rch & Prof#=Big Bushy Creek ,Reach-1,4
Up Type=0
Dn Type=3
Dn Slope=0.005
Boundary for River Rch & Prof#=Big Bushy Creek ,Reach-1,5
Up Type=0
Dn Type=3
Dn Slope=0.005
Boundary for River Rch & Prof#=Big Bushy Creek ,Reach-1,6
Up Type=0
Dn Type=3
Dn Slope=0.005
Boundary for River Rch & Prof#=Big Bushy Creek ,Reach-1,7
Up Type=0
Dn Type=3
Dn Slope=0.005

--- Big Bushy Creek Trib 3.g01 (geometry) ---

Geom Title=Existing Conditions

River Reach=Big Bushy Creek ,Reach-1
Reach XY= 30
      2618776.00      6938811.00      2619015.45      6938762.10
      2619081.94      6938808.73      2619224.53      6938814.56
      2619336.44      6938909.96      2619620.11      6938862.97
      2619755.63      6938961.37      2619823.47      6938866.77
      2620231.94      6938713.26      2620670.33      6938709.02
      2620765.90      6938571.39      2620878.42      6938555.46
      2620977.50      6938464.62      2621074.41      6938457.17
      2621227.58      6938364.83      2621531.94      6938263.27
      2621876.00      6938211.00      2621918.76      6938164.45
      2621875.41      6938040.95      2621929.15      6937869.32
      2622103.27      6937784.88      2622129.17      6937669.34
      2622256.22      6937581.12      2622323.45      6937465.99
      2622510.10      6937510.46      2622555.76      6937430.29
      2622614.26      6937411.97      2622636.47      6937570.84
      2622722.65      6937653.76      2622776.00      6937611.00

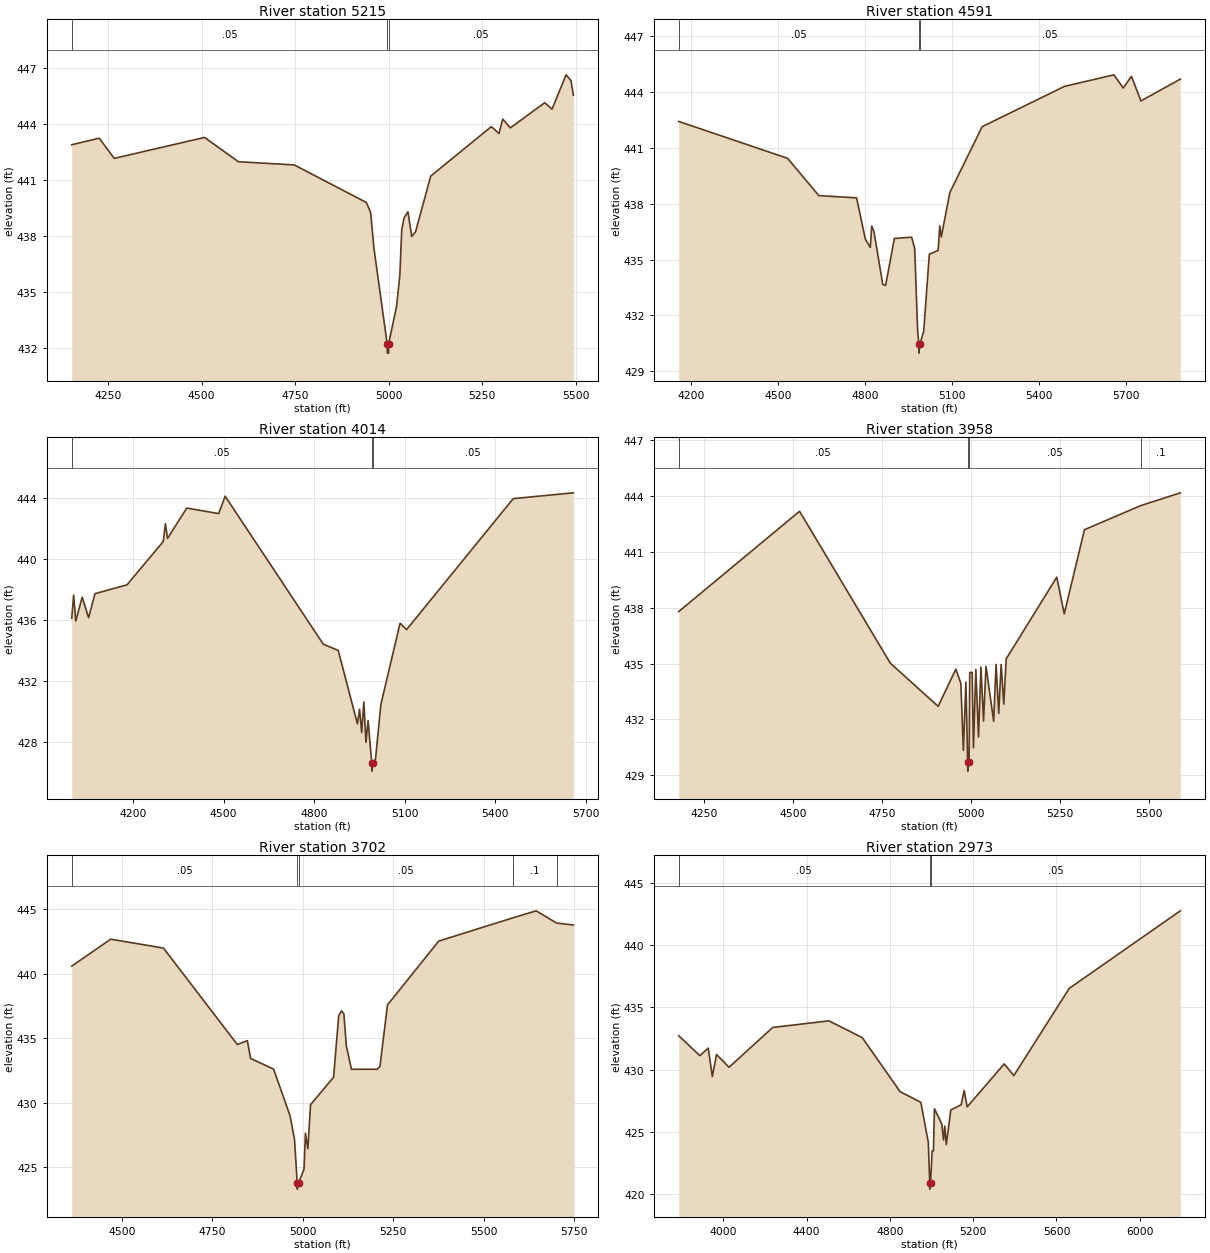
Type RM Length L Ch R = 1,5215,624,624,624
BEGIN DESCRIPTION:
Big Bushy Creek Trib 3 5.0
END DESCRIPTION:
XS GIS Cut Line= 3
      2618740.38      6939653.88      2618826.27      6938811.65
      2618748.22      6938324.77
#Sta/Elev= 30
  4153.4  442.87  4226.7  443.22  4266.9  442.14  4508.1  443.26  4598.6  441.96
  4747.6  441.79  4940.3  439.78  4951.7  439.24  4960.4  437.34  4995.8  432.22
  4996.1  431.72  4999.6  431.72  4999.8  432.22  5020.9  434.22  5029.6  435.88
  5034.7  438.32  5041.2  438.97  5051.3  439.28  5061.4  437.96  5071.6  438.21
  5112.1  441.19  5274.1  443.84  5294.4  443.47  5304.5  444.24  5324.7  443.77
  5416.7  445.12  5436.1  444.77  5473.6  446.61  5486.8  446.30  5493.1  445.52
#Mann=3,-1,0
  4153.4    0.05       0  4995.8    0.03       0  4999.8    0.05       0
Bank Sta=4995.8,4999.8
Exp/Cntr=0.3,0.1

Type RM Length L Ch R = 1,4591,577,577,577
BEGIN DESCRIPTION:
Mapping XS 52e40733
END DESCRIPTION:
XS GIS Cut Line= 3
      2619325.26      6939753.32      2619382.60      6938923.73
      2619233.51      6938036.84
#Sta/Elev= 30
  4156.0  442.41  4531.8  440.43  4639.5  438.43  4769.8  438.31  4799.9  436.10
  4817.1  435.65  4822.1  436.80  4829.9  436.50  4860.0  433.67  4870.0  433.61
  4900.1  436.13  4959.8  436.20  4970.3  435.59  4980.3  431.26  4984.4  430.48
  4984.7  429.98  4988.4  430.48  5001.4  431.16  5020.8  435.29  5051.2  435.49
  5056.9  436.81  5062.0  436.21  5091.7  438.60  5203.3  442.13  5487.2  444.29
  5657.7  444.91  5690.0  444.20  5718.2  444.83  5750.9  443.51  5886.9  444.68
#Mann=3,-1,0
  4156.0    0.05       0  4984.4    0.04       0  4988.4    0.05       0
Bank Sta=4984.4,4988.4
Exp/Cntr=0.3,0.1

Type RM Length L Ch R = 1,4014,56,56,56
BEGIN DESCRIPTION:
Big Bushy Creek Trib 3 4.0
END DESCRIPTION:
XS GIS Cut Line= 3
      2620556.16      6939569.75      2619846.03      6938861.28
      2619386.45      6938388.57
#Sta/Elev= 30
  3996.9  436.13  4003.2  437.64  4010.3  435.95  4031.5  437.51  4052.7  436.17
  4073.9  437.74  4180.0  438.32  4300.2  441.16  4307.3  442.32  4314.3  441.36
  4378.0  443.35  4484.0  442.99  4505.3  444.13  4830.5  434.43  4880.0  434.02
  4943.6  429.21  4950.7  430.16  4957.8  428.64  4964.9  430.64  4971.9  428.00
  4979.0  429.43  4991.2  426.61  4991.4  426.11  4995.2  426.61  5003.6  426.92
  5021.4  430.48  5085.0  435.81  5106.3  435.38  5460.0  443.97  5659.3  444.35
#Mann=3,-1,0
  3996.9    0.05       0  4991.2    0.03       0  4995.2    0.05       0
Bank Sta=4991.2,4995.2
Exp/Cntr=0.3,0.1

Type RM Length L Ch R = 1,3958,256,256,256
BEGIN DESCRIPTION:
Big Bushy Creek Trib 3 3.0
END DESCRIPTION:
XS GIS Cut Line= 3
      2620483.55      6939413.03      2619895.88      6938840.72
      2619502.06      6938404.89
#Sta/Elev= 30
  4179.7  437.79  4518.9  443.18  4773.5  435.02  4907.8  432.70  4957.4  434.70
  4971.5  433.94  4978.5  430.34  4985.7  434.01  4990.6  429.72  4990.9  429.22
  4994.6  429.72  4996.4  434.52  5003.2  434.52  5006.8  430.48  5013.6  434.68
  5021.0  431.05  5027.8  434.81  5035.2  431.91  5042.0  434.85  5063.6  431.90
  5070.3  434.95  5077.8  432.32  5084.5  434.95  5092.0  432.82  5098.7  435.25
  5240.7  439.64  5261.6  437.67  5318.4  442.19  5475.8  443.48  5587.4  444.17
#Mann=4,-1,0
  4179.7    0.05       0  4990.6    0.03       0  4994.6    0.05       0
  5475.8     0.1       0
Bank Sta=4990.6,4994.6
Exp/Cntr=0.3,0.1

Type RM Length L Ch R = 1,3702,729,729,729
BEGIN DESCRIPTION:
Big Bushy Creek Trib 3 2.0
END DESCRIPTION:
XS GIS Cut Line= 3
      2620464.45      6939302.19      2620126.00      6938761.00
      2619631.07      6938201.22
#Sta/Elev= 30
  4361.7  440.59  4469.2  442.68  4615.0  441.99  4819.0  434.51  4846.7  434.81
  4855.6  433.43  4919.2  432.60  4964.6  428.99  4977.0  427.15  4984.4  423.79
  4984.7  423.29  4988.4  423.79  5003.3  424.85  5007.1  427.63  5013.8  426.42
  5021.3  429.84  5084.9  431.97  5099.1  436.75  5106.7  437.12  5113.3  436.89
  5120.1  434.41  5134.2  432.59  5205.4  432.59  5212.9  432.80  5233.8  437.58
  5375.2  442.53  5581.8  444.35  5644.5  444.88  5701.0  443.93  5747.2  443.78
#Mann=5,-1,0
  4361.7    0.05       0  4984.4    0.03       0  4988.4    0.05       0
  5581.8     0.1       0  5701.0    0.05       0
Bank Sta=4984.4,4988.4
Exp/Cntr=0.3,0.1

Type RM Length L Ch R = 1,2973,559,559,559
BEGIN DESCRIPTION:
Mapping XS 8c59145a
END DESCRIPTION:
XS GIS Cut Line= 5
      2620856.26      6939762.73      2620851.54      6938709.97
      2620757.12      6938573.06      2620530.51      6938285.08
      2619751.60      6938016.00
#Sta/Elev= 30
  3785.3  432.72  3887.0  431.11  3927.0  431.72  3947.0  429.44  3967.0  431.21
  4027.0  430.18  4237.0  433.38  4507.0  433.91  4667.0  432.56  4849.0  428.22
  4948.5  427.36  4984.3  424.15  4991.1  420.89  4991.3  420.39  4995.1  420.89
  5002.6  423.46  5008.9  423.46  5013.8  426.85  5049.1  425.62  5057.2  424.34
  5063.5  425.45  5070.6  423.97  5092.4  426.75  5142.1  427.17  5156.6  428.31
  5171.0  427.00  5349.0  430.45  5395.1  429.51  5661.3  436.52  6194.9  442.75
#Mann=3,-1,0
  3785.3    0.05       0  4991.1    0.03       0  4995.1    0.05       0
Bank Sta=4991.1,4995.1
Exp/Cntr=0.3,0.1

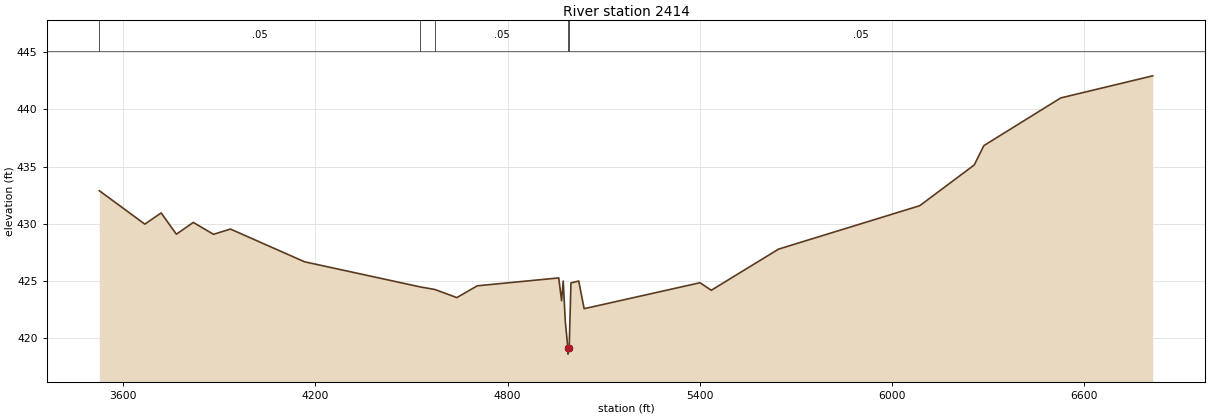
Type RM Length L Ch R = 1,2414,0,0,0
BEGIN DESCRIPTION:
Big Bushy Creek Trib 3 1.0
END DESCRIPTION:
XS GIS Cut Line= 4
      2620976.70      6939810.60      2621246.09      6938361.23
      2621045.10      6937874.35      2619759.16      6937914.46
#Sta/Elev= 30
  3525.8  432.90  3667.8  429.98  3718.7  430.96  3766.3  429.10  3819.1  430.13
  3882.1  429.09  3934.9  429.55  4166.2  426.69  4526.1  424.50  4572.8  424.27
  4641.5  423.56  4705.3  424.59  4959.5  425.28  4968.4  423.29  4973.5  425.01
  4979.9  421.51  4988.1  419.12  4988.3  418.62  4992.1  419.12  4997.6  424.84
  5021.9  425.01  5038.8  422.59  5400.5  424.86  5435.5  424.20  5645.9  427.80
  6086.1  431.59  6256.2  435.15  6286.2  436.84  6526.3  441.01  6813.3  442.94
#Mann=5,-1,0
  3525.8    0.05       0  4526.1    0.12       0  4572.8    0.05       0
  4988.1    0.03       0  4992.1    0.05       0
Bank Sta=4988.1,4992.1
Exp/Cntr=0.3,0.1

Chan Stop Cuts=-1