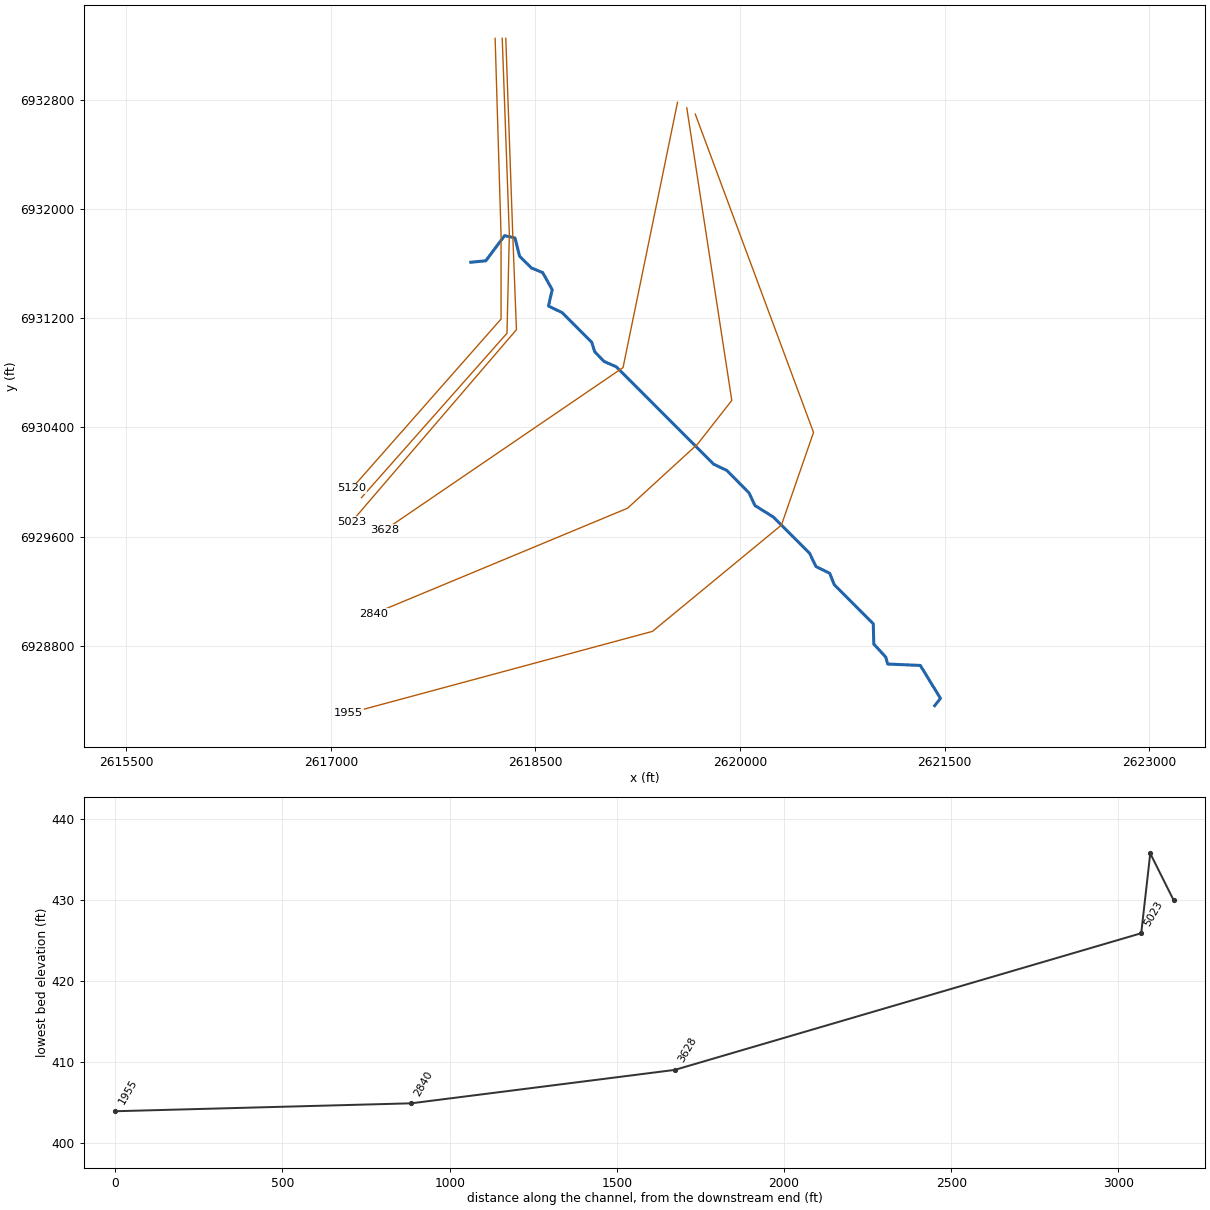
--- Big Bushy Creek Trib 5_2.prj (project) ---

Proj Title=Big Bushy Creek Trib 5_2 Base Level Engineering
Current Plan=p01
Default Exp/Contr=0.3,0.1
English Units
Geom File=g01
Flow File=f01
Plan File=p01
Y Axis Title=Elevation
X Axis Title(PF)=Main Channel Distance
X Axis Title(XS)=Station
BEGIN DESCRIPTION:
Big Bushy Creek Trib 5_2
END DESCRIPTION:
DSS Export Rating Curves= 0
DSS Export Rating Curve Sorted= 0
DSS Export Volume Flow Curves= 0
DXF OffsetX= 0
DXF OffsetY= 0
DXF ScaleX= 1
DXF ScaleY= 10

--- Big Bushy Creek Trib 5_2.p01 (plan) ---

Plan Title=Multiple Run
Short Identifier=Multiple
Geom File=g01
Flow File=f01
Subcritical Flow
K Sum by GR= 0
Std Step Tol= 0.01
Critical Tol= 0.01
Num of Std Step Trials= 20
Max Error Tol= 0.3
Flow Tol Ratio= 0.001
Split Flow NTrial= 30
Split Flow Tol= 0.02
Split Flow Ratio= 0.02
Log Output Level= 0
Friction Slope Method= 1
Unsteady Friction Slope Method= 2
Unsteady Bridges Friction Slope Method= 1
Parabolic Critical Depth
Global Vel Dist=  1 , 1 , 1
Global Log Level= 0
CheckData=True
Encroach Param= -1, 0, 0, 0
BEGIN DESCRIPTION:
Multiple Run
END DESCRIPTION:

--- Big Bushy Creek Trib 5_2.f01 (steady flow) ---

Flow Title=Multiple
Number of Profiles=7
Profile Names=10-year,25-year,50-year,1pct_min,100-year,1pct_plu,500-year
River Rch & RM= Big Bushy Creek ,Reach-1,5120
    1386    1960    2447    1512    3018    6021    4592
Boundary for River Rch & Prof#=Big Bushy Creek ,Reach-1,1
Up Type=0
Dn Type=3
Dn Slope=0.005
Boundary for River Rch & Prof#=Big Bushy Creek ,Reach-1,2
Up Type=0
Dn Type=3
Dn Slope=0.005
Boundary for River Rch & Prof#=Big Bushy Creek ,Reach-1,3
Up Type=0
Dn Type=3
Dn Slope=0.005
Boundary for River Rch & Prof#=Big Bushy Creek ,Reach-1,4
Up Type=0
Dn Type=3
Dn Slope=0.005
Boundary for River Rch & Prof#=Big Bushy Creek ,Reach-1,5
Up Type=0
Dn Type=3
Dn Slope=0.005
Boundary for River Rch & Prof#=Big Bushy Creek ,Reach-1,6
Up Type=0
Dn Type=3
Dn Slope=0.005
Boundary for River Rch & Prof#=Big Bushy Creek ,Reach-1,7
Up Type=0
Dn Type=3
Dn Slope=0.005

--- Big Bushy Creek Trib 5_2.g01 (geometry) ---

Geom Title=Existing Conditions
Program Version=4.10

River Reach=Big Bushy Creek ,Reach-1
Reach XY= 30
        2618026.        6931611.      2618135.84      6931621.42
      2618273.49      6931806.05      2618349.95       6931788.5
      2618383.86      6931654.81      2618469.95      6931569.16
      2618553.15      6931534.84      2618622.63      6931409.26
      2618595.14      6931290.58      2618696.07      6931241.21
      2618912.37      6931024.21      2618934.15      6930954.93
      2619002.49      6930883.99      2619092.67      6930844.35
      2619805.91      6930130.79      2619902.82       6930084.7
      2620065.22      6929920.68      2620108.92      6929827.42
      2620242.67      6929744.35      2620509.34      6929477.66
      2620555.54      6929380.64      2620656.36      6929331.47
      2620689.64       6929247.8        2620976.        6928961.
      2620979.51      6928812.45      2621067.68      6928716.69
      2621081.44      6928666.18      2621320.56      6928655.82
      2621468.42       6928414.2        2621426.        6928361.

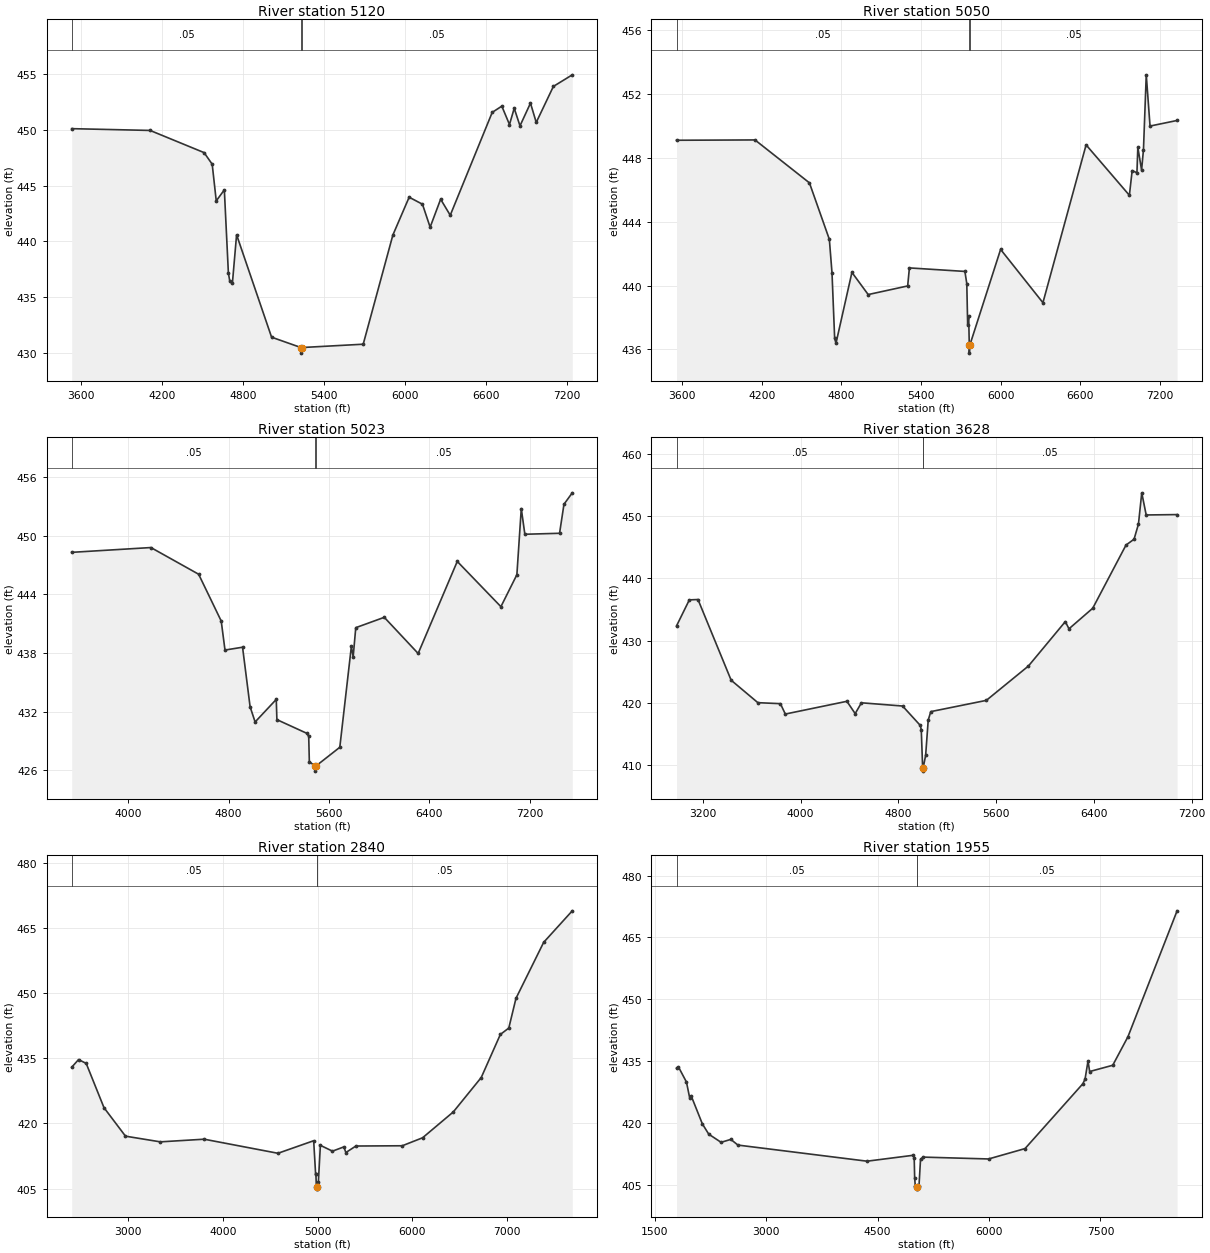
Type RM Length L Ch R = 1 ,5120    ,70,70,70
BEGIN DESCRIPTION:
Mapping XS c6cbcf65
END DESCRIPTION:
XS GIS Cut Line= 4
      2618204.33        6933252.      2618247.73      6931811.03
      2618247.73      6931194.71      2617155.16      6929954.73
#Sta/Elev= 30
  3531.2  450.11  4112.5  449.95  4512.6  447.96  4572.7  446.92  4602.7  443.63
  4662.7  444.62  4692.7  437.16  4702.7  436.45  4722.7  436.28  4753.5  440.59
  5012.9   431.4  5230.9  430.47  5231.1  429.97  5234.9  430.47  5692.1  430.77
  5912.1  440.57  6032.6  443.96  6131.3  443.33  6188.2  441.27    6266  443.78
  6337.2  442.34  6648.4  451.57  6719.5  452.13  6776.4  450.48  6811.5  451.94
  6854.2  450.36    6932   452.4  6974.7  450.67  7101.8   453.9  7241.8  454.94
#Mann= 3 ,-1 , 0
  3531.2     .05       0  5230.9     .04       0  5234.9     .05       0
Bank Sta=5230.9,5234.9
XS Rating Curve= 0 ,0
Exp/Cntr=0.3,0.1

Type RM Length L Ch R = 1 ,5050    ,27,27,27
BEGIN DESCRIPTION:
Mapping XS b55ebee9
END DESCRIPTION:
XS GIS Cut Line= 4
      2618256.41      6933252.02      2618308.49      6931811.03
      2618291.13      6931090.55      2617224.35      6929884.99
#Sta/Elev= 30
  3558.4  449.11  4149.8  449.13  4560.1  446.44  4710.2   442.9  4730.2   440.8
  4750.2  436.69  4760.2  436.39  4880.3  440.83  5002.8  439.44  5300.4  439.98
  5313.5  441.11  5731.7  440.89  5745.9  440.13  5752.6  437.55  5760.1  438.07
  5764.8  436.27  5765.1  435.77  5768.8  436.27  6000.8  442.27  6319.7  438.93
  6645.1  448.82  6971.3  445.66  6992.2  447.21  7028.2  447.07  7034.9  448.67
  7063.3  447.24  7077.5  448.53  7098.4  453.21  7126.9     450  7330.8  450.35
#Mann= 3 ,-1 , 0
  3558.4     .05       0  5764.8     .04       0  5768.8     .05       0
Bank Sta=5764.8,5768.8
XS Rating Curve= 0 ,0
Exp/Cntr=0.3,0.1

Type RM Length L Ch R = 1 ,5023    ,1395,1395,1395
BEGIN DESCRIPTION:
Mapping XS 1fed4d48
END DESCRIPTION:
XS GIS Cut Line= 4
      2618282.45      6933252.03      2618334.54      6931784.99
      2618360.58      6931116.59      2617153.99      6929710.35
#Sta/Elev= 30
  3549.6  448.29    4181  448.78  4561.3  446.05  4741.4  441.26  4771.4  438.29
  4911.5  438.58  4971.5  432.49  5011.5  430.93  5180.1  433.24  5185.1  431.17
  5421.9  429.78  5438.7  429.47  5443.7  426.88  5489.9   426.4  5490.2   425.9
  5493.9   426.4  5686.5  428.34  5778.7  438.67    5793   437.6  5813.8  440.58
    6041  441.64    6311  437.94  6622.7  447.36  6970.6  442.73  7097.9     446
    7133  452.77  7161.5  450.14  7438.1  450.24  7473.2  453.21  7539.4  454.38
#Mann= 3 ,-1 , 0
  3549.6     .05       0  5489.9     .04       0  5493.9     .05       0
Bank Sta=5489.9,5493.9
XS Rating Curve= 0 ,0
Exp/Cntr=0.3,0.1

Type RM Length L Ch R = 1 ,3628    ,788,788,788
BEGIN DESCRIPTION:
Mapping XS cc5c5e01
END DESCRIPTION:
XS GIS Cut Line= 3
      2619541.13      6932783.24      2619141.83      6930838.81
      2617397.07      6929649.59
#Sta/Elev= 30
  2983.9  432.35  3088.7  436.54  3159.7   436.6  3431.1  423.62  3649.7  420.01
  3834.1  419.85  3874.3  418.18  4378.1  420.23    4446  418.25  4497.1  419.99
    4834  419.47  4977.9  416.37  4986.8  415.69  4998.2   409.5  4998.4     409
  5002.2   409.5  5022.7  411.54  5043.7   417.2  5064.7  418.57  5519.4  420.38
  5863.6   425.9  6165.7  433.05  6195.6  431.89  6390.1   435.2  6662.4  445.36
  6728.2   446.3  6764.1  448.72  6791.2  453.76  6827.5   450.2  7080.4  450.26
#Mann= 3 ,-1 , 0
  2983.9     .05       0  4998.2     .05       0  5002.2     .05       0
Bank Sta=4998.2,5002.2
XS Rating Curve= 0 ,0
Exp/Cntr=0.3,0.1

Type RM Length L Ch R = 1 ,2840    ,885,885,885
BEGIN DESCRIPTION:
Mapping XS b1d5533c
END DESCRIPTION:
XS GIS Cut Line= 5
      2619609.03      6932742.24      2619938.89      6930598.16
      2619687.16      6930276.98        2619175.      6929808.23
      2617317.32      6929035.64
#Sta/Elev= 30
  2403.4  432.92  2475.5  434.68  2556.4  433.81  2744.4  423.61  2971.2  417.06
  3338.8  415.75  3801.7  416.36  4580.5  413.12  4957.5  416.01  4977.7  408.44
  4980.8  408.44  4985.7  405.43  4991.1  405.37  4991.3  404.87  4995.1  405.37
  5007.3  406.61  5028.2  414.95  5155.9  413.61  5276.1  414.59  5297.1  413.29
  5403.2  414.79  5892.6  414.85  6107.2  416.69  6431.4  422.64  6726.2  430.56
  6927.9  440.47    7017  441.94  7092.8  448.78  7385.2  461.67    7687  468.92
#Mann= 3 ,-1 , 0
  2403.4     .05       0  4991.1     .05       0  4995.1     .05       0
Bank Sta=4991.1,4995.1
XS Rating Curve= 0 ,0
Exp/Cntr=0.3,0.1

Type RM Length L Ch R = 1 ,1955    ,0,0,0
BEGIN DESCRIPTION:
Big Bushy Creek Trib 5_2 1.0
END DESCRIPTION:
XS GIS Cut Line= 5
      2619671.33      6932696.49      2620537.85      6930363.78
      2620302.69      6929684.38       2619357.3      6928905.45
      2617129.47       6928304.5
#Sta/Elev= 30
  1792.6  433.25  1817.4  433.59  1926.5  429.88  1969.2  426.09  1988.9  426.58
  2140.7  419.72  2226.5  417.23  2392.6  415.25  2523.9  415.96  2619.5  414.58
    4358  410.67  4982.4  412.11    4993  411.37  4999.1  406.55  5007.7  404.63
    5033  404.39  5033.2  403.89    5037  404.39  5057.2  404.62    5078  411.11
  5113.2  411.66    5994  411.21  6485.2  413.73  7263.4  429.46  7292.9  430.57
  7332.9  434.96  7355.3  432.43    7666  433.95  7870.9  440.88  8532.4  471.43
#Mann= 3 ,-1 , 0
  1792.6     .05       0    5033    .035       0    5037     .05       0
Bank Sta=5033,5037
XS Rating Curve= 0 ,0
Exp/Cntr=0.3,0.1

Chan Stop Cuts=-1
Use User Specified Reach Order=0
Composite Channel Slope=5