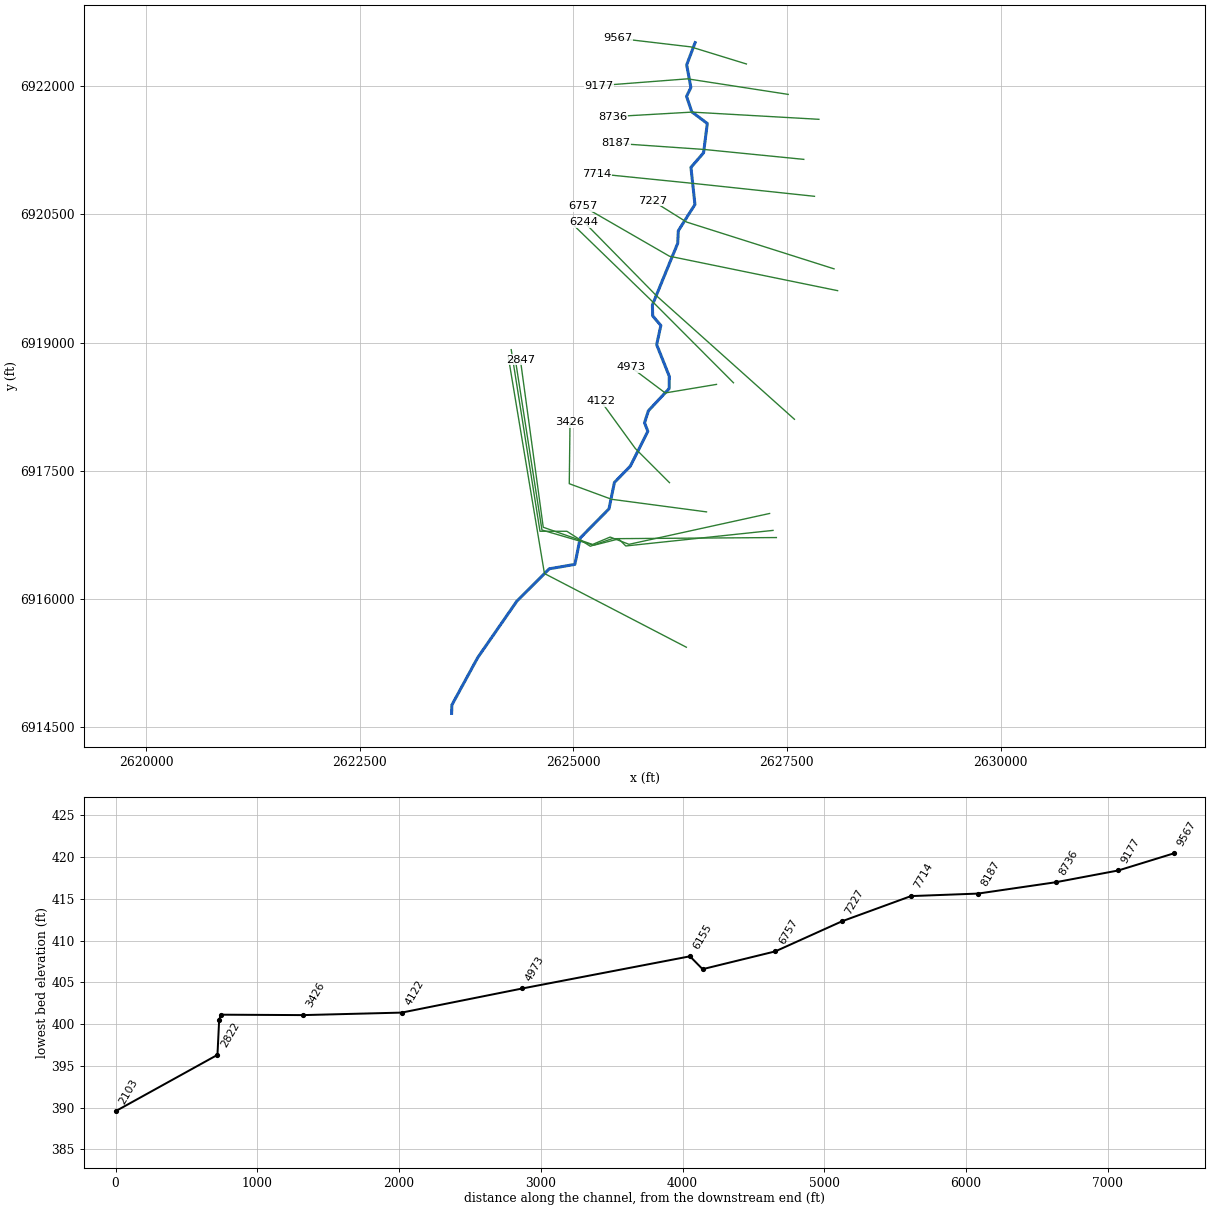
--- Big Bushy Creek Trib 7.prj (project) ---

Proj Title=Big Bushy Creek Trib 7 Base Level Engineering
Current Plan=p01
Default Exp/Contr=0.3,0.1
English Units
Geom File=g01
Flow File=f01
Plan File=p01
BEGIN DESCRIPTION:
Big Bushy Creek Trib 7
END DESCRIPTION:

--- Big Bushy Creek Trib 7.p01 (plan) ---

Plan Title=Multiple Run
Short Identifier=Multiple
Geom File=g01
Flow File=f01
Subcritical Flow
K Sum by GR= 0
Std Step Tol= 0.01
Critical Tol= 0.01
Num of Std Step Trials= 20
Max Error Tol= 0.3
Flow Tol Ratio= 0.001
Split Flow NTrial= 30
Split Flow Tol= 0.02
Split Flow Ratio= 0.02
Log Output Level= 0
Friction Slope Method= 1
Unsteady Friction Slope Method= 2
Unsteady Bridges Friction Slope Method= 1
Parabolic Critical Depth
Global Vel Dist=  1 , 1 , 1
Global Log Level= 0
CheckData=True
Encroach Param= -1, 0, 0, 0
BEGIN DESCRIPTION:
Multiple Run
END DESCRIPTION:

--- Big Bushy Creek Trib 7.f01 (steady flow) ---

Flow Title=Multiple
Number of Profiles=7
Profile Names=10-year,25-year,50-year,1pct_min,100-year,1pct_plu,500-year
River Rch & RM= Big Bushy Creek ,Reach-1,9567
     299     379     440     253     505    1008     665
River Rch & RM= Big Bushy Creek ,Reach-1,7714
     488     639     757     444     887    1769    1216
River Rch & RM= Big Bushy Creek ,Reach-1,6244
     748    1010    1223     732    1462    2916    2090
Boundary for River Rch & Prof#=Big Bushy Creek ,Reach-1,1
Up Type=0
Dn Type=3
Dn Slope=0.005
Boundary for River Rch & Prof#=Big Bushy Creek ,Reach-1,2
Up Type=0
Dn Type=3
Dn Slope=0.005
Boundary for River Rch & Prof#=Big Bushy Creek ,Reach-1,3
Up Type=0
Dn Type=3
Dn Slope=0.005
Boundary for River Rch & Prof#=Big Bushy Creek ,Reach-1,4
Up Type=0
Dn Type=3
Dn Slope=0.005
Boundary for River Rch & Prof#=Big Bushy Creek ,Reach-1,5
Up Type=0
Dn Type=3
Dn Slope=0.005
Boundary for River Rch & Prof#=Big Bushy Creek ,Reach-1,6
Up Type=0
Dn Type=3
Dn Slope=0.005
Boundary for River Rch & Prof#=Big Bushy Creek ,Reach-1,7
Up Type=0
Dn Type=3
Dn Slope=0.005

--- Big Bushy Creek Trib 7.g01 (geometry) ---

Geom Title=Existing Conditions

River Reach=Big Bushy Creek ,Reach-1
Reach XY= 30
      2626426.00      6922511.00      2626327.22      6922250.49
      2626376.39      6921986.00      2626325.72      6921881.18
      2626386.51      6921701.19      2626568.31      6921564.67
      2626524.95      6921221.43      2626377.04      6921050.56
      2626423.93      6920616.86      2626229.56      6920309.53
      2626222.24      6920162.56      2625926.05      6919440.96
      2625929.54      6919312.47      2626024.96      6919200.56
      2625976.09      6918976.39      2626123.75      6918605.06
      2626122.48      6918462.46      2625879.19      6918202.65
      2625833.59      6918060.99      2625872.63      6917962.73
      2625668.14      6917554.83      2625481.47      6917363.45
      2625418.14      6917054.83      2625081.52      6916713.43
      2625018.32      6916404.48      2624719.81      6916353.19
      2624339.62      6915974.24      2623881.52      6915313.43
      2623579.39      6914759.59      2623576.00      6914661.00

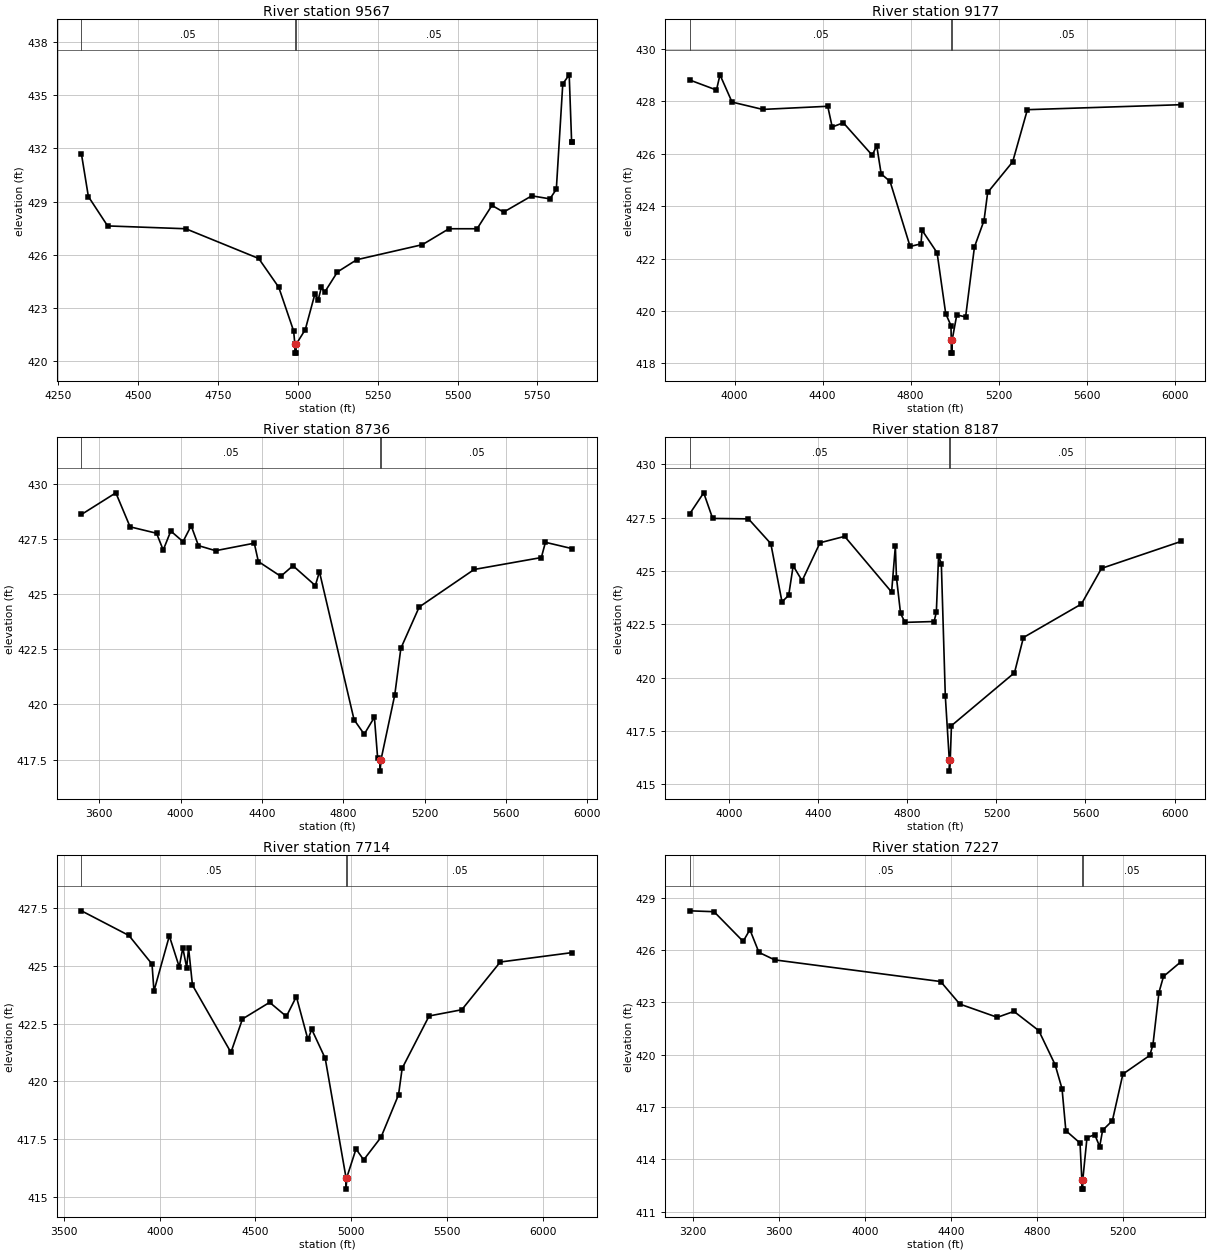
Type RM Length L Ch R = 1,9567,390,390,390
BEGIN DESCRIPTION:
Big Bushy Creek Trib 7 17.0
END DESCRIPTION:
XS GIS Cut Line= 3
      2627026.03      6922260.99      2626376.00      6922461.00
      2625525.96      6922561.00
#Sta/Elev= 30
  4323.5  431.68  4345.1  429.28  4405.3  427.62  4649.8  427.46  4878.0  425.78
  4940.8  424.15  4987.3  421.68  4991.1  420.93  4991.4  420.43  4994.9  420.43
  4995.1  420.93  5023.7  421.76  5053.9  423.78  5064.0  423.44  5074.1  424.14
  5084.2  423.87  5124.4  425.02  5184.8  425.71  5390.0  426.56  5473.1  427.46
  5561.2  427.46  5607.7  428.78  5644.2  428.40  5732.3  429.32  5789.0  429.15
  5809.1  429.69  5829.3  435.65  5849.4  436.16  5856.9  432.39  5859.5  432.39
#Mann=3,-1,0
  4323.5    0.05       0  4991.1    0.04       0  4995.1    0.05       0
Bank Sta=4991.1,4995.1
Exp/Cntr=0.3,0.1

Type RM Length L Ch R = 1,9177,441,441,441
BEGIN DESCRIPTION:
Big Bushy Creek Trib 7 16.0
END DESCRIPTION:
XS GIS Cut Line= 3
      2627515.39      6921905.00      2626337.18      6922087.02
      2625300.24      6922007.12
#Sta/Elev= 30
  3796.4  428.81  3917.2  428.43  3933.2  429.01  3988.0  427.97  4127.5  427.69
  4423.1  427.81  4443.4  427.02  4494.0  427.18  4625.5  425.94  4645.7  426.31
  4666.0  425.23  4706.5  424.94  4797.5  422.46  4847.0  422.56  4852.0  423.08
  4920.2  422.22  4959.4  419.90  4983.3  419.44  4984.7  418.89  4984.9  418.39
  4988.4  418.39  4988.7  418.89  5009.8  419.85  5049.9  419.77  5090.1  422.44
  5133.6  423.45  5150.2  424.52  5263.9  425.69  5330.8  427.68  6028.6  427.87
#Mann=3,-1,0
  3796.4    0.05       0  4984.7    0.04       0  4988.7    0.05       0
Bank Sta=4984.7,4988.7
Exp/Cntr=0.3,0.1

Type RM Length L Ch R = 1,8736,549,549,549
BEGIN DESCRIPTION:
Big Bushy Creek Trib 7 15.0
END DESCRIPTION:
XS GIS Cut Line= 3
      2627874.80      6921613.33      2626389.39      6921697.67
      2625463.31      6921644.58
#Sta/Elev= 30
  3512.2  428.60  3681.3  429.58  3751.4  428.04  3881.6  427.75  3914.4  426.99
  3951.7  427.85  4011.8  427.37  4051.9  428.09  4087.7  427.19  4172.1  426.96
  4362.4  427.30  4382.4  426.47  4492.6  425.80  4552.7  426.28  4662.9  425.38
  4682.9  426.01  4853.2  419.31  4903.2  418.65  4953.3  419.42  4969.4  417.56
  4981.4  417.48  4981.6  416.98  4985.4  417.48  5053.5  420.43  5083.5  422.54
  5173.7  424.41  5444.1  426.11  5774.7  426.65  5794.7  427.34  5927.6  427.05
#Mann=3,-1,0
  3512.2    0.05       0  4981.4    0.03       0  4985.4    0.05       0
Bank Sta=4981.4,4985.4
Exp/Cntr=0.3,0.1

Type RM Length L Ch R = 1,8187,473,473,473
BEGIN DESCRIPTION:
Big Bushy Creek Trib 7 14.0
END DESCRIPTION:
XS GIS Cut Line= 3
      2627697.67      6921144.59      2626526.00      6921261.00
      2625500.40      6921332.04
#Sta/Elev= 30
  3823.0  427.69  3885.0  428.66  3925.2  427.46  4086.0  427.44  4186.5  426.28
  4236.7  423.55  4266.8  423.86  4286.9  425.24  4327.1  424.54  4407.5  426.32
  4518.1  426.62  4729.1  424.01  4745.9  426.16  4750.9  424.69  4769.3  423.01
  4789.4  422.59  4920.0  422.63  4930.1  423.07  4940.1  425.71  4952.5  425.33
  4970.3  419.15  4988.4  416.12  4988.6  415.62  4992.4  416.12  4997.9  417.75
  5281.1  420.23  5321.2  421.88  5581.8  423.45  5672.0  425.12  6028.5  426.38
#Mann=3,-1,0
  3823.0    0.05       0  4988.4    0.04       0  4992.4    0.05       0
Bank Sta=4988.4,4992.4
Exp/Cntr=0.3,0.1

Type RM Length L Ch R = 1,7714,487,487,487
BEGIN DESCRIPTION:
Big Bushy Creek Trib 7 13.0
END DESCRIPTION:
XS GIS Cut Line= 3
      2627822.67      6920712.30      2626426.00      6920861.00
      2625270.76      6920977.90
#Sta/Elev= 30
  3590.6  427.39  3838.7  426.32  3959.3  425.08  3969.4  423.91  4049.8  426.30
  4101.5  424.96  4120.2  425.78  4140.4  424.93  4150.4  425.78  4170.5  424.17
  4371.7  421.25  4432.0  422.70  4574.0  423.42  4661.4  422.81  4713.6  423.67
  4773.9  421.81  4794.0  422.25  4864.4  420.99  4973.0  415.82  4973.3  415.32
  4977.0  415.82  5025.3  417.06  5065.5  416.59  5156.0  417.57  5247.5  419.41
  5266.5  420.56  5407.3  422.83  5578.1  423.10  5779.1  425.17  6156.3  425.58
#Mann=3,-1,0
  3590.6    0.05       0  4973.0    0.04       0  4977.0    0.05       0
Bank Sta=4973,4977
Exp/Cntr=0.3,0.1

Type RM Length L Ch R = 1,7227,470,470,470
BEGIN DESCRIPTION:
Big Bushy Creek Trib 7 12.0
END DESCRIPTION:
XS GIS Cut Line= 3
      2628051.86      6919863.34      2626326.00      6920411.00
      2625925.98      6920661.02
#Sta/Elev= 30
  3185.3  428.24  3297.5  428.19  3432.8  426.49  3464.2  427.16  3506.2  425.86
  3579.6  425.43  4351.0  424.19  4439.9  422.90  4614.4  422.14  4691.7  422.48
  4807.1  421.38  4883.0  419.43  4915.3  418.05  4933.0  415.65  4998.9  414.94
  5007.5  412.80  5007.8  412.30  5011.3  412.30  5011.5  412.80  5031.3  415.25
  5067.3  415.42  5090.3  414.74  5103.9  415.67  5149.3  416.22  5198.2  418.89
  5323.2  419.96  5338.0  420.58  5365.7  423.56  5386.9  424.48  5467.7  425.32
#Mann=3,-1,0
  3185.3    0.05       0  5007.5    0.03       0  5011.5    0.05       0
Bank Sta=5007.5,5011.5
Exp/Cntr=0.3,0.1

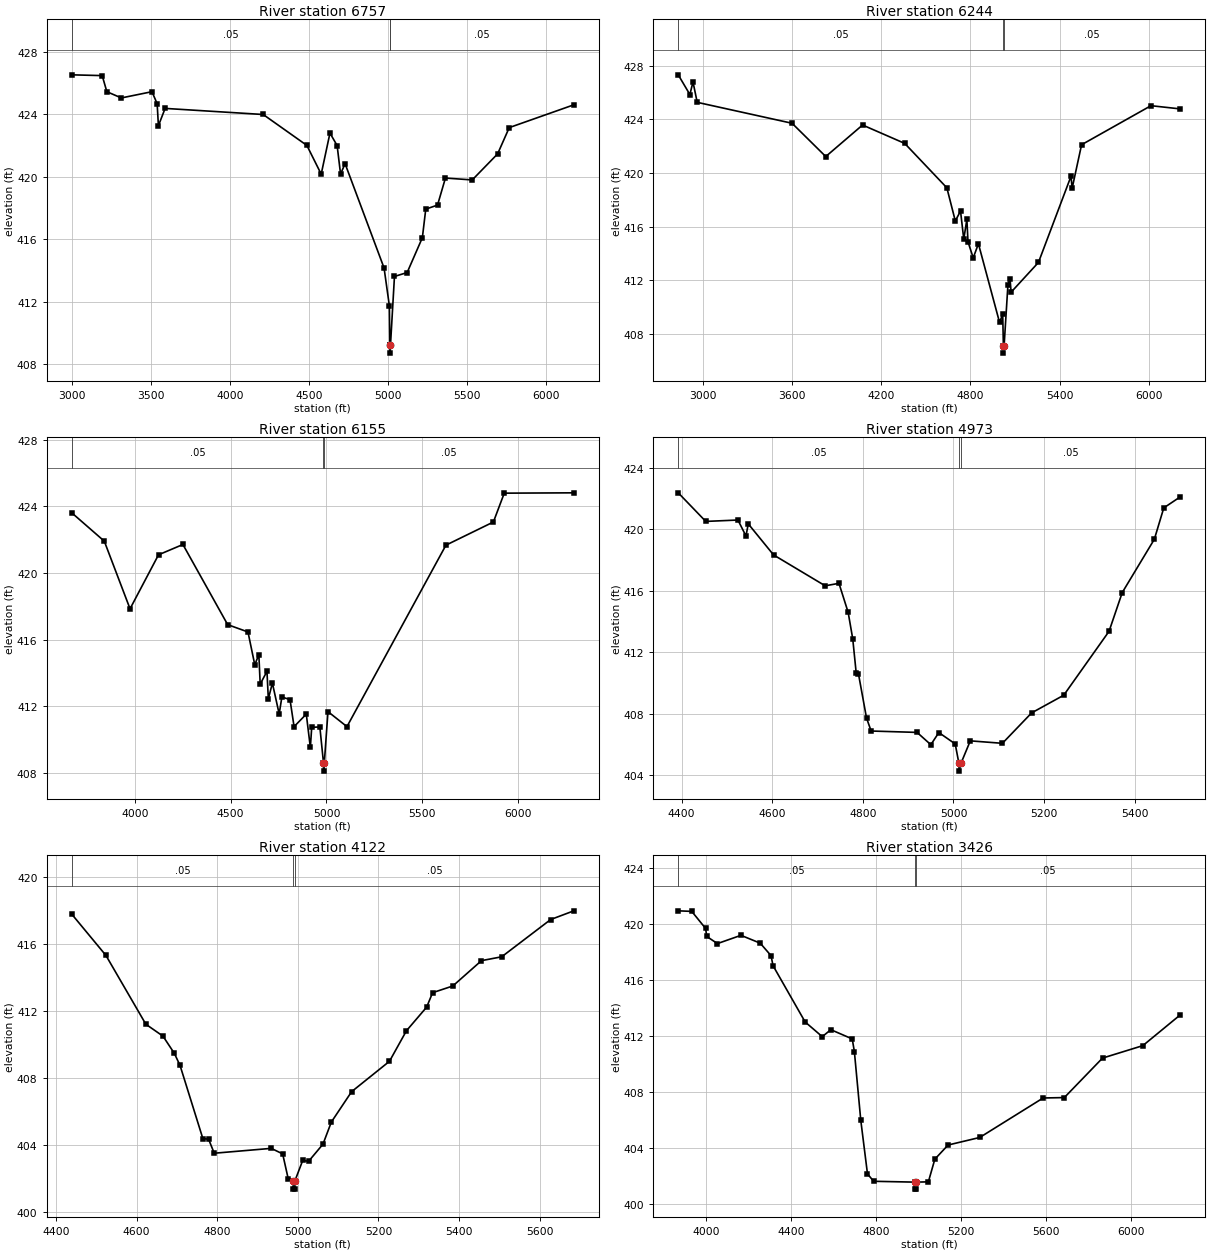
Type RM Length L Ch R = 1,6757,513,513,513
BEGIN DESCRIPTION:
Big Bushy Creek Trib 7 11.0
END DESCRIPTION:
XS GIS Cut Line= 3
      2628093.55      6919608.12      2626126.00      6920011.00
      2625111.53      6920596.34
#Sta/Elev= 30
  2995.9  426.52  3188.6  426.47  3218.0  425.44  3309.8  425.04  3503.8  425.44
  3536.6  424.67  3544.6  423.26  3587.0  424.37  4208.1  423.98  4484.8  422.00
  4575.5  420.16  4631.0  422.79  4676.4  421.99  4698.1  420.17  4726.8  420.83
  4973.7  414.15  5007.2  411.73  5010.2  409.20  5010.4  408.70  5014.2  409.20
  5039.5  413.61  5119.9  413.86  5216.1  416.09  5237.7  417.92  5312.3  418.18
  5362.2  419.91  5532.1  419.79  5692.9  421.46  5766.3  423.14  6175.5  424.60
#Mann=3,-1,0
  2995.9    0.05       0  5010.2    0.04       0  5014.2    0.05       0
Bank Sta=5010.2,5014.2
Exp/Cntr=0.3,0.1

Type RM Length L Ch R = 1,6244,89,89,89
BEGIN DESCRIPTION:
Big Bushy Creek Trib 7 10.0
END DESCRIPTION:
XS GIS Cut Line= 3
      2627588.35      6918102.89      2625976.15      6919545.94
      2625126.83      6920410.72
#Sta/Elev= 30
  2836.3  427.31  2914.6  425.84  2935.5  426.78  2963.9  425.26  3601.7  423.70
  3828.2  421.22  4075.7  423.57  4359.0  422.20  4642.4  418.89  4699.2  416.42
  4734.3  417.16  4756.1  415.06  4777.0  416.54  4784.5  414.87  4819.6  413.67
  4854.7  414.72  4996.7  408.86  5017.9  409.46  5022.7  407.07  5023.1  406.57
  5027.0  407.07  5053.2  411.68  5067.3  412.10  5074.4  411.11  5258.3  413.33
  5477.5  419.76  5484.5  418.84  5548.2  422.10  6014.9  425.01  6212.1  424.77
#Mann=3,-1,0
  2836.3    0.05       0  5022.7    0.03       0  5027.0    0.05       0
Bank Sta=5022.7,5027
Exp/Cntr=0.3,0.1

Type RM Length L Ch R = 1,6155,1182,1182,1182
BEGIN DESCRIPTION:
Big Bushy Creek Trib 7 9.0
END DESCRIPTION:
XS GIS Cut Line= 3
      2626874.81      6918529.97      2625936.84      6919470.65
      2625010.20      6920368.54
#Sta/Elev= 30
  3671.6  423.61  3841.2  421.91  3975.5  417.85  4124.0  421.09  4251.3  421.71
  4484.7  416.90  4590.7  416.46  4626.1  414.49  4647.3  415.10  4654.4  413.33
  4689.7  414.10  4696.8  412.45  4718.0  413.39  4753.4  411.54  4767.5  412.56
  4809.9  412.40  4831.1  410.78  4894.8  411.53  4916.0  409.53  4923.1  410.74
  4965.5  410.76  4984.5  408.61  4984.9  408.11  4988.8  408.61  5007.9  411.68
  5106.9  410.78  5623.2  421.67  5870.7  423.06  5927.3  424.79  6290.3  424.81
#Mann=3,-1,0
  3671.6    0.05       0  4984.5    0.03       0  4988.8    0.05       0
Bank Sta=4984.5,4988.8
Exp/Cntr=0.3,0.1

Type RM Length L Ch R = 1,4973,851,851,851
BEGIN DESCRIPTION:
Big Bushy Creek Trib 7 7.0
END DESCRIPTION:
XS GIS Cut Line= 3
      2626675.99      6918511.00      2626076.00      6918411.00
      2625675.97      6918711.02
#Sta/Elev= 30
  4392.5  422.37  4453.3  420.51  4524.3  420.60  4542.0  419.56  4547.1  420.35
  4602.9  418.33  4716.9  416.32  4747.3  416.48  4767.6  414.59  4777.7  412.87
  4785.3  410.66  4790.4  410.58  4808.1  407.72  4818.3  406.87  4919.7  406.78
  4950.1  405.98  4967.8  406.77  5003.9  406.03  5012.1  404.76  5012.5  404.26
  5016.5  404.76  5037.2  406.23  5108.1  406.07  5172.6  408.05  5243.5  409.20
  5343.5  413.36  5372.6  415.88  5443.5  419.35  5464.3  421.39  5500.8  422.11
#Mann=3,-1,0
  4392.5    0.05       0  5012.1    0.04       0  5016.5    0.05       0
Bank Sta=5012.1,5016.5
Exp/Cntr=0.3,0.1

Type RM Length L Ch R = 1,4122,696,696,696
BEGIN DESCRIPTION:
Big Bushy Creek Trib 7 5.0
END DESCRIPTION:
XS GIS Cut Line= 3
      2626126.00      6917361.00      2625726.00      6917761.00
      2625325.97      6918311.04
#Sta/Elev= 30
  4439.1  417.76  4523.9  415.30  4622.9  411.20  4665.4  410.49  4693.7  409.46
  4707.8  408.74  4764.4  404.38  4778.5  404.35  4792.6  403.51  4934.1  403.80
  4962.4  403.47  4976.5  401.95  4988.4  401.87  4988.8  401.37  4992.4  401.37
  4992.9  401.87  5012.1  403.08  5026.8  403.03  5062.4  404.05  5083.2  405.37
  5133.5  407.18  5227.4  408.99  5269.5  410.81  5319.7  412.22  5334.4  413.08
  5384.6  413.48  5455.7  414.99  5505.9  415.22  5627.3  417.44  5684.9  417.96
#Mann=3,-1,0
  4439.1    0.05       0  4988.4    0.04       0  4992.9    0.05       0
Bank Sta=4988.4,4992.9
Exp/Cntr=0.3,0.1

Type RM Length L Ch R = 1,3426,579,579,579
BEGIN DESCRIPTION:
Mapping XS 51fafbe5
END DESCRIPTION:
XS GIS Cut Line= 4
      2626559.15      6917019.02      2625447.99      6917166.60
      2624953.20      6917348.89      2624961.86      6918067.72
#Sta/Elev= 30
  3867.3  420.95  3931.0  420.91  3996.4  419.69  4001.6  419.12  4052.1  418.61
  4163.0  419.20  4253.8  418.64  4304.7  417.75  4314.3  417.03  4465.7  413.01
  4546.4  411.96  4586.7  412.46  4687.6  411.80  4697.7  410.90  4727.9  405.99
  4759.5  402.16  4788.5  401.63  4984.3  401.57  4984.8  401.07  4988.5  401.07
  4989.1  401.57  5046.6  401.59  5077.1  403.21  5139.5  404.22  5288.7  404.76
  5587.6  407.58  5687.6  407.61  5867.6  410.43  6057.7  411.32  6234.4  413.52
#Mann=3,-1,0
  3867.3    0.05       0  4984.3    0.03       0  4989.1    0.05       0
Bank Sta=4984.3,4989.1
Exp/Cntr=0.3,0.1

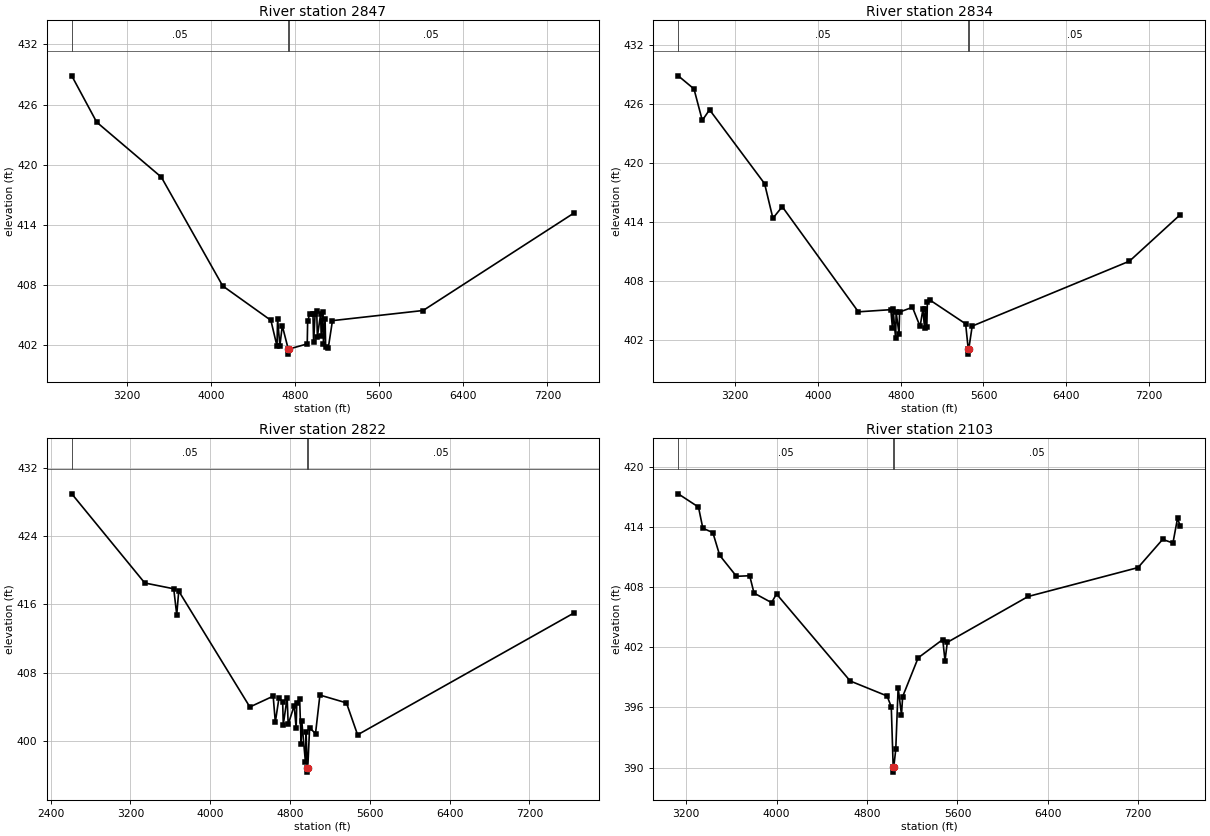
Type RM Length L Ch R = 1,2847,13,13,13
BEGIN DESCRIPTION:
Mapping XS bb93adc4
END DESCRIPTION:
XS GIS Cut Line= 6
      2627297.43      6917000.38      2625652.07      6916639.43
      2625431.59      6916724.50      2625224.99      6916637.69
      2624648.60      6916839.08      2624380.86      6918800.54
#Sta/Elev= 30
  2679.3  428.87  2916.2  424.25  3530.5  418.77  4114.1  407.92  4572.1  404.49
  4630.2  401.91  4635.7  404.66  4657.3  401.94  4680.4  403.95  4737.1  401.62
  4737.6  401.12  4741.9  401.62  4917.5  402.14  4921.5  404.39  4942.4  405.17
  4971.9  405.17  4978.0  402.32  4992.8  405.16  5007.9  405.40  5013.8  402.87
  5044.6  405.10  5050.4  402.90  5065.8  405.33  5071.7  402.16  5087.1  404.60
  5093.0  401.82  5118.2  401.77  5157.3  404.46  6019.2  405.47  7451.9  415.18
#Mann=3,-1,0
  2679.3    0.05       0  4737.1    0.04       0  4741.9    0.05       0
Bank Sta=4737.1,4741.9
Exp/Cntr=0.3,0.1

Type RM Length L Ch R = 1,2834,12,12,12
BEGIN DESCRIPTION:
Mapping XS 19e65810
END DESCRIPTION:
XS GIS Cut Line= 6
      2627337.61      6916802.41      2625614.53      6916620.11
      2625532.07      6916702.58      2625241.27      6916628.80
      2624633.63      6916806.75      2624321.25      6918806.82
#Sta/Elev= 30
  2650.0  428.82  2802.1  427.49  2882.4  424.29  2952.7  425.37  3484.5  417.86
  3564.8  414.34  3655.1  415.52  4390.6  404.83  4704.5  405.05  4720.5  403.14
  4726.2  405.09  4750.6  402.17  4755.8  404.80  4783.9  402.59  4789.1  404.81
  4913.6  405.29  4987.4  403.34  5014.8  405.12  5030.6  403.14  5036.3  405.07
  5052.1  403.26  5057.8  405.82  5080.6  406.04  5427.3  403.61  5452.6  401.03
  5453.2  400.53  5457.4  401.03  5490.9  403.38  7010.3  409.98  7502.0  414.71
#Mann=3,-1,0
  2650.0    0.05       0  5452.6    0.04       0  5457.4    0.05       0
Bank Sta=5452.6,5457.4
Exp/Cntr=0.3,0.1

Type RM Length L Ch R = 1,2822,719,719,719
BEGIN DESCRIPTION:
Mapping XS 7ddb0595
END DESCRIPTION:
XS GIS Cut Line= 6
      2627376.86      6916718.68      2625454.16      6916705.40
      2625198.95      6916616.86      2624924.64      6916792.21
      2624610.41      6916792.21      2624273.77      6918917.57
#Sta/Elev= 30
  2611.6  428.99  3343.5  418.52  3633.9  417.84  3664.0  414.79  3684.0  417.57
  4397.1  403.96  4630.8  405.23  4652.4  402.18  4689.3  405.05  4726.1  404.54
  4732.0  401.89  4771.2  405.04  4781.3  401.91  4841.8  404.13  4861.2  401.45
  4867.7  404.46  4896.4  404.91  4910.8  399.67  4917.3  402.34  4954.4  397.47
  4960.6  401.08  4972.9  396.81  4973.4  396.31  4977.7  396.81  4996.2  401.51
  5055.4  400.84  5099.4  405.36  5365.6  404.44  5477.3  400.69  7645.4  414.99
#Mann=3,-1,0
  2611.6    0.05       0  4972.9    0.04       0  4977.7    0.05       0
Bank Sta=4972.9,4977.7
Exp/Cntr=0.3,0.1

Type RM Length L Ch R = 1,2103,0,0,0
BEGIN DESCRIPTION:
Big Bushy Creek Trib 7 2.0
END DESCRIPTION:
XS GIS Cut Line= 3
      2626323.35      6915435.13      2624662.62      6916297.76
      2624239.40      6918835.31
#Sta/Elev= 30
  3128.6  417.29  3307.8  415.97  3346.4  413.86  3434.9  413.43  3495.6  411.16
  3644.0  409.07  3761.0  409.13  3799.5  407.40  3954.4  406.45  3998.6  407.31
  4650.8  398.64  4976.9  397.15  5014.2  396.07  5031.2  390.06  5031.8  389.56
  5036.2  390.06  5054.0  391.82  5075.0  397.98  5104.7  395.27  5114.8  397.08
  5252.3  400.95  5469.6  402.77  5489.9  400.67  5510.2  402.49  6225.3  407.06
  7198.2  409.94  7416.2  412.75  7507.4  412.39  7548.0  414.86  7572.6  414.04
#Mann=3,-1,0
  3128.6    0.05       0  5031.2    0.04       0  5036.2    0.05       0
Bank Sta=5031.2,5036.2
Exp/Cntr=0.3,0.1

Chan Stop Cuts=-1