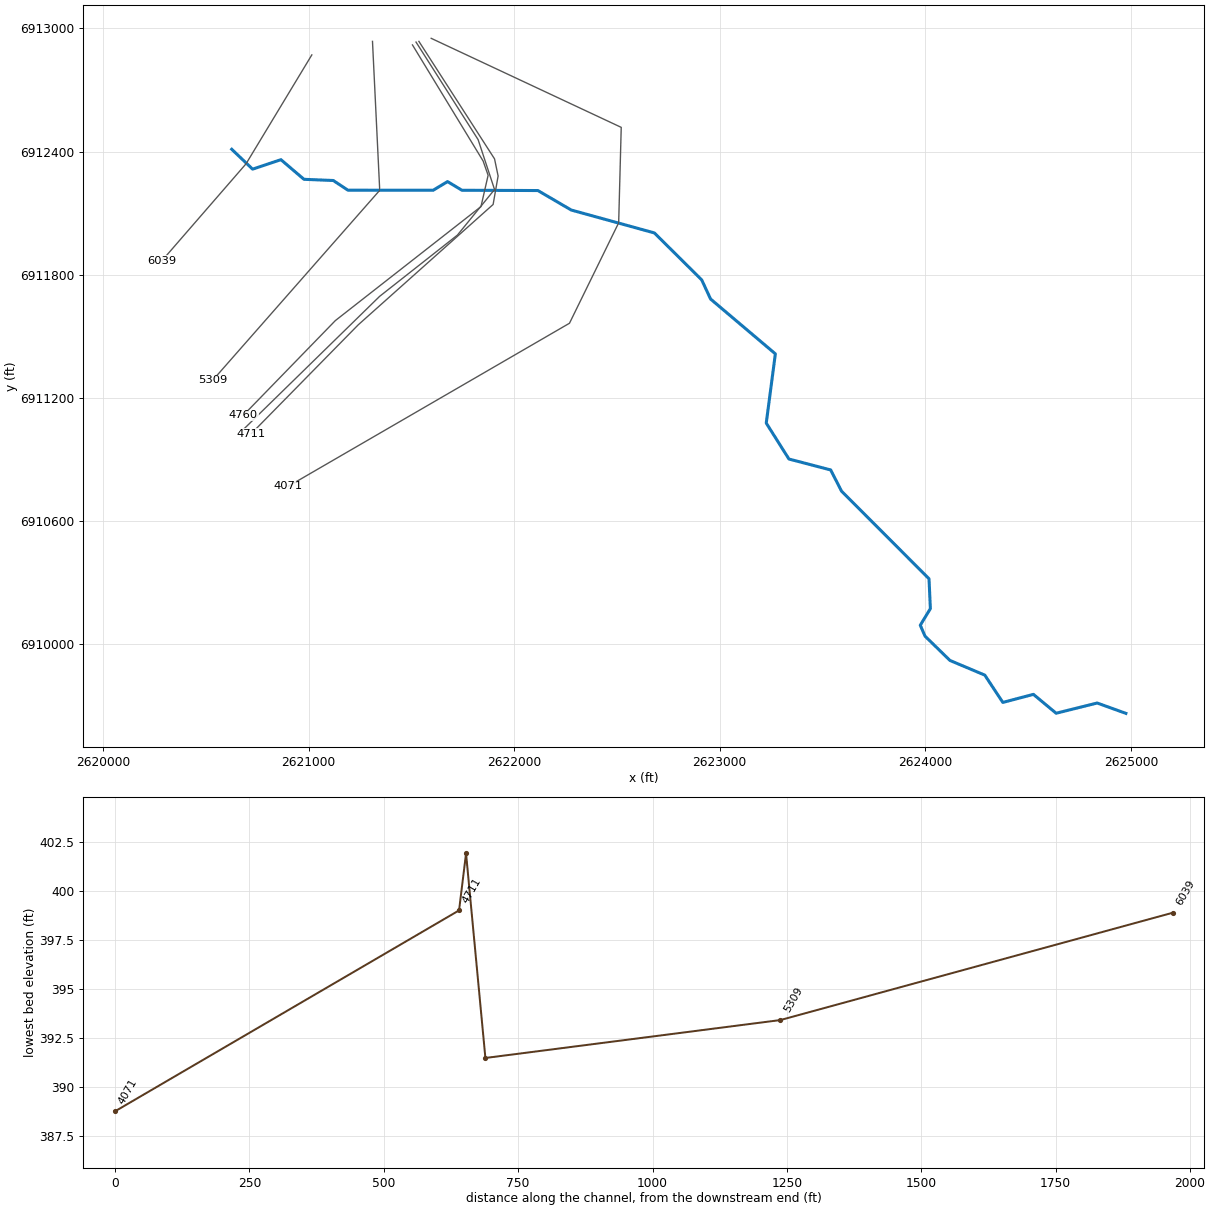
--- Big Bushy Creek Trib 8.prj (project) ---

Proj Title=Big Bushy Creek Trib 8 Base Level Engineering
Current Plan=p01
Default Exp/Contr=0.3,0.1
English Units
Geom File=g01
Flow File=f01
Plan File=p01
BEGIN DESCRIPTION:
Big Bushy Creek Trib 8
END DESCRIPTION:

--- Big Bushy Creek Trib 8.p01 (plan) ---

Plan Title=Multiple Run
Short Identifier=Multiple
Geom File=g01
Flow File=f01
Subcritical Flow
K Sum by GR= 0
Std Step Tol= 0.01
Critical Tol= 0.01
Num of Std Step Trials= 20
Max Error Tol= 0.3
Flow Tol Ratio= 0.001
Split Flow NTrial= 30
Split Flow Tol= 0.02
Split Flow Ratio= 0.02
Log Output Level= 0
Friction Slope Method= 1
Unsteady Friction Slope Method= 2
Unsteady Bridges Friction Slope Method= 1
Parabolic Critical Depth
Global Vel Dist=  1 , 1 , 1
Global Log Level= 0
CheckData=True
Encroach Param= -1, 0, 0, 0
BEGIN DESCRIPTION:
Multiple Run
END DESCRIPTION:

--- Big Bushy Creek Trib 8.f01 (steady flow) ---

Flow Title=Multiple
Number of Profiles=7
Profile Names=10-year,25-year,50-year,1pct_min,100-year,1pct_plu,500-year
River Rch & RM= Big Bushy Creek ,Reach-1,6039
     488     654     788     472     942    1880    1346
River Rch & RM= Big Bushy Creek ,Reach-1,4760
     780    1072    1315     799    1595    3182    2347
Boundary for River Rch & Prof#=Big Bushy Creek ,Reach-1,1
Up Type=0
Dn Type=3
Dn Slope=0.005
Boundary for River Rch & Prof#=Big Bushy Creek ,Reach-1,2
Up Type=0
Dn Type=3
Dn Slope=0.005
Boundary for River Rch & Prof#=Big Bushy Creek ,Reach-1,3
Up Type=0
Dn Type=3
Dn Slope=0.005
Boundary for River Rch & Prof#=Big Bushy Creek ,Reach-1,4
Up Type=0
Dn Type=3
Dn Slope=0.005
Boundary for River Rch & Prof#=Big Bushy Creek ,Reach-1,5
Up Type=0
Dn Type=3
Dn Slope=0.005
Boundary for River Rch & Prof#=Big Bushy Creek ,Reach-1,6
Up Type=0
Dn Type=3
Dn Slope=0.005
Boundary for River Rch & Prof#=Big Bushy Creek ,Reach-1,7
Up Type=0
Dn Type=3
Dn Slope=0.005

--- Big Bushy Creek Trib 8.g01 (geometry) ---

Geom Title=Existing Conditions

River Reach=Big Bushy Creek ,Reach-1
Reach XY= 30
      2620626.00      6912411.00      2620727.62      6912314.06
      2620865.37      6912360.39      2620977.47      6912264.56
      2621120.06      6912258.73      2621191.22      6912211.52
      2621606.02      6912211.18      2621676.00      6912253.44
      2621745.98      6912211.18      2622115.50      6912209.80
      2622277.58      6912114.83      2622682.17      6912003.14
      2622912.37      6911774.21      2622955.62      6911680.84
      2623270.65      6911413.70      2623226.37      6911076.17
      2623336.62      6910900.95      2623539.67      6910847.77
      2623592.66      6910744.34      2624018.19      6910317.19
      2624024.77      6910171.50      2623975.64      6910090.79
      2623998.71      6910037.53      2624119.94      6909919.14
      2624289.56      6909847.52      2624377.28      6909714.38
      2624526.10      6909753.67      2624636.62      6909661.61
      2624836.17      6909711.51      2624976.00      6909661.00

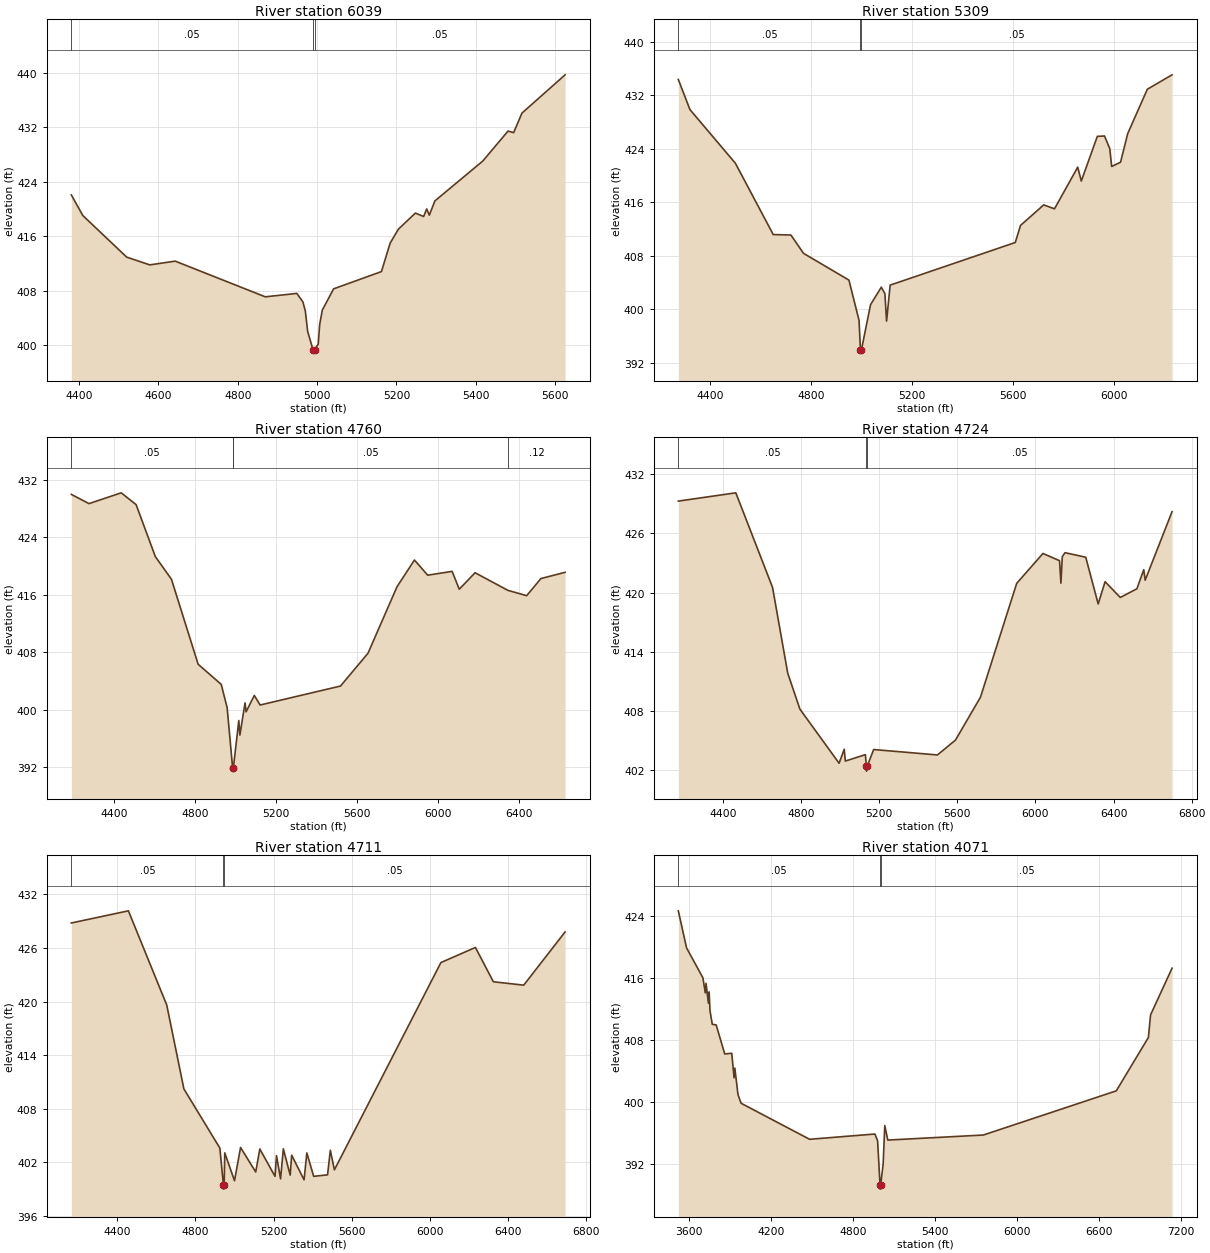
Type RM Length L Ch R = 1,6039,730,730,730
BEGIN DESCRIPTION:
Big Bushy Creek Trib 8 4.0
END DESCRIPTION:
XS GIS Cut Line= 3
      2621015.66      6912871.05      2620695.80      6912340.27
      2620286.47      6911867.57
#Sta/Elev= 30
  4380.3  422.06  4409.1  419.05  4519.8  412.95  4578.0  411.81  4642.1  412.36
  4869.3  407.13  4948.9  407.63  4964.1  406.39  4970.3  405.04  4976.1  402.08
  4989.6  399.38  4989.9  398.88  4993.6  399.38  5002.8  400.21  5006.5  403.08
  5013.1  405.19  5041.6  408.30  5162.2  410.83  5184.1  414.99  5205.0  417.05
  5247.8  419.40  5268.6  418.90  5276.3  420.01  5282.9  419.10  5297.1  421.19
  5417.8  427.03  5481.4  431.42  5495.6  431.19  5516.5  434.05  5625.3  439.66
#Mann=3,-1,0
  4380.3    0.05       0  4989.6    0.04       0  4993.6    0.05       0
Bank Sta=4989.6,4993.6
Exp/Cntr=0.3,0.1

Type RM Length L Ch R = 1,5309,549,549,549
BEGIN DESCRIPTION:
Big Bushy Creek Trib 8 3.0
END DESCRIPTION:
XS GIS Cut Line= 3
      2621310.81      6912937.04      2621346.00      6912211.00
      2620533.81      6911285.15
#Sta/Elev= 30
  4273.1  434.39  4319.2  429.88  4499.4  421.85  4649.6  411.17  4719.7  411.10
  4769.7  408.36  4949.9  404.35  4990.0  398.32  4995.5  393.92  4995.7  393.42
  4999.5  393.92  5035.6  400.67  5078.3  403.29  5092.5  402.33  5099.2  398.21
  5113.4  403.60  5609.7  409.98  5630.6  412.54  5722.6  415.61  5765.3  415.02
  5857.4  421.26  5871.6  419.18  5935.2  425.87  5963.7  425.92  5984.6  424.02
  5992.1  421.36  6027.3  422.00  6055.7  426.28  6133.5  432.92  6231.6  435.08
#Mann=3,-1,0
  4273.1    0.05       0  4995.5    0.04       0  4999.5    0.05       0
Bank Sta=4995.5,4999.5
Exp/Cntr=0.3,0.1

Type RM Length L Ch R = 1,4760,36,36,36
BEGIN DESCRIPTION:
Mapping XS b28c6d1b
END DESCRIPTION:
XS GIS Cut Line= 6
      2621505.26      6912919.68      2621849.01      6912353.71
      2621873.31      6912284.27      2621838.59      6912131.49
      2621130.26      6911575.94      2620683.26      6911115.08
#Sta/Elev= 30
  4190.4  429.96  4277.6  428.68  4436.5  430.18  4510.1  428.54  4605.1  421.31
  4684.6  418.16  4816.3  406.35  4930.3  403.55  4959.5  400.31  4986.4  391.99
  4986.6  391.49  4990.4  391.99  5017.1  398.53  5022.4  396.50  5047.8  400.97
  5053.1  399.74  5093.7  402.01  5122.2  400.68  5519.2  403.32  5654.9  407.88
  5797.9  417.11  5884.2  420.84  5949.6  418.73  6070.2  419.26  6105.4  416.78
  6183.4  419.07  6345.7  416.62  6438.0  415.88  6508.5  418.26  6627.9  419.13
#Mann=4,-1,0
  4190.4    0.05       0  4986.4    0.04       0  4990.4    0.05       0
  6345.7    0.12       0
Bank Sta=4986.4,4990.4
Exp/Cntr=0.3,0.1

Type RM Length L Ch R = 1,4724,13,13,13
BEGIN DESCRIPTION:
Mapping XS e19ca8ef
END DESCRIPTION:
XS GIS Cut Line= 6
      2621522.59      6912933.61      2621824.70      6912457.88
      2621904.56      6912214.83      2621724.01      6911992.60
      2621345.53      6911693.99      2620679.95      6911042.27
#Sta/Elev= 30
  4172.0  429.28  4466.4  430.12  4654.4  420.53  4732.1  411.84  4794.4  408.19
  4995.1  402.70  5021.4  404.12  5027.0  402.92  5129.8  403.57  5134.9  402.40
  5135.2  401.90  5138.9  402.40  5172.2  404.09  5498.5  403.54  5590.9  405.05
  5718.7  409.39  5904.4  420.94  6038.7  423.97  6123.5  423.24  6130.7  420.96
  6137.7  423.65  6151.8  424.05  6257.8  423.59  6321.5  418.85  6356.8  421.11
  6434.7  419.51  6519.6  420.39  6554.9  422.33  6562.0  421.26  6699.7  428.21
#Mann=3,-1,0
  4172.0    0.05       0  5134.9    0.04       0  5138.9    0.05       0
Bank Sta=5134.9,5138.9
Exp/Cntr=0.3,0.1

Type RM Length L Ch R = 1,4711,640,640,640
BEGIN DESCRIPTION:
Mapping XS 56459a64
END DESCRIPTION:
XS GIS Cut Line= 6
      2621536.53      6912937.02      2621904.56      6912364.13
      2621921.92      6912280.80      2621897.62      6912141.91
      2621241.37      6911555.10      2620721.84      6911025.18
#Sta/Elev= 30
  4163.7  428.79  4456.1  430.15  4652.6  419.61  4740.5  410.22  4924.8  403.60
  4943.0  399.50  4943.3  399.00  4947.0  399.50  4950.0  403.06  5000.0  399.94
  5031.0  403.66  5108.8  400.92  5129.7  403.49  5207.6  400.43  5215.2  402.74
  5236.1  400.15  5250.3  403.51  5285.4  400.57  5292.9  402.80  5356.5  400.04
  5370.7  403.05  5405.8  400.43  5476.9  400.60  5491.1  403.35  5512.1  401.16
  6058.0  424.36  6234.9  426.05  6326.8  422.21  6482.4  421.83  6694.5  427.79
#Mann=3,-1,0
  4163.7    0.05       0  4943.0    0.04       0  4947.0    0.05       0
Bank Sta=4943,4947
Exp/Cntr=0.3,0.1

Type RM Length L Ch R = 1,4071,0,0,0
BEGIN DESCRIPTION:
Big Bushy Creek Trib 8 2.0
END DESCRIPTION:
XS GIS Cut Line= 5
      2621596.41      6912951.80      2622520.88      6912517.78
      2622508.42      6912052.47      2622269.15      6911562.92
      2620901.97      6910768.65
#Sta/Elev= 30
  3521.3  424.69  3581.8  419.90  3701.4  416.04  3718.7  414.10  3724.2  415.33
  3741.5  412.78  3747.0  414.23  3752.8  411.85  3769.8  410.05  3798.2  409.97
  3861.1  406.22  3912.2  406.31  3929.5  403.14  3935.0  404.39  3957.9  400.98
  3980.7  399.86  4482.0  395.21  4959.5  395.89  4979.5  395.02  4997.5  389.28
  4997.8  388.78  5001.5  389.28  5020.1  392.01  5032.0  396.98  5054.2  395.11
  5753.2  395.76  6725.9  401.46  6961.0  408.35  6976.7  411.26  7134.1  417.29
#Mann=3,-1,0
  3521.3    0.05       0  4997.5    0.03       0  5001.5    0.05       0
Bank Sta=4997.5,5001.5
Exp/Cntr=0.3,0.1

Chan Stop Cuts=-1