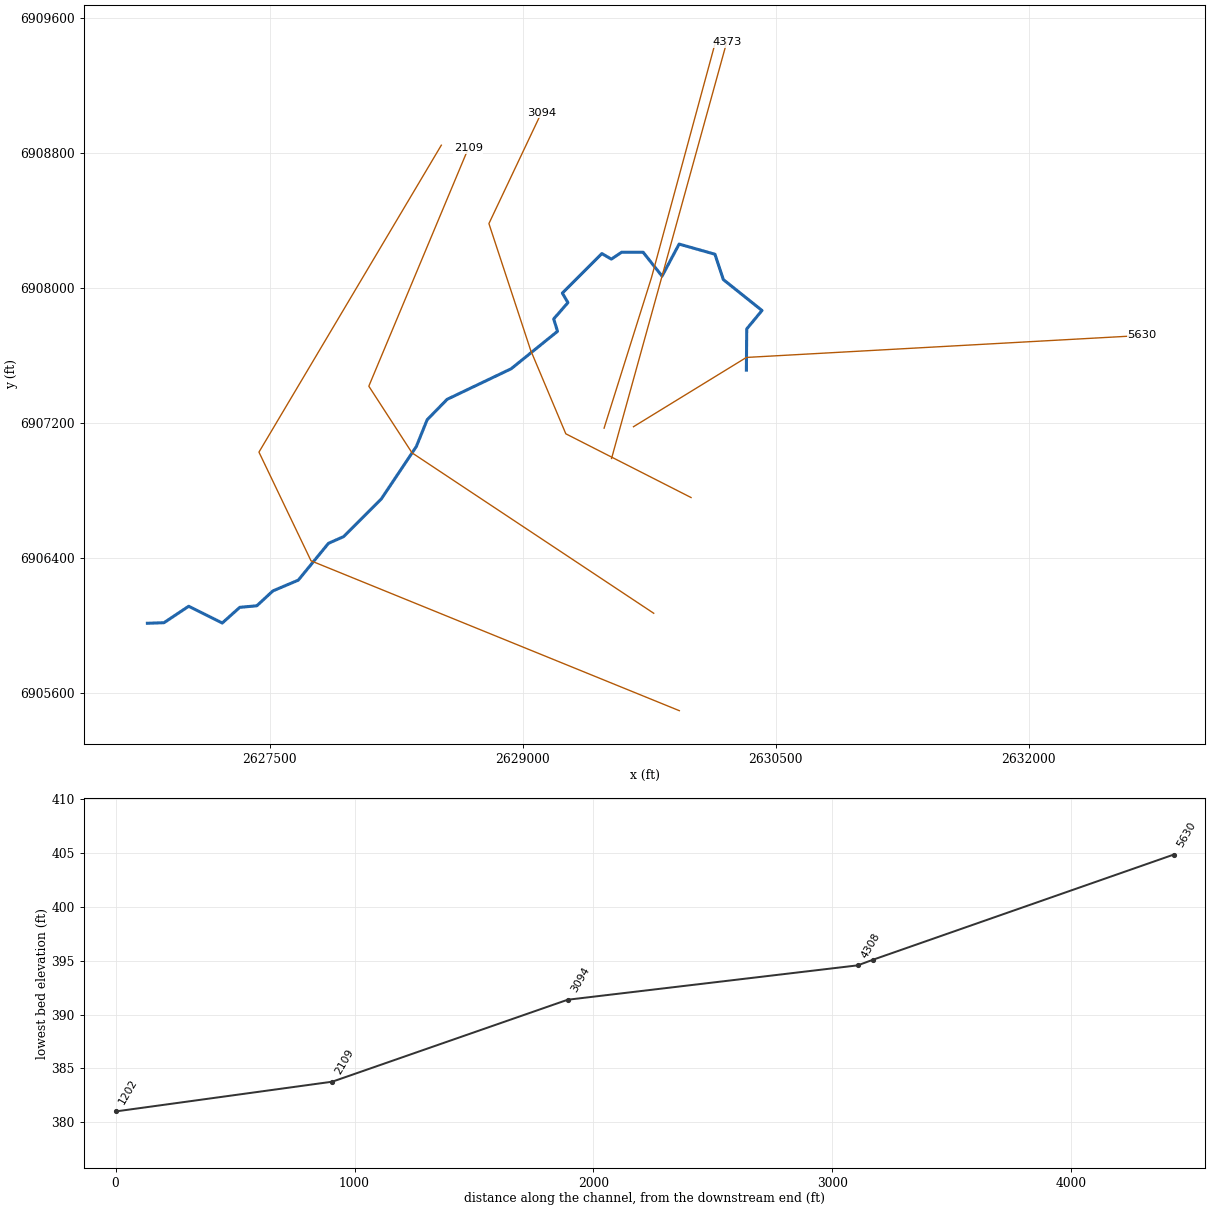
--- Big Bushy Creek Trib 9.prj (project) ---

Proj Title=Big Bushy Creek Trib 9 Base Level Engineering
Current Plan=p01
Default Exp/Contr=0.3,0.1
English Units
Geom File=g01
Flow File=f01
Plan File=p01
BEGIN DESCRIPTION:
Big Bushy Creek Trib 9
END DESCRIPTION:

--- Big Bushy Creek Trib 9.p01 (plan) ---

Plan Title=Multiple Run
Short Identifier=Multiple
Geom File=g01
Flow File=f01
Subcritical Flow
K Sum by GR= 0
Std Step Tol= 0.01
Critical Tol= 0.01
Num of Std Step Trials= 20
Max Error Tol= 0.3
Flow Tol Ratio= 0.001
Split Flow NTrial= 30
Split Flow Tol= 0.02
Split Flow Ratio= 0.02
Log Output Level= 0
Friction Slope Method= 1
Unsteady Friction Slope Method= 2
Unsteady Bridges Friction Slope Method= 1
Parabolic Critical Depth
Global Vel Dist=  1 , 1 , 1
Global Log Level= 0
CheckData=True
Encroach Param= -1, 0, 0, 0
BEGIN DESCRIPTION:
Multiple Run
END DESCRIPTION:

--- Big Bushy Creek Trib 9.f01 (steady flow) ---

Flow Title=Multiple
Number of Profiles=7
Profile Names=10-year,25-year,50-year,1pct_min,100-year,1pct_plu,500-year
River Rch & RM= Big Bushy Creek ,Reach-1,5630
     539     718     861     512    1021    2038    1438
Boundary for River Rch & Prof#=Big Bushy Creek ,Reach-1,1
Up Type=0
Dn Type=3
Dn Slope=0.005
Boundary for River Rch & Prof#=Big Bushy Creek ,Reach-1,2
Up Type=0
Dn Type=3
Dn Slope=0.005
Boundary for River Rch & Prof#=Big Bushy Creek ,Reach-1,3
Up Type=0
Dn Type=3
Dn Slope=0.005
Boundary for River Rch & Prof#=Big Bushy Creek ,Reach-1,4
Up Type=0
Dn Type=3
Dn Slope=0.005
Boundary for River Rch & Prof#=Big Bushy Creek ,Reach-1,5
Up Type=0
Dn Type=3
Dn Slope=0.005
Boundary for River Rch & Prof#=Big Bushy Creek ,Reach-1,6
Up Type=0
Dn Type=3
Dn Slope=0.005
Boundary for River Rch & Prof#=Big Bushy Creek ,Reach-1,7
Up Type=0
Dn Type=3
Dn Slope=0.005

--- Big Bushy Creek Trib 9.g01 (geometry) ---

Geom Title=Existing Conditions

River Reach=Big Bushy Creek ,Reach-1
Reach XY= 30
      2630326.00      6907511.00      2630328.07      6907755.15
      2630418.47      6907864.57      2630189.40      6908047.67
      2630139.72      6908197.77      2629927.39      6908257.97
      2629826.23      6908067.97      2629714.17      6908209.39
      2629586.45      6908209.64      2629525.90      6908168.81
      2629469.33      6908201.70      2629235.30      6907967.67
      2629268.41      6907911.00      2629184.03      6907814.33
      2629206.64      6907740.96      2628932.06      6907519.14
      2628552.53      6907337.99      2628434.14      6907217.06
      2628370.15      6907058.71      2628162.37      6906747.79
      2627939.21      6906524.63      2627849.18      6906484.70
      2627670.39      6906266.59      2627519.95      6906202.84
      2627424.50      6906114.63      2627323.58      6906105.46
      2627219.95      6906012.59      2627020.96      6906111.87
      2626874.59      6906014.39      2626776.00      6906011.00

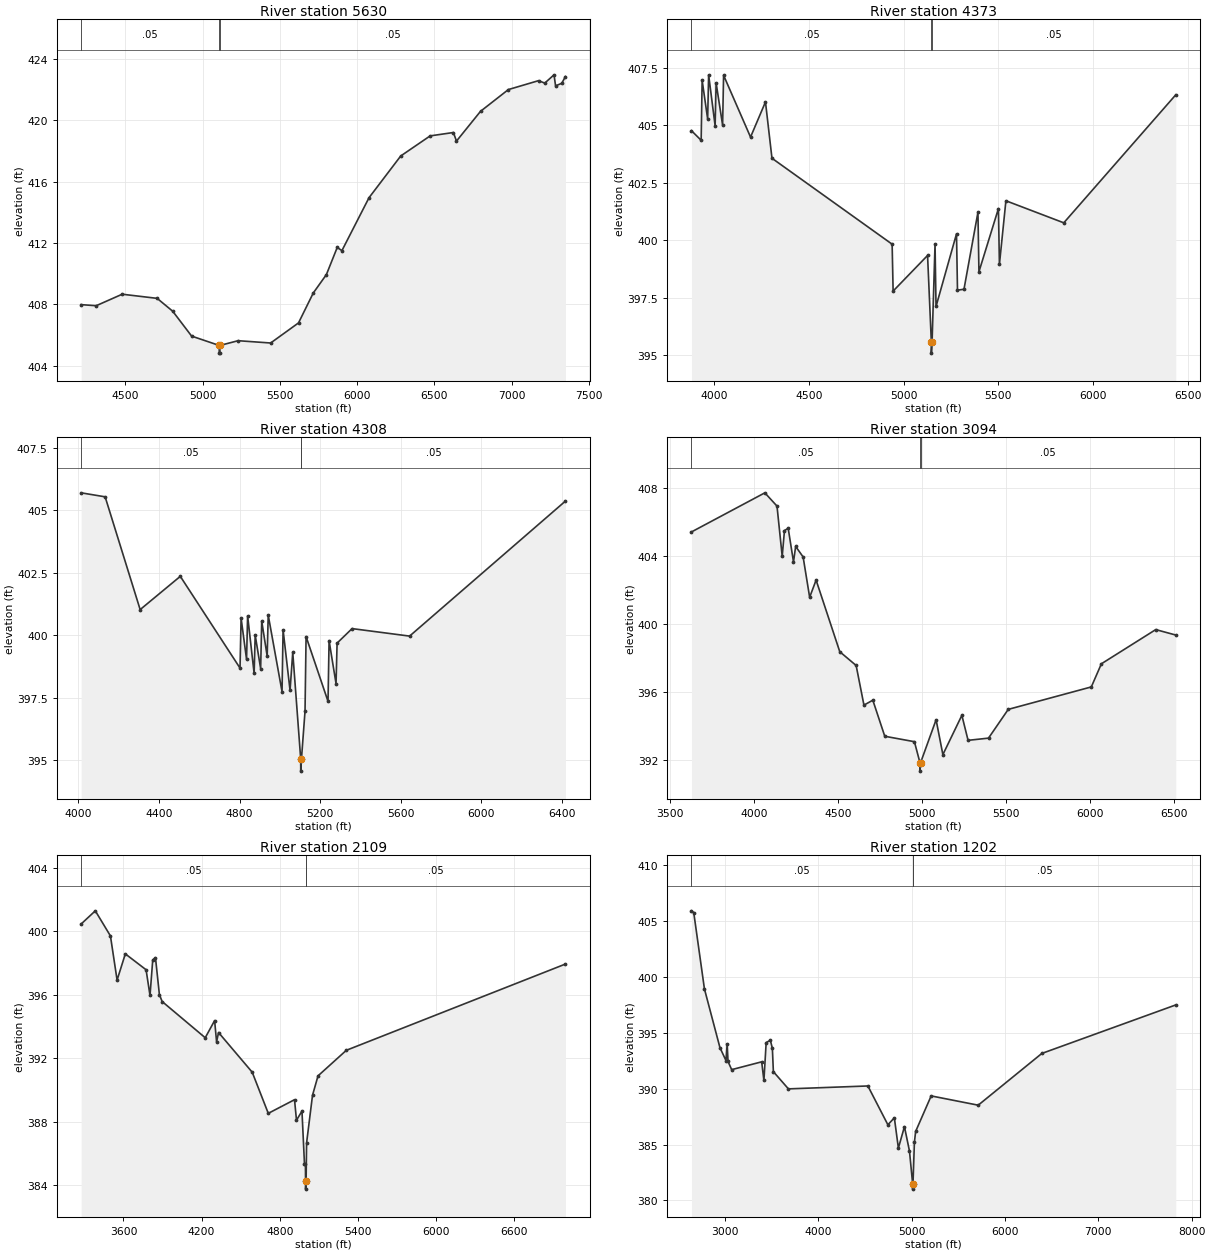
Type RM Length L Ch R = 1,5630,1257,1257,1257
BEGIN DESCRIPTION:
Big Bushy Creek Trib 9 4.0
END DESCRIPTION:
XS GIS Cut Line= 3
      2629656.88      6907175.71      2630325.97      6907586.25
      2632669.66      6907716.46
#Sta/Elev= 30
  4215.0  407.99  4312.4  407.92  4480.6  408.67  4706.7  408.40  4807.4  407.56
  4929.6  405.94  5108.2  405.33  5108.4  404.83  5111.9  404.83  5112.2  405.33
  5230.4  405.64  5440.7  405.49  5621.0  406.80  5716.4  408.75  5801.3  409.95
  5871.4  411.72  5901.6  411.51  6076.9  414.96  6282.0  417.68  6472.3  418.99
  6622.7  419.21  6642.6  418.65  6798.0  420.59  6978.3  422.01  7173.4  422.59
  7213.4  422.43  7273.5  422.97  7283.5  422.25  7323.6  422.42  7347.3  422.86
#Mann=3,-1,0
  4215.0    0.05       0  5108.2    0.03       0  5112.2    0.05       0
Bank Sta=5108.2,5112.2
Exp/Cntr=0.3,0.1

Type RM Length L Ch R = 1,4373,65,65,65
BEGIN DESCRIPTION:
Big Bushy Creek Trib 9 3.0
END DESCRIPTION:
XS GIS Cut Line= 3
      2629526.99      6906987.65      2629826.23      6908067.97
      2630209.28      6909453.80
#Sta/Elev= 30
  3879.0  404.77  3930.3  404.35  3935.5  406.96  3964.6  405.28  3969.8  407.20
  4004.1  404.98  4009.3  406.85  4043.6  405.01  4048.8  407.18  4191.2  404.49
  4270.1  406.02  4304.4  403.57  4939.3  399.83  4944.5  397.79  5126.5  399.34
  5146.4  395.59  5146.6  395.09  5150.4  395.59  5166.0  399.84  5171.2  397.12
  5279.4  400.28  5284.6  397.83  5318.9  397.87  5392.7  401.22  5397.9  398.63
  5500.9  401.38  5506.1  398.95  5540.4  401.72  5846.2  400.76  6437.8  406.33
#Mann=3,-1,0
  3879.0    0.05       0  5146.4    0.03       0  5150.4    0.05       0
Bank Sta=5146.4,5150.4
Exp/Cntr=0.3,0.1

Type RM Length L Ch R = 1,4308,1214,1214,1214
BEGIN DESCRIPTION:
Big Bushy Creek Trib 9 2.0
END DESCRIPTION:
XS GIS Cut Line= 3
      2629482.72      6907167.34      2629763.97      6908060.56
      2630148.85      6909477.87
#Sta/Elev= 30
  4013.3  405.69  4132.5  405.53  4306.4  401.02  4505.8  402.35  4802.4  398.68
  4807.7  400.68  4834.8  399.03  4840.1  400.77  4872.4  398.47  4877.7  400.00
  4904.8  398.66  4910.1  400.56  4937.2  399.16  4942.4  400.80  5011.0  397.74
  5016.2  400.21  5050.8  397.79  5064.2  399.31  5103.6  395.06  5103.9  394.56
  5107.6  395.06  5125.2  396.96  5130.4  399.94  5239.4  397.35  5244.6  399.78
  5279.2  398.06  5284.4  399.68  5358.8  400.26  5644.5  399.96  6418.4  405.36
#Mann=3,-1,0
  4013.3    0.05       0  5103.6    0.03       0  5107.6    0.05       0
Bank Sta=5103.6,5107.6
Exp/Cntr=0.3,0.1

Type RM Length L Ch R = 1,3094,985,985,985
BEGIN DESCRIPTION:
Mapping XS f046952e
END DESCRIPTION:
XS GIS Cut Line= 5
      2629998.10      6906756.15      2629255.90      6907133.76
      2629047.56      6907628.55      2628800.17      6908379.42
      2629111.10      6909035.83
#Sta/Elev= 30
  3626.8  405.43  4064.3  407.73  4136.7  406.95  4167.7  404.00  4181.2  405.51
  4203.4  405.65  4235.0  403.67  4247.9  404.58  4292.4  403.96  4331.3  401.59
  4369.7  402.60  4510.8  398.39  4608.4  397.58  4654.9  395.25  4707.8  395.54
  4779.0  393.42  4955.7  393.10  4988.6  391.87  4988.8  391.37  4992.6  391.87
  5084.9  394.39  5125.3  392.34  5238.5  394.65  5275.5  393.18  5397.3  393.31
  5514.9  395.00  6010.0  396.32  6070.1  397.68  6394.0  399.69  6513.3  399.37
#Mann=3,-1,0
  3626.8    0.05       0  4988.6    0.03       0  4992.6    0.05       0
Bank Sta=4988.6,4992.6
Exp/Cntr=0.3,0.1

Type RM Length L Ch R = 1,2109,907,907,907
BEGIN DESCRIPTION:
Mapping XS 7079952c
END DESCRIPTION:
XS GIS Cut Line= 4
      2629776.71      6906070.40      2628344.44      6907020.91
      2628088.36      6907415.88      2628678.52      6908826.19
#Sta/Elev= 30
  3275.1  400.46  3384.0  401.29  3500.1  399.71  3551.2  396.93  3614.4  398.58
  3773.8  397.58  3803.9  395.96  3824.9  398.20  3845.9  398.34  3876.0  396.02
  3897.1  395.58  4227.9  393.30  4300.0  394.38  4315.1  393.04  4330.1  393.63
  4588.7  391.13  4712.0  388.54  4913.5  389.40  4928.6  388.11  4970.7  388.68
  4990.1  385.33  4997.1  385.33  4998.3  384.27  4998.5  383.77  5002.3  384.27
  5006.2  386.68  5051.7  389.68  5093.9  390.90  5311.4  392.51  6993.6  397.94
#Mann=3,-1,0
  3275.1    0.05       0  4998.3    0.03       0  5002.3    0.05       0
Bank Sta=4998.3,5002.3
Exp/Cntr=0.3,0.1

Type RM Length L Ch R = 1,1202,0,0,0
BEGIN DESCRIPTION:
Big Bushy Creek Trib 9 1.0
END DESCRIPTION:
XS GIS Cut Line= 4
      2629928.65      6905493.13      2627745.93      6906381.02
      2627437.32      6907025.25      2628518.05      6908843.83
#Sta/Elev= 30
  2643.6  405.91  2668.1  405.76  2782.7  398.92  2948.7  393.67  3013.5  392.51
  3026.2  394.01  3035.1  392.43  3074.4  391.70  3395.5  392.40  3419.6  390.73
  3443.7  394.12  3488.5  394.33  3510.1  393.61  3520.9  391.52  3681.8  389.98
  4532.9  390.24  4747.0  386.77  4816.4  387.39  4859.6  384.68  4924.4  386.60
  4978.3  384.42  5012.0  381.51  5012.3  381.01  5016.0  381.51  5031.1  385.20
  5044.3  386.17  5210.6  389.35  5714.3  388.52  6395.7  393.15  7829.8  397.49
#Mann=3,-1,0
  2643.6    0.05       0  5012.0    0.03       0  5016.0    0.05       0
Bank Sta=5012,5016
Exp/Cntr=0.3,0.1

Chan Stop Cuts=-1