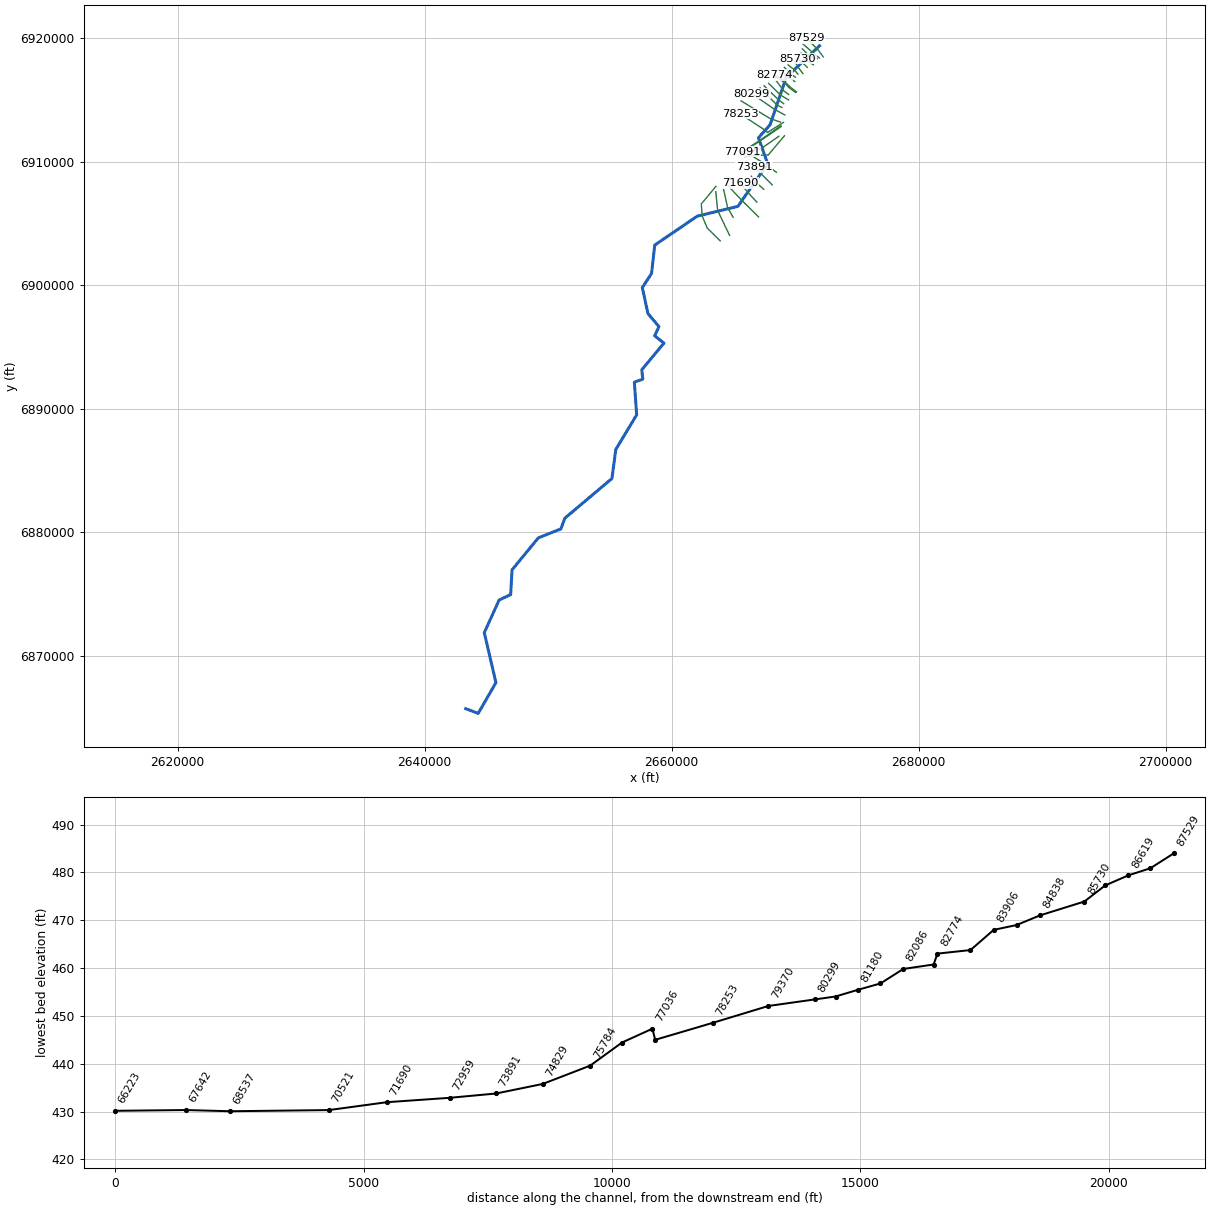
--- Big Cottonwood Creek.prj (project) ---

Proj Title=Big Cottonwood Creek Base Level Engineering
Current Plan=p01
Default Exp/Contr=0.3,0.1
English Units
Geom File=g01
Flow File=f01
Plan File=p01
Y Axis Title=Elevation
X Axis Title(PF)=Main Channel Distance
X Axis Title(XS)=Station
BEGIN DESCRIPTION:
Big Cottonwood Creek
END DESCRIPTION:
DSS Export Rating Curves= 0
DSS Export Rating Curve Sorted= 0
DSS Export Volume Flow Curves= 0
DXF OffsetX= 0
DXF OffsetY= 0
DXF ScaleX= 1
DXF ScaleY= 10

--- Big Cottonwood Creek.p01 (plan) ---

Plan Title=Multiple Run
Short Identifier=Multiple
Geom File=g01
Flow File=f01
Subcritical Flow
K Sum by GR= 0
Std Step Tol= 0.01
Critical Tol= 0.01
Num of Std Step Trials= 20
Max Error Tol= 0.3
Flow Tol Ratio= 0.001
Split Flow NTrial= 30
Split Flow Tol= 0.02
Split Flow Ratio= 0.02
Log Output Level= 0
Friction Slope Method= 1
Unsteady Friction Slope Method= 2
Unsteady Bridges Friction Slope Method= 1
Parabolic Critical Depth
Global Vel Dist=  1 , 1 , 1
Global Log Level= 0
CheckData=True
Encroach Param= -1, 0, 0, 0
BEGIN DESCRIPTION:
Multiple Run
END DESCRIPTION:

--- Big Cottonwood Creek.f01 (steady flow) ---

Flow Title=Multiple
Program Version=4.10
Number of Profiles= 7
Profile Names=10-year,25-year,50-year,1pct_min,100-year,1pct_plu,500-year
River Rch & RM=Big Cottonwood C,Reach-1         ,87529
     501     668     803     480     957    1910    1357
River Rch & RM=Big Cottonwood C,Reach-1         ,86619
     706     959    1166     704    1404    2801    2033
River Rch & RM=Big Cottonwood C,Reach-1         ,82086
    1017    1405    1727    1051    2097    4183    3093
River Rch & RM=Big Cottonwood C,Reach-1         ,74829
    1789    2532    3161    1949    3889    7760    5897
River Rch & RM=Big Cottonwood C,Reach-1         ,65337
    1796    2537    3163    1947    3884    7750    5868
River Rch & RM=Big Cottonwood C,Reach-1         ,63510
    2518    3618    4564    2840    5667   11308    8755
River Rch & RM=Big Cottonwood C,Reach-1         ,59661
    2706    3896    4921    3066    6118   12206    9470
River Rch & RM=Big Cottonwood C,Reach-1         ,54785
    2763    3974    5015    3122    6229   12428    9622
River Rch & RM=Big Cottonwood C,Reach-1         ,52319
    2907    4184    5283    3289    6563   13095   10144
River Rch & RM=Big Cottonwood C,Reach-1         ,46163
    2990    4296    5418    3369    6722   13412   10361
River Rch & RM=Big Cottonwood C,Reach-1         ,38629
    3090    4437    5593    3475    6934   13835   10673
River Rch & RM=Big Cottonwood C,Reach-1         ,33255
    3646    5269    6672    4162    8303   16568   12882
River Rch & RM=Big Cottonwood C,Reach-1         ,29593
    3688    5326    6741    4203    8385   16731   12995
River Rch & RM=Big Cottonwood C,Reach-1         ,26962
    3703    5340    6753    4205    8391   16742   12976
River Rch & RM=Big Cottonwood C,Reach-1         ,24005
    3903    5636    7131    4444    8867   17691   13728
River Rch & RM=Big Cottonwood C,Reach-1         ,16384
    3879    5597    7078    4409    8797   17551   13605
River Rch & RM=Big Cottonwood C,Reach-1         ,14818
    4940    7175    9115    5700   11372   22690   17724
Boundary for River Rch & Prof#=Big Cottonwood C,Reach-1         , 1
Up Type= 0
Dn Type= 3
Dn Slope=0.0002
Boundary for River Rch & Prof#=Big Cottonwood C,Reach-1         , 2
Up Type= 0
Dn Type= 3
Dn Slope=0.0002
Boundary for River Rch & Prof#=Big Cottonwood C,Reach-1         , 3
Up Type= 0
Dn Type= 3
Dn Slope=0.0002
Boundary for River Rch & Prof#=Big Cottonwood C,Reach-1         , 4
Up Type= 0
Dn Type= 3
Dn Slope=0.0002
Boundary for River Rch & Prof#=Big Cottonwood C,Reach-1         , 5
Up Type= 0
Dn Type= 3
Dn Slope=0.0002
Boundary for River Rch & Prof#=Big Cottonwood C,Reach-1         , 6
Up Type= 0
Dn Type= 3
Dn Slope=0.0002
Boundary for River Rch & Prof#=Big Cottonwood C,Reach-1         , 7
Up Type= 0
Dn Type= 3
Dn Slope=0.0002
DSS Import GetInterval= 0
DSS Import GetPeak= 0
DSS Import FillOption= 0

--- Big Cottonwood Creek.g01 (geometry) ---

Geom Title=Existing Conditions
Program Version=4.10

River Reach=Big Cottonwood C,Reach-1
Reach XY= 30
        2671976.        6919411.      2669281.46      6916863.66
      2667972.46      6913012.46       2667027.1      6911950.45
      2667772.86      6909862.64      2665362.55      6906397.35
      2662077.47      6905607.45      2658631.83       6903263.3
      2658374.04      6900966.65      2657625.88      6899826.42
      2658078.96      6897719.32      2658968.49       6896664.1
       2658629.1      6895912.65      2659374.96      6895321.44
      2657581.09      6893163.86      2657665.96      6892400.89
      2656979.53      6892159.55      2657167.96      6889507.69
      2655479.52      6886709.72      2655166.87      6884354.26
      2651349.11      6881134.98      2651035.43      6880271.05
      2649209.32      6879544.78      2647078.43      6876952.89
      2646967.23       6874954.2      2646028.37      6874503.18
      2644832.97      6871861.24      2645774.37      6867822.85
      2644343.23      6865327.48        2643326.        6865711.

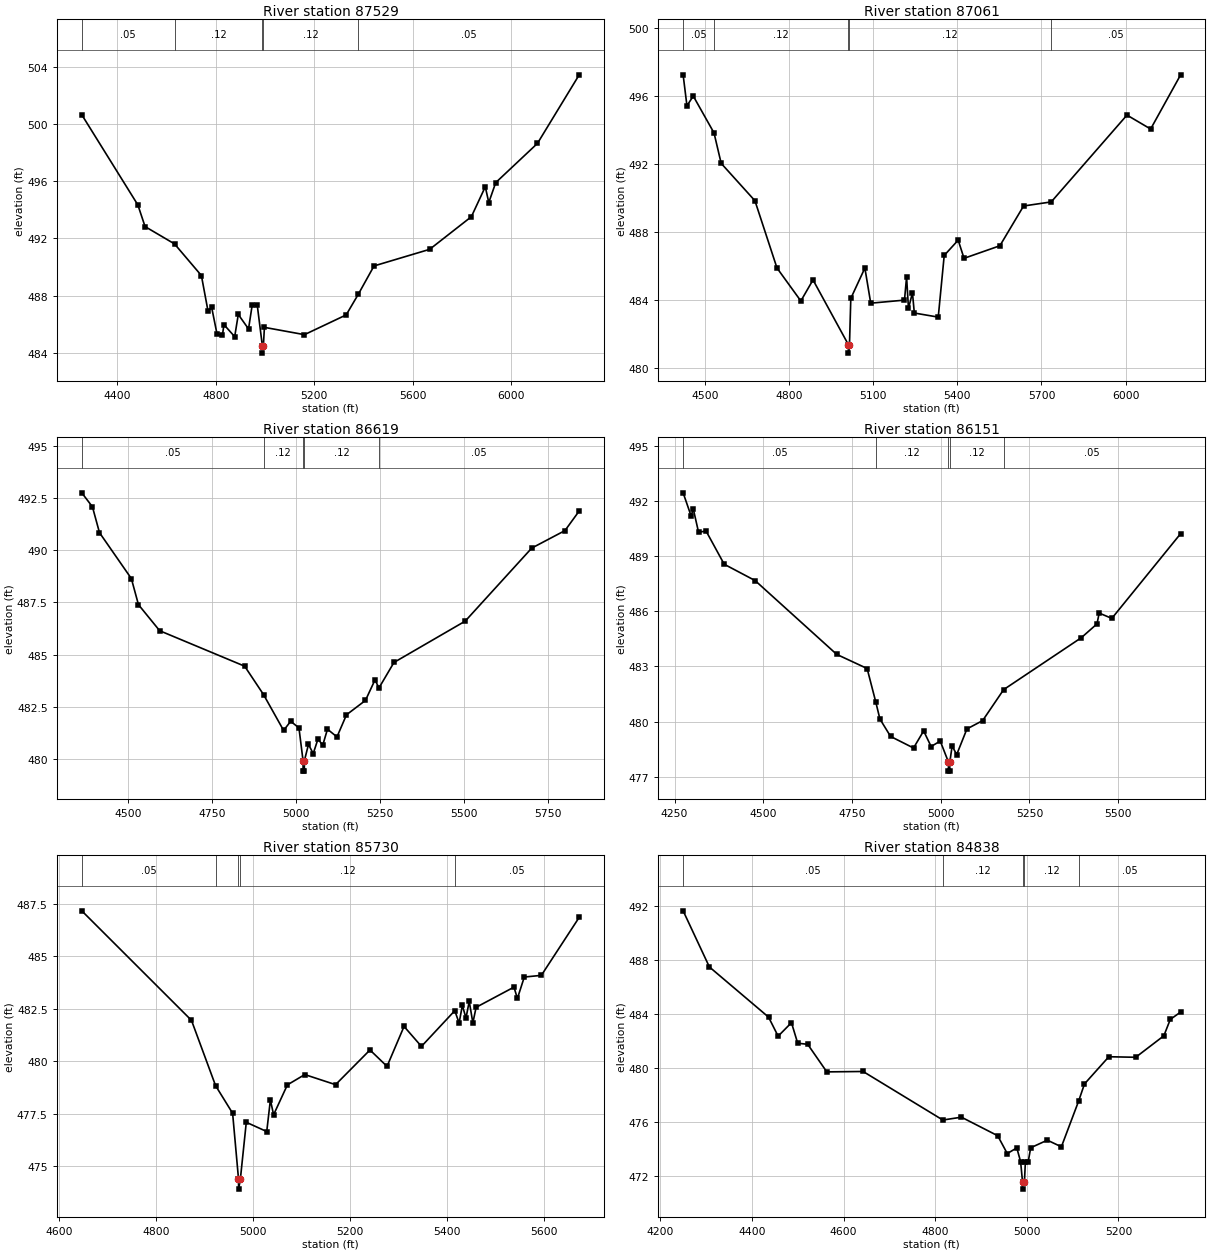
Type RM Length L Ch R = 1 ,87529   ,468,468,468
BEGIN DESCRIPTION:
Big Cottonwood Creek 115.0
END DESCRIPTION:
XS GIS Cut Line= 3
      2672275.98      6918511.03        2671826.        6919111.
      2670925.97      6920011.03
#Sta/Elev= 30
  4254.9  500.64    4483  494.34  4512.2  492.83    4632  491.62  4741.3  489.41
  4768.4  486.91    4783  487.19  4804.9  485.32  4826.7  485.23    4833  485.98
  4876.7  485.14  4891.3  486.69    4933  485.68  4947.6  487.32  4968.4  487.35
  4989.3  484.49  4989.6  483.99  4993.3  484.49  4997.6  485.79  5160.4  485.28
  5330.1  486.66    5379  488.09  5443.3  490.08  5669.5  491.24  5839.2  493.52
  5895.8  495.61    5910  494.51  5938.2   495.9  6107.9  498.64  6277.7  503.43
#Mann= 5 ,-1 , 0
  4254.9     .05       0    4632     .12       0  4989.3     .07       0
  4993.3     .12       0    5379     .05       0
Bank Sta=4989.3,4993.3
XS Rating Curve= 0 ,0
Exp/Cntr=0.3,0.1

Type RM Length L Ch R = 1 ,87061   ,442,442,442
BEGIN DESCRIPTION:
Big Cottonwood Creek 114.0
END DESCRIPTION:
XS GIS Cut Line= 3
        2671976.        6918411.        2671526.        6918761.
      2670625.96      6919561.03
#Sta/Elev= 30
  4421.9  497.27  4435.5  495.45  4458.1  496.02  4532.1  493.85  4557.6  492.06
    4678  489.86  4756.7   485.9  4841.8  483.96  4885.2   485.2  5011.3  481.39
  5011.6  480.89  5015.3  481.39    5020  484.11  5070.2   485.9  5091.1  483.83
  5211.5  484.01    5219  485.38  5225.7  483.52  5239.9  484.44  5246.6  483.25
  5331.9  483.01  5353.2  486.64    5403  487.54  5423.9  486.47  5551.8  487.21
  5636.3  489.55  5734.9  489.79  6005.1   494.9  6089.5  494.08  6196.2  497.26
#Mann= 5 ,-1 , 0
  4421.9     .05       0  4532.1     .12       0  5011.3     .07       0
  5015.3     .12       0  5734.9     .05       0
Bank Sta=5011.3,5015.3
XS Rating Curve= 0 ,0
Exp/Cntr=0.3,0.1

Type RM Length L Ch R = 1 ,86619   ,468,468,468
BEGIN DESCRIPTION:
Big Cottonwood Creek 113.0
END DESCRIPTION:
XS GIS Cut Line= 3
      2671776.04      6918360.99        2671176.        6918561.
      2670576.02      6919160.98
#Sta/Elev= 30
  4362.7  492.75  4394.4  492.08  4415.4  490.84  4510.3  488.64  4531.4  487.39
  4594.6  486.14  4847.6  484.44  4903.8  483.08  4963.6  481.36  4984.7   481.8
  5009.3  481.48  5021.5  479.91  5021.7  479.41  5025.2  479.41  5025.5  479.91
  5037.6  480.69  5051.8  480.25  5065.9  480.95  5080.1  480.65  5094.2  481.42
  5122.5  481.05  5150.8  482.11  5207.3   482.8  5235.6  483.78  5247.6   483.4
  5292.2  484.62  5504.3   486.6  5702.3   490.1  5801.3  490.94  5843.7  491.88
#Mann= 5 ,-1 , 0
  4362.7     .05       0  4903.8     .12       0  5021.5     .07       0
  5025.5     .12       0  5247.6     .05       0
Bank Sta=5021.5,5025.5
XS Rating Curve= 0 ,0
Exp/Cntr=0.3,0.1

Type RM Length L Ch R = 1 ,86151   ,421,421,421
BEGIN DESCRIPTION:
Big Cottonwood Creek 112.0
END DESCRIPTION:
XS GIS Cut Line= 3
      2671475.98      6917861.01        2670876.        6918261.
      2670475.98      6918811.03
#Sta/Elev= 30
  4274.3  492.46  4296.8   491.2  4302.8  491.59  4317.8  490.31  4338.9  490.38
    4390  488.57  4477.1  487.68  4706.9  483.66  4792.6  482.89  4816.9  481.07
  4828.6  480.14  4858.7  479.19  4923.3  478.56  4951.8  479.49  4972.9  478.64
  4998.5  478.94  5021.6   477.8  5021.8   477.3  5025.3   477.3  5025.6   477.8
  5032.1  478.67  5044.9   478.2  5073.8   479.6  5117.9  480.05  5177.2  481.74
  5396.1  484.57  5440.1  485.32  5446.3  485.91  5481.9  485.62  5675.5  490.23
#Mann= 5 ,-1 , 0
  4274.3     .05       0  4816.9     .12       0  5021.6     .07       0
  5025.6     .12       0  5177.2     .05       0
Bank Sta=5021.6,5025.6
XS Rating Curve= 0 ,0
Exp/Cntr=0.3,0.1

Type RM Length L Ch R = 1 ,85730   ,892,892,892
BEGIN DESCRIPTION:
Big Cottonwood Creek 111.0
END DESCRIPTION:
XS GIS Cut Line= 3
      2670976.02      6917660.98        2670726.        6917911.
      2670225.98      6918361.02
#Sta/Elev= 30
    4647  487.16  4873.3  481.95  4923.1  478.84  4958.2  477.53  4970.3  474.42
  4970.6  473.92  4974.3  474.42  4986.4   477.1  5028.6  476.66  5036.1  478.16
  5042.8  477.46  5071.2  478.88  5107.1  479.37  5170.6  478.89  5241.6  480.54
  5276.8  479.76  5311.9  481.66  5347.8  480.71  5416.6  482.41  5425.5  481.82
  5432.2  482.66  5439.7  482.06  5446.4  482.85  5453.9  481.83  5460.6  482.57
  5538.7  483.53  5545.8  482.99    5560  484.01  5595.2  484.09  5673.3  486.85
#Mann= 5 ,-1 , 0
    4647     .05       0  4923.1     .12       0  4970.3     .07       0
  4974.3     .12       0  5416.6     .05       0
Bank Sta=4970.3,4974.3
XS Rating Curve= 0 ,0
Exp/Cntr=0.3,0.1

Type RM Length L Ch R = 1 ,84838   ,469,469,469
BEGIN DESCRIPTION:
Big Cottonwood Creek 110.0
END DESCRIPTION:
XS GIS Cut Line= 3
      2670625.98      6917161.02        2670176.        6917761.
      2670025.99      6918061.02
#Sta/Elev= 30
    4250  491.61  4307.3  487.46  4436.4  483.75  4457.3  482.34  4486.4  483.34
    4500  481.82  4521.8  481.74  4563.5   479.7  4642.7  479.73  4816.7  476.14
  4857.3  476.35  4936.4  474.98  4957.3  473.66  4978.1  474.08  4986.4  473.06
  4990.7  471.53  4990.9  471.03  4994.7  471.53  4996.8  473.02  5002.8  473.02
  5008.4  474.09  5044.7  474.65  5075.4  474.16    5113  477.54  5125.8  478.81
  5178.9  480.82  5237.6  480.78    5299  482.37    5313  483.58  5335.4  484.12
#Mann= 5 ,-1 , 0
    4250     .05       0  4816.7     .12       0  4990.7     .07       0
  4994.7     .12       0    5113     .05       0
Bank Sta=4990.7,4994.7
XS Rating Curve= 0 ,0
Exp/Cntr=0.3,0.1

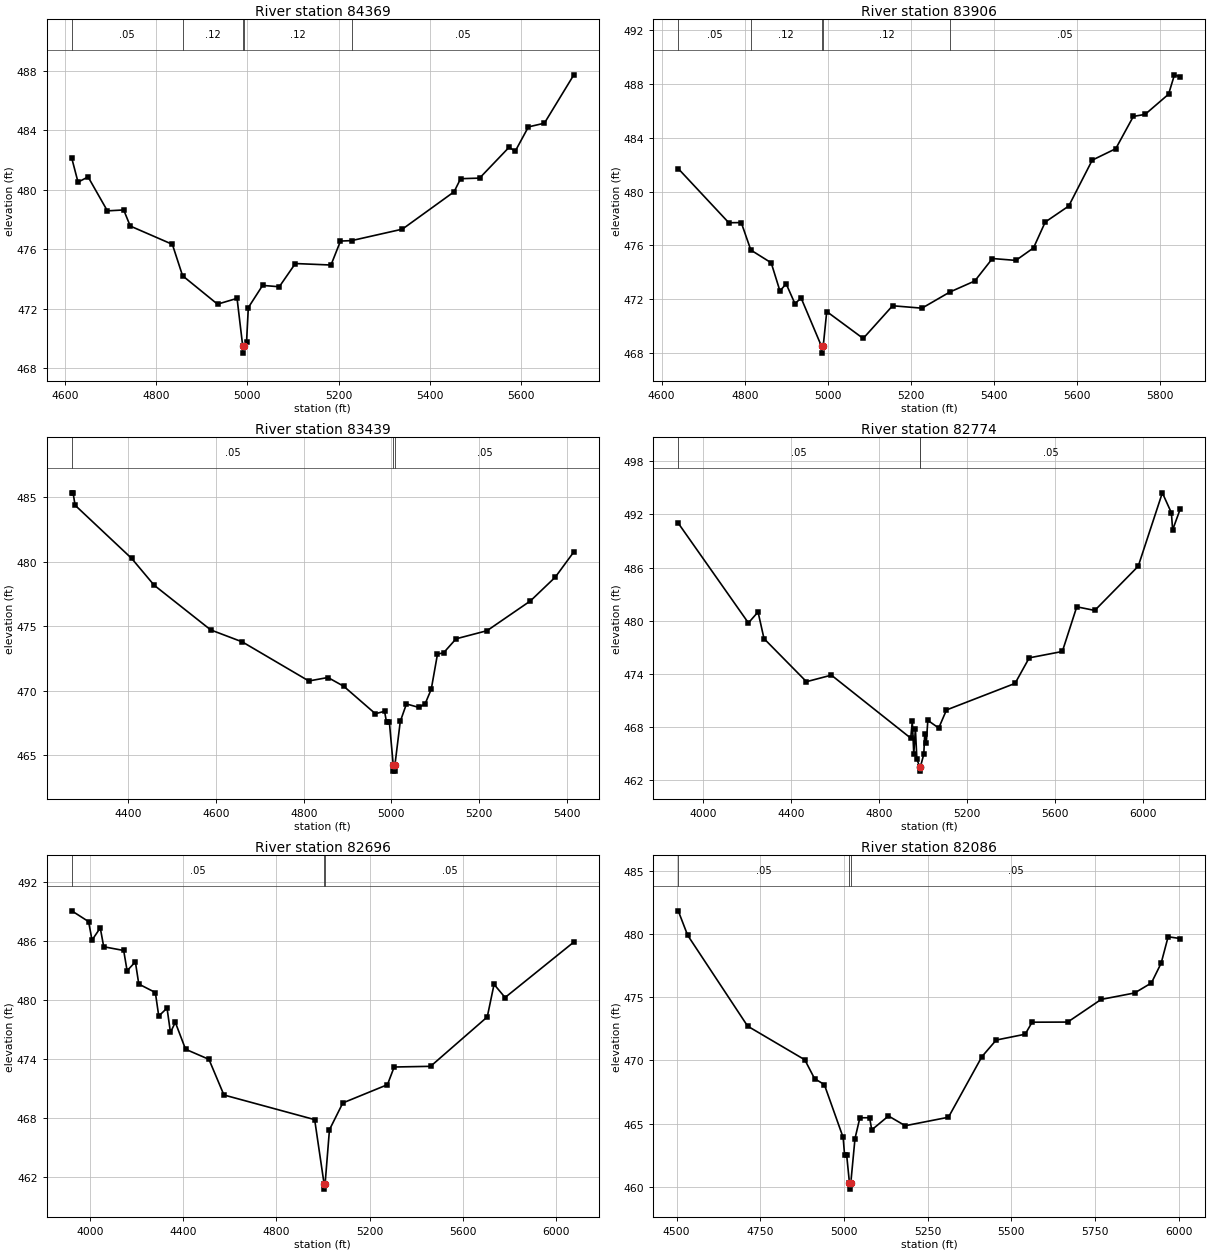
Type RM Length L Ch R = 1 ,84369   ,463,463,463
BEGIN DESCRIPTION:
Big Cottonwood Creek 109.0
END DESCRIPTION:
XS GIS Cut Line= 3
      2670225.99      6917111.01        2669976.        6917411.
      2669426.03      6917860.98
#Sta/Elev= 30
  4614.8  482.12  4628.5  480.51  4650.6  480.86  4692.9  478.58  4728.7  478.64
    4743  477.56  4835.4  476.33  4857.8  474.22  4934.4  472.31  4977.3   472.7
  4989.6  469.52  4989.9  469.02  4993.6  469.52  4998.1  469.77    5002  472.08
  5033.3  473.57  5069.9  473.48  5105.1  475.04  5183.3  474.94  5204.1  476.55
  5228.5  476.58  5339.8  477.35  5453.2  479.86  5467.6  480.74  5509.2  480.78
  5573.8  482.85  5587.4  482.59  5616.2  484.22  5651.3  484.47  5715.9  487.72
#Mann= 5 ,-1 , 0
  4614.8     .05       0  4857.8     .12       0  4989.6     .07       0
  4993.6     .12       0  5228.5     .05       0
Bank Sta=4989.6,4993.6
XS Rating Curve= 0 ,0
Exp/Cntr=0.3,0.1

Type RM Length L Ch R = 1 ,83906   ,467,467,467
BEGIN DESCRIPTION:
Big Cottonwood Creek 108.0
END DESCRIPTION:
XS GIS Cut Line= 3
      2670026.03      6916860.98        2669726.        6917061.
      2669126.01      6917660.99
#Sta/Elev= 30
  4639.9  481.71  4761.6  477.69  4791.7   477.7  4814.7  475.66  4863.8  474.71
  4884.8  472.62  4899.8  473.15  4920.9  471.68  4935.9  472.09    4985   468.5
  4985.2     468    4989   468.5  4997.5  471.09  5085.3  469.09  5156.1  471.52
  5226.8  471.34    5294  472.54    5354  473.36  5396.5  475.03    5453  474.89
  5495.5  475.82  5523.7  477.74  5580.3  478.93  5636.9  482.34  5693.5  483.19
  5735.9  485.59  5764.2  485.74  5820.7  487.24  5834.9  488.68    5849  488.52
#Mann= 5 ,-1 , 0
  4639.9     .05       0  4814.7     .12       0    4985     .07       0
    4989     .12       0    5294     .05       0
Bank Sta=4985,4989
XS Rating Curve= 0 ,0
Exp/Cntr=0.3,0.1

Type RM Length L Ch R = 1 ,83439   ,665,665,665
BEGIN DESCRIPTION:
Big Cottonwood Creek 107.0
END DESCRIPTION:
XS GIS Cut Line= 3
        2669976.        6916511.        2669376.        6916911.
      2669075.98      6917211.02
#Sta/Elev= 30
  4270.9  485.36  4273.9  485.36  4278.4   484.4  4407.6  480.27  4458.7   478.2
  4587.9  474.73    4660   473.8  4811.7  470.77  4855.3  471.04  4891.4  470.36
  4963.5  468.23  4984.5  468.42    4989  467.56  4995.5  467.56  5004.2  464.28
  5004.4  463.78  5007.9  463.78  5008.2  464.28  5020.3  467.63  5034.4  468.99
  5062.7  468.72  5076.9  468.99    5091  470.13  5105.2  472.85  5119.3  472.96
  5147.6  474.04  5218.3  474.67  5317.3  476.98  5373.9  478.82  5416.3  480.78
#Mann= 3 ,-1 , 0
  4270.9     .05       0  5004.2     .03       0  5008.2     .05       0
Bank Sta=5004.2,5008.2
XS Rating Curve= 0 ,0
Exp/Cntr=0.3,0.1

Type RM Length L Ch R = 1 ,82774   ,78,78,78
BEGIN DESCRIPTION:
Mapping XS f722212b
END DESCRIPTION:
XS GIS Cut Line= 6
      2670108.34      6915676.37      2669681.22       6915994.1
      2669254.14      6916389.94       2668978.1      6916671.19
      2668691.64       6916869.1      2668300.99      6917040.99
#Sta/Elev= 30
  3885.9  491.02  4205.1  479.76  4248.9     481    4276  477.99  4469.1  473.13
  4582.5  473.87  4943.5  466.76  4950.5  468.65  4957.3  464.98  4964.6  467.83
  4971.4   464.4  4983.6  463.54  4983.9  463.04  4987.6  463.54  5002.8  464.95
    5007  467.22  5014.2  466.24  5021.2  468.77  5070.7   467.9    5106  469.94
    5418  472.94  5482.3  475.82    5633  476.54  5698.6  481.58  5780.5  481.17
  5978.2  486.16  6087.9  494.44  6129.1  492.18  6134.6  490.25  6169.6  492.64
#Mann= 3 ,-1 , 0
  3885.9     .05       0  4983.6     .04       0  4987.6     .05       0
Bank Sta=4983.6,4987.6
XS Rating Curve= 0 ,0
Exp/Cntr=0.3,0.1

Type RM Length L Ch R = 1 ,82696   ,610,610,610
BEGIN DESCRIPTION:
Mapping XS 5c10e83b
END DESCRIPTION:
XS GIS Cut Line= 5
      2670040.59      6915624.32      2669499.83      6916023.61
      2669225.55      6916321.19      2668768.92      6916702.43
      2668327.02      6916889.95
#Sta/Elev= 30
  3923.1  489.11  3995.2  488.01  4009.9  486.13  4045.3  487.37    4060  485.45
  4145.6  485.07  4160.2  483.01  4195.7  483.91  4210.3  481.65  4281.3  480.79
  4295.9  478.39  4331.4   479.2    4346  476.73  4366.9  477.75  4410.8  475.01
    4511  473.98  4575.2  470.35  4964.1  467.84  5004.7  461.26    5005  460.76
  5008.7  461.26  5027.5  466.81  5084.8  469.54  5276.1   471.4  5304.8   473.2
  5460.9  473.27  5703.8   478.3  5732.9  481.62  5780.2  480.28  6074.9  485.93
#Mann= 3 ,-1 , 0
  3923.1     .05       0  5004.7     .04       0  5008.7     .05       0
Bank Sta=5004.7,5008.7
XS Rating Curve= 0 ,0
Exp/Cntr=0.3,0.1

Type RM Length L Ch R = 1 ,82086   ,459,459,459
BEGIN DESCRIPTION:
Big Cottonwood Creek 104.0
END DESCRIPTION:
XS GIS Cut Line= 3
      2669476.01      6915460.99        2669076.        6915761.
      2668476.01      6916560.99
#Sta/Elev= 30
  4504.8  481.82  4532.9  479.89  4712.1  472.71  4882.9  470.05  4912.1  468.56
  4941.3  468.09  4997.5  463.91  5001.7  462.55  5007.9  462.55  5016.3  460.33
  5016.6  459.83  5020.4  460.33  5032.9  463.83  5047.5  465.47  5076.7  465.47
  5082.9  464.51  5132.9  465.61  5182.9  464.84  5312.1  465.51  5412.1   470.3
  5454.8  471.61  5541.3  472.07  5562.1  473.02  5668.4  473.03  5768.4  474.82
  5868.4  475.33  5918.4  476.12  5947.5  477.68  5968.4  479.77  6004.8  479.63
#Mann= 3 ,-1 , 0
  4504.8     .05       0  5016.3     .03       0  5020.4     .05       0
Bank Sta=5016.3,5020.4
XS Rating Curve= 0 ,0
Exp/Cntr=0.3,0.1

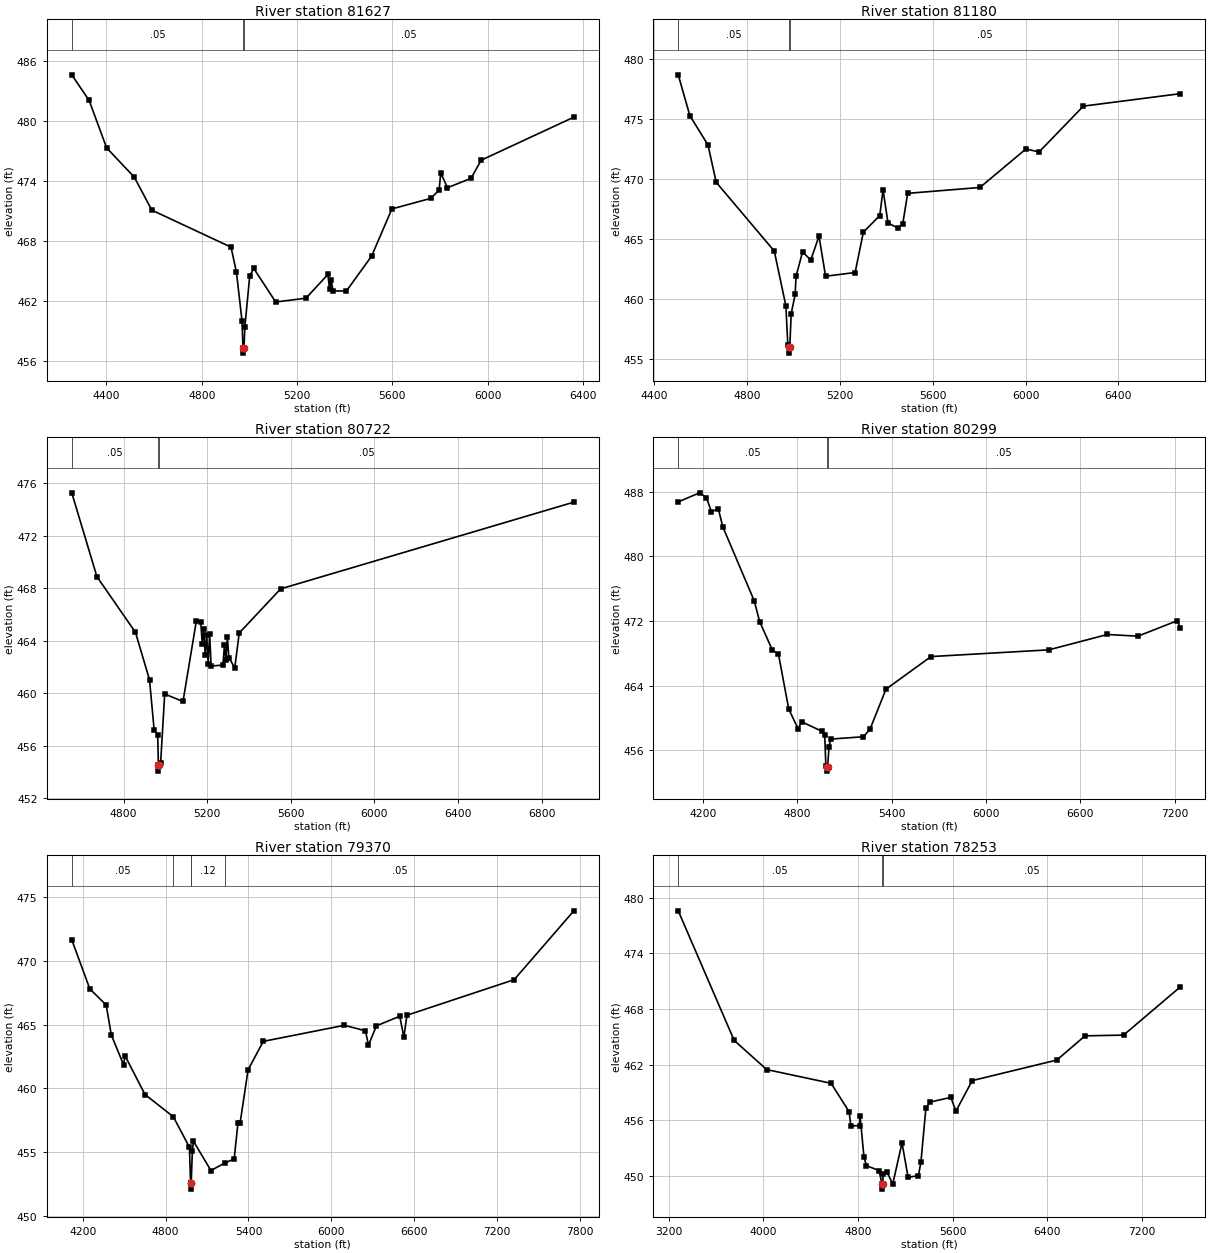
Type RM Length L Ch R = 1 ,81627   ,447,447,447
BEGIN DESCRIPTION:
Big Cottonwood Creek 103.0
END DESCRIPTION:
XS GIS Cut Line= 3
      2669465.31      6915019.25        2668826.        6915411.
      2667851.76      6916356.78
#Sta/Elev= 30
  4254.6  484.61  4327.5  482.05  4400.9  477.31    4517  474.39  4590.5  471.09
  4923.2  467.39  4945.7   464.9  4969.2  460.04  4973.3   457.3  4973.6   456.8
  4977.5   457.3  4981.2  459.41  5001.5  464.48  5018.4  465.27  5110.5  461.91
  5237.8  462.29  5329.7  464.66  5336.8  463.19  5343.8  464.12    5351  463.01
  5407.6  463.01  5513.6  466.51  5598.4  471.21    5761  472.26  5796.5  473.08
  5803.5   474.8  5831.8  473.33  5930.8  474.27  5973.2  476.08  6362.2  480.38
#Mann= 3 ,-1 , 0
  4254.6     .05       0  4973.3     .03       0  4977.5     .05       0
Bank Sta=4973.3,4977.5
XS Rating Curve= 0 ,0
Exp/Cntr=0.3,0.1

Type RM Length L Ch R = 1 ,81180   ,458,458,458
BEGIN DESCRIPTION:
Big Cottonwood Creek 102.0
END DESCRIPTION:
XS GIS Cut Line= 3
      2669075.99      6914711.01        2668676.        6915011.
      2667481.83      6916166.81
#Sta/Elev= 30
  4504.3  478.69  4554.3  475.29  4632.4  472.84  4667.8  469.73  4917.8     464
  4967.8  459.43  4976.2  456.17  4980.3  455.99  4980.6  455.49  4984.6  455.99
  4990.7  458.79  5007.8  460.38  5011.4  461.89  5039.7  463.93  5074.9  463.25
  5110.4  465.24  5138.7   461.9    5266  462.21  5301.3  465.57    5372  466.96
  5386.2   469.1  5407.5  466.34  5449.7  465.92    5471  466.26  5492.2  468.81
  5803.4   469.3  6001.5  472.51  6058.1  472.26  6248.9  476.08  6666.2  477.12
#Mann= 3 ,-1 , 0
  4504.3     .05       0  4980.3     .03       0  4984.6     .05       0
Bank Sta=4980.3,4984.6
XS Rating Curve= 0 ,0
Exp/Cntr=0.3,0.1

Type RM Length L Ch R = 1 ,80722   ,423,423,423
BEGIN DESCRIPTION:
Big Cottonwood Creek 101.0
END DESCRIPTION:
XS GIS Cut Line= 3
      2668926.02      6914410.99        2668526.        6914611.
       2667155.4      6916003.63
#Sta/Elev= 30
  4552.5  475.25  4672.7  468.87  4857.2  464.63  4924.3  461.02  4946.6  457.19
  4963.4  456.81  4966.8  454.57  4967.2  454.07  4971.1  454.57  4977.4  454.67
  4996.9  459.94  5084.5  459.37  5148.2  465.49  5169.4  465.41  5176.5  463.76
  5183.5  464.89  5190.7   462.9  5197.7  464.44  5204.8  462.26  5211.8  464.52
    5219  462.07  5275.5  462.14  5282.6  463.64  5289.7   462.5  5296.7  464.29
  5303.8  462.71  5332.1  461.93  5353.3  464.58  5551.3  467.94  6953.7  474.54
#Mann= 3 ,-1 , 0
  4552.5     .05       0  4966.8     .05       0  4971.1     .05       0
Bank Sta=4966.8,4971.1
XS Rating Curve= 0 ,0
Exp/Cntr=0.3,0.1

Type RM Length L Ch R = 1 ,80299   ,929,929,929
BEGIN DESCRIPTION:
Big Cottonwood Creek 100.0
END DESCRIPTION:
XS GIS Cut Line= 3
       2669170.8       6913801.4        2668326.        6914261.
      2666489.78      6915529.68
#Sta/Elev= 30
  4042.1  486.73  4177.9  487.85  4221.6  487.25  4252.5  485.54  4297.6  485.84
  4325.1  483.67  4525.7  474.49  4559.8  471.94  4641.4  468.39  4679.4  467.94
    4745  461.12  4804.8  458.67  4826.7  459.55  4958.3  458.36  4973.9  457.87
  4981.1  454.06  4987.9  453.95  4988.3  453.45  4992.3  453.95    5001  456.43
  5011.3  457.41  5220.1   457.7    5262  458.63  5363.4  463.58    5650  467.61
    6399  468.44  6772.1  470.34  6966.1  470.13  7216.8  472.05  7235.7  471.12
#Mann= 3 ,-1 , 0
  4042.1     .05       0  4987.9     .03       0  4992.3     .05       0
Bank Sta=4987.9,4992.3
XS Rating Curve= 0 ,0
Exp/Cntr=0.3,0.1

Type RM Length L Ch R = 1 ,79370   ,1117,1117,1117
BEGIN DESCRIPTION:
Big Cottonwood Creek 98.0
END DESCRIPTION:
XS GIS Cut Line= 3
      2668811.62       6913222.4        2667976.        6913511.
      2665623.96        6914942.
#Sta/Elev= 30
  4119.8  471.65  4250.4   467.8  4369.1  466.53  4406.3  464.18  4494.6  461.86
  4506.6  462.53  4650.5  459.51  4855.3  457.77  4972.1  455.38  4980.4  452.59
  4980.9  452.09    4985  452.59  4993.5  455.11  5001.2  455.85  5127.8  453.55
  5230.4  454.15  5296.3  454.45  5323.5  457.26    5339  457.26  5397.1  461.45
  5507.2  463.68  6094.6  464.94  6247.6  464.51    6269  463.38  6327.1   464.9
  6495.6  465.65  6525.5  464.02  6547.9  465.73  7324.8  468.52    7757  473.92
#Mann= 5 ,-1 , 0
  4119.8     .05       0  4855.3     .12       0  4980.4     .07       0
    4985     .12       0  5230.4     .05       0
Bank Sta=4980.4,4985
XS Rating Curve= 0 ,0
Exp/Cntr=0.3,0.1

Type RM Length L Ch R = 1 ,78253   ,1162,1162,1162
BEGIN DESCRIPTION:
Mapping XS 8c875627
END DESCRIPTION:
XS GIS Cut Line= 4
      2669056.26      6913202.46      2667754.14      6912384.73
      2667639.55      6912520.15      2665524.97      6913905.56
#Sta/Elev= 30
  3282.2   478.6  3754.8  464.62    4030  461.47  4574.2  459.99  4726.2  456.92
  4741.5  455.38  4814.6  455.43  4818.6  456.49  4851.6  452.07  4872.5   451.1
  4979.1  450.58  5005.3  449.07  5005.8  448.57    5010  449.07  5013.6  450.21
  5043.8  450.46  5095.1  449.13  5173.4  453.56  5224.7  449.84  5312.2  450.03
  5333.3   451.5  5375.4  457.35  5411.6  457.97  5586.5  458.47  5628.7  456.98
  5766.6  460.28  6481.9   462.5  6720.1  465.11  7045.7  465.19  7525.2  470.39
#Mann= 3 ,-1 , 0
  3282.2     .05       0  5005.3     .03       0    5010     .05       0
Bank Sta=5005.3,5010
XS Rating Curve= 0 ,0
Exp/Cntr=0.3,0.1

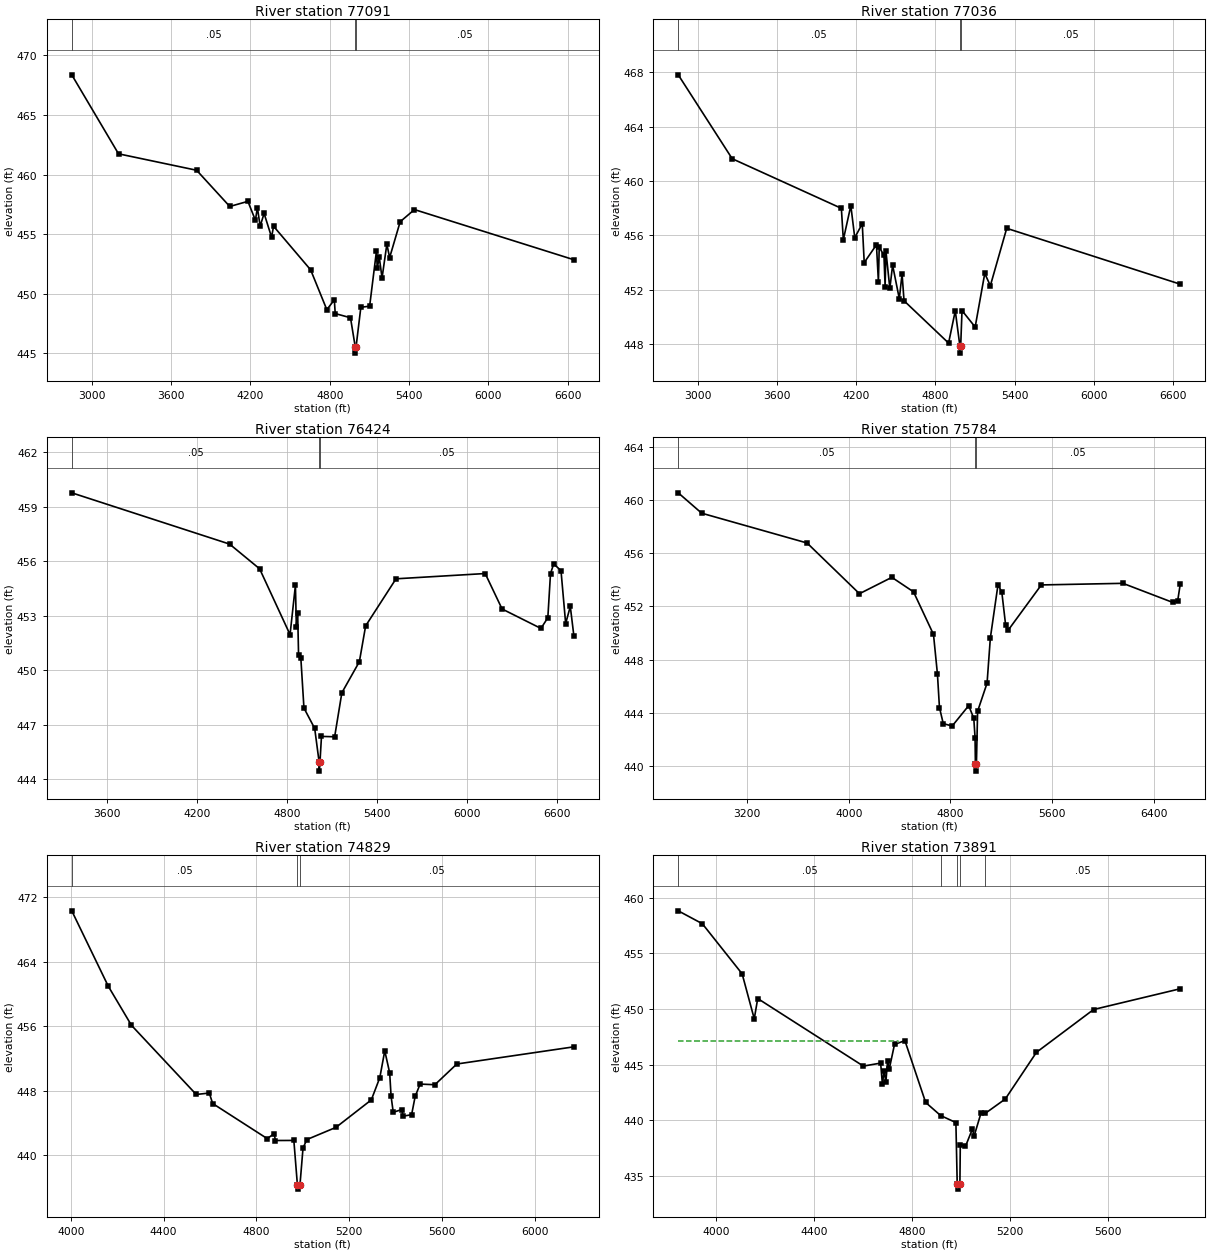
Type RM Length L Ch R = 1 ,77091   ,55,55,55
BEGIN DESCRIPTION:
Mapping XS f2b3e945
END DESCRIPTION:
XS GIS Cut Line= 3
      2668842.67      6912926.39      2667077.05      6911702.44
       2665691.6      6910811.79
#Sta/Elev= 30
  2849.9  468.37  3203.2  461.74  3793.6  460.36  4044.3  457.32  4181.4  457.75
  4238.1  456.16    4253  457.23    4274  455.66  4303.7  456.74  4360.4  454.74
  4375.3  455.66  4655.6     452  4777.9  448.66  4834.7  449.48  4841.4  448.33
  4956.9  447.98  4993.1  445.51  4993.9  445.01  4998.7  445.51  5035.2  448.86
  5101.6  448.95  5153.1  453.57  5159.1  452.14  5174.2  453.07  5195.4  451.32
  5231.7  454.15  5252.8  453.03  5332.4  456.04  5440.4  457.06  6645.3  452.85
#Mann= 3 ,-1 , 0
  2849.9     .05       0  4993.1     .04       0  4998.7     .05       0
Bank Sta=4993.1,4998.7
XS Rating Curve= 0 ,0
Exp/Cntr=0.3,0.1

Type RM Length L Ch R = 1 ,77036   ,612,612,612
BEGIN DESCRIPTION:
Mapping XS 5fc3de8d
END DESCRIPTION:
XS GIS Cut Line= 3
      2668863.48      6912863.87      2667097.89      6911655.56
      2665692.83      6910755.29
#Sta/Elev= 30
  2848.9  467.81  3258.1  461.64  4086.2  457.99  4101.1  455.68    4158  458.19
  4187.8  455.83  4244.7  456.86  4259.6     454  4352.3  455.31  4367.2  452.59
  4373.3  455.13  4409.2  454.54    4418  452.24  4424.1  454.86  4453.9   452.1
  4474.9  453.81  4525.7  451.34  4546.6  453.16  4561.6  451.19  4899.4  448.08
  4950.2  450.45  4985.6  447.84  4986.4  447.34  4991.2  447.84  5001.3  450.47
  5101.1  449.26  5173.8   453.2  5216.3   452.3  5340.4  456.52  6657.1  452.41
#Mann= 3 ,-1 , 0
  2848.9     .05       0  4985.6     .04       0  4991.2     .05       0
Bank Sta=4985.6,4991.2
XS Rating Curve= 0 ,0
Exp/Cntr=0.3,0.1

Type RM Length L Ch R = 1 ,76424   ,640,640,640
BEGIN DESCRIPTION:
Mapping XS 48a07a49
END DESCRIPTION:
XS GIS Cut Line= 3
      2668681.22      6912077.44      2667342.68      6911145.15
      2665729.51      6910577.93
#Sta/Elev= 30
  3368.5  459.76  4418.8  456.94  4618.6  455.58  4821.1  451.96  4856.9  454.68
    4863   452.4  4871.7  453.17  4877.8  450.83  4892.7   450.7  4913.6  447.92
  4985.1   446.8  5014.6  444.95  5015.4  444.45  5020.2  444.95  5030.3  446.36
  5117.9  446.34  5165.8  448.76  5282.4  450.47  5324.1  452.44  5526.2  455.03
  6119.8  455.32  6232.1  453.37  6490.8   452.3  6536.6  452.89  6554.4  455.32
  6575.6  455.85  6624.2  455.48  6655.2  452.57  6686.1  453.51  6709.7   451.9
#Mann= 3 ,-1 , 0
  3368.5     .05       0  5014.6     .04       0  5020.2     .05       0
Bank Sta=5014.6,5020.2
XS Rating Curve= 0 ,0
Exp/Cntr=0.3,0.1

Type RM Length L Ch R = 1 ,75784   ,955,955,955
BEGIN DESCRIPTION:
Big Cottonwood Creek 93.0
END DESCRIPTION:
XS GIS Cut Line= 5
      2669131.09      6912115.64       2668002.6      6910778.82
      2667821.85       6910551.4      2667519.72      6910562.84
      2665915.56      6910436.81
#Sta/Elev= 30
  2657.7  460.53  2842.2     459  3671.7  456.76  4083.9  452.95  4338.9  454.18
  4509.5  453.09  4666.6  449.89  4697.7  446.91  4713.5   444.4  4743.5  443.19
  4813.6  443.01  4943.7  444.54  4983.7  443.59  4993.7  442.14  4996.5  440.12
  4997.4  439.62  5002.2  440.12  5004.4  440.12  5013.8  444.12  5088.2  446.23
  5114.1  449.63  5174.3  453.63  5204.3  453.07  5234.4  450.59  5254.5  450.21
  5515.3  453.61  6157.3  453.73  6548.5   452.3  6588.6  452.43  6609.1   453.7
#Mann= 3 ,-1 , 0
  2657.7     .05       0  4996.5     .04       0  5002.2     .05       0
Bank Sta=4996.5,5002.2
XS Rating Curve= 0 ,0
Exp/Cntr=0.3,0.1

Type RM Length L Ch R = 1 ,74829   ,938,938,938
BEGIN DESCRIPTION:
Big Cottonwood Creek 92.0
END DESCRIPTION:
XS GIS Cut Line= 3
      2668476.04      6909160.97        2667676.        6909761.
       2666686.4      6910374.33
#Sta/Elev= 30
  4004.5  470.31  4161.8  460.96  4261.8  456.11    4541  447.53  4597.3  447.71
  4611.8  446.41  4847.3  442.05  4876.4  442.67  4882.7  441.82  4961.8  441.83
  4977.2  436.29  4978.7  435.79  4988.1  436.29  5001.4   440.9  5018.1  441.94
  5143.4  443.45  5295.8  446.86  5332.4  449.62  5353.7  452.95  5374.9  450.21
    5381   447.3  5390.3  445.32  5426.9  445.66  5432.8  444.84  5469.4  445.02
  5484.8  447.29  5506.1  448.82  5569.8  448.74  5664.3  451.31  6168.8  453.44
#Mann= 3 ,-1 , 0
  4004.5     .05       0  4977.2     .03       0  4988.1     .05       0
#XS Ineff= 2 , 0
       0                  5353.7       0  452.95
Permanent Ineff=
       F       F
Bank Sta=4977.2,4988.1
XS Rating Curve= 0 ,0
Exp/Cntr=0.3,0.1

Type RM Length L Ch R = 1 ,73891   ,932,932,932
BEGIN DESCRIPTION:
Big Cottonwood Creek 89.0
END DESCRIPTION:
XS GIS Cut Line= 3
      2668136.39      6908142.27      2667336.42      6908942.25
       2666686.4      6909592.27
#Sta/Elev= 30
  3845.3  458.83  3943.7  457.67  4106.3  453.16  4155.8  449.11  4169.9  450.94
  4601.3  444.86    4672  445.13  4679.1  443.24  4686.1  444.45  4693.2  443.41
  4700.3  445.31  4707.3  444.61  4728.6  446.81    4771  447.15  4855.8  441.59
    4917  440.41  4979.3  439.78  4984.7  434.29  4986.2  433.79  4995.7  434.29
  4997.3  437.79  5018.5  437.64  5046.8   439.2  5053.8  438.57  5082.1  440.65
  5099.5  440.61  5181.1   441.9  5308.4   446.1  5541.7  449.95  5895.9  451.82
#Mann= 5 ,-1 , 0
  3845.3     .05       0    4917     .12       0  4984.7     .07       0
  4995.7     .12       0  5099.5     .05       0
#XS Ineff= 2 , 0
       0  4742.7  447.11               0
Permanent Ineff=
       F       F
Bank Sta=4984.7,4995.7
XS Rating Curve= 0 ,0
Exp/Cntr=0.3,0.1

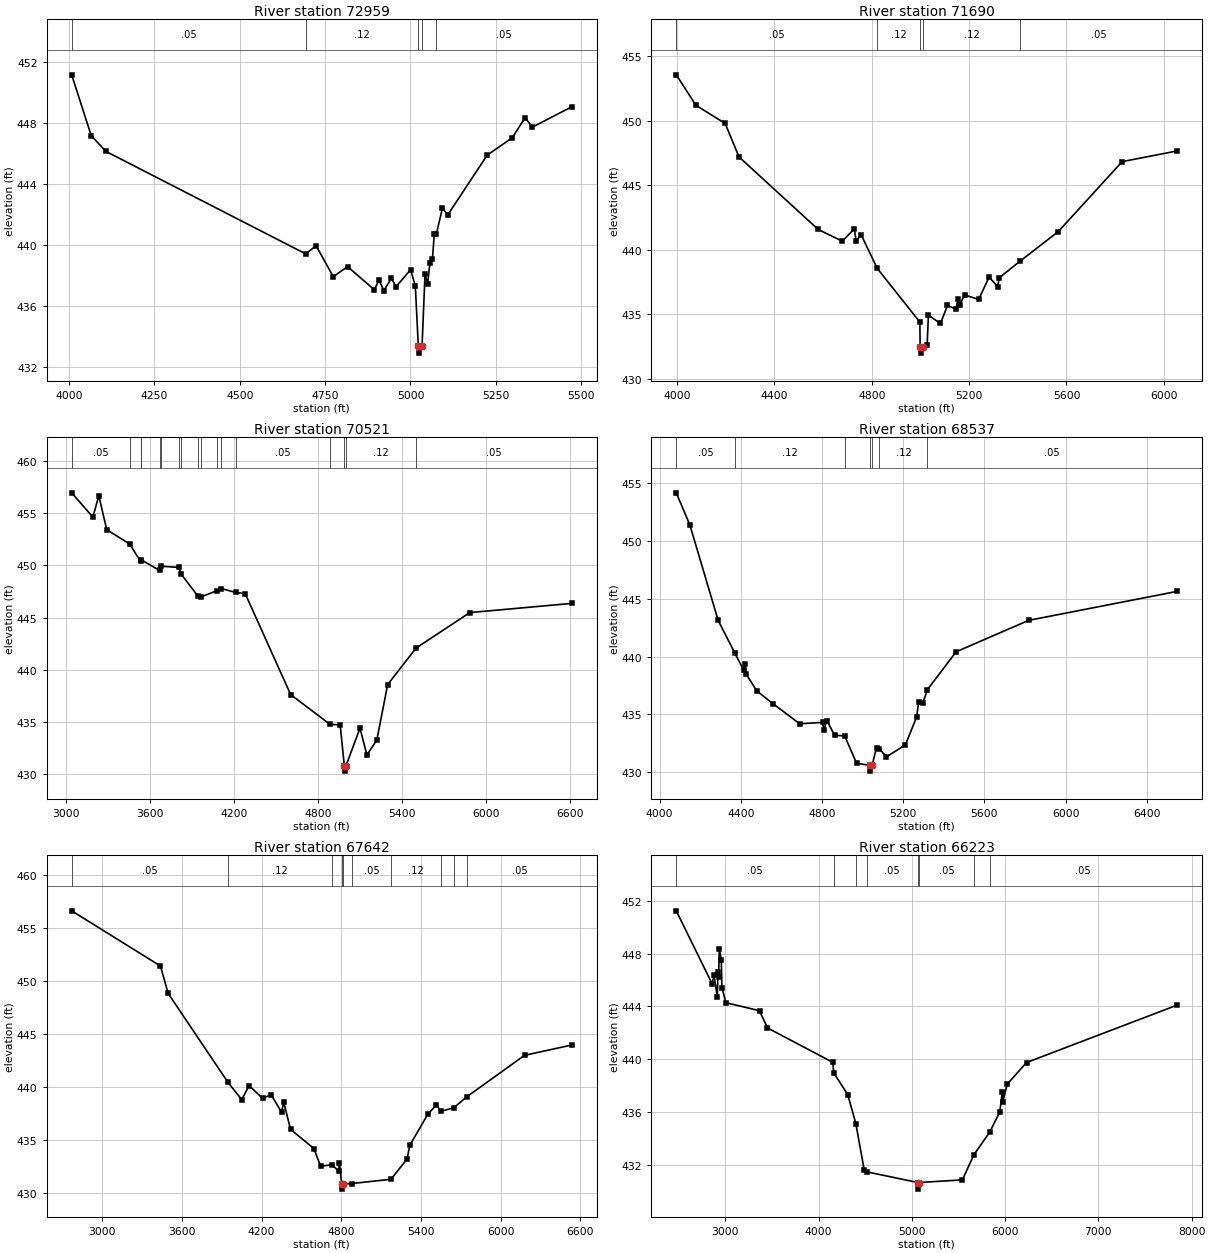
Type RM Length L Ch R = 1 ,72959   ,1269,1269,1269
BEGIN DESCRIPTION:
Big Cottonwood Creek 88.0
END DESCRIPTION:
XS GIS Cut Line= 3
      2667452.94      6907787.43      2666652.96      6908487.41
      2666453.36      6908836.71
#Sta/Elev= 30
  4007.8  451.15    4065  447.16  4107.7  446.13  4693.2   439.4  4723.6  439.94
  4773.9   437.9  4815.7  438.57    4894  437.05  4907.8  437.69    4922  436.99
  4943.8  437.79  4958.1  437.26  5000.3  438.36  5014.1  437.31  5022.8  433.39
  5024.3  432.89  5033.9  433.39  5042.5  438.06  5050.1  437.44  5056.8  438.78
  5064.4  439.09  5069.7  440.72  5075.6  440.69  5093.5   442.4  5109.4  441.97
  5224.7  445.88    5298  447.02  5335.4  448.33    5357  447.72  5473.1  449.06
#Mann= 5 ,-1 , 0
  4007.8     .05       0  4693.2     .12       0  5022.8     .07       0
  5033.9     .12       0  5075.6     .05       0
Bank Sta=5022.8,5033.9
XS Rating Curve= 0 ,0
Exp/Cntr=0.3,0.1

Type RM Length L Ch R = 1 ,71690   ,1169,1169,1169
BEGIN DESCRIPTION:
Big Cottonwood Creek 85.0
END DESCRIPTION:
XS GIS Cut Line= 3
      2666906.95      6906737.97      2666206.94      6907487.98
      2665557.76      6908286.97
#Sta/Elev= 30
  3997.2  453.55  4077.9  451.19  4198.1  449.78  4254.7  447.19  4580.1  441.56
  4679.3  440.65  4728.6  441.61  4735.9  440.69  4756.9  441.14  4822.8  438.54
  4997.8  434.38    4999  432.47  5000.6  431.97  5010.2  432.47  5027.8  432.61
    5033  434.91  5082.6  434.27  5111.3  435.67  5146.5  435.38  5154.4  436.19
  5160.9  435.69  5181.7  436.49  5239.2  436.13  5282.3  437.86  5317.5  437.13
  5323.9  437.81  5410.9  439.12  5566.7   441.4  5828.9  446.82  6052.6  447.64
#Mann= 5 ,-1 , 0
  3997.2     .05       0  4822.8     .12       0    4999     .07       0
  5010.2     .12       0  5410.9     .05       0
Bank Sta=4999,5010.2
XS Rating Curve= 0 ,0
Exp/Cntr=0.3,0.1

Type RM Length L Ch R = 1 ,70521   ,1984,1984,1984
BEGIN DESCRIPTION:
Big Cottonwood Creek 84.0
END DESCRIPTION:
XS GIS Cut Line= 3
      2667035.35      6905546.22      2665643.23      6906927.06
      2664530.21      6908098.24
#Sta/Elev= 30
  3039.2  456.93  3190.6  454.61  3233.1  456.65  3289.6  453.41  3453.8  452.03
  3531.9  450.37  3537.7  450.51  3667.6  449.51  3680.6  449.91  3803.3   449.8
  3823.4  449.13    3939   447.1  3966.3  446.99  4074.8  447.56  4109.2  447.77
  4210.5  447.41  4279.5  447.29  4604.8  437.63  4885.2   434.8  4958.4  434.73
  4988.1  430.82  4989.7  430.32  4999.4  430.82    5100  434.42  5149.3  431.87
  5220.1  433.28  5297.8   438.6  5501.2  442.09  5885.1  445.48  6615.7  446.36
#Mann= 17 ,-1 , 0
  3039.2     .05       0  3453.8     .12       0  3531.9     .05       0
  3537.7     .12       0  3667.6     .05       0  3680.6     .12       0
  3803.3     .05       0  3823.4     .12       0    3939     .05       0
  3966.3     .12       0  4074.8     .05       0  4109.2     .12       0
  4210.5     .05       0  4885.2     .12       0  4988.1     .07       0
  4999.4     .12       0  5501.2     .05       0
Bank Sta=4988.1,4999.4
XS Rating Curve= 0 ,0
Exp/Cntr=0.3,0.1

Type RM Length L Ch R = 1 ,68537   ,895,895,895
BEGIN DESCRIPTION:
Big Cottonwood Creek 82.0
END DESCRIPTION:
XS GIS Cut Line= 3
      2664975.99      6905511.01        2664526.        6906311.
      2664196.85       6907822.2
#Sta/Elev= 30
  4082.1  454.17  4149.3  451.38  4288.6  443.12  4371.5  440.27  4413.9  438.82
  4419.6  439.39  4426.3  438.48  4478.9  437.02  4559.8   435.9  4690.2  434.18
  4802.7   434.3  4808.4  433.67  4824.4  434.45    4862  433.18  4911.5  433.13
  4970.3  430.76  5035.2  430.58  5036.8  430.08  5046.6  430.58  5068.5  432.12
    5083  431.99  5117.6  431.32  5210.6  432.35  5266.1  434.77  5276.3  436.08
  5296.8  435.98  5319.1  437.13  5460.5  440.41  5817.9  443.13  6546.6  445.63
#Mann= 7 ,-1 , 0
  4082.1     .05       0  4371.5     .12       0  4911.5      .1       0
  5035.2     .07       0  5046.6      .1       0    5083     .12       0
  5319.1     .05       0
Bank Sta=5035.2,5046.6
XS Rating Curve= 0 ,0
Exp/Cntr=0.3,0.1

Type RM Length L Ch R = 1 ,67642   ,1419,1419,1419
BEGIN DESCRIPTION:
Big Cottonwood Creek 80.0
END DESCRIPTION:
XS GIS Cut Line= 3
      2664691.62      6904046.22        2663726.        6906061.
      2663571.94      6907586.92
#Sta/Elev= 30
  2770.3  456.64  3439.1  451.42  3496.4  448.84    3947  440.43  4050.9  438.79
  4106.3  440.11    4209   438.9  4271.4  439.27  4350.5  437.61  4367.6  438.53
  4418.4  435.98  4594.1  434.17    4645  432.49  4732.4  432.64    4781     432
  4786.5   432.8  4803.4  430.83    4805  430.33  4814.9  430.83  4880.1  430.86
  5174.7  431.26    5296  433.18  5316.1  434.46  5452.1  437.41  5517.1   438.3
  5550.2  437.68  5648.3  438.03  5744.5  439.05  6180.5  442.98  6538.2  443.96
#Mann= 10 ,-1 , 0
  2770.3     .05       0    3947     .12       0  4732.4      .1       0
  4803.4     .03       0  4814.9      .1       0  4880.1     .05       0
  5174.7     .12       0  5550.2     .05       0  5648.3     .12       0
  5744.5     .05       0
Bank Sta=4803.4,4814.9
XS Rating Curve= 0 ,0
Exp/Cntr=0.3,0.1

Type RM Length L Ch R = 1 ,66223   ,886,886,886
BEGIN DESCRIPTION:
Big Cottonwood Creek 78.0
END DESCRIPTION:
XS GIS Cut Line= 5
       2663931.2       6903603.5      2662879.14      6904645.15
        2662476.        6905611.      2662399.97      6906593.06
      2663584.08      6908019.66
#Sta/Elev= 30
  2472.9  451.23  2856.7  445.72  2877.9  446.36  2913.2  444.71  2920.3  446.57
  2927.4  446.22  2934.4  448.37  2955.7  447.54  2962.7  445.42  3005.1  444.28
  3365.8  443.67  3450.7  442.37  4152.8  439.76  4160.7  438.98    4312  437.32
  4398.8  435.13  4489.5  431.58  4514.8  431.48  5064.4  430.67    5066  430.17
    5076  430.67  5541.6  430.87  5665.3  432.78  5834.6  434.48  5942.8  436.02
  5969.8  437.54  5974.8  436.79  6022.9  438.12  6229.3  439.75    7839  444.08
#Mann= 8 ,-1 , 0
  2472.9     .05       0  4160.7     .12       0  4398.8      .1       0
  4514.8     .05       0  5064.4     .03       0    5076     .05       0
  5665.3     .12       0  5834.6     .05       0
Bank Sta=5064.4,5076
XS Rating Curve= 0 ,0
Exp/Cntr=0.3,0.1