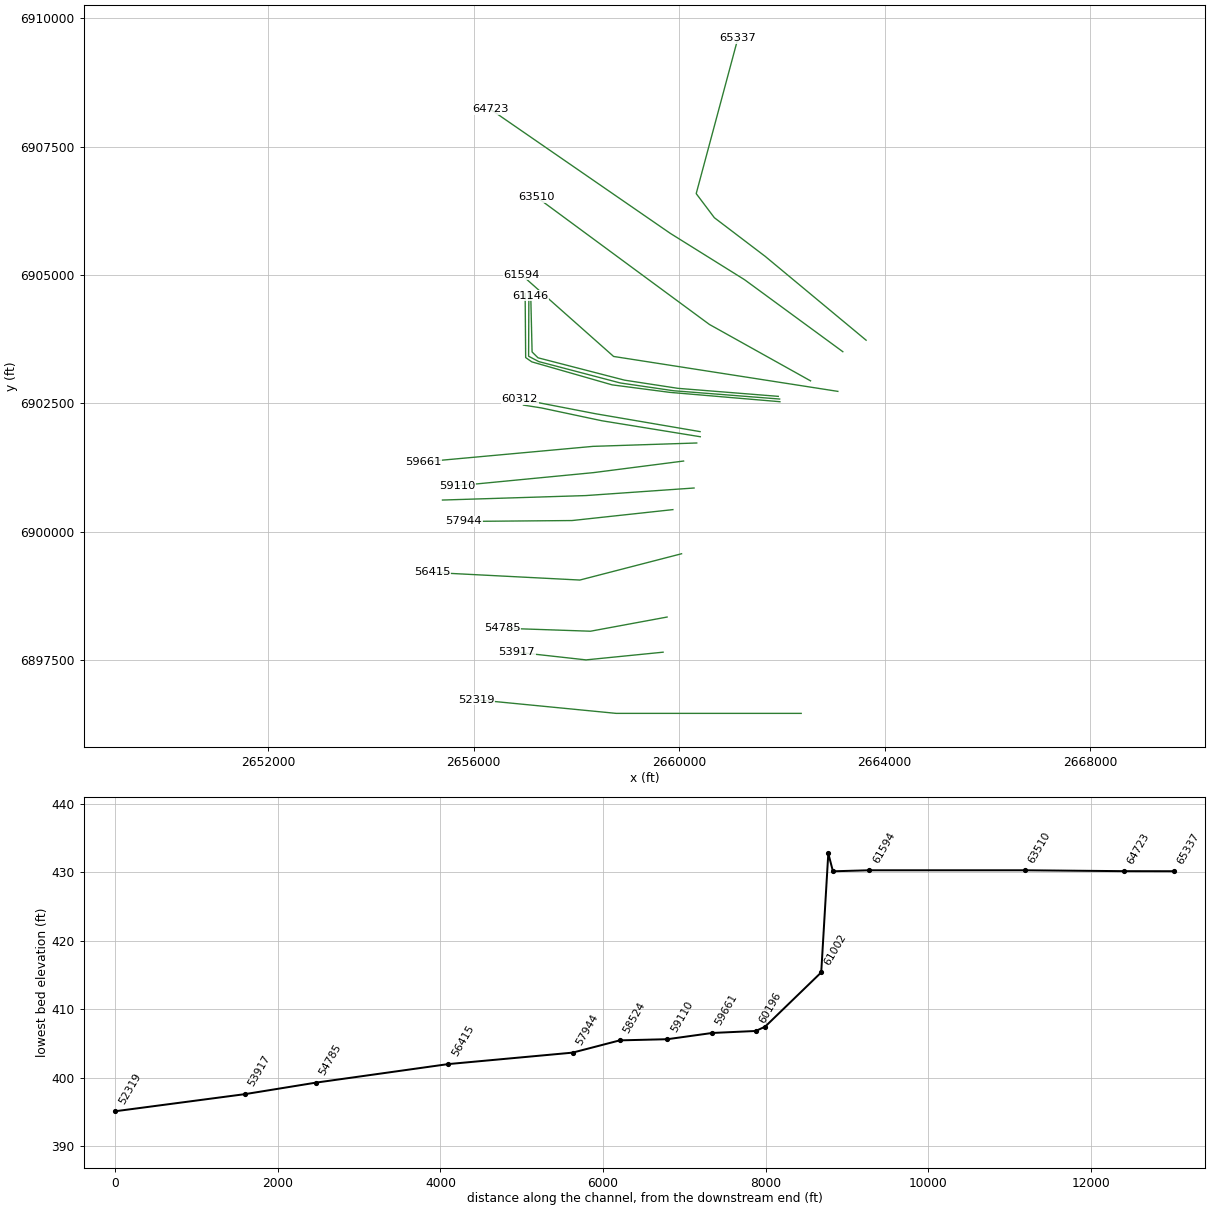
HEC-RAS study Big Cottonwood Creek.prj: Big Cottonwood Creek Base Level Engineering

--- Big Cottonwood Creek.g01 (geometry) --- (continued)

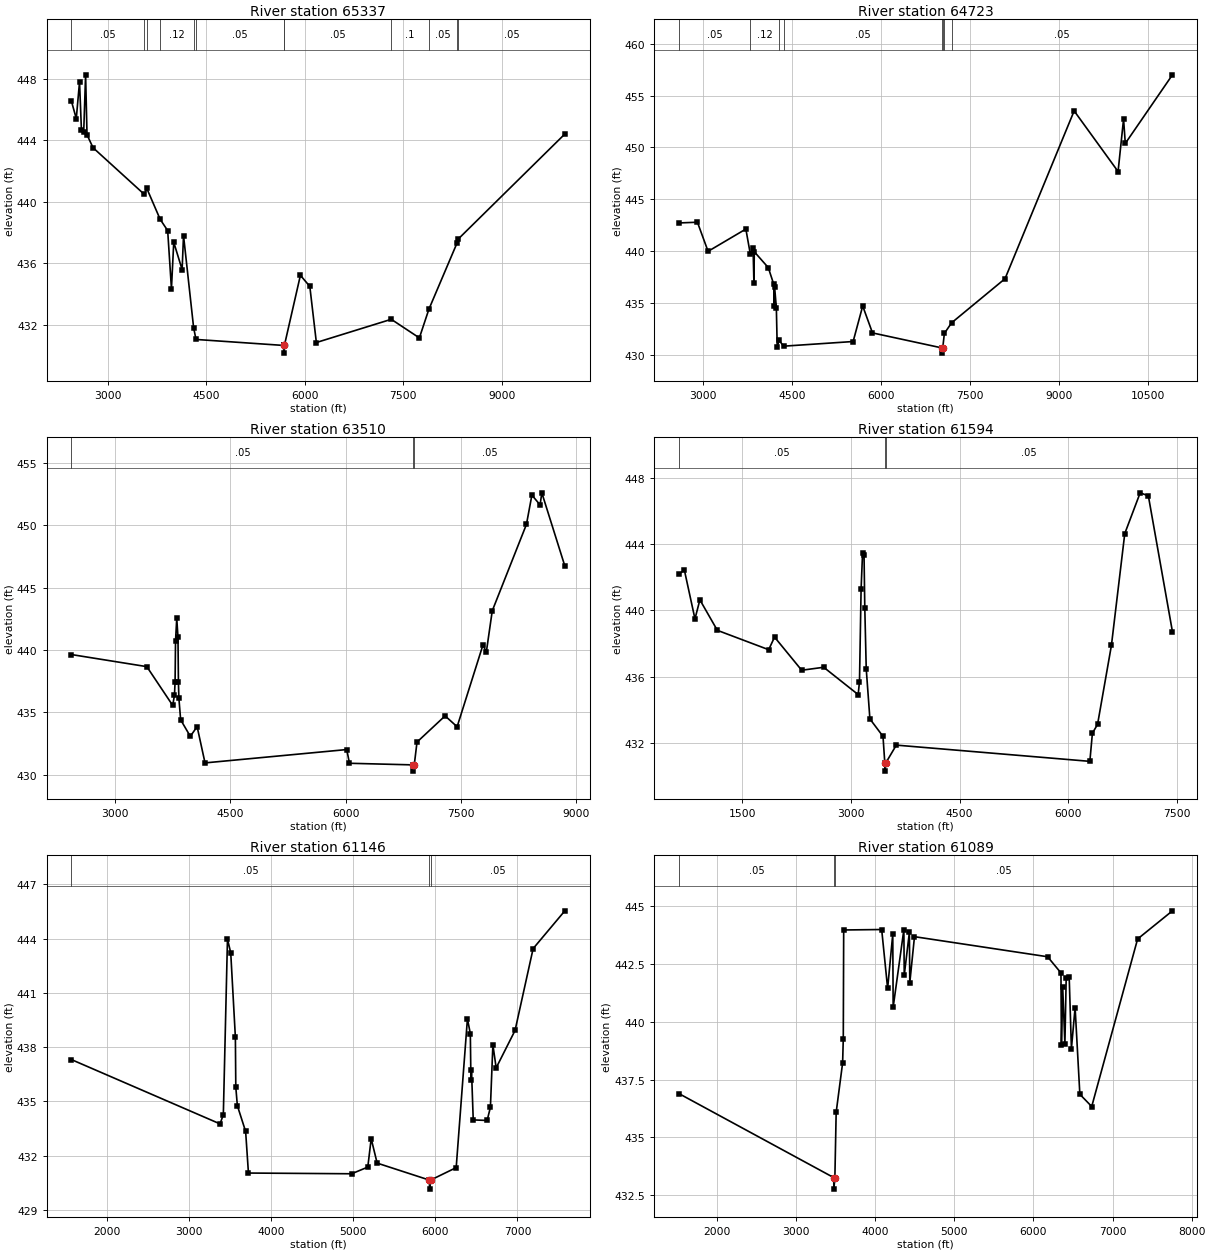
Type RM Length L Ch R = 1 ,65337   ,614,614,614
BEGIN DESCRIPTION:
Big Cottonwood Creek 77.0
END DESCRIPTION:
XS GIS Cut Line= 5
      2663639.56      6903728.47        2661676.        6905361.
      2660686.62      6906113.62      2660333.23      6906583.05
      2661144.57      6909607.15
#Sta/Elev= 30
  2446.2  446.56  2521.4   445.4  2570.9  447.79  2599.6  444.68  2634.7  444.55
  2663.4  448.25  2684.9  444.35  2776.6  443.51  3558.9  440.47  3595.7  440.86
    3799  438.85  3913.3  438.12  3970.6  434.34  4005.7  437.36  4133.3  435.58
  4154.5   437.8  4308.2  431.81  4344.5  431.04    5679  430.65  5680.7  430.15
  5690.7  430.65  5934.4  435.21  6077.8  434.49  6177.6  430.84  7318.2  432.35
  7746.3  431.14  7890.7     433  8322.7  437.34  8337.9  437.57  9961.5   444.4
#Mann= 12 ,-1 , 0
  2446.2     .05       0  3558.9     .12       0  3595.7     .05       0
    3799     .12       0  4308.2      .1       0  4344.5     .05       0
    5679     .03       0  5690.7     .05       0  7318.2      .1       0
  7890.7     .05       0  8322.7     .12       0  8337.9     .05       0
Bank Sta=5679,5690.7
XS Rating Curve= 0 ,0
Exp/Cntr=0.3,0.1

Type RM Length L Ch R = 1 ,64723   ,1213,1213,1213
BEGIN DESCRIPTION:
Big Cottonwood Creek 76.0
END DESCRIPTION:
XS GIS Cut Line= 4
       2663186.4      6903504.54      2661273.92      6904906.83
      2659826.35      6905810.86       2656331.5      6908223.67
#Sta/Elev= 30
  2590.7  442.72  2902.5  442.79  3082.3  439.98  3719.6  442.13  3794.3  439.73
    3841  440.33  3855.7  436.92  3861.9  439.94  4098.1  438.41  4190.8  436.79
  4198.4  434.69  4204.6  436.53  4233.9  434.54  4248.6  430.75  4280.8   431.4
    4355  430.83  5529.3  431.28  5690.7  434.71  5855.8  432.11  7029.1  430.66
  7030.7  430.16  7040.8  430.66  7068.3  432.06  7189.5  433.08  8091.6  437.34
  9257.6  453.53  9998.7  447.68 10091.3  452.74 10120.4  450.39 10915.7  457.01
#Mann= 8 ,-1 , 0
  2590.7     .05       0  3794.3     .12       0  4280.8      .1       0
    4355     .05       0  7029.1     .03       0  7040.8     .05       0
  7068.3     .12       0  7189.5     .05       0
Bank Sta=7029.1,7040.8
XS Rating Curve= 0 ,0
Exp/Cntr=0.3,0.1

Type RM Length L Ch R = 1 ,63510   ,1916,1916,1916
BEGIN DESCRIPTION:
Big Cottonwood Creek 75.0
END DESCRIPTION:
XS GIS Cut Line= 3
      2662557.92      6902936.83      2660589.21      6904035.77
      2657235.04      6906509.73
#Sta/Elev= 30
    2431  439.64  3413.2  438.67  3750.2  435.56  3773.1  436.38  3781.1  437.45
  3786.9  440.72  3802.8  442.55  3818.8  441.03  3824.6  437.42  3830.4  436.16
  3853.3  434.41  3979.3  433.08  4067.9  433.86  4170.7  430.95    6015  432.02
  6050.5  430.92    6882  430.79  6883.6  430.29  6893.9  430.79  6929.6  432.62
  7295.1  434.72  7451.7  433.85  7787.9  440.41  7831.8  439.84    7909  443.15
  8353.9  450.08  8424.8  452.43  8531.3  451.64  8554.1  452.61  8853.5  446.74
#Mann= 3 ,-1 , 0
    2431     .05       0    6882     .03       0  6893.9     .05       0
Bank Sta=6882,6893.9
XS Rating Curve= 0 ,0
Exp/Cntr=0.3,0.1

Type RM Length L Ch R = 1 ,61594   ,448,448,448
BEGIN DESCRIPTION:
Big Cottonwood Creek 73.0
END DESCRIPTION:
XS GIS Cut Line= 3
       2663089.4      6902731.95      2658725.87      6903411.89
      2656936.34      6905000.17
#Sta/Elev= 30
   628.7  442.17     703  442.44   849.8  439.48   917.7  440.63  1158.4  438.79
  1866.9  437.62  1947.8  438.38  2322.3  436.38  2625.9  436.56  3101.6  434.91
  3119.9   435.7  3142.1   441.3  3162.3  443.47  3182.6  443.31  3192.9  440.16
  3212.9  436.46  3263.5  433.44  3444.2  432.39  3468.9  430.79  3470.9  430.29
  3483.2  430.79  3627.9  431.86  6298.2  430.88  6333.3  432.58  6404.4  433.11
  6595.7  437.88  6779.9  444.63  6992.3  447.09  7105.2  446.91  7437.6  438.71
#Mann= 3 ,-1 , 0
   628.7     .05       0  3468.9     .03       0  3483.2     .05       0
Bank Sta=3468.9,3483.2
XS Rating Curve= 0 ,0
Exp/Cntr=0.3,0.1

Type RM Length L Ch R = 1 ,61146   ,57,57,57
BEGIN DESCRIPTION:
Mapping XS d199a3e4
END DESCRIPTION:
XS GIS Cut Line= 6
       2661931.2      6902634.73       2659978.1      6902790.98
      2658938.96       6902950.3      2657254.63      6903385.74
      2657139.55      6903499.31      2657113.54      6904597.13
#Sta/Elev= 30
  1566.4  437.31  3377.4  433.75  3417.5  434.26    3468  443.98  3507.8  443.21
  3564.3  438.54  3569.4  435.78  3588.3  434.76  3689.1  433.33  3723.4  431.03
  4980.4  430.99  5176.9  431.36  5218.3  432.93  5290.8  431.58    5927  430.64
    5929  430.14  5941.6  430.64  6253.5  431.33  6390.4  439.56  6425.8  438.75
  6432.9  436.18    6440  436.71  6461.2  433.97  6630.4  433.94  6670.4  434.67
  6700.4  438.13  6740.4  436.85  6970.5  438.92  7190.6  443.45  7576.8  445.54
#Mann= 3 ,-1 , 0
  1566.4     .05       0    5927     .03       0  5941.6     .05       0
Bank Sta=5927,5941.6
XS Rating Curve= 0 ,0
Exp/Cntr=0.3,0.1

Type RM Length L Ch R = 1 ,61089   ,87,87,87
BEGIN DESCRIPTION:
Mapping XS 7d5e8f4f
END DESCRIPTION:
XS GIS Cut Line= 6
      2661957.22      6902582.65      2659894.76       6902744.1
       2658858.3      6902895.15      2657269.76      6903311.81
      2657071.85      6903415.98      2657077.05       6904671.2
#Sta/Elev= 30
  1519.8  436.89  3476.1  433.25  3478.1  432.75  3490.7  433.25  3507.1  436.08
  3588.6  438.22    3597  439.27  3602.1  443.98  4082.3     444  4157.4  441.45
  4222.4   443.8  4227.4  440.63  4362.5  443.99  4367.5  442.02  4432.5  443.88
  4437.6  441.69  4496.8  443.69  6179.4  442.82  6348.2  442.12  6353.9  439.01
  6370.3  441.49  6397.9  439.04  6414.3  441.89  6452.1  441.96  6480.4  438.84
    6527  440.62    6587  436.86    6737  436.33    7317  443.59  7757.2  444.81
#Mann= 3 ,-1 , 0
  1519.8     .05       0  3476.1     .03       0  3490.7     .05       0
Bank Sta=3476.1,3490.7
XS Rating Curve= 0 ,0
Exp/Cntr=0.3,0.1

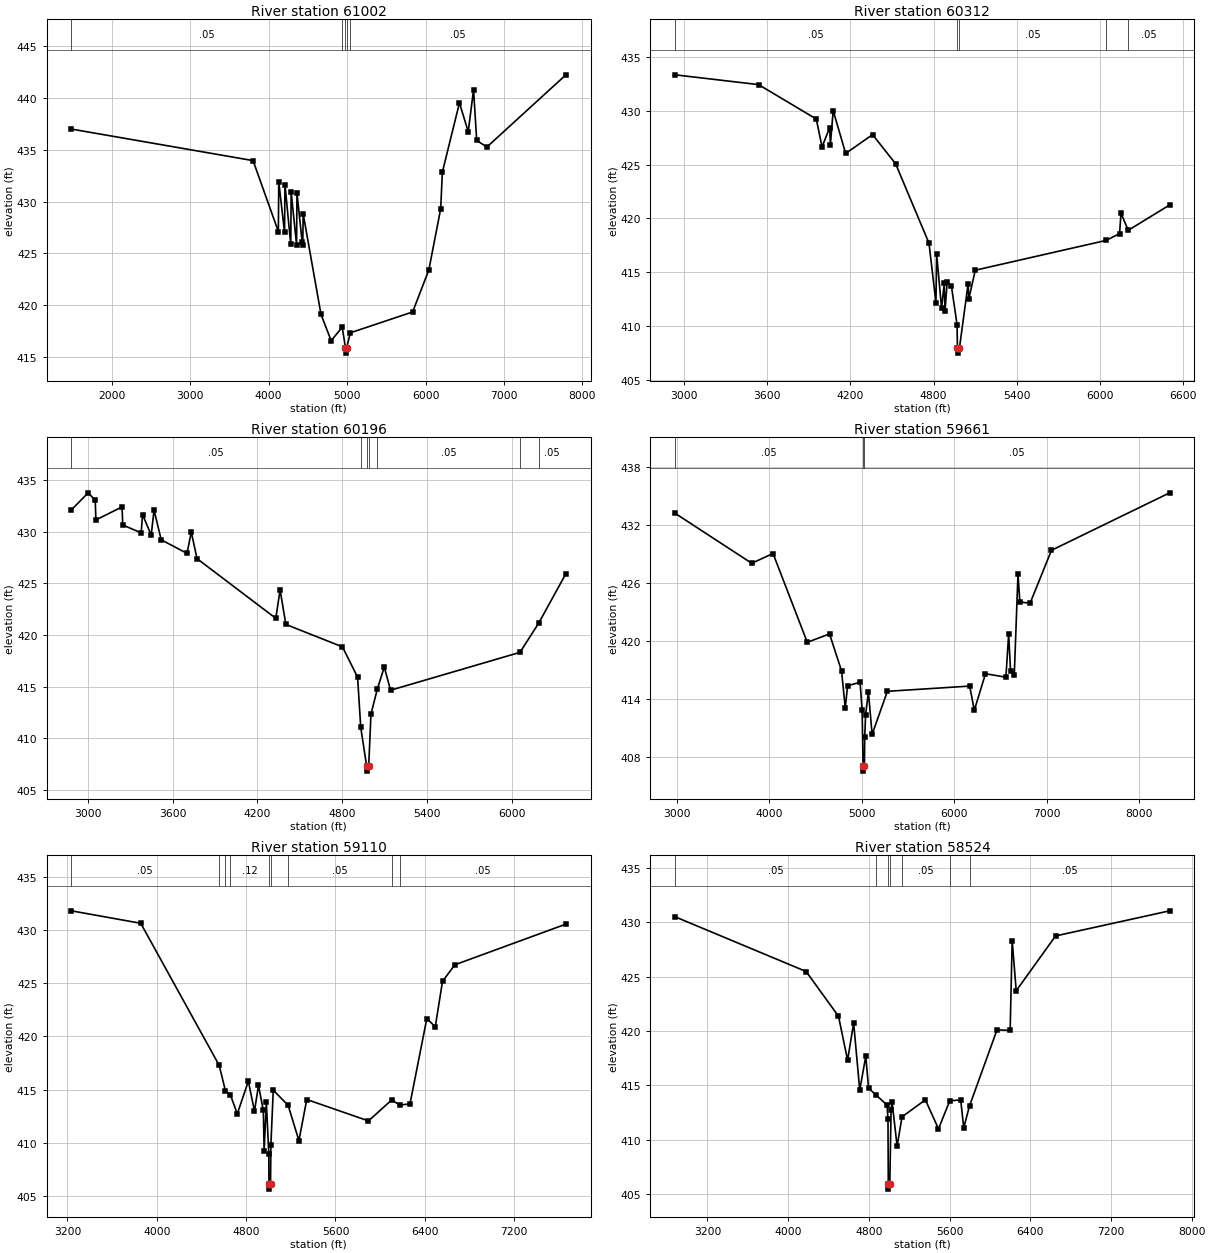
Type RM Length L Ch R = 1 ,61002   ,690,690,690
BEGIN DESCRIPTION:
Mapping XS be34972c
END DESCRIPTION:
XS GIS Cut Line= 6
       2661962.5      6902530.56      2659816.64      6902712.85
      2658696.85      6902858.69      2657134.35       6903306.6
      2657014.55      6903389.94      2657004.15      6904637.97
#Sta/Elev= 30
  1486.1  436.99  3801.7  433.95    4124  427.11    4129  431.92  4203.1  427.02
  4208.1  431.63  4282.1  425.87  4287.2  430.88  4356.1  425.85  4361.2  430.83
  4426.9  426.14  4435.2  425.86  4440.2  428.83  4667.3  419.13  4796.8  416.59
  4938.2  417.89  4979.6  415.89  4981.6  415.39  4994.2  415.89  5041.6  417.35
  5835.7  419.36  6041.9  423.41  6193.1  429.31  6214.2  432.83  6432.3  439.52
    6544  436.73    6612  440.78    6652  435.89    6782  435.26    7789  442.22
#Mann= 5 ,-1 , 0
  1486.1     .05       0  4938.2     .12       0  4979.6     .07       0
  4994.2     .12       0  5041.6     .05       0
Bank Sta=4979.6,4994.2
XS Rating Curve= 0 ,0
Exp/Cntr=0.3,0.1

Type RM Length L Ch R = 1 ,60312   ,116,116,116
BEGIN DESCRIPTION:
Mapping XS 2a0fbb7a
END DESCRIPTION:
XS GIS Cut Line= 3
      2660408.68      6901948.09      2658376.13      6902295.94
      2656901.68      6902581.78
#Sta/Elev= 30
  2937.9  433.35  3539.2  432.44  3955.2  429.24  3996.7  426.64  4051.7  428.45
  4056.8  426.84  4076.9  430.02  4166.8  426.04    4361  427.79  4527.2  425.07
  4767.5  417.69  4817.5  412.17  4822.5  416.69  4858.1  411.66  4877.5  413.95
  4882.6  411.37  4898.7  414.09  4929.1   413.7  4969.7  410.13  4972.5  407.97
  4974.5  407.47  4987.2  407.97  5049.4  413.92  5054.5  412.53  5101.1  415.18
  6043.2  417.95    6141  418.58  6151.2  420.48  6203.4  418.89  6501.9  421.25
#Mann= 5 ,-1 , 0
  2937.9     .05       0  4972.5     .03       0  4987.2     .05       0
  6043.2    .075       0  6203.4     .05       0
Bank Sta=4972.5,4987.2
XS Rating Curve= 0 ,0
Exp/Cntr=0.3,0.1

Type RM Length L Ch R = 1 ,60196   ,535,535,535
BEGIN DESCRIPTION:
Mapping XS c7353ff0
END DESCRIPTION:
XS GIS Cut Line= 5
      2660413.01      6901848.27      2658500.07      6902159.28
      2658326.52      6902195.78      2657318.43      6902409.94
      2656971.19      6902464.58
#Sta/Elev= 30
  2884.6  432.09  3003.1  433.74  3053.1  433.02  3058.1  431.12  3242.8  432.38
  3247.9  430.63    3378  429.87  3388.1  431.64  3448.9  429.65  3469.2  432.07
  3519.8   429.2  3702.2  427.89  3732.6  429.95  3773.1  427.38  4330.3  421.61
  4360.7  424.36  4401.3  421.02  4801.8  418.85  4908.8  415.92    4931  411.07
  4972.7  407.34  4974.7  406.84  4987.4  407.34  5003.3  412.34  5048.4  414.78
  5097.5   416.9    5142  414.66  6057.3  418.32  6189.5  421.14  6382.1  425.93
#Mann= 7 ,-1 , 0
  2884.6     .05       0    4931     .12       0  4972.7     .07       0
  4987.4     .12       0  5048.4     .05       0  6057.3    .075       0
  6189.5     .05       0
Bank Sta=4972.7,4987.4
XS Rating Curve= 0 ,0
Exp/Cntr=0.3,0.1

Type RM Length L Ch R = 1 ,59661   ,551,551,551
BEGIN DESCRIPTION:
Big Cottonwood Creek 69.0
END DESCRIPTION:
XS GIS Cut Line= 3
      2660343.54      6901726.74        2658326.        6901661.
      2655013.65      6901357.82
#Sta/Elev= 30
  2981.4  433.23  3809.4  428.06  4039.5  429.07  4409.7  419.88  4649.8  420.75
  4779.9  416.93  4819.9  413.11  4845.7  415.38    4980  415.75  5002.5  412.86
  5012.7  407.05  5014.7  406.55  5027.4  407.05  5030.1  410.03  5040.2  412.39
  5070.3  414.75  5110.5  410.35  5275.2  414.81  6164.9  415.35  6215.1  412.85
  6335.6  416.63  6556.5  416.27  6586.2  420.75  6606.7   416.9  6646.9   416.5
    6687  426.95  6707.1  424.06  6817.6  423.92  7048.5   429.4  8326.2  435.35
#Mann= 3 ,-1 , 0
  2981.4     .05       0  5012.7     .03       0  5027.4     .05       0
Bank Sta=5012.7,5027.4
XS Rating Curve= 0 ,0
Exp/Cntr=0.3,0.1

Type RM Length L Ch R = 1 ,59110   ,586,586,586
BEGIN DESCRIPTION:
Mapping XS 5c1bdfe6
END DESCRIPTION:
XS GIS Cut Line= 3
       2660087.5      6901375.18        2658334.      6901149.49
      2655686.42      6900893.41
#Sta/Elev= 30
  3235.5  431.79  3856.4  430.62  4558.9  417.27  4614.9  414.87  4658.4  414.53
  4720.8  412.71    4820  415.78  4874.8  412.97  4910.7  415.38  4954.3  413.03
  4961.1  409.25  4981.3  413.79  5003.5  408.91  5004.1  406.14  5006.1  405.64
  5018.8  406.14  5021.5  409.76  5043.2  414.94  5176.4  413.51  5272.7   410.2
    5343  414.06  5895.6  412.05  6102.3  414.01  6178.1  413.54  6267.3  413.65
    6418  421.67  6493.6  420.89  6558.7  425.17  6669.2  426.72  7663.4  430.54
#Mann= 9 ,-1 , 0
  3235.5     .05       0  4558.9     .12       0  4614.9     .05       0
  4658.4     .12       0  5004.1     .07       0  5018.8     .12       0
  5176.4     .05       0  6102.3     .12       0  6178.1     .05       0
Bank Sta=5004.1,5018.8
XS Rating Curve= 0 ,0
Exp/Cntr=0.3,0.1

Type RM Length L Ch R = 1 ,58524   ,580,580,580
BEGIN DESCRIPTION:
Mapping XS e988a74c
END DESCRIPTION:
XS GIS Cut Line= 3
      2660291.43        6900850.      2658182.09      6900702.44
      2655395.64      6900615.63
#Sta/Elev= 30
  2879.5  430.51  4178.1  425.48  4498.9  421.37  4589.1  417.33  4649.2  420.74
  4709.4  414.58  4769.5  417.68  4797.1  414.76  4866.5  414.16  4980.1  413.21
  4989.5  411.92  4992.6  405.97  4994.6  405.47  5007.6  405.97  5020.1  412.72
  5030.1   413.5  5080.1  409.42  5128.8  412.12  5360.3  413.68  5490.3  411.01
  5601.9  413.59  5710.4  413.67  5740.5  411.11  5797.8  413.12  6070.6  420.12
  6200.7  420.06  6220.7  428.33  6260.7  423.71  6650.9  428.75  7781.8  431.06
#Mann= 7 ,-1 , 0
  2879.5     .05       0  4866.5     .12       0  4992.6     .07       0
  5007.6     .12       0  5128.8     .05       0  5601.9     .12       0
  5797.8     .05       0
Bank Sta=4992.6,5007.6
XS Rating Curve= 0 ,0
Exp/Cntr=0.3,0.1

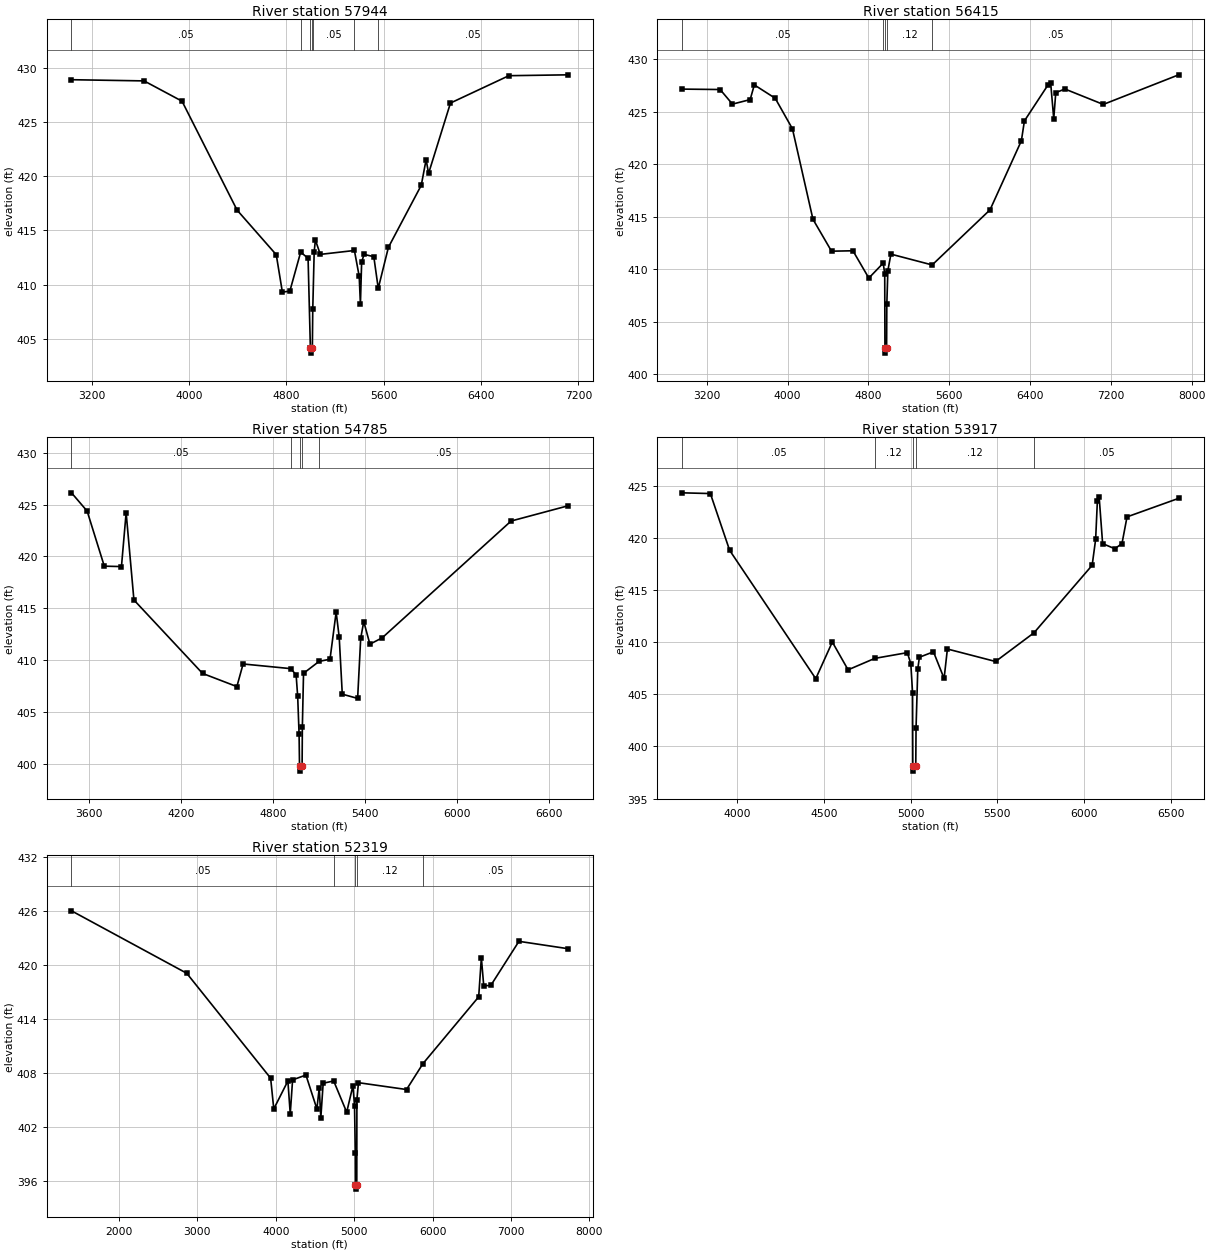
Type RM Length L Ch R = 1 ,57944   ,1529,1529,1529
BEGIN DESCRIPTION:
Mapping XS 2f3dfe8b
END DESCRIPTION:
XS GIS Cut Line= 3
      2659879.12        6900429.      2657917.33      6900216.33
      2655809.48      6900198.98
#Sta/Elev= 30
  3033.5  428.88  3630.1  428.77  3941.9   426.9  4394.5  416.86  4716.4  412.75
  4766.7   409.3  4828.2   409.4  4917.1  412.99  4977.9  412.42  4996.8  404.18
  4998.8  403.68  5013.1  404.18  5016.4  407.72  5028.1  413.03  5038.1  414.11
  5078.1  412.78  5358.7  413.14  5398.1  410.76  5408.1  408.19  5418.1  412.08
  5438.1  412.78  5518.1  412.57  5554.6  409.65  5638.1  413.43  5908.1  419.15
  5948.1  421.52  5968.1  420.24  6148.1  426.73  6628.2  429.25  7114.7  429.33
#Mann= 7 ,-1 , 0
  3033.5     .05       0  4917.1     .12       0  4996.8     .07       0
  5013.1     .12       0  5016.4     .05       0  5358.7     .12       0
  5554.6     .05       0
Bank Sta=4996.8,5013.1
XS Rating Curve= 0 ,0
Exp/Cntr=0.3,0.1

Type RM Length L Ch R = 1 ,56415   ,1630,1630,1630
BEGIN DESCRIPTION:
Big Cottonwood Creek 66.0
END DESCRIPTION:
XS GIS Cut Line= 3
      2660048.36      6899569.61      2658068.61      6899057.56
       2655200.7      6899205.02
#Sta/Elev= 30
  2955.1  427.16  3331.7  427.12  3453.6  425.73  3628.9  426.16  3670.2  427.56
  3876.8  426.29  4047.5  423.38  4250.7  414.76  4434.6  411.72  4646.6  411.76
  4803.9  409.16    4946  410.58  4961.3  409.59  4963.5  402.51  4965.5  402.01
  4979.9  402.51    4982  406.65  4992.4  409.87  5022.6  411.44  5431.1  410.41
  6003.9  415.66  6314.3  422.24  6344.4  424.13  6574.7  427.51  6604.7  427.71
  6634.8  424.33  6654.8  426.82  6744.9  427.17  7125.4   425.7  7871.7  428.52
#Mann= 5 ,-1 , 0
  2955.1     .05       0    4946     .12       0  4963.5     .07       0
  4979.9     .12       0  5431.1     .05       0
Bank Sta=4963.5,4979.9
XS Rating Curve= 0 ,0
Exp/Cntr=0.3,0.1

Type RM Length L Ch R = 1 ,54785   ,868,868,868
BEGIN DESCRIPTION:
Big Cottonwood Creek 63.0
END DESCRIPTION:
XS GIS Cut Line= 3
      2659766.33      6898336.99        2658276.        6898061.
      2656554.48      6898119.97
#Sta/Elev= 30
    3484  426.13    3586  424.37  3697.9  419.06  3809.8  419.02  3840.3  424.21
  3891.1   415.8  4338.6  408.72  4562.4  407.45    4603  409.63  4914.1  409.18
  4948.8  408.58    4959   406.5  4968.1  402.87  4970.9   399.8  4972.9   399.3
  4987.8   399.8  4989.5  403.58  4997.1  408.73  5098.6  409.88  5169.8  410.09
  5209.8  414.63  5229.8  412.21  5249.8  406.72  5349.9  406.31  5369.9   412.1
  5389.9  413.72  5429.9  411.54    5510  412.15  6350.5  423.41  6722.2  424.88
#Mann= 5 ,-1 , 0
    3484     .05       0  4914.1     .12       0  4970.9     .07       0
  4987.8     .12       0  5098.6     .05       0
Bank Sta=4970.9,4987.8
XS Rating Curve= 0 ,0
Exp/Cntr=0.3,0.1

Type RM Length L Ch R = 1 ,53917   ,1598,1598,1598
BEGIN DESCRIPTION:
Big Cottonwood Creek 62.0
END DESCRIPTION:
XS GIS Cut Line= 3
      2659688.88      6897652.67      2658188.85      6897502.67
      2656839.96      6897652.54
#Sta/Elev= 30
    3681  424.36  3844.1  424.29  3955.2  418.84  4452.1  406.51  4547.6  410.03
  4638.6  407.36  4792.7  408.46  4980.3  409.01  5000.4  407.96  5010.5  405.16
    5012  398.13    5014  397.63    5029  398.13  5030.6  401.74  5040.6  407.45
  5050.1  408.57  5131.1  409.09  5192.5  406.53  5211.5  409.36  5489.3  408.16
  5711.3  410.92  6046.6   417.4  6066.7  419.89  6076.8  423.61  6086.9  423.97
    6107  419.48  6177.4  418.99  6218.7  419.49  6247.8  422.05  6545.7  423.83
#Mann= 5 ,-1 , 0
    3681     .05       0  4792.7     .12       0    5012     .07       0
    5029     .12       0  5711.3     .05       0
Bank Sta=5012,5029
XS Rating Curve= 0 ,0
Exp/Cntr=0.3,0.1

Type RM Length L Ch R = 1 ,52319   ,546,546,546
BEGIN DESCRIPTION:
Big Cottonwood Creek 61.0
END DESCRIPTION:
XS GIS Cut Line= 3
      2662376.01        6896461.        2658776.        6896461.
      2656055.35      6896726.74
#Sta/Elev= 30
  1395.3  426.06  2865.3  419.12  3935.3  407.46  3975.3  404.04  4155.3  407.15
  4185.3   403.5  4215.3  407.27  4385.3  407.81  4525.3  404.04  4555.3  406.39
  4575.3  403.05  4605.3   406.9  4739.5  407.15  4905.3  403.68  4985.3  406.64
  5005.4  404.36  5015.4  399.11  5016.8  395.63  5018.8  395.13    5034  395.63
  5035.5  405.09  5055.6  406.96  5668.7   406.2  5878.3  409.08  6588.8   416.5
    6623  420.85  6653.2  417.73  6743.6  417.77  7102.2  422.67  7728.9  421.85
#Mann= 5 ,-1 , 0
  1395.3     .05       0  4739.5     .12       0  5016.8     .07       0
    5034     .12       0  5878.3     .05       0
Bank Sta=5016.8,5034
XS Rating Curve= 0 ,0
Exp/Cntr=0.3,0.1