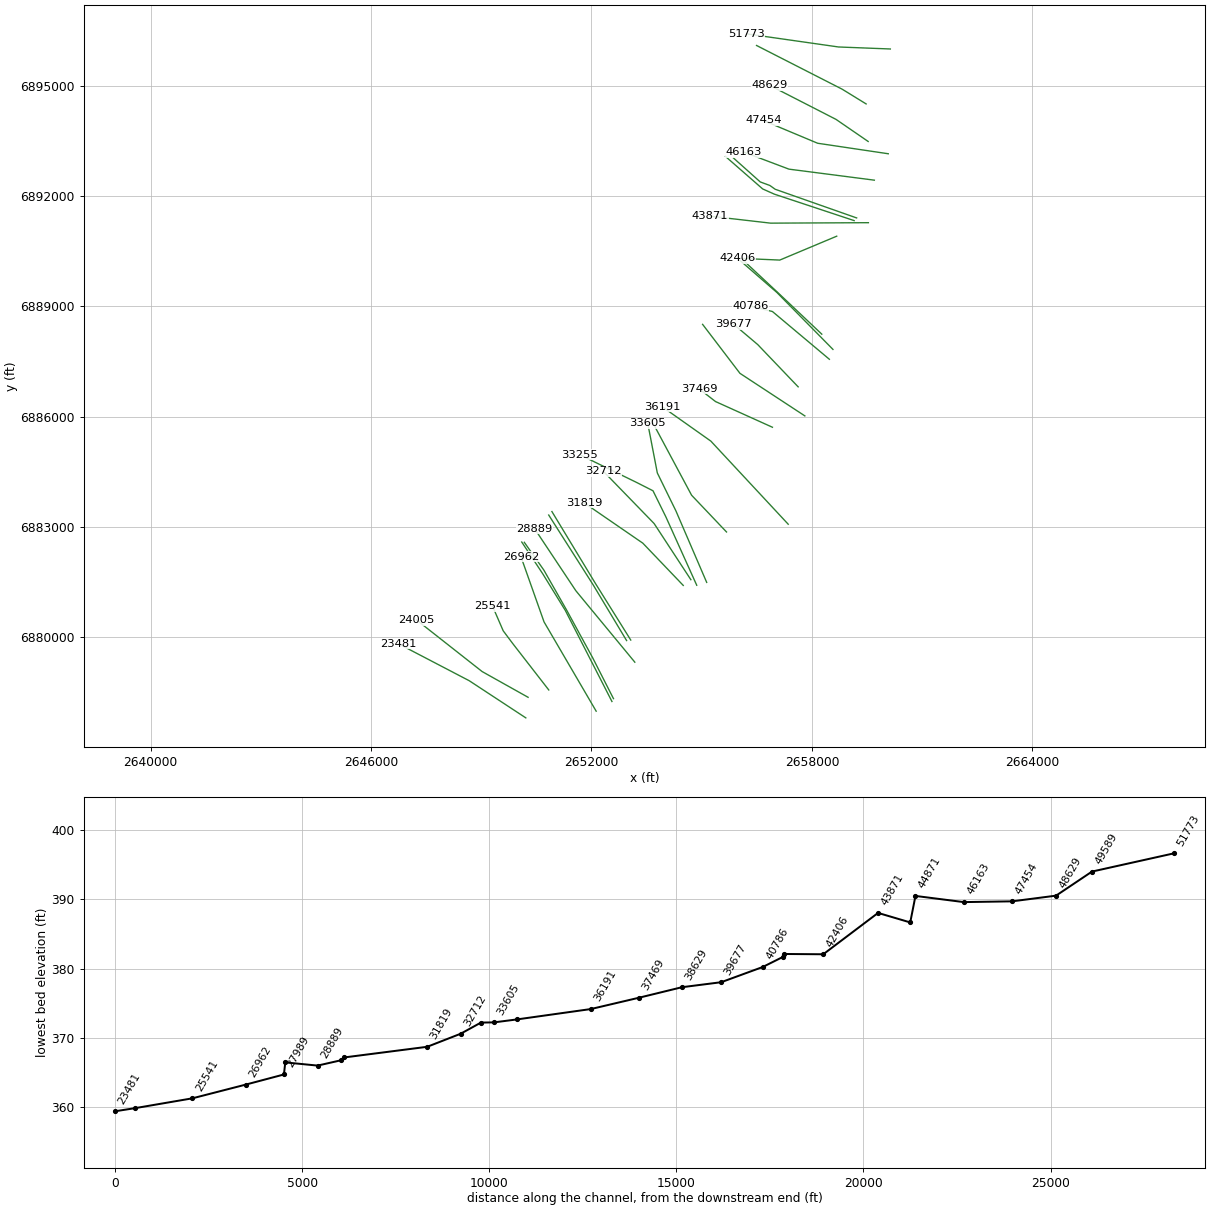
HEC-RAS study Big Cottonwood Creek.prj: Big Cottonwood Creek Base Level Engineering

--- Big Cottonwood Creek.g01 (geometry) --- (continued)

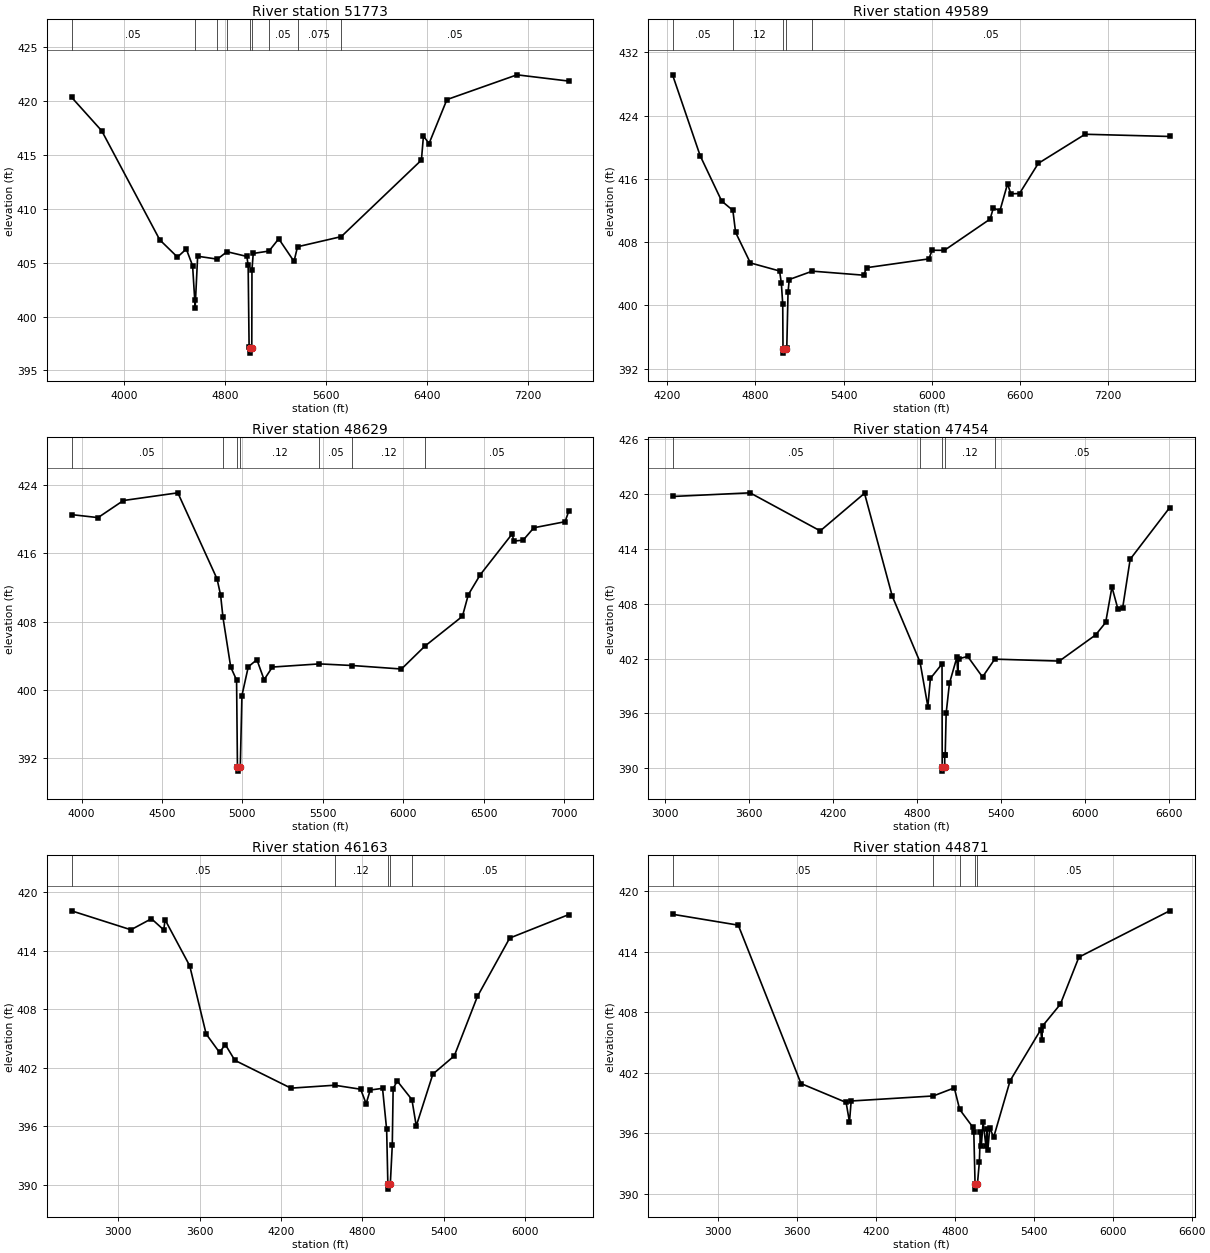
Type RM Length L Ch R = 1 ,51773   ,2184,2184,2184
BEGIN DESCRIPTION:
Big Cottonwood Creek 60.0
END DESCRIPTION:
XS GIS Cut Line= 3
      2660135.19      6896006.26        2658726.        6896061.
      2656220.64      6896418.53
#Sta/Elev= 30
  3582.2  420.37  3821.6  417.25  4281.9  407.12    4422  405.52  4492.1  406.27
  4542.1  404.72  4559.2  401.49  4562.1  400.81  4582.1   405.6  4738.3  405.33
    4815  406.02  4972.4  405.58  4982.4  404.75    4990  397.21    4994   397.1
    4996   396.6  5011.2   397.1  5012.7  404.36  5022.8  405.86  5147.7  406.08
  5224.8  407.22    5346  405.12  5373.8  406.48  5720.4  407.42  6356.1  414.53
    6372  416.76  6416.7  416.07  6558.2  420.15  7113.7  422.45  7523.2  421.87
#Mann= 9 ,-1 , 0
  3582.2     .05       0  4559.2     .12       0  4738.3     .05       0
    4815     .12       0    4994     .07       0  5011.2     .12       0
  5147.7     .05       0  5373.8    .075       0  5720.4     .05       0
Bank Sta=4994,5011.2
XS Rating Curve= 0 ,0
Exp/Cntr=0.3,0.1

Type RM Length L Ch R = 1 ,49589   ,960,960,960
BEGIN DESCRIPTION:
Big Cottonwood Creek 58.0
END DESCRIPTION:
XS GIS Cut Line= 3
      2659476.02      6894510.99        2658826.        6894911.
      2656493.72      6896101.74
#Sta/Elev= 30
  4236.4  429.15  4424.3  418.93  4570.7   413.2  4646.8  412.02  4665.4  409.24
  4765.9  405.38  4964.4  404.36  4976.5  402.85  4986.1  400.17  4987.9  394.48
  4989.9  393.98  5005.6  394.48  5013.6  394.64  5022.1  401.65  5030.2  403.28
  5187.3  404.34  5535.7  403.83  5557.9  404.78  5980.2  405.89  6002.4  406.98
  6085.7  406.97  6396.8  410.92    6419  412.33  6463.5  411.97  6515.4  415.37
  6537.9  414.11  6596.8  414.15  6724.6  417.96  7043.1  421.64  7618.3  421.36
#Mann= 5 ,-1 , 0
  4236.4     .05       0  4646.8     .12       0  4987.9     .07       0
  5005.6     .12       0  5187.3     .05       0
Bank Sta=4987.9,5005.6
XS Rating Curve= 0 ,0
Exp/Cntr=0.3,0.1

Type RM Length L Ch R = 1 ,48629   ,1175,1175,1175
BEGIN DESCRIPTION:
Big Cottonwood Creek 57.0
END DESCRIPTION:
XS GIS Cut Line= 3
      2659531.88      6893488.92      2658656.16      6894090.61
      2656850.93        6895016.
#Sta/Elev= 30
  3937.5  420.53  4102.4  420.18  4260.1  422.18  4598.6  423.08  4842.5     413
  4864.5  411.11  4879.2   408.5  4927.4  402.69  4963.8  401.17  4969.2  391.01
  4971.2  390.51  4986.9  391.01  4997.1  399.36  5036.6  402.72  5090.1  403.55
    5135  401.21  5186.4  402.69  5478.4  403.06  5683.6  402.87  5989.1  402.46
  6134.2  405.13  6368.2  408.63  6404.8  411.16  6479.2   413.5    6679  418.31
  6685.8  417.43  6745.6  417.54  6812.2  418.99  7006.4   419.7  7028.6   420.9
#Mann= 7 ,-1 , 0
  3937.5     .05       0  4879.2     .12       0  4969.2     .07       0
  4986.9     .12       0  5478.4     .05       0  5683.6     .12       0
  6134.2     .05       0
Bank Sta=4969.2,4986.9
XS Rating Curve= 0 ,0
Exp/Cntr=0.3,0.1

Type RM Length L Ch R = 1 ,47454   ,1291,1291,1291
BEGIN DESCRIPTION:
Big Cottonwood Creek 56.0
END DESCRIPTION:
XS GIS Cut Line= 3
       2660078.8      6893154.69      2658156.95      6893440.61
      2656676.04      6894060.98
#Sta/Elev= 30
    3057  419.71  3610.2  420.11  4111.3  415.95  4427.4  420.06  4625.3  408.82
  4823.7  401.61  4879.6  396.75  4897.7  399.82  4980.7  401.41    4982  390.19
    4984  389.69  4999.7  390.19    5000   391.4  5003.2   391.4  5010.2  396.02
  5033.6  399.29    5087  402.14  5092.4  400.47  5098.6  401.96  5163.7  402.23
  5269.7  399.98  5356.9  401.93  5817.9  401.72  6077.4  404.58  6148.8  405.94
  6193.6  409.81    6237  407.37  6269.5  407.47  6323.8  412.85  6605.6  418.49
#Mann= 5 ,-1 , 0
    3057     .05       0  4823.7     .12       0    4982     .07       0
  4999.7     .12       0  5356.9     .05       0
Bank Sta=4982,4999.7
XS Rating Curve= 0 ,0
Exp/Cntr=0.3,0.1

Type RM Length L Ch R = 1 ,46163   ,1292,1292,1292
BEGIN DESCRIPTION:
Big Cottonwood Creek 55.0
END DESCRIPTION:
XS GIS Cut Line= 3
      2659700.35      6892435.94      2657375.34      6892736.01
      2656139.41       6893202.7
#Sta/Elev= 30
  2655.7  418.08  3093.7  416.14  3244.9  417.27  3335.6  416.13  3345.7  417.16
  3527.2  412.45  3648.2  405.47    3747  403.58  3789.4  404.39    3860  402.77
  4273.4  399.92  4595.5  400.22  4787.6  399.81  4827.9  398.33  4858.2  399.73
  4948.9   399.9  4979.2  395.69  4988.2  390.08  4990.2  389.58  5006.1  390.08
  5020.7  394.08  5027.1  399.88  5057.3  400.65  5165.4  398.75  5197.6  396.05
    5320  401.36  5478.1  403.23  5648.5  409.31  5886.5  415.29  6321.1  417.69
#Mann= 5 ,-1 , 0
  2655.7     .05       0  4595.5     .12       0  4988.2     .07       0
  5006.1     .12       0  5165.4     .05       0
Bank Sta=4988.2,5006.1
XS Rating Curve= 0 ,0
Exp/Cntr=0.3,0.1

Type RM Length L Ch R = 1 ,44871   ,140,140,140
BEGIN DESCRIPTION:
Big Cottonwood Creek 54.0
END DESCRIPTION:
XS GIS Cut Line= 5
      2659217.72      6891408.15      2657002.14      6892187.94
      2656858.36      6892290.36      2656595.28      6892387.33
      2655867.48      6893037.16
#Sta/Elev= 30
  2651.2   417.7  3151.3  416.62  3628.3  400.93  3971.5  399.06  3997.1  397.12
    4010   399.2  4634.8   399.7  4794.5   400.5  4835.4  398.36  4935.8   396.6
  4942.9  396.11  4952.4  390.97  4954.4  390.47  4970.4  390.97  4985.3   393.2
  4992.4  396.12    5000  394.79  5013.8  397.12  5034.7  394.76  5043.3  396.42
  5049.4  394.31  5064.2  396.57  5093.5  395.59    5219  401.21  5451.9  406.26
  5459.8  405.21  5466.3  406.64  5600.9  408.78  5742.2  413.45  6432.6  418.04
#Mann= 5 ,-1 , 0
  2651.2     .05       0  4634.8     .12       0  4835.4     .05       0
  4952.4     .03       0  4970.4     .05       0
Bank Sta=4952.4,4970.4
XS Rating Curve= 0 ,0
Exp/Cntr=0.3,0.1

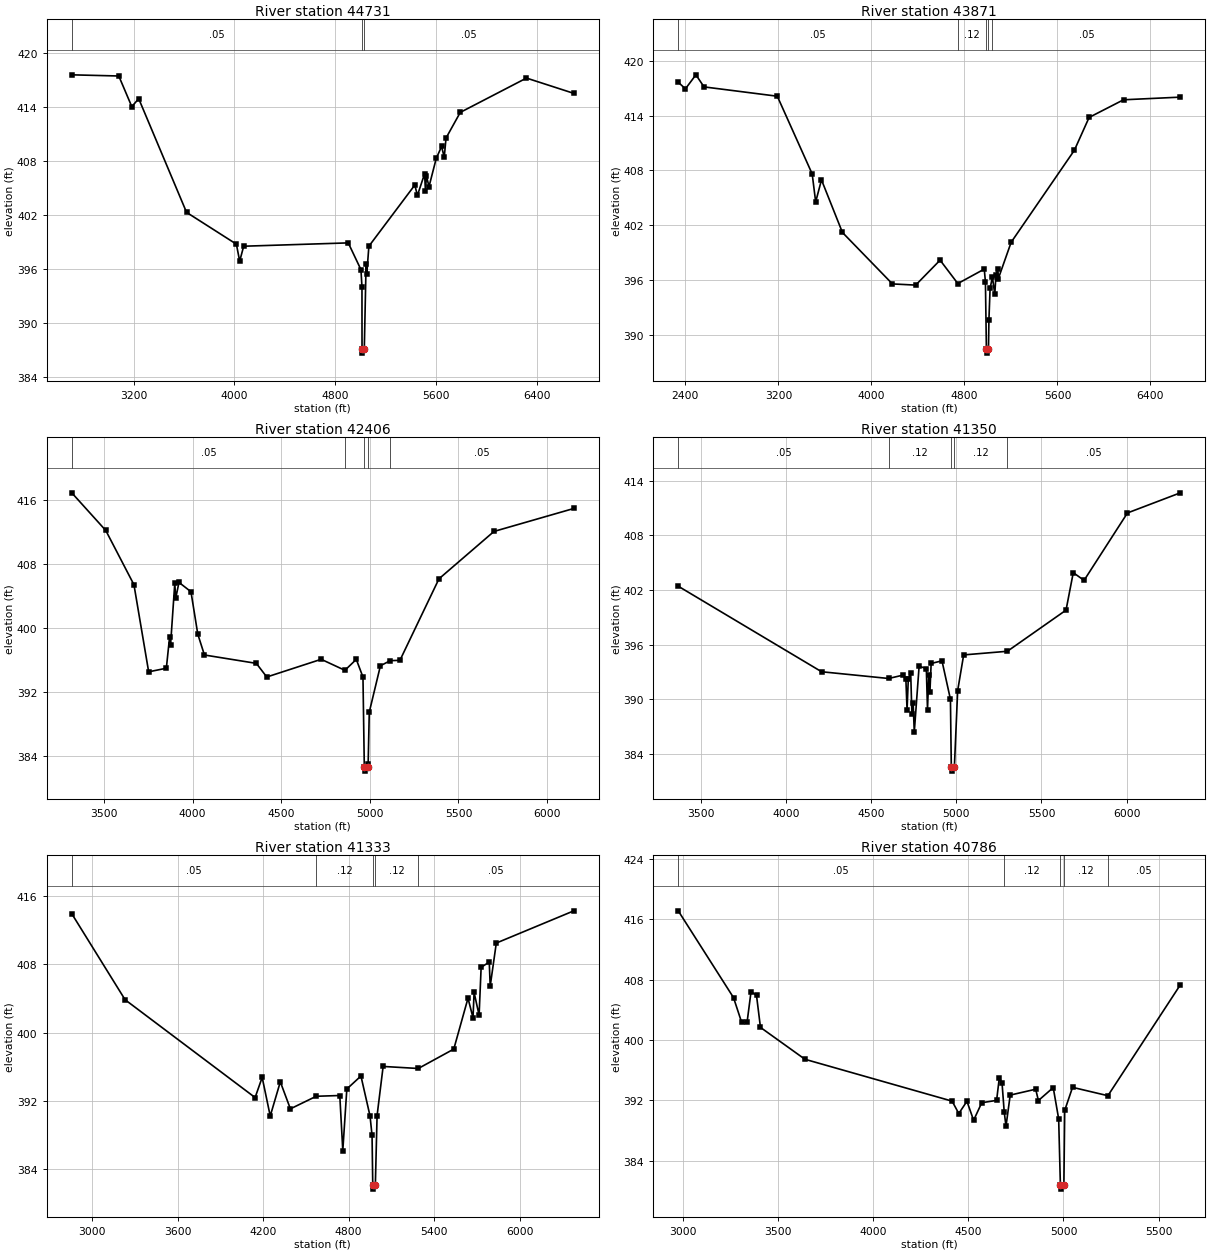
Type RM Length L Ch R = 1 ,44731   ,860,860,860
BEGIN DESCRIPTION:
Big Cottonwood Creek 53.0
END DESCRIPTION:
XS GIS Cut Line= 4
      2659149.97      6891335.25      2656975.94      6892056.03
      2656660.39      6892197.23      2655647.39      6893082.63
#Sta/Elev= 30
  2709.6  417.55  3082.5  417.42  3185.6  414.02  3240.5   414.9  3619.8  402.28
  4014.9  398.75  4041.2  396.86  4072.8  398.52  4902.2  398.89  5002.7  395.92
  5010.9     394  5011.3  387.15  5013.3  386.65  5029.4  387.15  5043.6  396.58
  5049.1  395.44  5065.7  398.52  5429.8  405.31  5450.7  404.16  5507.6  406.57
  5514.3  404.64  5521.9   406.3  5542.7  405.15  5599.7  408.26  5642.4   409.6
  5663.3  408.39  5677.5  410.53  5790.5  413.38  6315.4  417.19  6691.1  415.49
#Mann= 3 ,-1 , 0
  2709.6     .05       0  5011.3     .03       0  5029.4     .05       0
Bank Sta=5011.3,5029.4
XS Rating Curve= 0 ,0
Exp/Cntr=0.3,0.1

Type RM Length L Ch R = 1 ,43871   ,1465,1465,1465
BEGIN DESCRIPTION:
Big Cottonwood Creek 52.0
END DESCRIPTION:
XS GIS Cut Line= 3
      2659537.95      6891278.57      2656876.37      6891266.16
      2655230.85      6891455.63
#Sta/Elev= 30
  2338.4  417.65  2400.3  416.93  2490.3  418.46  2560.3  417.14  3190.4  416.12
  3490.4  407.62  3520.4  404.56  3570.4  406.97  3750.4  401.22  4180.4  395.59
  4380.4  395.46  4590.4  398.19    4743  395.63  4970.4  397.21  4980.4  395.79
  4988.6  388.52  4990.6  388.02  5006.7  388.52  5010.4  391.69  5020.5   395.1
  5040.4  396.34  5060.8  394.44  5070.8  396.56    5086  397.19    5091  396.16
  5201.7  400.15  5745.3  410.21    5872   413.8    6168  415.73  6656.4  416.02
#Mann= 5 ,-1 , 0
  2338.4     .05       0    4743     .12       0  4988.6     .07       0
  5006.7     .12       0  5040.4     .05       0
Bank Sta=4988.6,5006.7
XS Rating Curve= 0 ,0
Exp/Cntr=0.3,0.1

Type RM Length L Ch R = 1 ,42406   ,1056,1056,1056
BEGIN DESCRIPTION:
Big Cottonwood Creek 50.0
END DESCRIPTION:
XS GIS Cut Line= 3
      2658675.98      6890910.99        2657126.        6890261.
      2655976.04        6890311.
#Sta/Elev= 30
  3318.8  416.95  3510.6  412.23  3669.5  405.43  3752.5  394.51  3852.2  394.96
  3870.6  398.88    3876   397.9  3899.7  405.59  3905.2  403.75  3923.5  405.72
  3991.1  404.55  4029.5  399.24    4067  396.62  4359.8  395.57  4418.6  393.86
  4725.5  396.08  4859.3   394.7  4923.6  396.07  4961.2  393.85  4968.8  382.56
  4970.8  382.06  4986.9  382.56  4990.4  382.91  4996.8  389.46  5059.6  395.27
  5115.2  395.91  5169.7  395.95  5389.9  406.17  5700.2  412.11  6150.6  414.99
#Mann= 5 ,-1 , 0
  3318.8     .05       0  4859.3     .12       0  4968.8     .07       0
  4986.9     .12       0  5115.2     .05       0
#XS Ineff= 2 , 0
       0  3923.5  405.72               0
Permanent Ineff=
       F       F
Bank Sta=4968.8,4986.9
XS Rating Curve= 0 ,0
Exp/Cntr=0.3,0.1

Type RM Length L Ch R = 1 ,41350   ,17,17,17
BEGIN DESCRIPTION:
Big Cottonwood Creek 49.0
END DESCRIPTION:
XS GIS Cut Line= 3
      2658269.79      6888244.34      2657082.62      6889367.24
      2656121.29      6890265.23
#Sta/Elev= 30
  3365.9  402.42  4208.1  393.02  4601.8  392.28  4689.1  392.66  4703.3  392.17
  4710.2  388.81  4717.4   392.2  4731.6  392.87  4738.5  388.42  4745.8  389.64
  4752.6  386.38    4781  393.63  4823.4  393.37  4830.3  388.84  4837.6  392.68
  4844.5  390.79  4851.7  393.93  4915.3  394.22    4965     390  4970.1   382.6
  4972.1   382.1  4988.3   382.6  5007.5  390.95  5042.7  394.87  5299.5  395.27
  5644.1  399.79  5686.6  403.91  5750.1  403.06  6005.1  410.47  6315.5  412.68
#Mann= 5 ,-1 , 0
  3365.9     .05       0  4601.8     .12       0  4970.1     .07       0
  4988.3     .12       0  5299.5     .05       0
Bank Sta=4970.1,4988.3
XS Rating Curve= 0 ,0
Exp/Cntr=0.3,0.1

Type RM Length L Ch R = 1 ,41333   ,547,547,547
BEGIN DESCRIPTION:
Big Cottonwood Creek 48.0
END DESCRIPTION:
XS GIS Cut Line= 3
      2658573.57      6887829.45       2657049.4      6889377.37
      2656029.74      6890262.34
#Sta/Elev= 30
  2858.2   413.9  3232.4  403.84  4144.5   392.4    4194  394.76  4250.6  390.24
  4321.3  394.24    4392  391.08  4573.3  392.55  4738.6  392.64  4759.7   386.2
    4788   393.4    4887  394.92  4950.7  390.25  4964.9  387.98  4969.9  382.19
  4971.9  381.69  4988.1  382.19  5000.2  390.29  5042.7  396.04  5289.4   395.8
  5538.4  398.07  5638.1  404.02  5673.2  401.74  5680.9  404.69    5716  402.03
  5730.2  407.63  5787.2  408.25  5793.9  405.43  5836.6  410.47  6380.7  414.24
#Mann= 5 ,-1 , 0
  2858.2     .05       0  4573.3     .12       0  4969.9     .07       0
  4988.1     .12       0  5289.4     .05       0
Bank Sta=4969.9,4988.1
XS Rating Curve= 0 ,0
Exp/Cntr=0.3,0.1

Type RM Length L Ch R = 1 ,40786   ,1109,1109,1109
BEGIN DESCRIPTION:
Big Cottonwood Creek 47.0
END DESCRIPTION:
XS GIS Cut Line= 3
      2658476.01      6887560.99        2656926.        6888861.
      2656325.97      6889011.01
#Sta/Elev= 30
  2973.1  417.13  3263.9  405.62  3306.8  402.33  3335.4  402.38  3356.2  406.42
  3384.9  405.91  3405.7  401.67  3639.9  397.44  4413.9  391.89  4449.1  390.25
    4492  391.87  4527.1  389.35    4570  391.68  4648.1  391.99  4662.4     395
  4676.7  394.29  4688.1  390.46  4697.5  388.56  4719.6  392.69  4853.7  393.47
    4868  391.97    4946  393.69  4974.6  389.54  4983.7  380.72  4985.7  380.22
    5002  380.72  5006.4  390.66  5047.6  393.72  5233.6  392.61  5614.6  407.31
#Mann= 5 ,-1 , 0
  2973.1     .05       0  4688.1     .12       0  4983.7     .07       0
    5002     .12       0  5233.6     .05       0
Bank Sta=4983.7,5002
XS Rating Curve= 0 ,0
Exp/Cntr=0.3,0.1

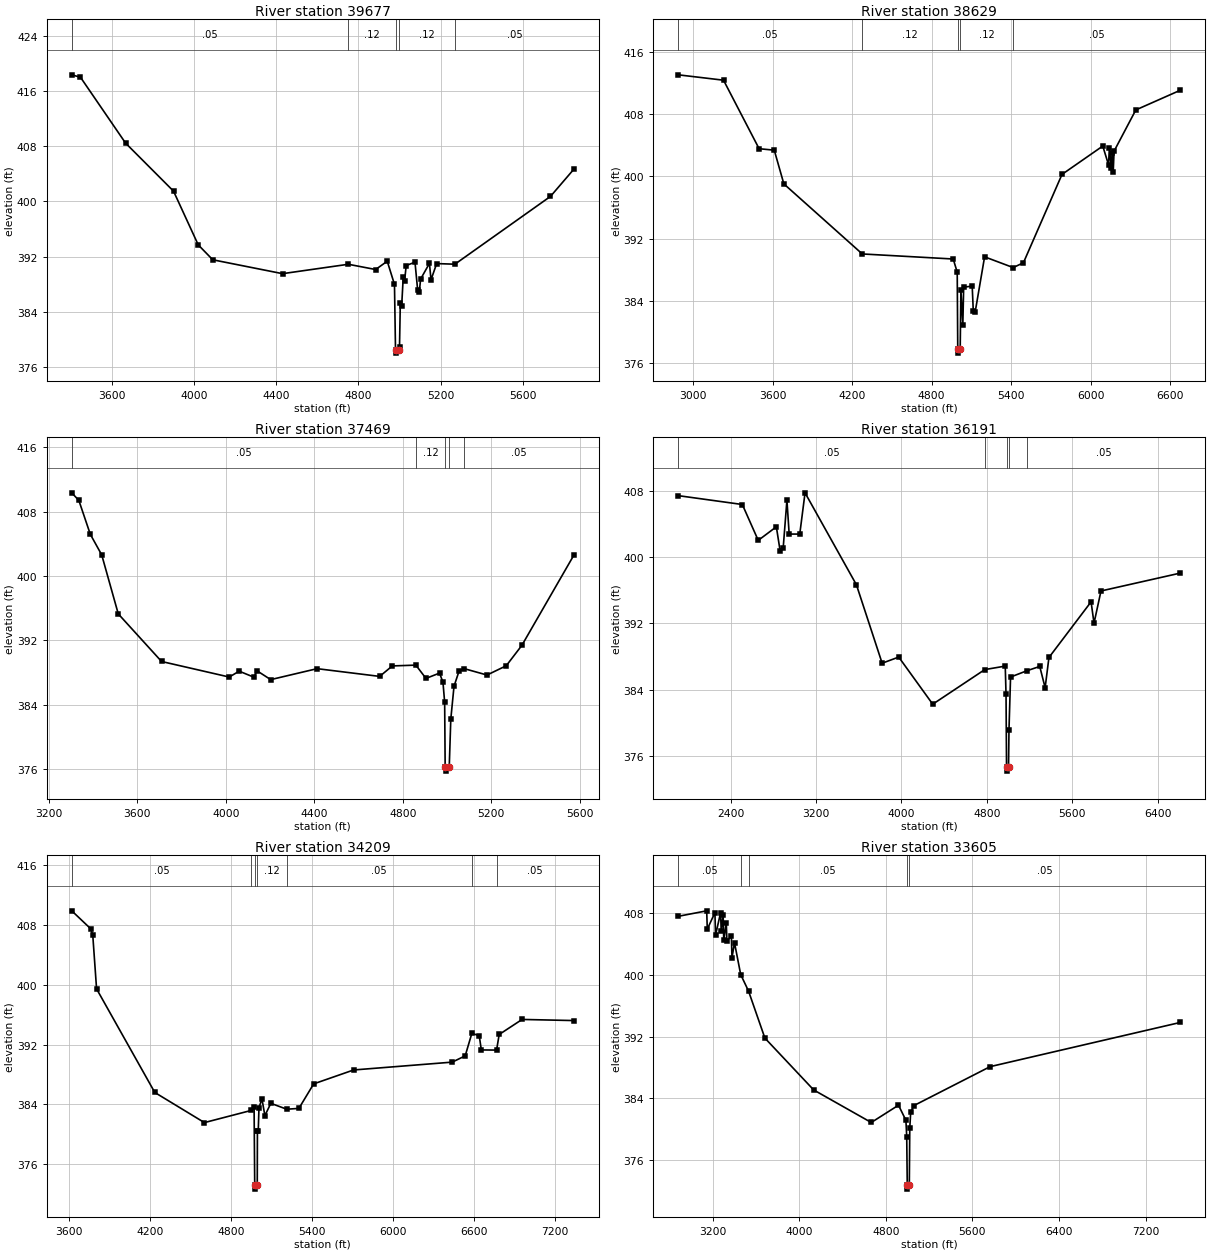
Type RM Length L Ch R = 1 ,39677   ,1048,1048,1048
BEGIN DESCRIPTION:
Big Cottonwood Creek 45.0
END DESCRIPTION:
XS GIS Cut Line= 3
      2657625.97      6886811.03        2656526.        6887961.
      2655876.01      6888510.99
#Sta/Elev= 30
    3405  418.34  3447.3  417.99  3666.8  408.45  3900.1  401.49  4020.3  393.71
    4091  391.55  4430.4  389.54  4750.6   390.9  4883.3  390.14  4939.9  391.34
  4975.1  387.98  4980.1  378.53  4982.1  378.03  4998.4  378.53  4999.6  378.98
  5003.5  385.32    5010  384.82  5017.8  389.07  5024.3   388.5  5032.1  390.72
  5074.9   391.2    5088  387.14  5095.8  386.87  5102.3  388.76  5145.2  391.03
  5152.9  388.65  5180.3     391  5269.1  390.91  5734.1  400.73  5847.8  404.67
#Mann= 5 ,-1 , 0
    3405     .05       0  4750.6     .12       0  4980.1     .07       0
  4998.4     .12       0  5269.1     .05       0
Bank Sta=4980.1,4998.4
XS Rating Curve= 0 ,0
Exp/Cntr=0.3,0.1

Type RM Length L Ch R = 1 ,38629   ,1160,1160,1160
BEGIN DESCRIPTION:
Big Cottonwood Creek 43.0
END DESCRIPTION:
XS GIS Cut Line= 3
      2657808.62      6886019.73      2656042.38       6887178.1
        2655026.        6888511.
#Sta/Elev= 30
  2887.8  413.06  3229.6  412.37  3497.9  403.57  3612.4  403.38  3684.7  399.05
  4276.4  390.05  4962.7   389.4  4992.9   387.7  4996.9  377.81  4998.9  377.31
  5015.3  377.81  5020.6  385.44  5035.2  380.97  5041.5  385.78  5105.9  385.92
  5114.1  382.69  5128.7  382.63  5199.4  389.68  5415.3   388.3  5492.4  388.92
  5783.5  400.27  6091.1  403.91  6134.7   401.5    6141  403.69  6155.5  401.09
  6161.8  403.08    6170  400.62  6176.3  403.25  6340.5  408.55  6676.2  411.08
#Mann= 5 ,-1 , 0
  2887.8     .05       0  4276.4     .12       0  4996.9     .07       0
  5015.3     .12       0  5415.3     .05       0
Bank Sta=4996.9,5015.3
XS Rating Curve= 0 ,0
Exp/Cntr=0.3,0.1

Type RM Length L Ch R = 1 ,37469   ,1278,1278,1278
BEGIN DESCRIPTION:
Big Cottonwood Creek 41.0
END DESCRIPTION:
XS GIS Cut Line= 3
      2656926.02      6885710.99        2655376.        6886411.
      2654926.04      6886760.97
#Sta/Elev= 30
  3303.1  410.33  3335.1  409.39  3386.8  405.19  3438.5  402.63  3513.4   395.3
  3709.3  389.39  4015.4  387.46  4060.2  388.19  4126.1  387.45  4141.9  388.22
  4202.9  387.14  4412.7   388.5  4695.7  387.54  4752.9  388.84  4859.4  388.94
  4905.1  387.29  4966.4  387.95  4981.9  386.82  4989.6  384.33  4991.9  376.28
  4993.9  375.78  5010.3  376.28  5017.4  382.25  5031.9  386.31  5054.5  388.18
    5077  388.51  5181.2  387.71  5268.1  388.86  5338.7  391.39  5573.9  402.59
#Mann= 5 ,-1 , 0
  3303.1     .05       0  4859.4     .12       0  4991.9     .07       0
  5010.3     .12       0    5077     .05       0
Bank Sta=4991.9,5010.3
XS Rating Curve= 0 ,0
Exp/Cntr=0.3,0.1

Type RM Length L Ch R = 1 ,36191   ,1982,1982,1982
BEGIN DESCRIPTION:
Big Cottonwood Creek 38.0
END DESCRIPTION:
XS GIS Cut Line= 3
      2657355.53      6883071.79      2655250.01      6885333.67
      2653933.66      6886264.49
#Sta/Elev= 30
  1909.8  407.42  2510.1  406.35  2659.1  402.02  2828.7  403.66  2864.3  400.74
  2892.4  401.05  2927.8  406.88  2948.8  402.78    3048  402.78  3097.4  407.76
  3578.6  396.66  3819.5  387.19  3974.9  387.93  4293.4  382.24    4781  386.42
  4972.5  386.84  4979.9  383.42  4984.7  374.66  4986.7  374.16  5003.3  374.66
  5007.5  379.13  5022.3  385.52  5173.7  386.27  5295.6   386.8  5346.1  384.23
  5381.8  387.88  5776.5   394.6  5803.9  392.02  5869.2  395.91  6612.2  398.07
#Mann= 5 ,-1 , 0
  1909.8     .05       0    4781     .12       0  4984.7     .07       0
  5003.3     .12       0  5173.7     .05       0
Bank Sta=4984.7,5003.3
XS Rating Curve= 0 ,0
Exp/Cntr=0.3,0.1

Type RM Length L Ch R = 1 ,34209   ,604,604,604
BEGIN DESCRIPTION:
Big Cottonwood Creek 36.0
END DESCRIPTION:
XS GIS Cut Line= 3
        2655676.        6882861.        2654726.        6883861.
      2653620.74      6885925.44
#Sta/Elev= 30
  3620.7  409.89  3762.1  407.47  3776.2  406.66  3804.5  399.45  4236.1  385.59
  4603.8  381.56  4951.1  383.19  4971.9  383.58  4976.6  373.16  4978.6  372.66
  4995.4  373.16  4996.6  380.46  5002.8  380.46  5008.1  383.56  5030.1  384.72
    5052  382.49  5095.9  384.14  5213.8  383.35  5303.9  383.46  5413.6  386.74
  5709.4   388.6  6440.6  389.65  6536.5  390.49  6585.9  393.51  6640.5  393.18
  6656.1  391.28    6769  391.26  6788.4  393.35  6958.2  395.36  7341.7  395.21
#Mann= 7 ,-1 , 0
  3620.7     .05       0  4951.1     .12       0  4976.6     .07       0
  4995.4     .12       0  5213.8     .05       0  6585.9    .075       0
    6769     .05       0
Bank Sta=4976.6,4995.4
XS Rating Curve= 0 ,0
Exp/Cntr=0.3,0.1

Type RM Length L Ch R = 1 ,33605   ,350,350,350
BEGIN DESCRIPTION:
Big Cottonwood Creek 35.0
END DESCRIPTION:
XS GIS Cut Line= 4
      2655136.77      6881488.48      2654299.07      6883434.33
      2653793.03      6884467.63      2653533.41      6885813.55
#Sta/Elev= 30
  2881.5  407.61  3144.5  408.32    3150  405.94  3220.6  408.09    3226  405.15
  3273.1  408.09  3278.5  405.72  3296.6  407.72  3302.1   404.5  3325.6  406.79
    3331  404.44  3372.7  405.02  3378.1  402.25  3401.6  404.17  3458.7  400.06
  3531.6   397.9  3682.3  391.82  4133.1   385.1  4665.3  380.88    4917  383.12
  4985.5  381.16    4993  379.06    4998  372.74    5000  372.24  5016.9  372.74
  5021.2  380.15  5029.7  382.23  5060.7  383.08  5763.8  388.12  7521.3  393.85
#Mann= 5 ,-1 , 0
  2881.5     .05       0  3458.7    .075       0  3531.6     .05       0
    4998     .03       0  5016.9     .05       0
Bank Sta=4998,5016.9
XS Rating Curve= 0 ,0
Exp/Cntr=0.3,0.1

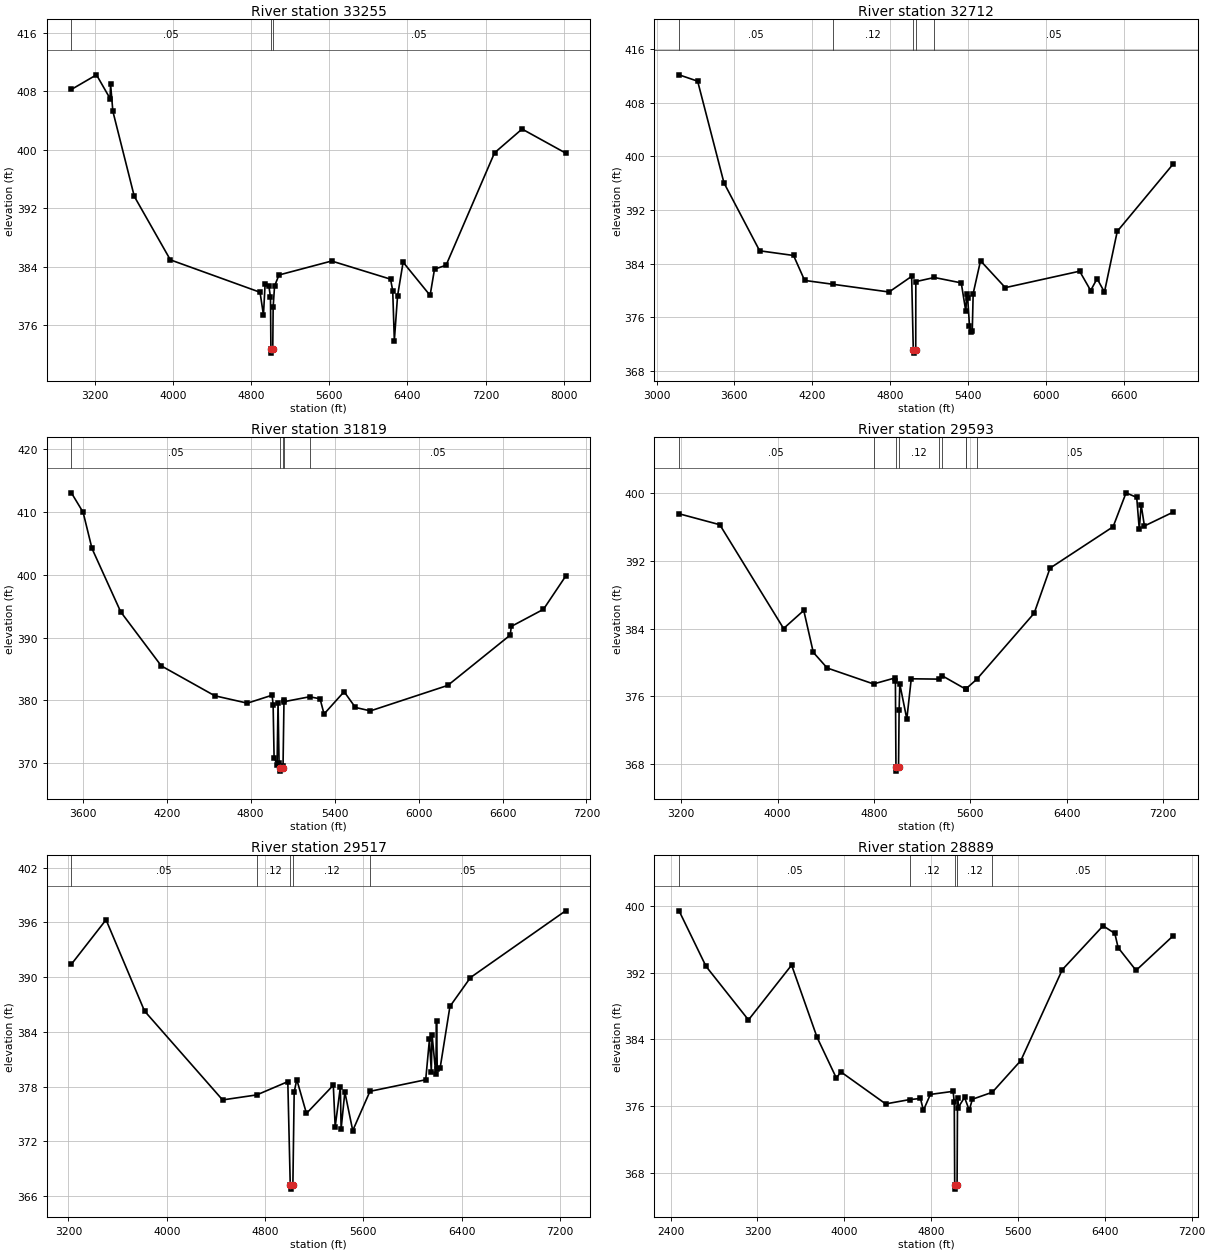
Type RM Length L Ch R = 1 ,33255   ,543,543,543
BEGIN DESCRIPTION:
Big Cottonwood Creek 34.0
END DESCRIPTION:
XS GIS Cut Line= 5
      2654865.92      6881410.38      2654028.17      6883267.14
      2653675.72      6883981.94       2653225.5      6884210.49
      2651683.66      6884962.41
#Sta/Elev= 30
    2963  408.25  3219.8  410.25  3358.6  407.01  3364.1  408.94  3387.2  405.27
  3606.3  393.64  3975.2  384.96  4892.5  380.53  4927.4  377.42  4944.2  381.62
  4982.3  381.45  4999.4  379.83  5003.6  372.71  5005.6  372.21  5022.5  372.71
  5026.6  378.53  5041.1  381.38    5086  382.89  5624.9   384.8  6227.1  382.32
  6249.3  380.76    6266  373.93  6298.8  380.02  6355.7  384.64  6631.7   380.1
  6676.8  383.69    6795  384.22  7290.7  399.59  7572.2  402.84  8017.3  399.56
#Mann= 3 ,-1 , 0
    2963     .05       0  5003.6     .03       0  5022.5     .05       0
Bank Sta=5003.6,5022.5
XS Rating Curve= 0 ,0
Exp/Cntr=0.3,0.1

Type RM Length L Ch R = 1 ,32712   ,893,893,893
BEGIN DESCRIPTION:
Big Cottonwood Creek 33.0
END DESCRIPTION:
XS GIS Cut Line= 3
      2654706.23      6881561.36      2653706.41       6883089.9
      2652325.98      6884511.02
#Sta/Elev= 30
  3173.5  412.21  3316.7  411.26  3519.6  396.05  3794.4   385.9  4055.6   385.2
    4141  381.47  4356.9   380.9  4791.4  379.74  4965.5  382.08  4978.1   371.1
  4980.1   370.6    4997   371.1  4997.7  381.29  5140.2  381.91  5347.7   381.1
  5382.9  376.84  5390.1  379.51  5397.1  378.86  5411.2  374.66  5425.4  373.72
  5432.5  373.84  5439.5  379.51  5496.1  384.41    5687  380.39  6259.8  382.85
  6344.7  379.96  6394.3  381.73  6450.9  379.73  6549.7  388.81  6981.2  398.89
#Mann= 5 ,-1 , 0
  3173.5     .05       0  4356.9     .12       0  4978.1     .07       0
    4997     .12       0  5140.2     .05       0
Bank Sta=4978.1,4997
XS Rating Curve= 0 ,0
Exp/Cntr=0.3,0.1

Type RM Length L Ch R = 1 ,31819   ,2226,2226,2226
BEGIN DESCRIPTION:
Big Cottonwood Creek 32.0
END DESCRIPTION:
XS GIS Cut Line= 3
       2654499.1      6881405.63      2653399.09      6882555.64
      2651800.03      6883654.99
#Sta/Elev= 30
  3518.8  413.07  3602.6  409.97  3666.1   404.2  3871.5   394.1  4161.5  385.49
  4543.3  380.73  4776.6  379.55  4953.4  380.82  4960.6  379.29  4967.5  370.87
  4988.9  369.77  4995.8  379.64  5003.1  369.95  5006.6  369.22  5008.7  368.72
  5027.9  369.22  5031.4  369.49  5038.3  380.01  5039.7  379.79  5221.1  380.57
    5296  380.25  5324.5  377.82  5467.9  381.38  5548.4  378.87    5656  378.32
  6208.7  382.38  6655.1   390.4  6662.7  391.78  6892.7  394.51  7050.7  399.77
#Mann= 5 ,-1 , 0
  3518.8     .05       0  5006.6     .03       0  5027.9     .05       0
  5039.7     .12       0  5221.1     .05       0
Bank Sta=5006.6,5027.9
XS Rating Curve= 0 ,0
Exp/Cntr=0.3,0.1

Type RM Length L Ch R = 1 ,29593   ,76,76,76
BEGIN DESCRIPTION:
Big Cottonwood Creek 29.0
END DESCRIPTION:
XS GIS Cut Line= 3
      2653069.93      6879919.03       2652112.1      6881453.66
      2650924.21      6883416.24
#Sta/Elev= 30
  3182.2  397.53  3520.3  396.24    4050     384  4217.5  386.13  4296.5  381.19
  4412.1  379.34  4796.8  377.46  4972.4  378.16  4978.3  377.76  4982.9  367.68
    4985  367.18  5004.4  367.68  5009.1  374.33    5015  377.44  5073.2  373.33
    5110  378.07  5339.1  378.03  5367.5  378.42  5564.7  376.83  5566.7  376.92
    5653     378  6130.3   385.8  6262.2  391.12  6785.9     396  6893.4     400
  6981.8  399.46  7003.1   395.7  7018.6  398.59  7045.8  396.09  7285.3  397.73
#Mann= 9 ,-1 , 0
  3182.2     .05       0  4796.8     .12       0  4982.9     .07       0
  5004.4     .12       0  5339.1     .05       0  5367.5     .12       0
  5564.7     .05       0  5566.7     .12       0    5653     .05       0
Bank Sta=4982.9,5004.4
XS Rating Curve= 0 ,0
Exp/Cntr=0.3,0.1

Type RM Length L Ch R = 1 ,29517   ,628,628,628
BEGIN DESCRIPTION:
Big Cottonwood Creek 28.0
END DESCRIPTION:
XS GIS Cut Line= 3
      2652956.89      6879905.26      2652042.48      6881428.11
      2650837.14      6883321.86
#Sta/Elev= 30
  3223.7  391.41  3505.8  396.28  3818.7  386.29  4454.1  376.55  4732.4   377.1
  4984.7  378.55  5004.5  367.28  5006.7  366.78    5026  367.28  5036.5  377.41
  5057.7  378.78  5136.4  375.07  5354.9  378.16  5370.1  373.62  5412.4  377.97
  5418.4  373.38  5448.8   377.4  5513.1  373.19  5653.1  377.49  6106.7  378.76
  6137.1  383.17  6152.4  379.65  6158.3   383.7  6188.8  379.41  6194.7   385.2
  6200.6  379.93  6224.4  380.08  6303.9  386.79  6470.7  389.95  7244.8  397.26
#Mann= 5 ,-1 , 0
  3223.7     .05       0  4732.4     .12       0  5004.5     .07       0
    5026     .12       0  5653.1     .05       0
Bank Sta=5004.5,5026
XS Rating Curve= 0 ,0
Exp/Cntr=0.3,0.1

Type RM Length L Ch R = 1 ,28889   ,864,864,864
BEGIN DESCRIPTION:
Big Cottonwood Creek 27.0
END DESCRIPTION:
XS GIS Cut Line= 3
      2653180.88      6879316.66        2651576.        6881261.
      2650451.73      6882952.05
#Sta/Elev= 30
  2478.3  399.45  2726.6  392.78  3117.5  386.34  3514.8  392.93  3749.4  384.25
  3926.5  379.37  3969.5  380.09  4381.2  376.25  4602.2  376.77  4701.2   376.9
  4729.1  375.49  4792.9  377.39  5002.4  377.76    5013  376.43  5017.1  366.51
  5019.3  366.01  5038.9  366.51    5043  376.94    5049  375.81  5107.5  377.03
  5151.2   375.5  5179.6  376.81  5363.5  377.65  5626.2  381.46  6008.1  392.38
  6383.8  397.65    6492  396.73  6522.1  395.03  6687.4  392.29  7030.1  396.46
#Mann= 5 ,-1 , 0
  2478.3     .05       0  4602.2     .12       0  5017.1     .07       0
  5038.9     .12       0  5363.5     .05       0
Bank Sta=5017.1,5038.9
XS Rating Curve= 0 ,0
Exp/Cntr=0.3,0.1

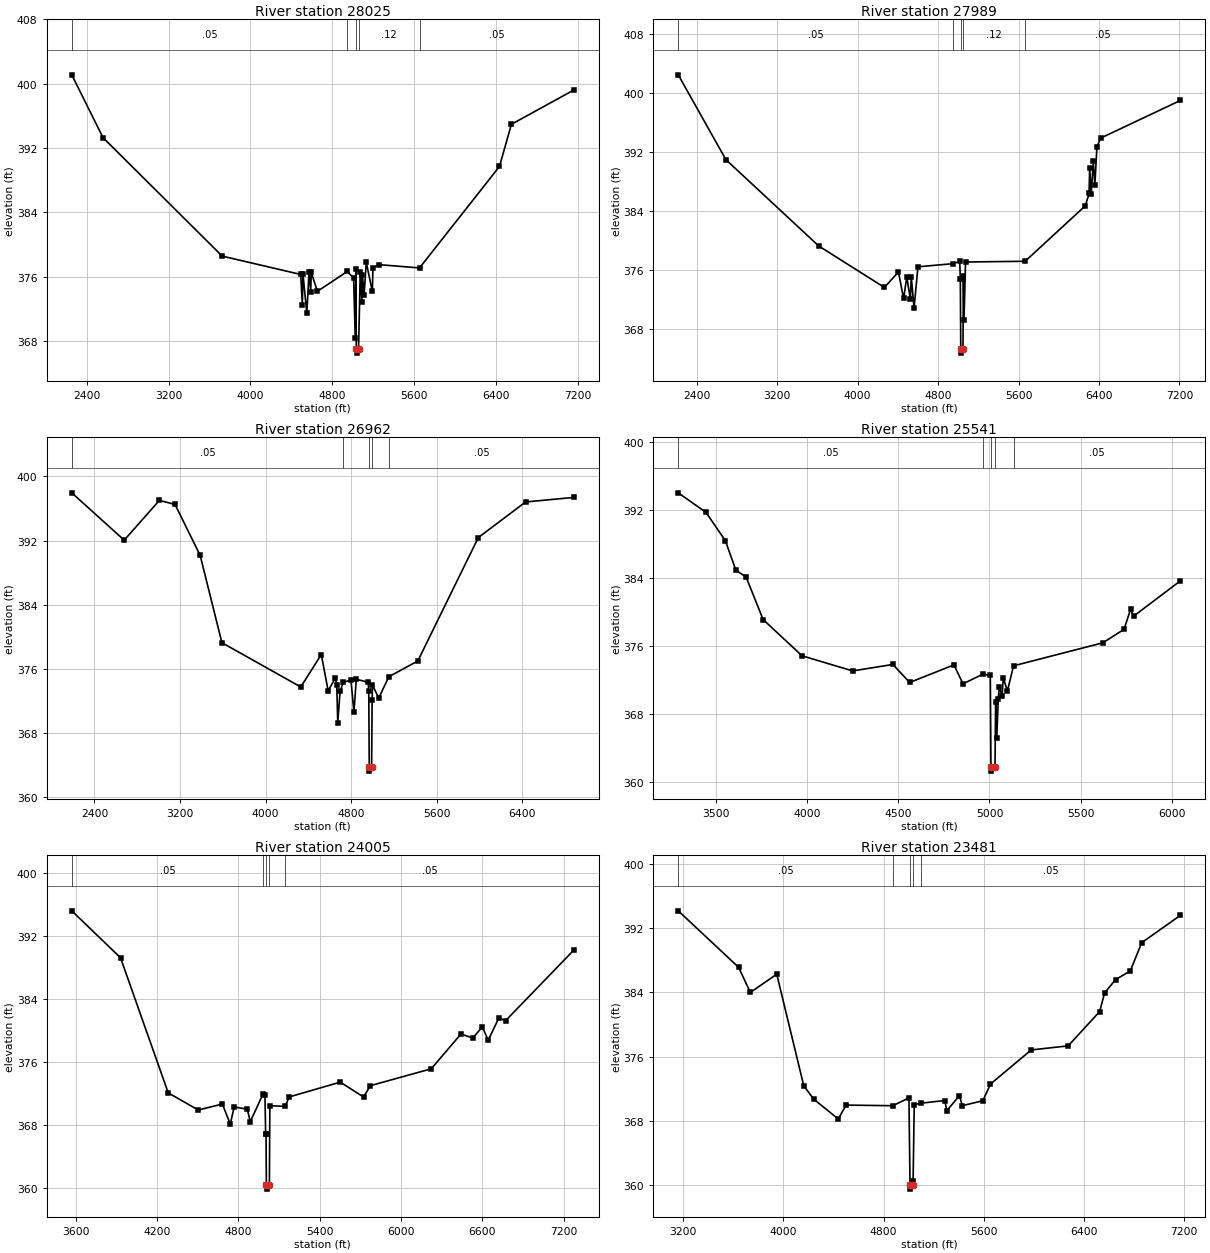
Type RM Length L Ch R = 1 ,28025   ,36,36,36
BEGIN DESCRIPTION:
Mapping XS 80937f9b
END DESCRIPTION:
XS GIS Cut Line= 5
      2652599.88      6878324.37      2652032.19      6879438.93
      2651323.85       6880735.8      2650704.06      6881824.35
       2650172.8      6882579.57
#Sta/Elev= 30
  2254.4   401.1  2559.8  393.28  3724.1  378.54  4490.7  376.26  4506.8  372.48
  4512.5  376.35  4550.5  371.44  4572.3  376.59  4588.4  374.12  4594.1  376.51
  4653.9  374.16  4945.3  376.63  5007.5  375.82  5023.4   368.4  5029.1  376.94
  5034.1  366.97  5036.2  366.47  5055.9  366.97  5072.4   376.6  5088.2  372.86
    5094  376.14  5109.8  373.76  5131.4  377.75  5190.5  374.14  5196.3   377.1
  5255.4  377.48  5651.4  377.07  6432.6   389.7  6548.5  394.94  7158.9  399.21
#Mann= 5 ,-1 , 0
  2254.4     .05       0  4945.3     .12       0  5034.1     .07       0
  5055.9     .12       0  5651.4     .05       0
Bank Sta=5034.1,5055.9
XS Rating Curve= 0 ,0
Exp/Cntr=0.3,0.1

Type RM Length L Ch R = 1 ,27989   ,1027,1027,1027
BEGIN DESCRIPTION:
Big Cottonwood Creek 26.0
END DESCRIPTION:
XS GIS Cut Line= 4
      2652558.22      6878246.24      2651289.66       6880724.2
      2650671.25      6881727.47      2650103.24      6882586.76
#Sta/Elev= 30
  2216.2  402.48  2690.3  390.97  3611.8  379.28  4266.2  373.64  4405.6  375.74
  4457.2  372.14  4488.8  375.05  4524.6  372.03  4533.2  375.12    4561  370.82
  4599.8  376.44  4944.7  376.86  5015.2  377.17  5021.1  374.79  5025.6  365.23
  5027.7  364.73  5047.4  365.23  5051.9  375.25  5057.7  369.28  5073.1  377.09
  5665.7  377.19  6265.2  384.73  6301.3   386.4  6307.3  389.87  6322.4  386.26
  6343.4  390.73  6358.5  387.47  6379.5  392.72  6415.6  393.89  7208.6     399
#Mann= 5 ,-1 , 0
  2216.2     .05       0  4944.7     .12       0  5025.6     .07       0
  5047.4     .12       0  5665.7     .05       0
Bank Sta=5025.6,5047.4
XS Rating Curve= 0 ,0
Exp/Cntr=0.3,0.1

Type RM Length L Ch R = 1 ,26962   ,1421,1421,1421
BEGIN DESCRIPTION:
Big Cottonwood Creek 25.0
END DESCRIPTION:
XS GIS Cut Line= 3
       2652128.8      6877983.32      2650710.42      6880411.97
      2650081.98      6882186.27
#Sta/Elev= 30
  2187.5  397.95  2677.9  392.05    3007  397.01  3153.3   396.5    3388  390.15
  3591.4  379.27  4328.8  373.75  4520.6  377.79  4585.1  373.27  4651.5  374.86
  4665.3  374.03  4674.6  369.31  4696.7  373.23  4727.4  374.36  4798.4  374.59
  4825.7  370.62  4848.3  374.72  4958.8  374.33  4964.6  373.28  4969.2  363.76
  4971.4  363.26  4991.3  363.76    4996  372.08  4999.4  373.99  5057.7  372.37
  5152.5  375.03  5423.3  376.99  5988.8  392.37  6430.9  396.81  6882.3  397.38
#Mann= 5 ,-1 , 0
  2187.5     .05       0  4727.4     .12       0  4969.2     .07       0
  4991.3     .12       0  5152.5     .05       0
Bank Sta=4969.2,4991.3
XS Rating Curve= 0 ,0
Exp/Cntr=0.3,0.1

Type RM Length L Ch R = 1 ,25541   ,1536,1536,1536
BEGIN DESCRIPTION:
Big Cottonwood Creek 22.0
END DESCRIPTION:
XS GIS Cut Line= 4
      2650838.48      6878560.68      2649855.54      6879827.16
      2649598.77      6880170.37      2649311.09      6880834.01
#Sta/Elev= 30
  3292.2  394.06  3444.5  391.76  3550.6  388.43  3608.5  384.95  3664.6  384.15
  3757.9  379.14  3971.5  374.87  4249.3  373.09  4469.8  373.85  4562.5  371.73
  4805.1   373.8  4854.9  371.57  4964.2  372.71  5004.7  372.57  5008.2  361.79
  5010.4  361.29  5030.4  361.79  5033.9  369.47  5040.1  365.23  5048.5  369.84
  5054.7  371.25  5069.3  370.09  5075.6  372.27  5098.5  370.74  5132.2  373.69
  5622.3   376.4  5738.8  377.99    5774  380.33    5792  379.55  6047.3  383.69
#Mann= 5 ,-1 , 0
  3292.2     .05       0  4964.2     .12       0  5008.2     .07       0
  5030.4     .12       0  5132.2     .05       0
Bank Sta=5008.2,5030.4
XS Rating Curve= 0 ,0
Exp/Cntr=0.3,0.1

Type RM Length L Ch R = 1 ,24005   ,524,524,524
BEGIN DESCRIPTION:
Big Cottonwood Creek 20.0
END DESCRIPTION:
XS GIS Cut Line= 3
      2650275.97      6878361.02        2649026.        6879061.
      2647241.67      6880464.21
#Sta/Elev= 30
  3571.8  395.19  3931.4  389.23    4283  372.09  4504.4  369.91  4682.5  370.67
  4740.8  368.12  4769.3   370.3  4866.3  370.01    4888  368.43  4981.8  371.92
  4996.4  371.85  5001.6  366.87  5004.4  366.87  5006.9  360.37  5009.1  359.87
  5029.2  360.37  5032.5  370.46  5145.2  370.37  5175.2  371.57  5552.1  373.45
  5723.7  371.56  5773.5     373  6222.6  375.14  6442.2  379.56  6528.9  379.04
  6599.4  380.47  6642.8  378.76  6721.4   381.6  6771.1  381.25  7274.4  390.21
#Mann= 5 ,-1 , 0
  3571.8     .05       0  4981.8     .12       0  5006.9     .07       0
  5029.2     .12       0  5145.2     .05       0
Bank Sta=5006.9,5029.2
XS Rating Curve= 0 ,0
Exp/Cntr=0.3,0.1

Type RM Length L Ch R = 1 ,23481   ,951,951,951
BEGIN DESCRIPTION:
Big Cottonwood Creek 19.0
END DESCRIPTION:
XS GIS Cut Line= 3
       2650213.9      6877801.02        2648676.        6878811.
      2646752.07      6879814.93
#Sta/Elev= 30
  3159.5   394.2  3641.9  387.14  3735.3     384  3946.3  386.28  4161.9  372.35
  4241.5  370.67  4437.1   368.2  4500.7  369.93  4873.4  369.85  5002.2  370.83
  5010.7  359.93    5013  359.43  5033.1  359.93  5035.3  360.44  5044.5  369.98
  5098.6  370.17  5289.1   370.5  5303.9  369.21  5405.5  371.12    5428  369.85
  5592.7  370.48  5653.3  372.56    5979  376.82    6274  377.33  6525.6  381.62
  6564.1  383.92  6652.4  385.61  6770.3  386.69  6860.5  390.21  7169.5  393.63
#Mann= 5 ,-1 , 0
  3159.5     .05       0  4873.4     .12       0  5010.7     .07       0
  5033.1     .12       0  5098.6     .05       0
Bank Sta=5010.7,5033.1
XS Rating Curve= 0 ,0
Exp/Cntr=0.3,0.1