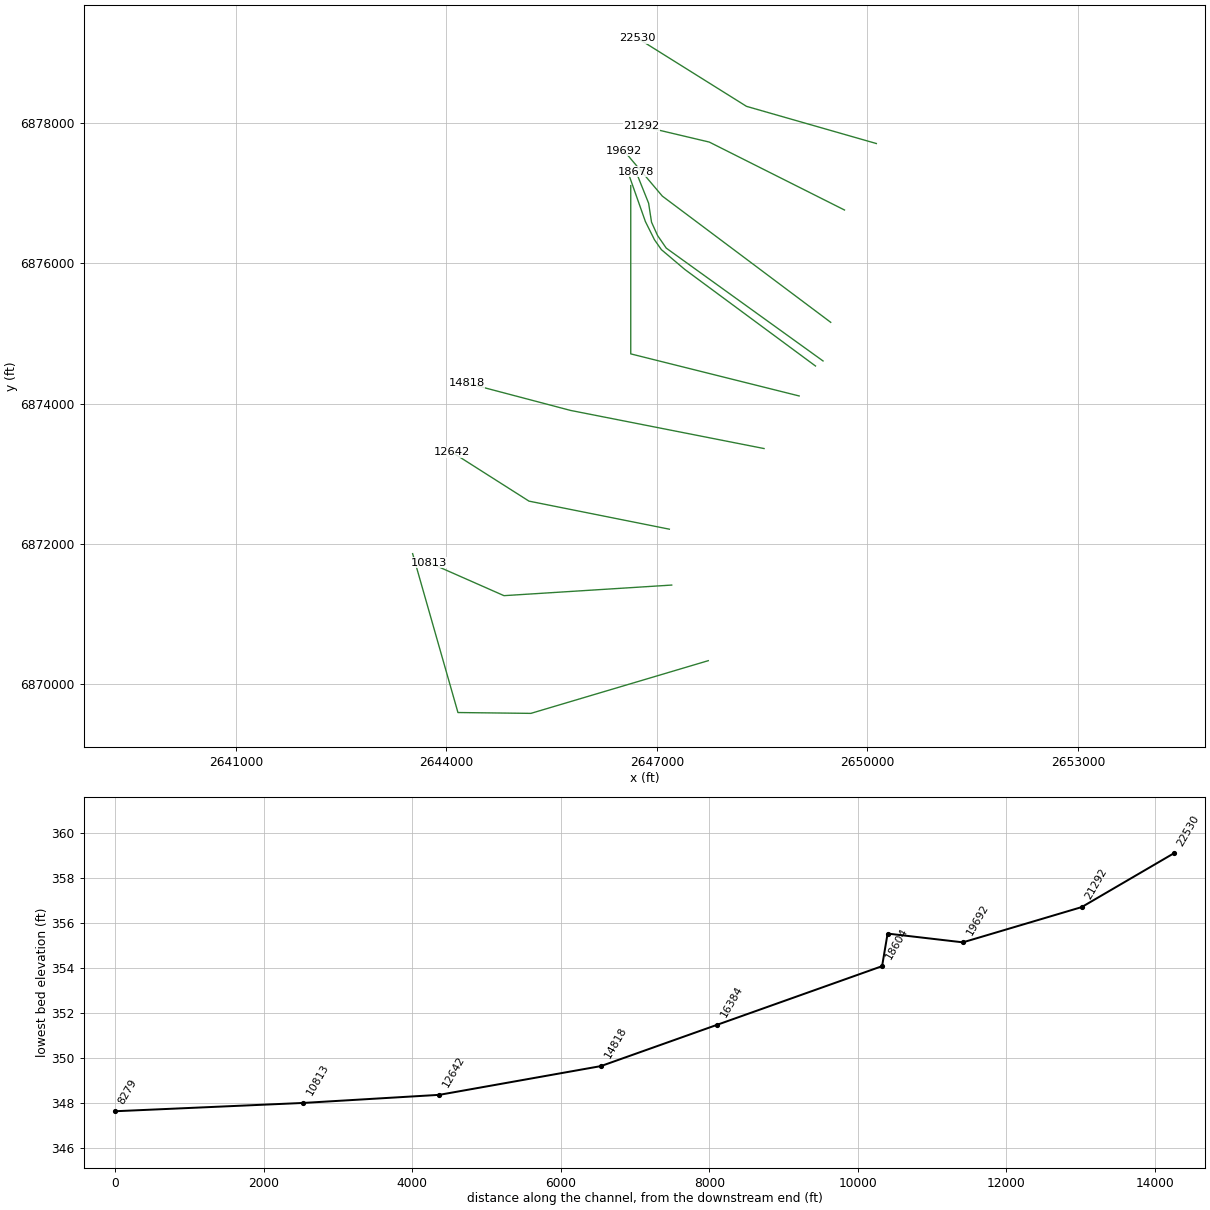
HEC-RAS study Big Cottonwood Creek.prj: Big Cottonwood Creek Base Level Engineering

--- Big Cottonwood Creek.g01 (geometry) --- (continued)

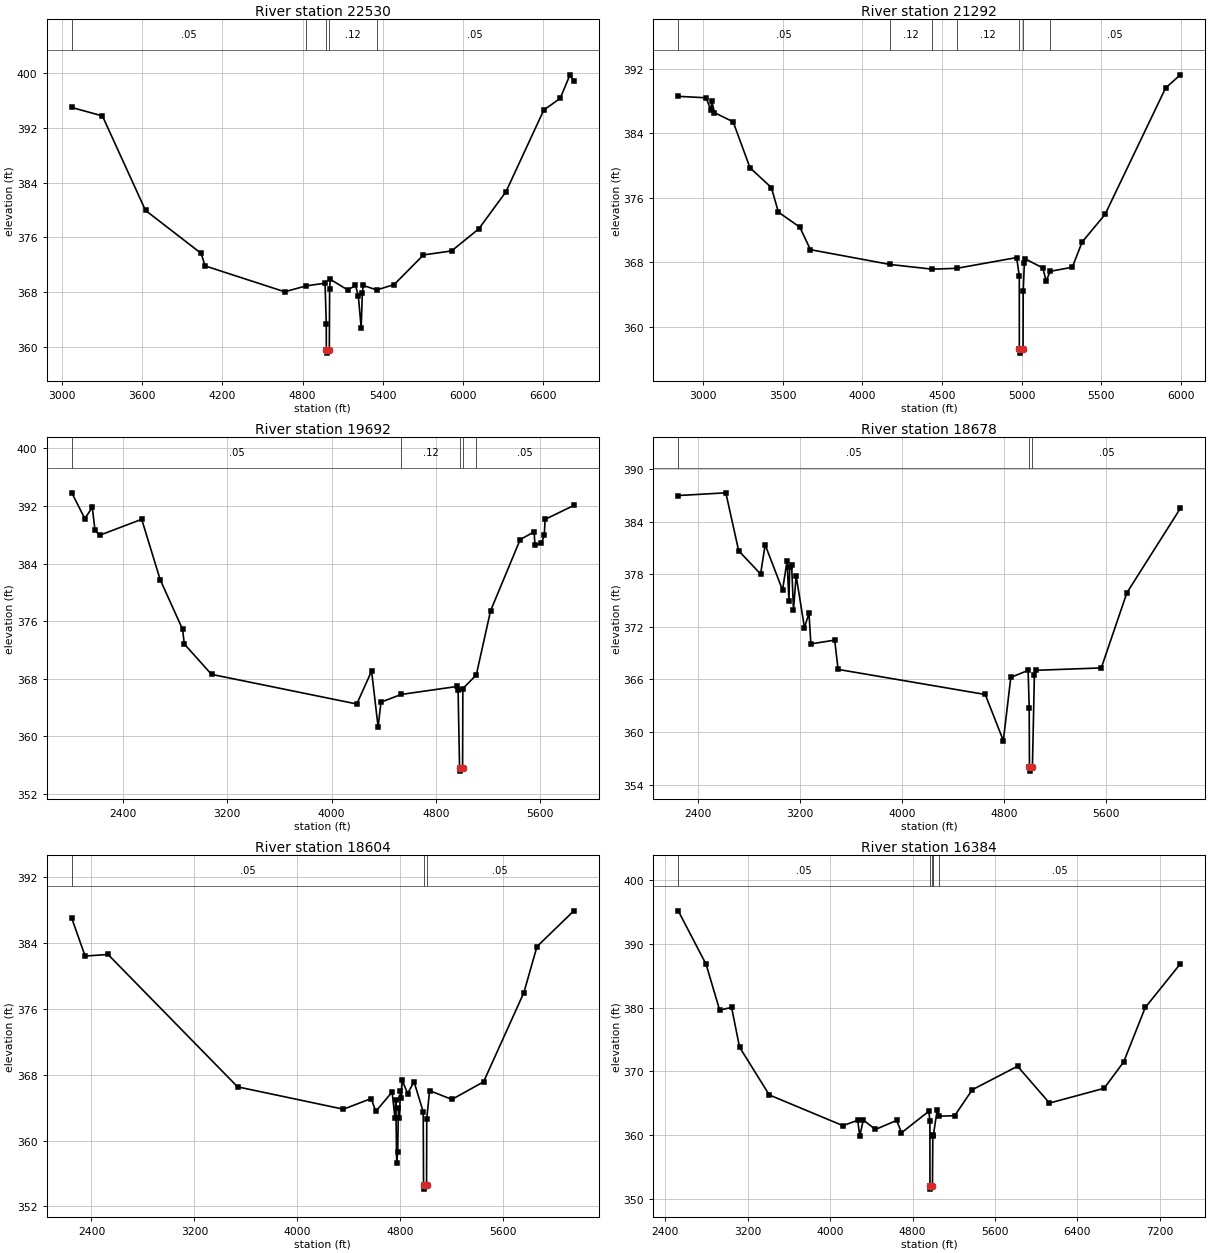
Type RM Length L Ch R = 1 ,22530   ,1238,1238,1238
BEGIN DESCRIPTION:
Big Cottonwood Creek 17.0
END DESCRIPTION:
XS GIS Cut Line= 3
      2650126.02      6877710.99      2648275.75      6878241.07
      2646725.96      6879211.03
#Sta/Elev= 30
  3075.3  394.98  3304.2  393.75  3626.6  379.95  4042.7  373.67  4071.3  371.85
  4666.9  368.07  4829.4  368.94  4968.5  369.32  4977.7  363.42  4978.1  359.61
  4980.4  359.11  5000.5  359.61  5002.8  368.46  5007.4  369.89  5138.3  368.33
  5196.1     369  5217.3  367.46  5238.5  362.82  5247.4  367.88  5253.8  368.99
  5355.1  368.34  5484.9  369.12  5704.2  373.45    5914  374.03    6118  377.26
    6321  382.68  6604.1  394.62  6726.3  396.31  6799.4  399.75  6828.3  398.85
#Mann= 5 ,-1 , 0
  3075.3     .05       0  4829.4     .12       0  4978.1     .07       0
  5000.5     .12       0  5355.1     .05       0
Bank Sta=4978.1,5000.5
XS Rating Curve= 0 ,0
Exp/Cntr=0.3,0.1

Type RM Length L Ch R = 1 ,21292   ,1600,1600,1600
BEGIN DESCRIPTION:
Big Cottonwood Creek 16.0
END DESCRIPTION:
XS GIS Cut Line= 3
      2649672.23      6876762.83      2647745.38      6877731.65
      2646776.04      6877960.99
#Sta/Elev= 30
  2843.3  388.59  3018.2  388.41  3048.4  386.87    3054  387.99  3070.7  386.57
    3188  385.43    3294  379.72  3427.9  377.27  3472.6  374.21  3606.5  372.36
  3673.5  369.56  4174.6  367.72  4438.1  367.14  4593.5  367.25  4968.2  368.58
    4985  366.27  4985.3  357.22  4987.6  356.72  5008.5  357.22  5009.6  364.39
  5016.8  367.91    5022  368.42  5132.9  367.29  5153.9  365.65  5178.4  366.87
  5317.9  367.38  5379.6  370.51  5523.4  373.93  5903.7  389.62  5996.1  391.26
#Mann= 7 ,-1 , 0
  2843.3     .05       0  4174.6     .12       0  4438.1     .05       0
  4593.5     .12       0  4985.3     .07       0  5008.5     .12       0
  5178.4     .05       0
Bank Sta=4985.3,5008.5
XS Rating Curve= 0 ,0
Exp/Cntr=0.3,0.1

Type RM Length L Ch R = 1 ,19692   ,1014,1014,1014
BEGIN DESCRIPTION:
Big Cottonwood Creek 14.0
END DESCRIPTION:
XS GIS Cut Line= 3
        2649476.        6875161.        2647076.        6876961.
      2646525.98      6877611.02
#Sta/Elev= 30
  2007.2  393.83  2107.2  390.25  2164.5  391.81  2185.3  388.63  2220.7  387.93
  2543.7  390.15  2685.3  381.76  2857.2  374.86  2870.7  372.81  3079.1   368.6
  4193.7  364.48  4307.2  369.06  4357.2  361.28  4379.1  364.74    4535  365.81
  4964.5  366.92  4970.7  366.49    4982  355.65  4984.4  355.15  5005.3  355.65
  5007.2  366.61  5110.3  368.52  5219.8  377.43  5447.2  387.34  5553.8   388.4
  5560.4  386.59  5609.8  386.79  5631.8  387.93  5638.4  390.14  5858.7  392.08
#Mann= 5 ,-1 , 0
  2007.2     .05       0    4535     .12       0    4982     .07       0
  5005.3     .12       0  5110.3     .05       0
Bank Sta=4982,5005.3
XS Rating Curve= 0 ,0
Exp/Cntr=0.3,0.1

Type RM Length L Ch R = 1 ,18678   ,74,74,74
BEGIN DESCRIPTION:
Mapping XS 014f277f
END DESCRIPTION:
XS GIS Cut Line= 6
       2649366.6       6874610.1      2647131.93      6876219.44
      2647007.83      6876399.33      2646922.19      6876589.24
      2646880.53      6876860.08      2646700.47      6877310.21
#Sta/Elev= 30
  2246.1  386.97  2619.6  387.28  2720.3  380.67  2892.4  378.02    2928  381.36
  3064.4  376.19    3100  379.51  3114.8  374.96  3120.9  378.78  3135.7  379.09
  3150.4  373.93  3171.3  377.82  3236.4  371.92  3272.1  373.55  3286.8  370.05
  3473.6  370.48  3500.6  367.14    4655  364.28    4797  359.02  4855.6  366.23
  4991.5  367.03    5000  362.79    5002  356.04  5004.3  355.54  5025.3  356.04
  5040.6  366.47  5055.5  367.04  5565.7  367.31  5766.5  375.88  6185.7   385.5
#Mann= 3 ,-1 , 0
  2246.1     .05       0    5002     .03       0  5025.3     .05       0
Bank Sta=5002,5025.3
XS Rating Curve= 0 ,0
Exp/Cntr=0.3,0.1

Type RM Length L Ch R = 1 ,18604   ,2220,2220,2220
BEGIN DESCRIPTION:
Big Cottonwood Creek 13.0
END DESCRIPTION:
XS GIS Cut Line= 6
      2649258.86      6874538.22      2647396.72      6875914.96
      2647062.78      6876197.38      2646964.42       6876337.7
      2646834.79      6876598.04      2646605.77      6877247.13
#Sta/Elev= 30
  2246.6  387.03  2350.4  382.44  2528.6  382.63  3535.8  366.53  4359.1  363.81
  4574.9  365.11  4610.1  363.54  4737.5   365.9  4759.5  362.79  4766.1  364.91
  4773.1  357.22  4780.4  358.58  4786.9  363.91  4794.7  362.71  4801.2  365.98
    4809  365.22  4815.5  367.33  4858.4  365.72  4907.8  367.16  4979.3  363.49
  4981.9  354.59  4984.3  354.09  5005.2  354.59  5006.8  362.67  5028.8  366.07
  5202.2     365  5448.5  367.14  5762.2     378  5863.6  383.59  6150.5  387.94
#Mann= 3 ,-1 , 0
  2246.6     .05       0  4981.9     .03       0  5005.2     .05       0
Bank Sta=4981.9,5005.2
XS Rating Curve= 0 ,0
Exp/Cntr=0.3,0.1

Type RM Length L Ch R = 1 ,16384   ,1566,1566,1566
BEGIN DESCRIPTION:
Big Cottonwood Creek 12.0
END DESCRIPTION:
XS GIS Cut Line= 3
      2649025.97      6874111.01        2646626.        6874711.
        2646626.      6877110.97
#Sta/Elev= 30
  2525.8  395.21  2796.3   386.8  2927.8  379.61  3043.7  380.03    3121  373.79
  3409.7  366.28  4123.5  361.46  4267.8  362.29  4288.4  359.81  4321.9  362.34
  4440.4  360.86  4646.6  362.28    4693  360.33  4958.4  363.72  4968.7  362.23
  4969.6  351.98    4972  351.48  4993.5  351.98  4997.1  359.84  5002.8  360.01
  5039.6   363.9  5061.3  362.94  5209.6  363.02  5379.6  367.09  5819.6  370.79
  6129.6     365  6659.6  367.32  6849.6  371.46  7059.6  380.03  7399.6  386.87
#Mann= 5 ,-1 , 0
  2525.8     .05       0  4969.6     .03       0  4993.5     .05       0
  5002.8     .12       0  5061.3     .05       0
Bank Sta=4969.6,4993.5
XS Rating Curve= 0 ,0
Exp/Cntr=0.3,0.1

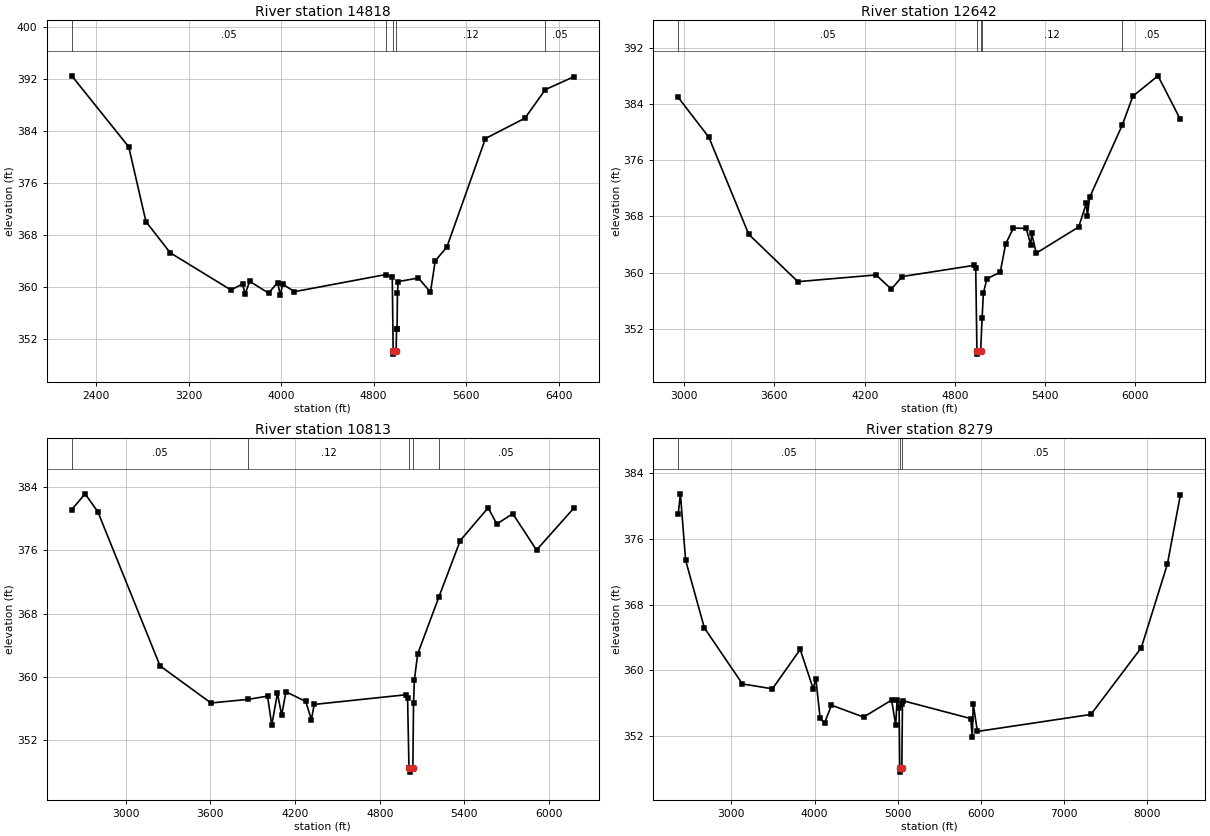
Type RM Length L Ch R = 1 ,14818   ,2176,2176,2176
BEGIN DESCRIPTION:
Big Cottonwood Creek 9.0
END DESCRIPTION:
XS GIS Cut Line= 3
      2648525.98        6873361.      2645767.57      6873904.81
      2644286.56       6874295.2
#Sta/Elev= 30
  2188.5  392.51  2681.2  381.57  2830.1  370.05  3040.5  365.25  3564.5  359.53
  3666.7  360.44  3686.8  358.86  3727.5  360.86  3890.6  359.04  3969.6  360.67
  3992.5   358.7  4012.9  360.42  4114.9  359.26  4902.6  361.89  4960.8  361.58
  4968.7  350.14  4971.2  349.64  4993.7  350.14  4998.3  353.51  5002.3  353.51
  5005.7  359.07    5012  360.82  5187.8  361.36  5291.2  359.18  5332.6  364.01
  5433.5  366.15  5766.9  382.85  6108.3  385.98  6285.2  390.39  6531.6  392.37
#Mann= 5 ,-1 , 0
  2188.5     .05       0  4902.6     .12       0  4968.7     .07       0
  4993.7     .12       0  6285.2     .05       0
Bank Sta=4968.7,4993.7
XS Rating Curve= 0 ,0
Exp/Cntr=0.3,0.1

Type RM Length L Ch R = 1 ,12642   ,1829,1829,1829
BEGIN DESCRIPTION:
Big Cottonwood Creek 6.0
END DESCRIPTION:
XS GIS Cut Line= 3
      2647176.02        6872211.        2645176.        6872611.
      2644079.64      6873308.21
#Sta/Elev= 30
  2960.4  384.99  3164.4  379.29  3429.5  365.45  3755.9   358.7    4276  359.66
  4377.9  357.63  4449.3  359.43  4928.6  361.03  4938.8   360.6  4946.7  348.86
  4949.2  348.36  4971.7  348.86    4981  353.47  4989.8  357.09  5013.6  359.13
  5101.6  360.04  5138.1  364.12  5189.6  366.35  5274.4   366.3  5304.9  363.95
  5310.8  365.59  5341.3  362.77  5623.3   366.5  5674.9  369.88  5680.8  368.02
  5696.1  370.72  5913.9  381.07    5984  385.17  6150.8  388.07  6299.3  381.86
#Mann= 5 ,-1 , 0
  2960.4     .05       0  4946.7     .07       0  4971.7     .05       0
    4981     .12       0  5913.9     .05       0
Bank Sta=4946.7,4971.7
XS Rating Curve= 0 ,0
Exp/Cntr=0.3,0.1

Type RM Length L Ch R = 1 ,10813   ,2534,2534,2534
BEGIN DESCRIPTION:
Mapping XS 6cca5e0c
END DESCRIPTION:
XS GIS Cut Line= 3
      2647210.04        6871414.      2644819.41      6871262.96
      2643756.91       6871731.7
#Sta/Elev= 30
  2618.7  381.11  2712.9   383.1  2803.1  380.85    3244   361.4  3604.7  356.72
  3868.8  357.18  4005.5  357.58  4035.6  353.93  4075.6  357.95  4105.7  355.19
  4135.8  358.13    4276  356.92  4316.1  354.63  4336.3  356.54  4987.5  357.76
  4997.5  357.36  5007.5   348.5    5010   348.5  5012.5     348    5035   348.5
  5039.7   356.7  5045.8  359.63  5069.1  362.91  5218.3  370.04  5370.8  377.21
  5568.2  381.34  5629.9  379.29  5742.4   380.6  5911.1  376.01  6175.4   381.3
#Mann= 5 ,-1 , 0
  2618.7     .05       0  3868.8     .12       0    5010     .07       0
    5035     .12       0  5218.3     .05       0
Bank Sta=5010,5035
XS Rating Curve= 0 ,0
Exp/Cntr=0.3,0.1

Type RM Length L Ch R = 1 ,8279    ,0,0,0
BEGIN DESCRIPTION:
Big Cottonwood Creek 4.0
END DESCRIPTION:
XS GIS Cut Line= 4
      2647730.83      6870335.86      2645202.58      6869584.24
      2644163.16      6869596.29      2643517.32      6871861.94
#Sta/Elev= 30
  2362.4  379.02  2388.3   381.5  2450.9  373.42  2676.5  365.18  3134.1  358.36
  3494.1  357.77    3828  362.56  3984.5  357.77  4016.1  358.99  4067.9  354.17
  4120.9  353.61  4203.6  355.78  4589.6  354.33  4926.1   356.4  4975.6  353.39
  4992.5  356.39  5016.6  355.43  5024.1  348.13  5026.6  347.63  5049.1  348.13
  5056.6  355.87  5066.6  356.31  5876.6  354.15  5896.6  351.85  5906.6  355.98
  5956.6  352.58  7321.2  354.65  7926.5  362.77  8239.9  372.94  8395.4  381.31
#Mann= 3 ,-1 , 0
  2362.4     .05       0  5024.1     .03       0  5049.1     .05       0
Bank Sta=5024.1,5049.1
XS Rating Curve= 0 ,0
Exp/Cntr=0.3,0.1

Chan Stop Cuts=-1
Use User Specified Reach Order=0
Composite Channel Slope=5