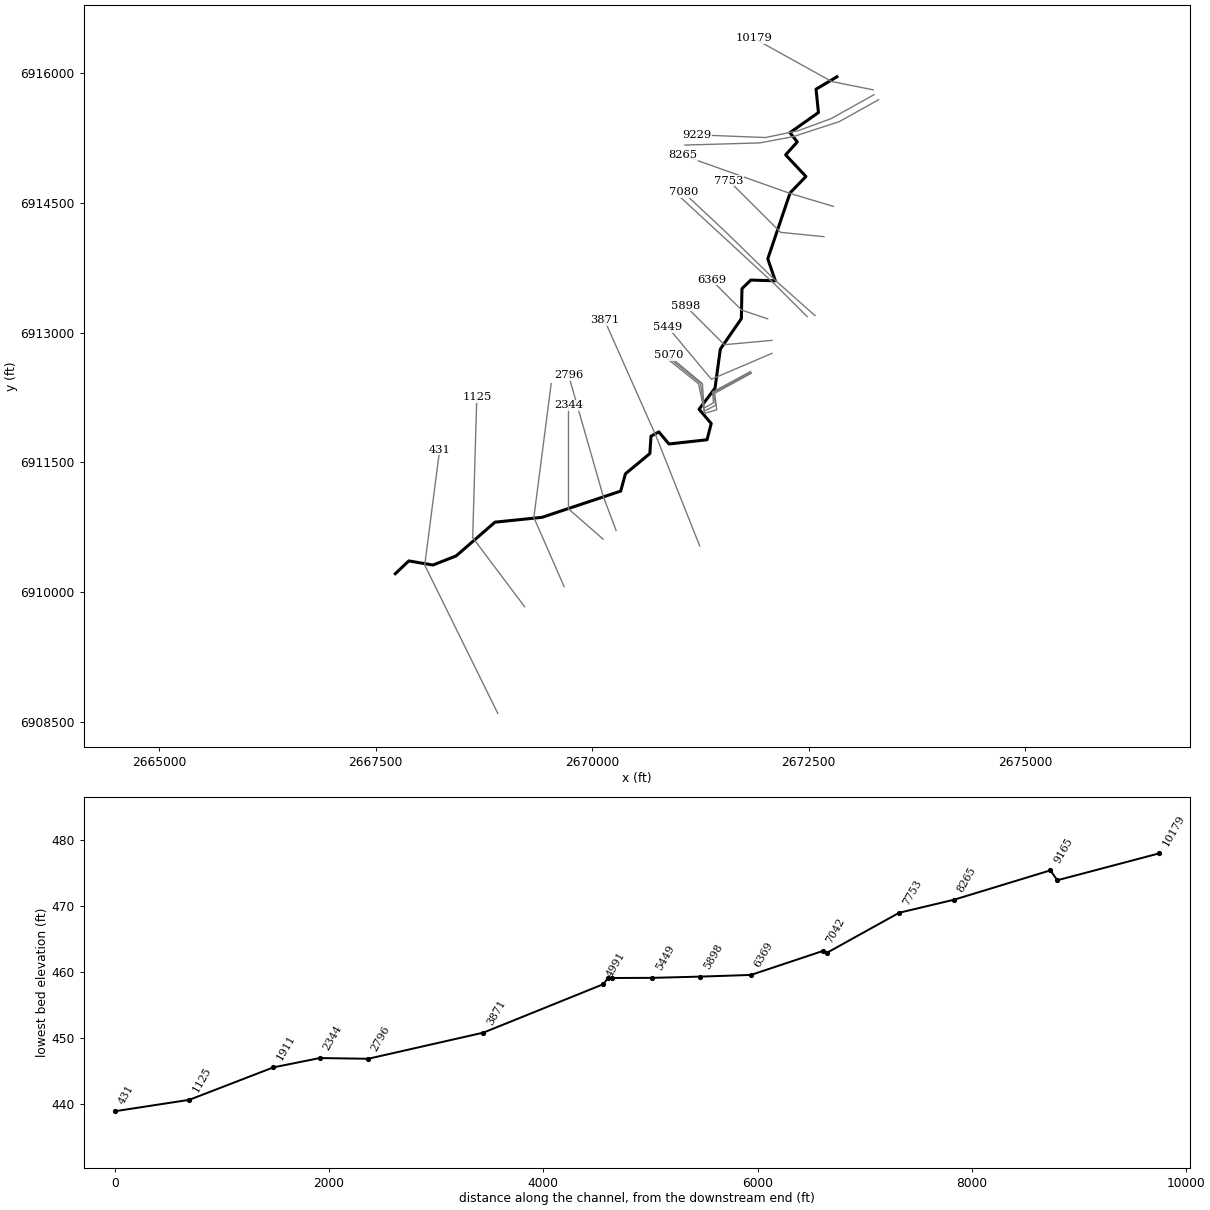
--- Big Cottonwood Creek Trib 1.prj (project) ---

Proj Title=Big Cottonwood Creek Trib 1 Base Level Engineering
Current Plan=p01
Default Exp/Contr=0.3,0.1
English Units
Geom File=g01
Flow File=f01
Plan File=p01
BEGIN DESCRIPTION:
Big Cottonwood Creek Trib 1
END DESCRIPTION:

--- Big Cottonwood Creek Trib 1.p01 (plan) ---

Plan Title=Multiple Run
Short Identifier=Multiple
Geom File=g01
Flow File=f01
Subcritical Flow
K Sum by GR= 0
Std Step Tol= 0.01
Critical Tol= 0.01
Num of Std Step Trials= 20
Max Error Tol= 0.3
Flow Tol Ratio= 0.001
Split Flow NTrial= 30
Split Flow Tol= 0.02
Split Flow Ratio= 0.02
Log Output Level= 0
Friction Slope Method= 1
Unsteady Friction Slope Method= 2
Unsteady Bridges Friction Slope Method= 1
Parabolic Critical Depth
Global Vel Dist=  1 , 1 , 1
Global Log Level= 0
CheckData=True
Encroach Param= -1, 0, 0, 0
BEGIN DESCRIPTION:
Multiple Run
END DESCRIPTION:

--- Big Cottonwood Creek Trib 1.f01 (steady flow) ---

Flow Title=Multiple
Number of Profiles=7
Profile Names=10-year,25-year,50-year,1pct_min,100-year,1pct_plu,500-year
River Rch & RM= Big Cottonwood C,Reach-1,10179
     534     710     850     505    1008    2010    1415
River Rch & RM= Big Cottonwood C,Reach-1,3871
    1066    1475    1815    1106    2206    4402    3260
Boundary for River Rch & Prof#=Big Cottonwood C,Reach-1,1
Up Type=0
Dn Type=3
Dn Slope=0.005
Boundary for River Rch & Prof#=Big Cottonwood C,Reach-1,2
Up Type=0
Dn Type=3
Dn Slope=0.005
Boundary for River Rch & Prof#=Big Cottonwood C,Reach-1,3
Up Type=0
Dn Type=3
Dn Slope=0.005
Boundary for River Rch & Prof#=Big Cottonwood C,Reach-1,4
Up Type=0
Dn Type=3
Dn Slope=0.005
Boundary for River Rch & Prof#=Big Cottonwood C,Reach-1,5
Up Type=0
Dn Type=3
Dn Slope=0.005
Boundary for River Rch & Prof#=Big Cottonwood C,Reach-1,6
Up Type=0
Dn Type=3
Dn Slope=0.005
Boundary for River Rch & Prof#=Big Cottonwood C,Reach-1,7
Up Type=0
Dn Type=3
Dn Slope=0.005

--- Big Cottonwood Creek Trib 1.g01 (geometry) ---

Geom Title=Existing Conditions

River Reach=Big Cottonwood C,Reach-1
Reach XY= 30
      2672826.00      6915961.00      2672585.13      6915817.78
      2672612.63      6915547.68      2672283.50      6915314.58
      2672368.39      6915207.67      2672233.59      6915057.67
      2672468.41      6914807.67      2672285.30      6914617.67
      2672027.59      6913854.95      2672114.90      6913600.56
      2671831.85      6913608.96      2671729.53      6913509.55
      2671722.25      6913162.55      2671479.55      6912809.53
      2671418.20      6912357.58      2671234.02      6912114.31
      2671374.48      6911949.12      2671326.00      6911761.00
      2670886.28      6911711.99      2670769.56      6911851.85
      2670679.07      6911802.75      2670665.52      6911601.20
      2670383.81      6911367.21      2670328.59      6911166.71
      2669420.06      6910863.26      2668877.47      6910807.45
      2668428.31      6910416.83      2668160.78      6910311.50
      2667881.94      6910358.87      2667726.00      6910211.00

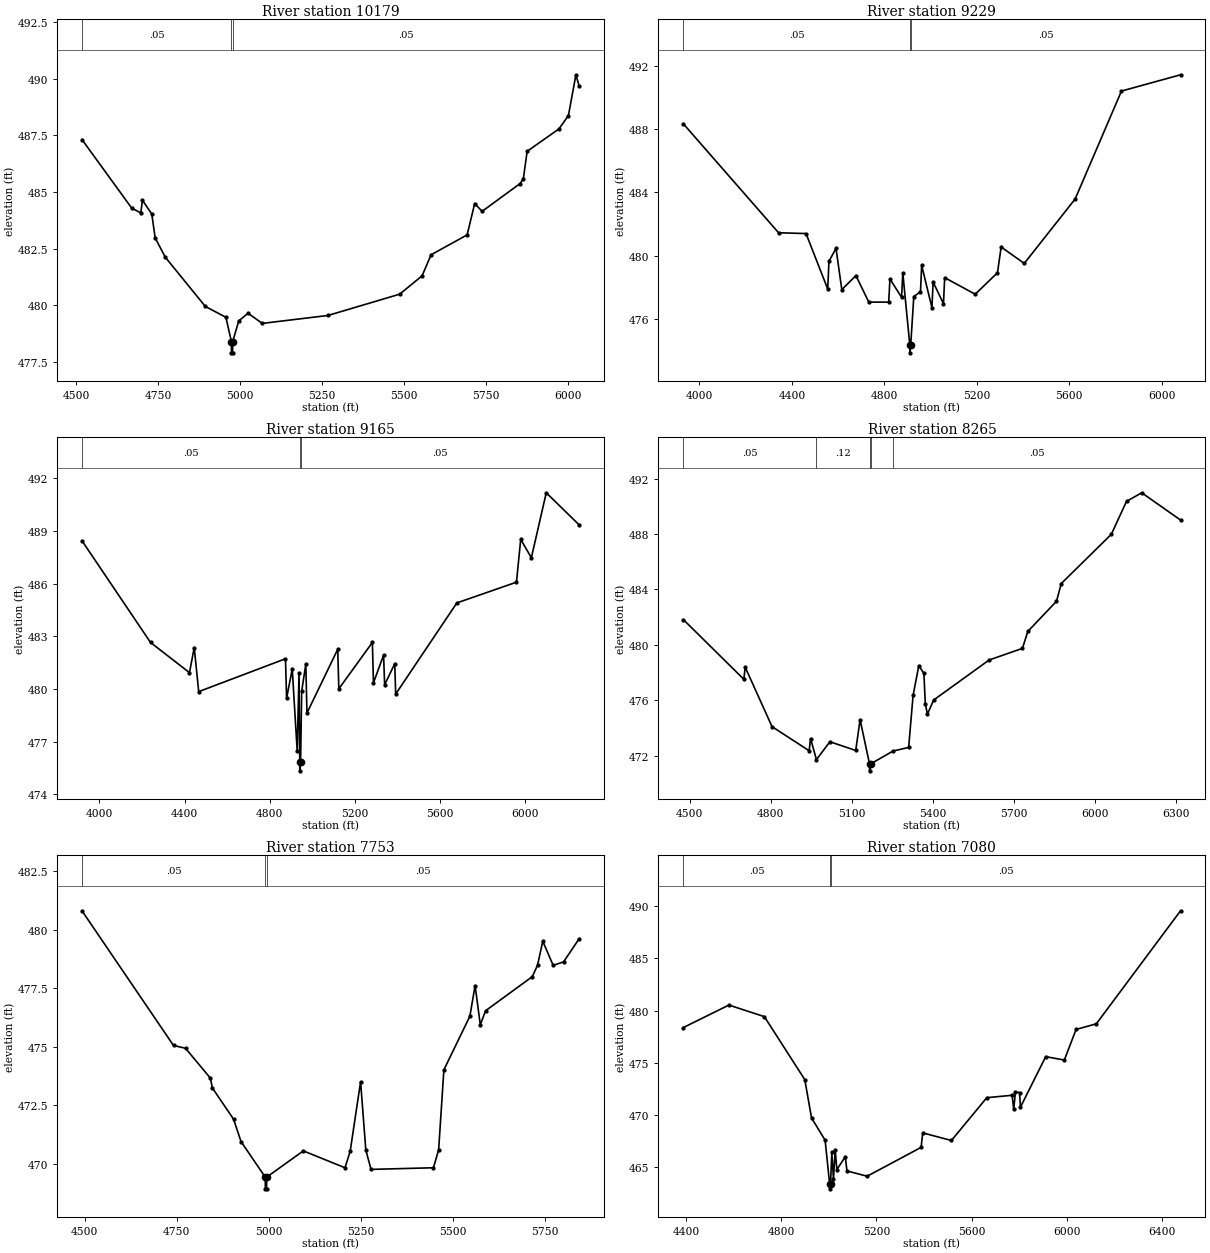
Type RM Length L Ch R = 1,10179,950,950,950
BEGIN DESCRIPTION:
Big Cottonwood Creek Trib 1 19.0
END DESCRIPTION:
XS GIS Cut Line= 3
      2673244.82      6915810.23      2672767.03      6915906.22
      2671867.20      6916406.13
#Sta/Elev= 30
  4516.9  487.32  4668.7  484.29  4696.3  484.08  4701.4  484.64  4729.9  484.03
  4740.1  482.98  4770.7  482.13  4893.1  479.95  4955.9  479.47  4972.7  478.40
  4972.9  477.90  4976.4  477.90  4976.7  478.40  4995.1  479.31  5023.5  479.65
  5066.9  479.20  5267.1  479.55  5485.9  480.49  5554.3  481.30  5581.7  482.23
  5691.8  483.11  5714.7  484.49  5737.5  484.15  5852.8  485.37  5863.1  485.58
  5874.8  486.80  5971.8  487.79  6000.7  488.38  6023.5  490.18  6033.6  489.67
#Mann=3,-1,0
  4516.9    0.05       0  4972.7    0.03       0  4976.7    0.05       0
Bank Sta=4972.7,4976.7
Exp/Cntr=0.3,0.1

Type RM Length L Ch R = 1,9229,64,64,64
BEGIN DESCRIPTION:
Mapping XS c0a7fe91
END DESCRIPTION:
XS GIS Cut Line= 6
      2673255.22      6915754.65      2672758.72      6915476.89
      2672380.25      6915338.00      2672283.03      6915317.17
      2672001.78      6915258.14      2671210.56      6915289.37
#Sta/Elev= 30
  3930.2  488.34  4342.3  481.44  4461.0  481.39  4554.8  477.88  4560.2  479.64
  4590.7  480.45  4615.8  477.84  4676.8  478.73  4732.5  477.05  4818.6  477.05
  4823.9  478.51  4874.3  477.36  4879.6  478.89  4909.8  474.34  4910.0  473.84
  4913.8  474.34  4927.1  477.40  4956.1  477.71  4961.2  479.37  5005.6  476.70
  5010.7  478.32  5055.5  476.95  5060.6  478.60  5192.8  477.55  5289.1  478.91
  5304.9  480.54  5404.9  479.50  5625.1  483.58  5825.3  490.41  6080.9  491.44
#Mann=3,-1,0
  3930.2    0.05       0  4909.8    0.04       0  4913.8    0.05       0
Bank Sta=4909.8,4913.8
Exp/Cntr=0.3,0.1

Type RM Length L Ch R = 1,9165,900,900,900
BEGIN DESCRIPTION:
Mapping XS 435b7b11
END DESCRIPTION:
XS GIS Cut Line= 5
      2673307.36      6915695.65      2672852.47      6915442.17
      2672321.22      6915268.56      2671932.33      6915195.64
      2671071.18      6915171.34
#Sta/Elev= 30
  3917.7  488.44  4239.8  482.65  4423.0  480.93  4445.3  482.36  4466.3  479.85
  4874.1  481.72  4879.3  479.47  4905.9  481.13  4929.2  476.47  4937.8  480.89
  4941.1  475.84  4941.3  475.34  4945.1  475.84  4950.2  479.87  4969.7  481.41
  4975.0  478.63  5119.7  482.26  5124.8  480.01  5282.5  482.65  5287.6  480.35
  5335.1  481.93  5340.1  480.24  5387.6  481.44  5392.0  479.71  5679.5  484.90
  5959.6  486.08  5979.6  488.52  6029.6  487.47  6099.6  491.17  6254.5  489.34
#Mann=3,-1,0
  3917.7    0.05       0  4941.1    0.03       0  4945.1    0.05       0
Bank Sta=4941.1,4945.1
Exp/Cntr=0.3,0.1

Type RM Length L Ch R = 1,8265,512,512,512
BEGIN DESCRIPTION:
Big Cottonwood Creek Trib 1 16.0
END DESCRIPTION:
XS GIS Cut Line= 3
      2672785.30      6914461.64      2672285.30      6914611.64
      2671043.41      6915053.29
#Sta/Elev= 30
  4476.3  481.82  4700.2  477.51  4705.4  478.38  4804.6  474.09  4942.0  472.35
  4947.2  473.23  4968.9  471.71  5018.8  473.00  5114.3  472.37  5130.5  474.59
  5165.4  471.40  5165.6  470.90  5169.4  471.40  5252.7  472.33  5310.2  472.59
  5326.6  476.34  5347.8  478.50  5366.6  477.93  5371.9  475.73  5379.7  474.99
  5402.7  476.01  5608.0  478.90  5731.4  479.74  5751.1  480.96  5857.3  483.14
  5875.0  484.42  6060.1  487.97  6116.4  490.35  6172.8  490.97  6316.4  489.00
#Mann=5,-1,0
  4476.3    0.05       0  4968.9    0.12       0  5165.4    0.07       0
  5169.4    0.12       0  5252.7    0.05       0
Bank Sta=5165.4,5169.4
Exp/Cntr=0.3,0.1

Type RM Length L Ch R = 1,7753,673,673,673
BEGIN DESCRIPTION:
Big Cottonwood Creek Trib 1 15.0
END DESCRIPTION:
XS GIS Cut Line= 3
      2672675.96      6914111.00      2672176.00      6914161.00
      2671575.98      6914761.02
#Sta/Elev= 30
  4493.0  480.80  4741.7  475.05  4774.4  474.93  4842.2  473.65  4847.2  473.24
  4905.0  471.90  4925.1  470.95  4990.9  469.43  4991.2  468.93  4994.7  468.93
  4994.9  469.43  5094.4  470.55  5207.6  469.83  5221.7  470.53  5250.0  473.50
  5264.2  470.59  5278.3  469.76  5448.0  469.83  5462.1  470.60  5476.3  474.01
  5547.0  476.30  5561.1  477.61  5575.3  475.93  5589.4  476.53  5716.7  477.99
  5730.8  478.48  5745.0  479.50  5773.3  478.47  5801.6  478.62  5844.0  479.61
#Mann=3,-1,0
  4493.0    0.05       0  4990.9    0.04       0  4994.9    0.05       0
Bank Sta=4990.9,4994.9
Exp/Cntr=0.3,0.1

Type RM Length L Ch R = 1,7080,38,38,38
BEGIN DESCRIPTION:
Mapping XS 5f44514f
END DESCRIPTION:
XS GIS Cut Line= 4
      2672572.93      6913197.84      2672121.57      6913599.29
      2671546.48      6914161.35      2671051.31      6914626.25
#Sta/Elev= 30
  4389.3  478.37  4580.7  480.53  4729.5  479.42  4899.3  473.37  4927.7  469.69
  4984.6  467.56  5003.5  463.39  5003.8  462.89  5007.5  463.39  5012.7  466.38
  5019.7  463.82  5026.8  466.66  5033.8  464.74  5069.3  465.97  5076.3  464.61
  5161.1  464.10  5387.5  466.87  5394.4  468.26  5514.8  467.53  5663.2  471.64
  5769.4  471.87  5776.4  470.53  5783.5  472.19  5800.9  472.13  5804.6  470.73
  5910.7  475.58  5988.8  475.25  6038.1  478.19  6123.1  478.73  6476.7  489.58
#Mann=3,-1,0
  4389.3    0.05       0  5003.5    0.03       0  5007.5    0.05       0
Bank Sta=5003.5,5007.5
Exp/Cntr=0.3,0.1

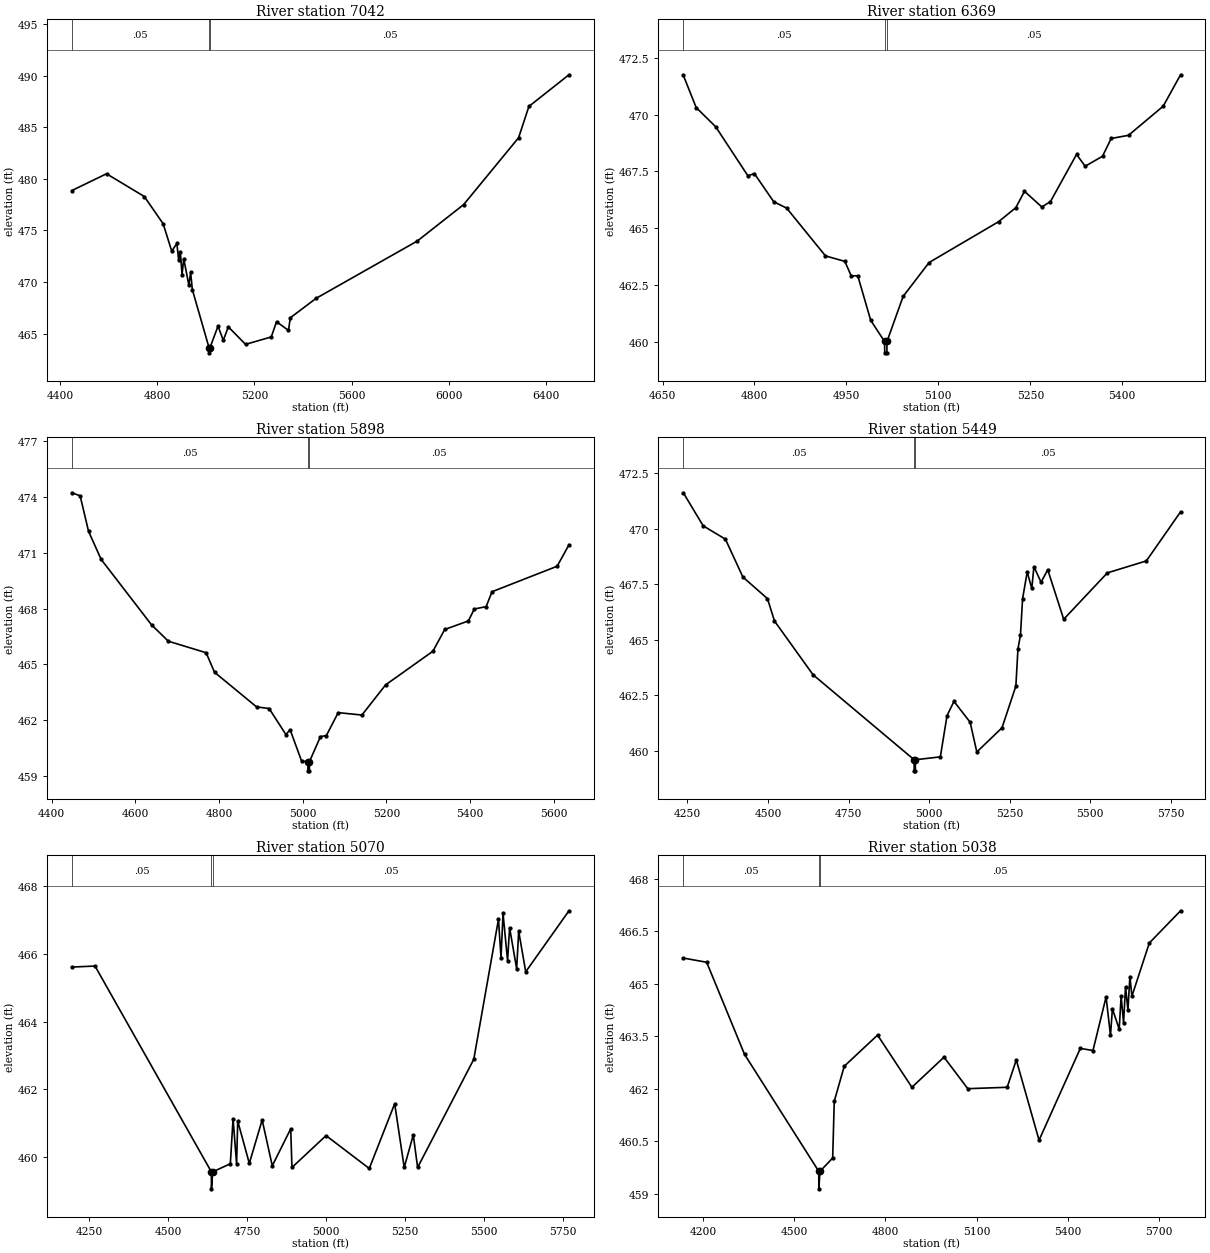
Type RM Length L Ch R = 1,7042,673,673,673
BEGIN DESCRIPTION:
Mapping XS 1228cdb6
END DESCRIPTION:
XS GIS Cut Line= 3
      2672482.96      6913185.12      2672102.73      6913565.35
      2670993.10      6914591.04
#Sta/Elev= 30
  4447.2  478.86  4590.6  480.49  4746.2  478.29  4824.0  475.65  4859.3  473.00
  4880.5  473.75  4887.6  472.18  4894.7  472.95  4901.8  470.73  4908.8  472.26
  4930.0  469.69  4937.1  470.96  4944.2  469.28  5012.9  463.66  5013.2  463.16
  5016.9  463.66  5050.1  465.75  5071.6  464.37  5092.6  465.67  5163.5  463.98
  5269.5  464.70  5291.1  466.17  5340.4  465.33  5347.8  466.55  5453.8  468.43
  5871.1  473.98  6062.2  477.51  6288.5  483.98  6331.0  487.01  6496.0  490.07
#Mann=3,-1,0
  4447.2    0.05       0  5012.9    0.03       0  5016.9    0.05       0
Bank Sta=5012.9,5016.9
Exp/Cntr=0.3,0.1

Type RM Length L Ch R = 1,6369,471,471,471
BEGIN DESCRIPTION:
Big Cottonwood Creek Trib 1 12.0
END DESCRIPTION:
XS GIS Cut Line= 3
      2672025.97      6913161.01      2671726.00      6913261.00
      2671375.98      6913611.02
#Sta/Elev= 30
  4683.9  471.73  4704.9  470.31  4736.6  469.47  4789.3  467.31  4799.8  467.41
  4831.4  466.17  4852.5  465.89  4915.8  463.79  4947.4  463.55  4957.9  462.91
  4968.5  462.92  4989.6  460.96  5012.2  460.03  5012.5  459.53  5016.0  459.53
  5016.2  460.03  5042.5  462.01  5084.9  463.50  5198.1  465.29  5226.4  465.91
  5240.5  466.63  5268.8  465.94  5282.9  466.18  5325.4  468.25  5339.5  467.73
  5367.8  468.17  5381.9  468.95  5410.2  469.09  5466.8  470.37  5495.1  471.75
#Mann=3,-1,0
  4683.9    0.05       0  5012.2    0.04       0  5016.2    0.05       0
Bank Sta=5012.2,5016.2
Exp/Cntr=0.3,0.1

Type RM Length L Ch R = 1,5898,449,449,449
BEGIN DESCRIPTION:
Big Cottonwood Creek Trib 1 11.0
END DESCRIPTION:
XS GIS Cut Line= 3
      2672076.00      6912911.00      2671526.00      6912861.00
      2671075.98      6913311.02
#Sta/Elev= 30
  4447.7  474.23  4467.8  474.07  4487.9  472.16  4518.0  470.65  4638.5  467.13
  4678.7  466.25  4769.0  465.63  4789.1  464.58  4889.5  462.72  4919.6  462.63
  4959.8  461.23  4969.8  461.49  4997.5  459.79  5012.1  459.78  5012.4  459.28
  5015.9  459.28  5016.1  459.78  5042.4  461.12  5056.5  461.18  5084.8  462.41
  5141.4  462.28  5198.0  463.90  5311.1  465.71  5339.4  466.88  5396.0  467.34
  5410.1  467.98  5438.4  468.11  5452.5  468.91  5608.1  470.28  5636.4  471.43
#Mann=3,-1,0
  4447.7    0.05       0  5012.1    0.04       0  5016.1    0.05       0
Bank Sta=5012.1,5016.1
Exp/Cntr=0.3,0.1

Type RM Length L Ch R = 1,5449,379,379,379
BEGIN DESCRIPTION:
Big Cottonwood Creek Trib 1 10.0
END DESCRIPTION:
XS GIS Cut Line= 3
      2672076.00      6912761.00      2671376.00      6912461.00
      2670876.00      6913061.00
#Sta/Elev= 30
  4237.2  471.62  4298.9  470.13  4367.8  469.53  4422.2  467.82  4498.3  466.85
  4520.1  465.84  4639.7  463.42  4953.3  459.59  4953.5  459.09  4957.0  459.09
  4957.3  459.59  5034.6  459.72  5055.4  461.58  5076.9  462.22  5127.0  461.28
  5147.8  459.94  5225.9  461.03  5268.9  462.91  5275.4  464.59  5283.2  465.21
  5289.7  466.84  5304.0  468.05  5318.3  467.31  5324.9  468.29  5347.0  467.59
  5367.8  468.15  5417.3  465.92  5552.7  468.01  5673.7  468.55  5779.8  470.76
#Mann=3,-1,0
  4237.2    0.05       0  4953.3    0.03       0  4957.3    0.05       0
Bank Sta=4953.3,4957.3
Exp/Cntr=0.3,0.1

Type RM Length L Ch R = 1,5070,32,32,32
BEGIN DESCRIPTION:
Mapping XS 5e32314e
END DESCRIPTION:
XS GIS Cut Line= 6
      2671827.32      6912550.46      2671388.56      6912312.20
      2671401.58      6912188.50      2671290.90      6912127.30
      2671272.67      6912409.86      2670879.41      6912738.00
#Sta/Elev= 30
  4194.1  465.61  4267.9  465.64  4636.6  459.57  4636.9  459.07  4640.6  459.57
  4696.7  459.81  4705.3  461.14  4716.5  459.81  4720.1  461.07  4756.8  459.82
  4797.5  461.10  4829.6  459.75  4888.0  460.84  4891.9  459.70  5000.0  460.64
  5136.9  459.67  5217.4  461.58  5247.6  459.70  5276.3  460.66  5290.1  459.70
  5468.0  462.89  5546.3  467.02  5554.3  465.89  5560.7  467.19  5575.1  465.80
  5581.5  466.77  5603.9  465.56  5610.3  466.67  5632.6  465.47  5769.6  467.27
#Mann=3,-1,0
  4194.1    0.05       0  4636.6    0.03       0  4640.6    0.05       0
Bank Sta=4636.6,4640.6
Exp/Cntr=0.3,0.1

Type RM Length L Ch R = 1,5038,47,47,47
BEGIN DESCRIPTION:
Big Cottonwood Creek Trib 1 9.0
END DESCRIPTION:
XS GIS Cut Line= 6
      2671833.89      6912537.47      2671398.76      6912306.12
      2671426.53      6912161.16      2671295.74      6912093.10
      2671249.88      6912414.63      2670871.62      6912721.06
#Sta/Elev= 30
  4134.8  465.73  4211.7  465.61  4336.3  462.98  4580.5  459.64  4580.8  459.14
  4584.5  459.64  4626.3  460.02  4631.5  461.64  4664.3  462.64  4774.0  463.53
  4887.0  462.04  4992.6  462.90  5070.9  462.00  5200.5  462.04  5230.5  462.82
  5305.4  460.53  5441.2  463.15  5482.8  463.09  5526.0  464.62  5540.4  463.52
  5546.8  464.28  5569.1  463.70  5575.5  464.64  5583.5  463.88  5589.9  464.91
  5597.9  464.25  5604.3  465.20  5610.9  464.64  5668.2  466.16  5771.0  467.08
#Mann=3,-1,0
  4134.8    0.05       0  4580.5    0.03       0  4584.5    0.05       0
Bank Sta=4580.5,4584.5
Exp/Cntr=0.3,0.1

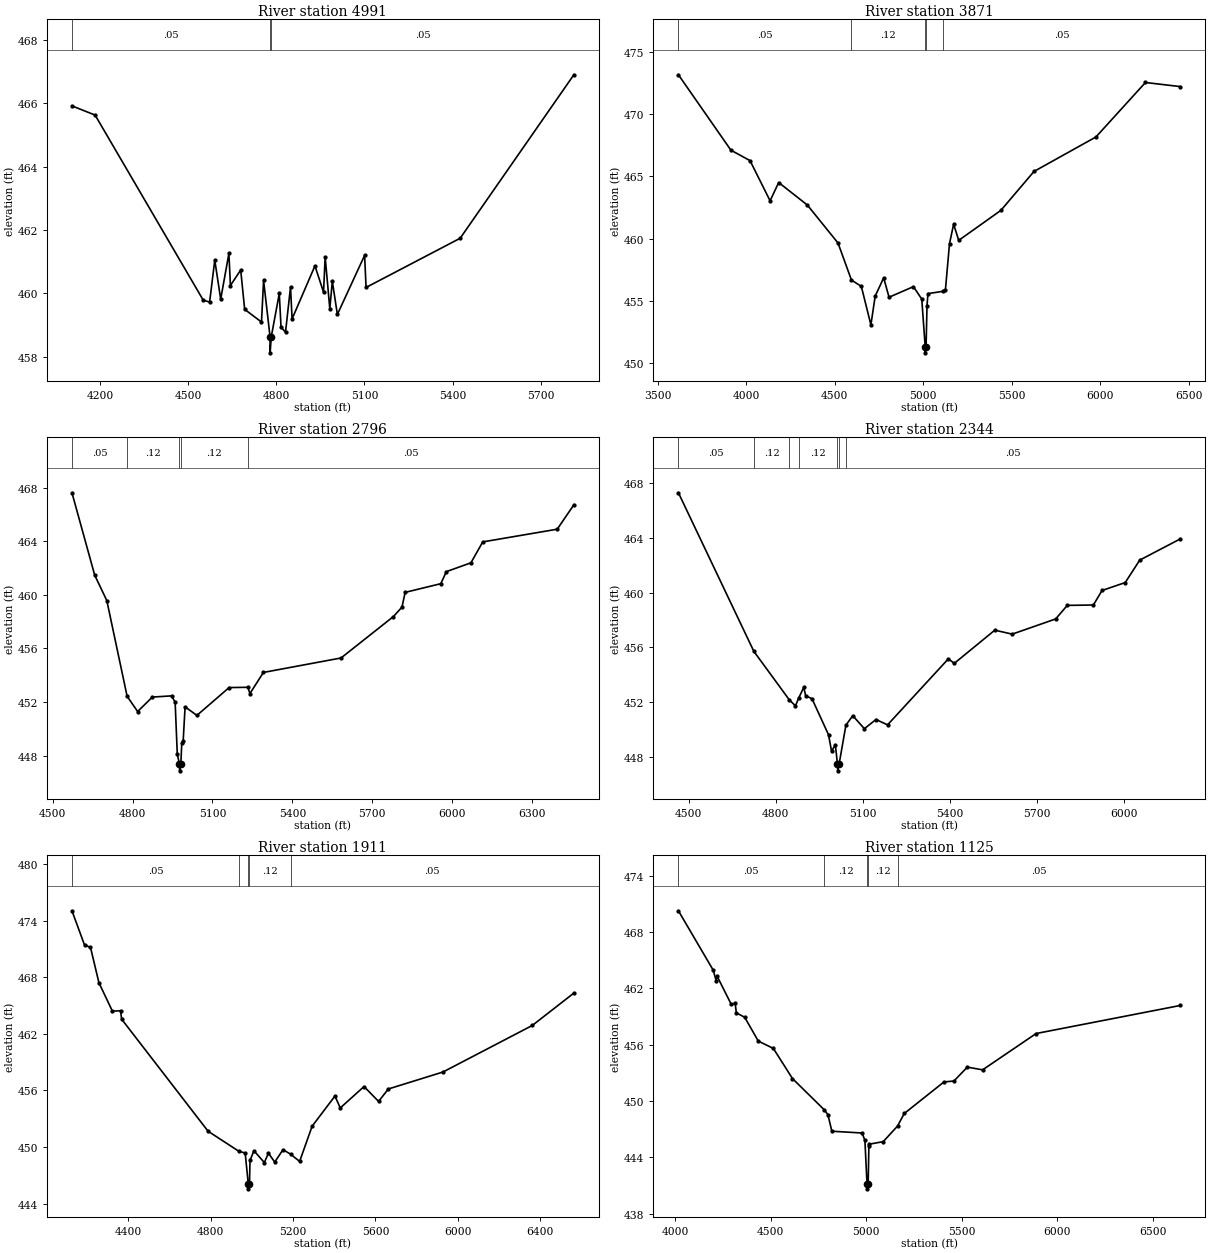
Type RM Length L Ch R = 1,4991,1120,1120,1120
BEGIN DESCRIPTION:
Mapping XS bc4f3609
END DESCRIPTION:
XS GIS Cut Line= 6
      2671835.18      6912529.65      2671414.60      6912299.18
      2671438.03      6912107.77      2671298.71      6912066.11
      2671228.40      6912408.55      2670852.09      6912710.64
#Sta/Elev= 30
  4104.0  465.91  4182.9  465.62  4551.0  459.79  4572.8  459.73  4590.3  461.05
  4610.5  459.82  4638.4  461.26  4643.6  460.25  4678.6  460.74  4692.1  459.50
  4749.4  459.10  4756.5  460.41  4778.6  458.63  4778.8  458.13  4782.6  458.63
  4810.0  460.00  4815.9  458.94  4831.2  458.78  4848.2  460.20  4853.6  459.20
  4931.4  460.87  4960.7  460.04  4966.2  461.15  4982.0  459.52  4990.6  460.38
  5007.8  459.34  5100.5  461.20  5105.5  460.19  5425.9  461.74  5813.0  466.89
#Mann=3,-1,0
  4104.0    0.05       0  4778.6    0.03       0  4782.6    0.05       0
Bank Sta=4778.6,4782.6
Exp/Cntr=0.3,0.1

Type RM Length L Ch R = 1,3871,1075,1075,1075
BEGIN DESCRIPTION:
Mapping XS 35364361
END DESCRIPTION:
XS GIS Cut Line= 3
      2671241.35      6910532.48      2670736.19      6911805.78
      2670141.56      6913147.14
#Sta/Elev= 30
  3615.6  473.16  3912.3  467.10  4020.4  466.26  4133.8  463.03  4182.4  464.50
  4344.4  462.69  4517.7  459.64  4593.7  456.66  4649.6  456.15  4703.6  453.06
  4727.9  455.37  4775.9  456.84  4806.2  455.28  4944.0  456.13  4991.2  455.13
  5010.5  451.31  5011.1  450.81  5015.6  451.31  5020.7  454.58  5026.2  455.57
  5113.6  455.76  5124.8  455.85  5148.0  459.59  5171.3  461.15  5200.1  459.85
  5438.3  462.26  5625.6  465.39  5975.6  468.16  6255.6  472.54  6452.7  472.21
#Mann=5,-1,0
  3615.6    0.05       0  4593.7    0.12       0  5010.5    0.07       0
  5015.6    0.12       0  5113.6    0.05       0
Bank Sta=5010.5,5015.6
Exp/Cntr=0.3,0.1

Type RM Length L Ch R = 1,2796,452,452,452
BEGIN DESCRIPTION:
Big Cottonwood Creek Trib 1 5.0
END DESCRIPTION:
XS GIS Cut Line= 3
      2670276.01      6910710.98      2670126.00      6911111.00
      2669726.01      6912510.96
#Sta/Elev= 30
  4572.8  467.63  4658.3  461.47  4703.6  459.58  4779.8  452.43  4819.3  451.29
  4874.5  452.37  4946.6  452.46  4960.0  451.99  4968.0  448.12  4976.0  447.36
  4976.8  446.86  4981.3  447.36  4984.9  448.92  4990.2  449.11  4997.3  451.64
  5041.6  451.00  5162.5  453.08  5233.2  453.10  5240.5  452.63  5291.2  454.21
  5582.4  455.29  5778.7  458.38  5811.2  459.09  5822.9  460.19  5956.8  460.84
  5977.6  461.74  6069.9  462.40  6114.1  463.96  6393.6  464.91  6456.0  466.73
#Mann=5,-1,0
  4572.8    0.05       0  4779.8    0.12       0  4976.0    0.07       0
  4981.3    0.12       0  5233.2    0.05       0
Bank Sta=4976,4981.3
Exp/Cntr=0.3,0.1

Type RM Length L Ch R = 1,2344,433,433,433
BEGIN DESCRIPTION:
Big Cottonwood Creek Trib 1 4.0
END DESCRIPTION:
XS GIS Cut Line= 3
      2670126.03      6910610.98      2669726.00      6910961.00
      2669726.00      6912160.96
#Sta/Elev= 30
  4464.1  467.29  4724.4  455.70  4846.9  452.15  4868.0  451.72  4878.4  452.26
  4896.5  453.07  4903.1  452.46  4924.9  452.24  4981.9  449.61  4992.3  448.42
  5005.6  448.86  5012.8  447.47  5013.7  446.97  5018.5  447.47  5042.0  450.31
  5065.6  451.00  5105.6  450.05  5145.6  450.72  5185.6  450.33  5395.6  455.16
  5415.6  454.82  5555.6  457.25  5615.6  456.96  5765.6  458.07  5805.6  459.06
  5895.6  459.09  5925.6  460.15  6005.6  460.73  6055.6  462.37  6195.6  463.92
#Mann=7,-1,0
  4464.1    0.05       0  4724.4    0.12       0  4846.9    0.05       0
  4878.4    0.12       0  5012.8    0.07       0  5018.5    0.12       0
  5042.0    0.05       0
Bank Sta=5012.8,5018.5
Exp/Cntr=0.3,0.1

Type RM Length L Ch R = 1,1911,786,786,786
BEGIN DESCRIPTION:
Big Cottonwood Creek Trib 1 3.0
END DESCRIPTION:
XS GIS Cut Line= 3
      2669675.99      6910061.03      2669326.00      6910861.00
      2669526.00      6912410.97
#Sta/Elev= 30
  4126.9  475.05  4188.1  471.41  4216.9  471.17  4257.8  467.42  4323.3  464.40
  4362.7  464.45  4368.2  463.55  4787.6  451.67  4937.2  449.54  4967.7  449.36
  4982.8  446.06  4983.7  445.56  4988.6  446.06  4991.1  448.57  5010.2  449.60
  5060.6  448.35  5080.7  449.34  5111.0  448.40  5151.3  449.71  5187.7  449.24
  5232.0  448.47  5292.5  452.20  5403.4  455.40  5429.2  454.14  5544.6  456.41
  5615.1  454.83  5662.4  456.15  5927.7  457.95  6361.3  462.89  6562.9  466.32
#Mann=5,-1,0
  4126.9    0.05       0  4937.2    0.12       0  4982.8    0.07       0
  4988.6    0.12       0  5187.7    0.05       0
Bank Sta=4982.8,4988.6
Exp/Cntr=0.3,0.1

Type RM Length L Ch R = 1,1125,694,694,694
BEGIN DESCRIPTION:
Big Cottonwood Creek Trib 1 2.0
END DESCRIPTION:
XS GIS Cut Line= 3
      2669219.55      6909828.71      2668619.52      6910628.74
      2668667.07      6912255.60
#Sta/Elev= 30
  4017.4  470.28  4199.9  463.94  4214.5  462.85  4220.7  463.28  4293.7  460.32
  4314.5  460.41  4320.7  459.40  4364.5  458.93  4435.3  456.40  4514.5  455.61
  4614.5  452.40  4780.0  449.09  4799.9  448.56  4820.7  446.79  4979.1  446.60
  4993.7  445.81  5004.8  441.15  5005.8  440.65  5010.8  441.15  5014.5  445.17
  5017.4  445.41  5089.7  445.68  5164.6  447.34  5199.8  448.68  5407.6  452.04
  5459.9  452.14  5529.9  453.62  5610.0  453.33  5890.1  457.20  6645.0  460.19
#Mann=5,-1,0
  4017.4    0.05       0  4780.0    0.12       0  5004.8    0.07       0
  5010.8    0.12       0  5164.6    0.05       0
Bank Sta=5004.8,5010.8
Exp/Cntr=0.3,0.1

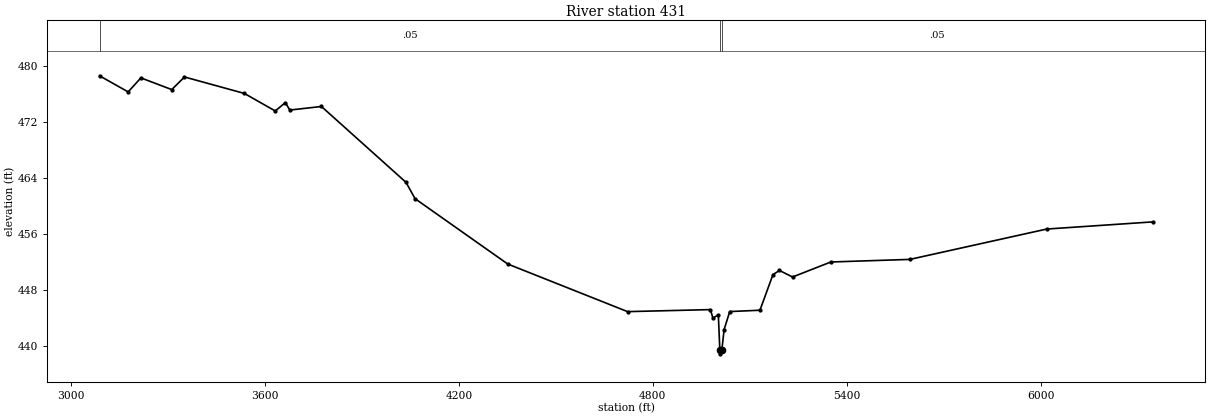
Type RM Length L Ch R = 1,431,0,0,0
BEGIN DESCRIPTION:
Big Cottonwood Creek Trib 1 1.0
END DESCRIPTION:
XS GIS Cut Line= 3
      2668909.28      6908594.82      2668065.83      6910310.50
      2668237.99      6911646.35
#Sta/Elev= 30
  3088.2  478.59  3176.8  476.29  3216.2  478.29  3311.7  476.62  3351.1  478.42
  3536.4  476.07  3631.9  473.57  3663.4  474.77  3676.9  473.70  3774.8  474.21
  4036.5  463.39  4064.5  461.06  4351.2  451.74  4722.0  444.95  4978.3  445.24
  4986.1  444.03  5002.8  444.50  5007.5  439.43  5008.5  438.93  5013.6  439.43
  5020.7  442.40  5038.1  444.96  5131.6  445.15  5171.9  450.24  5192.0  450.82
  5232.4  449.89  5350.9  452.03  5595.4  452.40  6018.9  456.73  6346.9  457.75
#Mann=3,-1,0
  3088.2    0.05       0  5007.5    0.04       0  5013.6    0.05       0
Bank Sta=5007.5,5013.6
Exp/Cntr=0.3,0.1

Chan Stop Cuts=-1