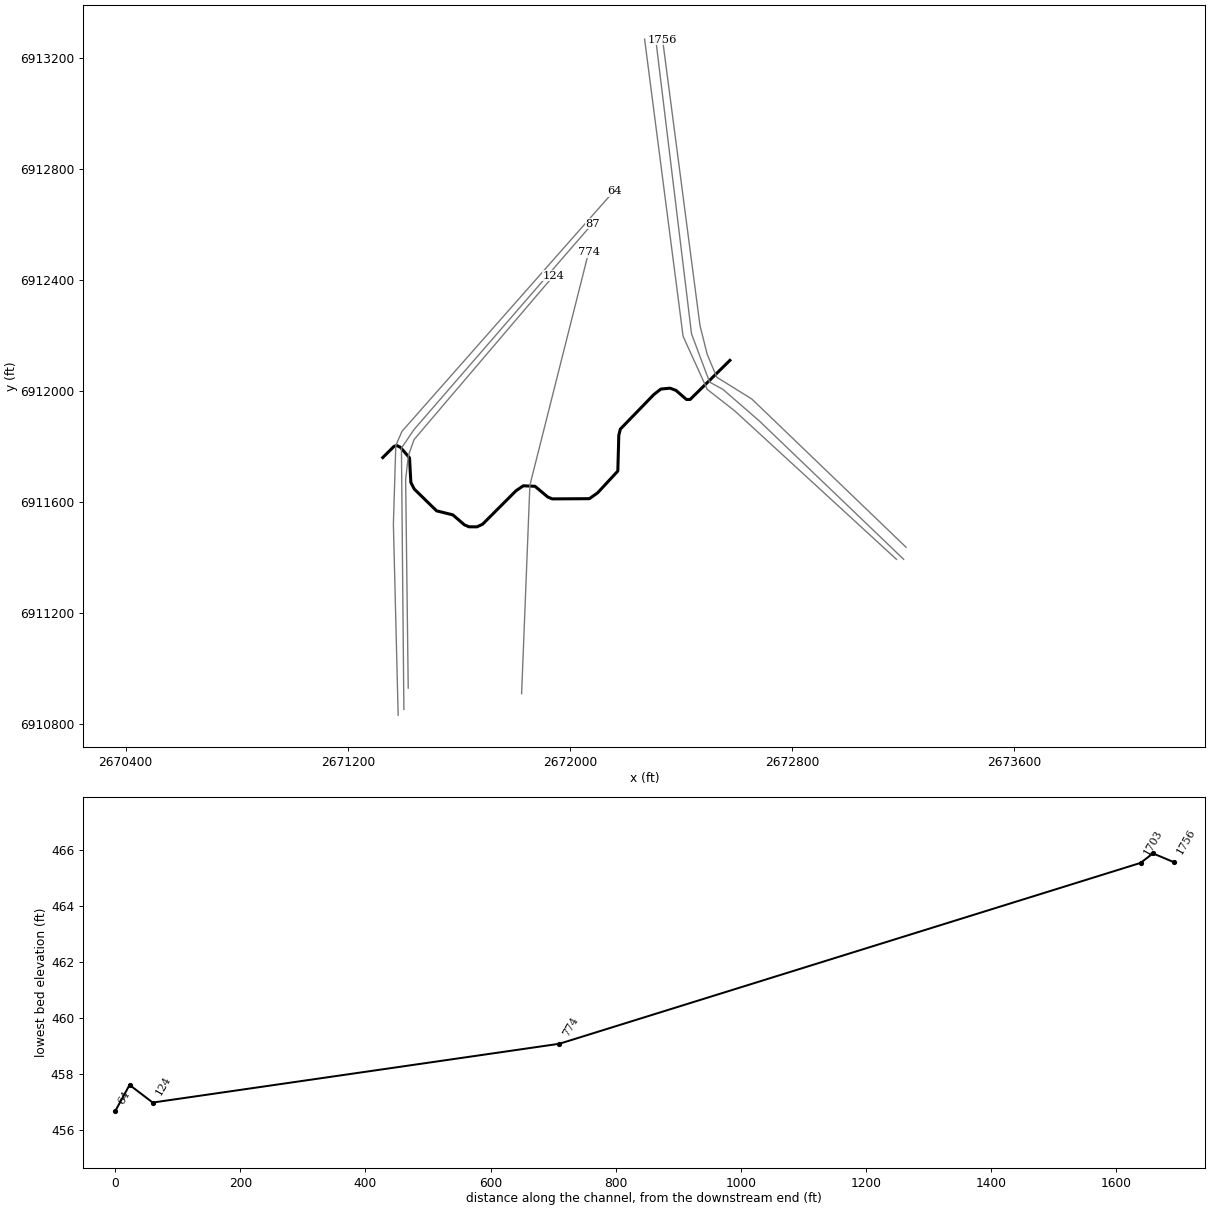
--- Big Cottonwood Creek Trib 1_1.prj (project) ---

Proj Title=Big Cottonwood Creek Trib 1_1 Base Level Engineering
Current Plan=p01
Default Exp/Contr=0.3,0.1
English Units
Geom File=g01
Flow File=f01
Plan File=p01
BEGIN DESCRIPTION:
Big Cottonwood Creek Trib 1_1
END DESCRIPTION:

--- Big Cottonwood Creek Trib 1_1.p01 (plan) ---

Plan Title=Multiple Run
Short Identifier=Multiple
Geom File=g01
Flow File=f01
Subcritical Flow
K Sum by GR= 0
Std Step Tol= 0.01
Critical Tol= 0.01
Num of Std Step Trials= 20
Max Error Tol= 0.3
Flow Tol Ratio= 0.001
Split Flow NTrial= 30
Split Flow Tol= 0.02
Split Flow Ratio= 0.02
Log Output Level= 0
Friction Slope Method= 1
Unsteady Friction Slope Method= 2
Unsteady Bridges Friction Slope Method= 1
Parabolic Critical Depth
Global Vel Dist=  1 , 1 , 1
Global Log Level= 0
CheckData=True
Encroach Param= -1, 0, 0, 0
BEGIN DESCRIPTION:
Multiple Run
END DESCRIPTION:

--- Big Cottonwood Creek Trib 1_1.f01 (steady flow) ---

Flow Title=Multiple
Number of Profiles=7
Profile Names=10-year,25-year,50-year,1pct_min,100-year,1pct_plu,500-year
River Rch & RM= Big Cottonwood C,Reach-1,1756
     584     789     956     575    1148    2290    1654
River Rch & RM= Big Cottonwood C,Reach-1,124
     569     760     914     545    1088    2170    1540
Boundary for River Rch & Prof#=Big Cottonwood C,Reach-1,1
Up Type=0
Dn Type=3
Dn Slope=0.005
Boundary for River Rch & Prof#=Big Cottonwood C,Reach-1,2
Up Type=0
Dn Type=3
Dn Slope=0.005
Boundary for River Rch & Prof#=Big Cottonwood C,Reach-1,3
Up Type=0
Dn Type=3
Dn Slope=0.005
Boundary for River Rch & Prof#=Big Cottonwood C,Reach-1,4
Up Type=0
Dn Type=3
Dn Slope=0.005
Boundary for River Rch & Prof#=Big Cottonwood C,Reach-1,5
Up Type=0
Dn Type=3
Dn Slope=0.005
Boundary for River Rch & Prof#=Big Cottonwood C,Reach-1,6
Up Type=0
Dn Type=3
Dn Slope=0.005
Boundary for River Rch & Prof#=Big Cottonwood C,Reach-1,7
Up Type=0
Dn Type=3
Dn Slope=0.005

--- Big Cottonwood Creek Trib 1_1.g01 (geometry) ---

Geom Title=Existing Conditions

River Reach=Big Cottonwood C,Reach-1
Reach XY= 30
      2672576.00      6912111.00      2672432.73      6911970.14
      2672419.45      6911970.33      2672382.05      6912002.88
      2672360.64      6912010.83      2672327.65      6912007.84
      2672302.53      6911988.29      2672181.47      6911863.45
      2672175.98      6911841.01      2672172.46      6911712.46
      2672099.58      6911633.83      2672070.15      6911613.04
      2671936.50      6911612.23      2671919.93      6911619.19
      2671874.25      6911657.66      2671832.03      6911659.38
      2671805.91      6911641.57      2671685.68      6911521.19
      2671665.38      6911511.59      2671636.70      6911511.70
      2671620.07      6911518.74      2671578.19      6911554.82
      2671519.93      6911569.13      2671439.39      6911647.67
      2671427.16      6911671.48      2671422.43      6911759.93
      2671389.86      6911797.78      2671376.33      6911804.56
      2671366.21      6911800.99      2671326.00      6911761.00

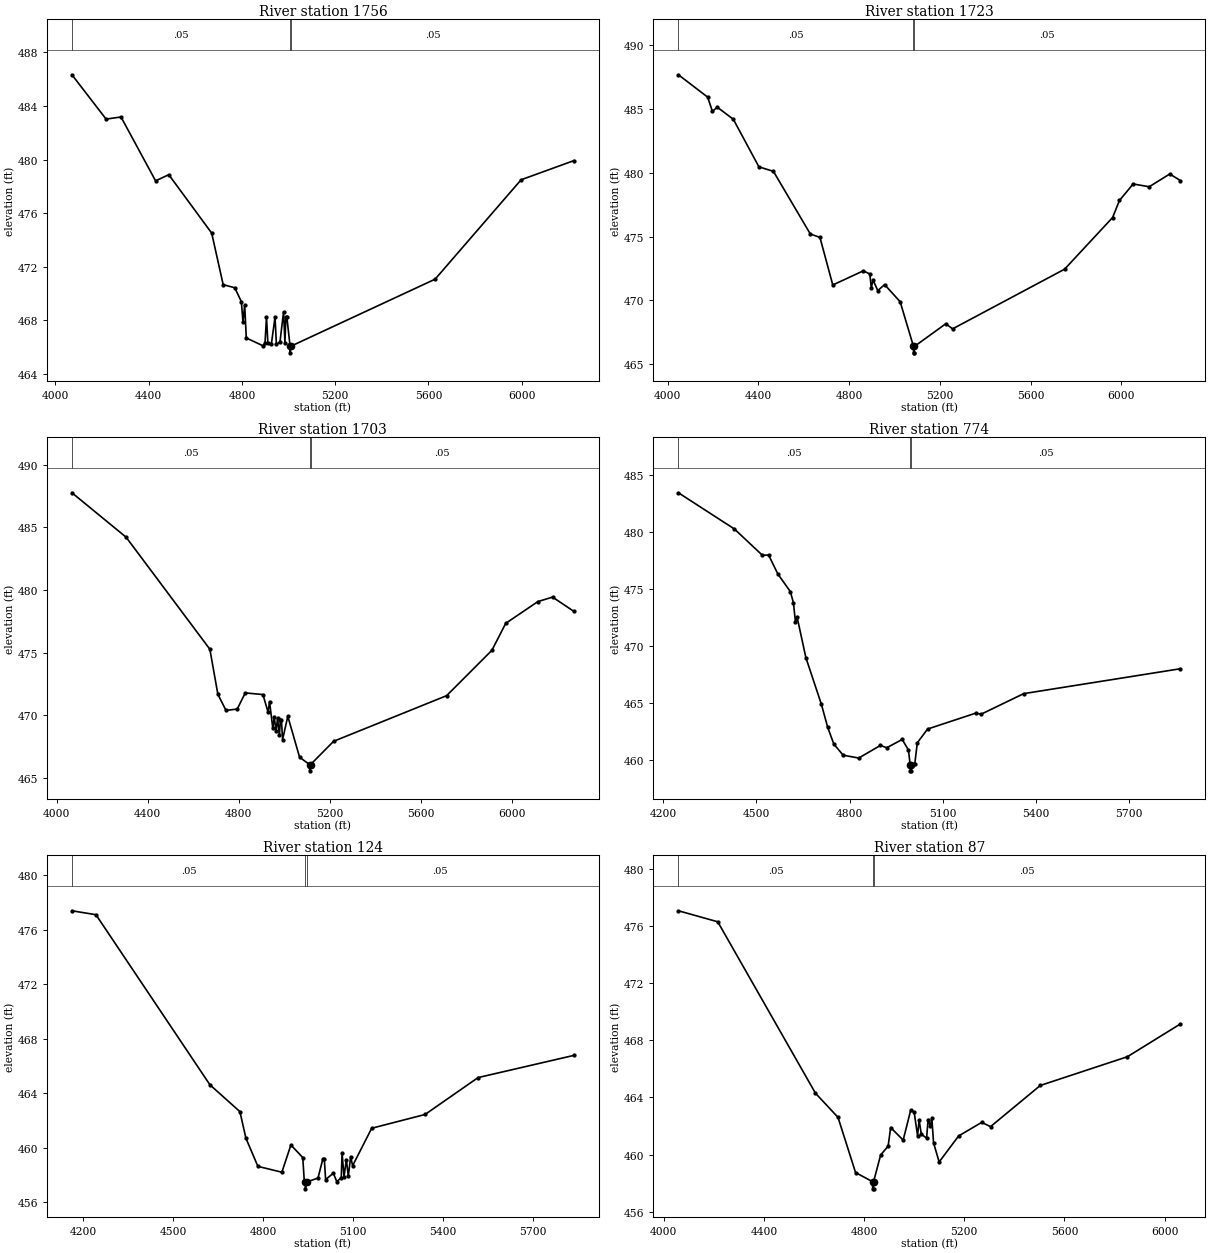
Type RM Length L Ch R = 1,1756,33,33,33
BEGIN DESCRIPTION:
Mapping XS 6af57be3
END DESCRIPTION:
XS GIS Cut Line= 6
      2673210.48      6911438.12      2672654.91      6911971.99
      2672529.05      6912050.11      2672494.32      6912132.58
      2672468.28      6912236.74      2672333.73      6913265.39
#Sta/Elev= 30
  4070.8  486.33  4217.3  483.02  4281.2  483.18  4429.6  478.41  4486.2  478.87
  4670.2  474.51  4719.5  470.66  4769.2  470.43  4797.5  469.39  4804.5  467.85
  4811.7  469.15  4818.6  466.68  4889.9  466.10  4898.9  466.29  4905.3  468.24
  4911.2  466.32  4926.5  466.26  4941.9  468.24  4947.8  466.20  4963.1  466.38
  4978.5  468.63  4984.4  466.33  4988.3  468.24  4992.6  468.24  5006.4  466.07
  5006.7  465.57  5010.4  466.07  5628.6  471.07  5997.4  478.49  6223.7  479.92
#Mann=3,-1,0
  4070.8    0.05       0  5006.4    0.03       0  5010.4    0.05       0
Bank Sta=5006.4,5010.4
Exp/Cntr=0.3,0.1

Type RM Length L Ch R = 1,1723,20,20,20
BEGIN DESCRIPTION:
Mapping XS a3049633
END DESCRIPTION:
XS GIS Cut Line= 6
      2673201.76      6911394.76      2672680.95      6911893.86
      2672550.75      6912006.71      2672503.00      6912032.75
      2672437.90      6912206.36      2672307.83      6913277.24
#Sta/Elev= 30
  4048.0  487.68  4176.8  485.93  4197.9  484.81  4219.2  485.14  4290.0  484.19
  4402.9  480.46  4466.7  480.11  4629.3  475.20  4671.8  474.93  4728.4  471.20
  4863.1  472.31  4891.6  472.06  4898.2  470.98  4905.8  471.59  4926.7  470.76
  4956.9  471.23  5025.5  469.88  5084.1  466.38  5084.3  465.88  5087.8  465.88
  5088.1  466.38  5226.4  468.16  5256.6  467.76  5750.2  472.44  5961.8  476.49
  5992.0  477.83  6052.4  479.12  6123.0  478.90  6213.6  479.90  6260.2  479.39
#Mann=3,-1,0
  4048.0    0.05       0  5084.1    0.03       0  5088.1    0.05       0
Bank Sta=5084.1,5088.1
Exp/Cntr=0.3,0.1

Type RM Length L Ch R = 1,1703,929,929,929
BEGIN DESCRIPTION:
Mapping XS 01f85ca7
END DESCRIPTION:
XS GIS Cut Line= 5
      2673175.76      6911394.71      2672594.15      6911928.58
      2672494.32      6912006.71      2672407.52      6912197.68
      2672268.86      6913267.91
#Sta/Elev= 30
  4066.9  487.77  4304.8  484.22  4672.9  475.26  4708.0  471.66  4743.8  470.37
  4793.1  470.48  4828.3  471.77  4906.0  471.64  4928.6  470.23  4935.0  471.08
  4949.4  468.95  4955.8  469.82  4963.9  468.71  4970.2  469.77  4978.3  468.37
  4982.6  469.61  4987.2  469.61  4992.3  468.04  5015.3  469.90  5067.0  466.63
  5111.1  466.04  5111.4  465.54  5115.1  466.04  5216.4  467.90  5713.1  471.55
  5912.2  475.18  5972.7  477.33  6113.9  479.07  6178.5  479.43  6272.1  478.29
#Mann=3,-1,0
  4066.9    0.05       0  5111.1    0.03       0  5115.1    0.05       0
Bank Sta=5111.1,5115.1
Exp/Cntr=0.3,0.1

Type RM Length L Ch R = 1,774,650,650,650
BEGIN DESCRIPTION:
Big Cottonwood Creek Trib 1_1 2.0
END DESCRIPTION:
XS GIS Cut Line= 3
      2671826.00      6910910.95      2671855.79      6911661.36
      2672067.25      6912500.01
#Sta/Elev= 30
  4249.0  483.43  4429.2  480.26  4519.3  477.96  4539.3  477.98  4569.3  476.31
  4609.3  474.78  4619.3  473.80  4625.8  472.11  4630.8  472.58  4659.4  468.99
  4709.4  464.90  4729.4  462.91  4749.4  461.42  4779.5  460.45  4829.5  460.20
  4899.6  461.31  4919.6  461.10  4969.6  461.83  4989.6  460.90  4995.3  459.58
  4995.6  459.08  4999.1  459.08  4999.3  459.58  5009.9  459.68  5018.2  461.54
  5051.2  462.74  5205.9  464.13  5223.6  464.04  5360.6  465.84  5864.9  468.02
#Mann=3,-1,0
  4249.0    0.05       0  4995.3    0.04       0  4999.3    0.05       0
Bank Sta=4995.3,4999.3
Exp/Cntr=0.3,0.1

Type RM Length L Ch R = 1,124,37,37,37
BEGIN DESCRIPTION:
Mapping XS 585559a6
END DESCRIPTION:
XS GIS Cut Line= 6
      2671417.70      6910930.87      2671408.41      6911682.36
      2671418.21      6911767.75      2671438.36      6911825.15
      2671480.89      6911875.50      2671941.07      6912415.86
#Sta/Elev= 30
  4162.5  477.40  4242.6  477.11  4622.7  464.62  4722.7  462.65  4742.7  460.70
  4782.7  458.63  4862.7  458.20  4892.7  460.20  4932.3  459.28  4937.3  457.59
  4940.9  457.48  4941.1  456.98  4944.9  457.48  4983.1  457.77  4999.1  459.16
  5004.2  459.16  5008.6  457.66  5034.3  458.13  5045.8  457.51  5060.8  457.80
  5063.4  459.62  5070.0  457.87  5077.7  459.13  5084.3  457.90  5092.0  459.35
  5098.6  458.68  5162.3  461.43  5340.2  462.44  5517.0  465.15  5836.5  466.78
#Mann=3,-1,0
  4162.5    0.05       0  4940.9    0.03       0  4944.9    0.05       0
Bank Sta=4940.9,4944.9
Exp/Cntr=0.3,0.1

Type RM Length L Ch R = 1,87,23,23,23
BEGIN DESCRIPTION:
Mapping XS 50ea2af4
END DESCRIPTION:
XS GIS Cut Line= 4
      2671402.07      6910853.99      2671393.23      6911794.95
      2671438.53      6911861.83      2672081.36      6912603.55
#Sta/Elev= 30
  4059.0  477.06  4216.0  476.29  4606.0  464.30  4696.0  462.61  4766.0  458.75
  4834.0  458.11  4834.3  457.61  4837.8  457.61  4838.0  458.11  4866.0  459.97
  4896.1  460.60  4906.1  461.90  4956.1  461.02  4986.1  463.11  5000.0  462.97
  5013.6  461.32  5019.6  462.42  5028.6  461.43  5049.6  461.16  5055.6  462.46
  5064.5  461.98  5070.5  462.57  5077.3  460.83  5099.7  459.49  5177.5  461.31
  5269.7  462.26  5304.8  461.96  5503.3  464.84  5850.9  466.85  6062.3  469.14
#Mann=3,-1,0
  4059.0    0.05       0  4834.0    0.03       0  4838.0    0.05       0
Bank Sta=4834,4838
Exp/Cntr=0.3,0.1

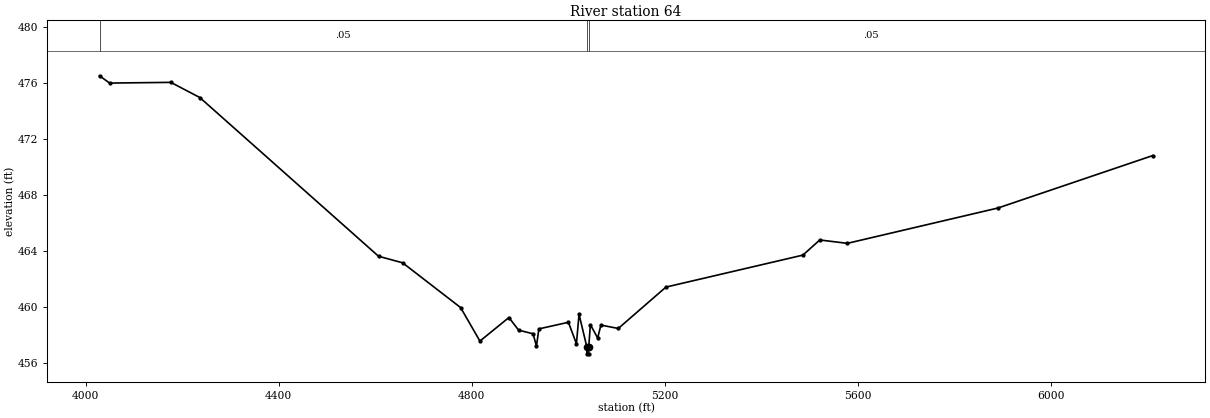
Type RM Length L Ch R = 1,64,0,0,0
BEGIN DESCRIPTION:
Big Cottonwood Creek Trib 1_1 1.0
END DESCRIPTION:
XS GIS Cut Line= 5
      2671381.48      6910833.32      2671364.31      6911520.69
      2671372.95      6911804.18      2671394.95      6911855.10
      2672158.91      6912721.12
#Sta/Elev= 30
  4028.8  476.50  4049.7  475.98  4176.5  476.03  4236.5  474.95  4606.7  463.63
  4656.7  463.16  4776.7  459.97  4816.7  457.58  4876.8  459.26  4896.8  458.36
  4926.8  458.10  4933.8  457.22  4938.8  458.45  5000.0  458.92  5016.6  457.39
  5022.0  459.49  5038.1  457.17  5038.3  456.67  5041.8  456.67  5042.1  457.17
  5045.5  458.75  5060.6  457.80  5067.3  458.72  5103.3  458.48  5202.0  461.43
  5485.6  463.71  5520.7  464.79  5577.7  464.55  5889.7  467.07  6210.3  470.81
#Mann=3,-1,0
  4028.8    0.05       0  5038.1    0.03       0  5042.1    0.05       0
Bank Sta=5038.1,5042.1
Exp/Cntr=0.3,0.1

Chan Stop Cuts=-1