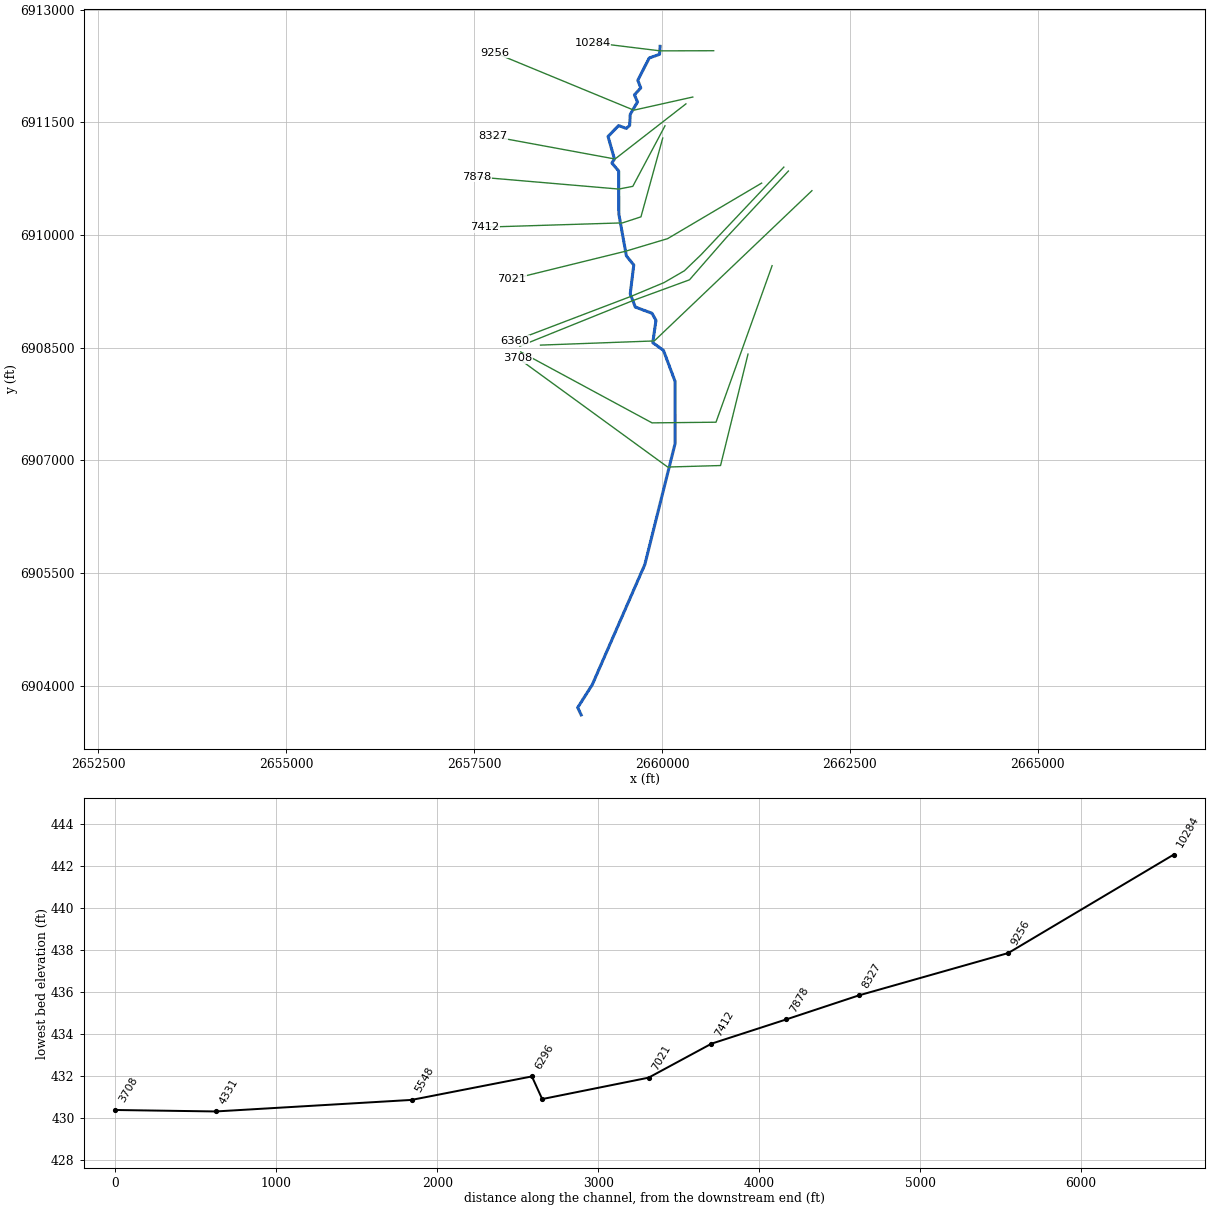
--- Big Cottonwood Creek Trib 2.prj (project) ---

Proj Title=Big Cottonwood Creek Trib 2 Base Level Engineering
Current Plan=p01
Default Exp/Contr=0.3,0.1
English Units
Geom File=g01
Flow File=f01
Plan File=p01
BEGIN DESCRIPTION:
Big Cottonwood Creek Trib 2
END DESCRIPTION:

--- Big Cottonwood Creek Trib 2.p01 (plan) ---

Plan Title=Multiple Run
Short Identifier=Multiple
Geom File=g01
Flow File=f01
Subcritical Flow
K Sum by GR= 0
Std Step Tol= 0.01
Critical Tol= 0.01
Num of Std Step Trials= 20
Max Error Tol= 0.3
Flow Tol Ratio= 0.001
Split Flow NTrial= 30
Split Flow Tol= 0.02
Split Flow Ratio= 0.02
Log Output Level= 0
Friction Slope Method= 1
Unsteady Friction Slope Method= 2
Unsteady Bridges Friction Slope Method= 1
Parabolic Critical Depth
Global Vel Dist=  1 , 1 , 1
Global Log Level= 0
CheckData=True
Encroach Param= -1, 0, 0, 0
BEGIN DESCRIPTION:
Multiple Run
END DESCRIPTION:

--- Big Cottonwood Creek Trib 2.f01 (steady flow) ---

Flow Title=Multiple
Number of Profiles=7
Profile Names=10-year,25-year,50-year,1pct_min,100-year,1pct_plu,500-year
River Rch & RM= Big Cottonwood C,Reach-1,10284
     450     588     697     409     816    1629    1120
River Rch & RM= Big Cottonwood C,Reach-1,6360
     835    1139    1388     837    1671    3334    2423
River Rch & RM= Big Cottonwood C,Reach-1,5548
     809    1097    1330     798    1593    3179    2288
Boundary for River Rch & Prof#=Big Cottonwood C,Reach-1,1
Up Type=0
Dn Type=3
Dn Slope=0.005
Boundary for River Rch & Prof#=Big Cottonwood C,Reach-1,2
Up Type=0
Dn Type=3
Dn Slope=0.005
Boundary for River Rch & Prof#=Big Cottonwood C,Reach-1,3
Up Type=0
Dn Type=3
Dn Slope=0.005
Boundary for River Rch & Prof#=Big Cottonwood C,Reach-1,4
Up Type=0
Dn Type=3
Dn Slope=0.005
Boundary for River Rch & Prof#=Big Cottonwood C,Reach-1,5
Up Type=0
Dn Type=3
Dn Slope=0.005
Boundary for River Rch & Prof#=Big Cottonwood C,Reach-1,6
Up Type=0
Dn Type=3
Dn Slope=0.005
Boundary for River Rch & Prof#=Big Cottonwood C,Reach-1,7
Up Type=0
Dn Type=3
Dn Slope=0.005

--- Big Cottonwood Creek Trib 2.g01 (geometry) ---

Geom Title=Existing Conditions

River Reach=Big Cottonwood C,Reach-1
Reach XY= 30
      2659976.00      6912511.00      2659968.41      6912404.41
      2659831.11      6912355.89      2659679.17      6912059.35
      2659718.15      6911957.59      2659633.85      6911864.41
      2659675.20      6911771.70      2659578.25      6911605.07
      2659570.54      6911457.99      2659526.33      6911418.25
      2659423.71      6911455.88      2659283.32      6911311.10
      2659368.19      6911010.90      2659334.01      6910957.67
      2659424.94      6910850.57      2659426.07      6910281.03
      2659527.06      6909721.44      2659625.40      6909600.38
      2659578.10      6909216.87      2659645.46      6909040.46
      2659867.69      6908957.85      2659920.37      6908863.36
      2659877.97      6908566.68      2660020.27      6908463.55
      2660174.78      6908050.50      2660175.48      6907226.22
      2659772.17      6905612.58      2659072.38      6904012.50
      2658879.31      6903709.33      2658926.00      6903611.00

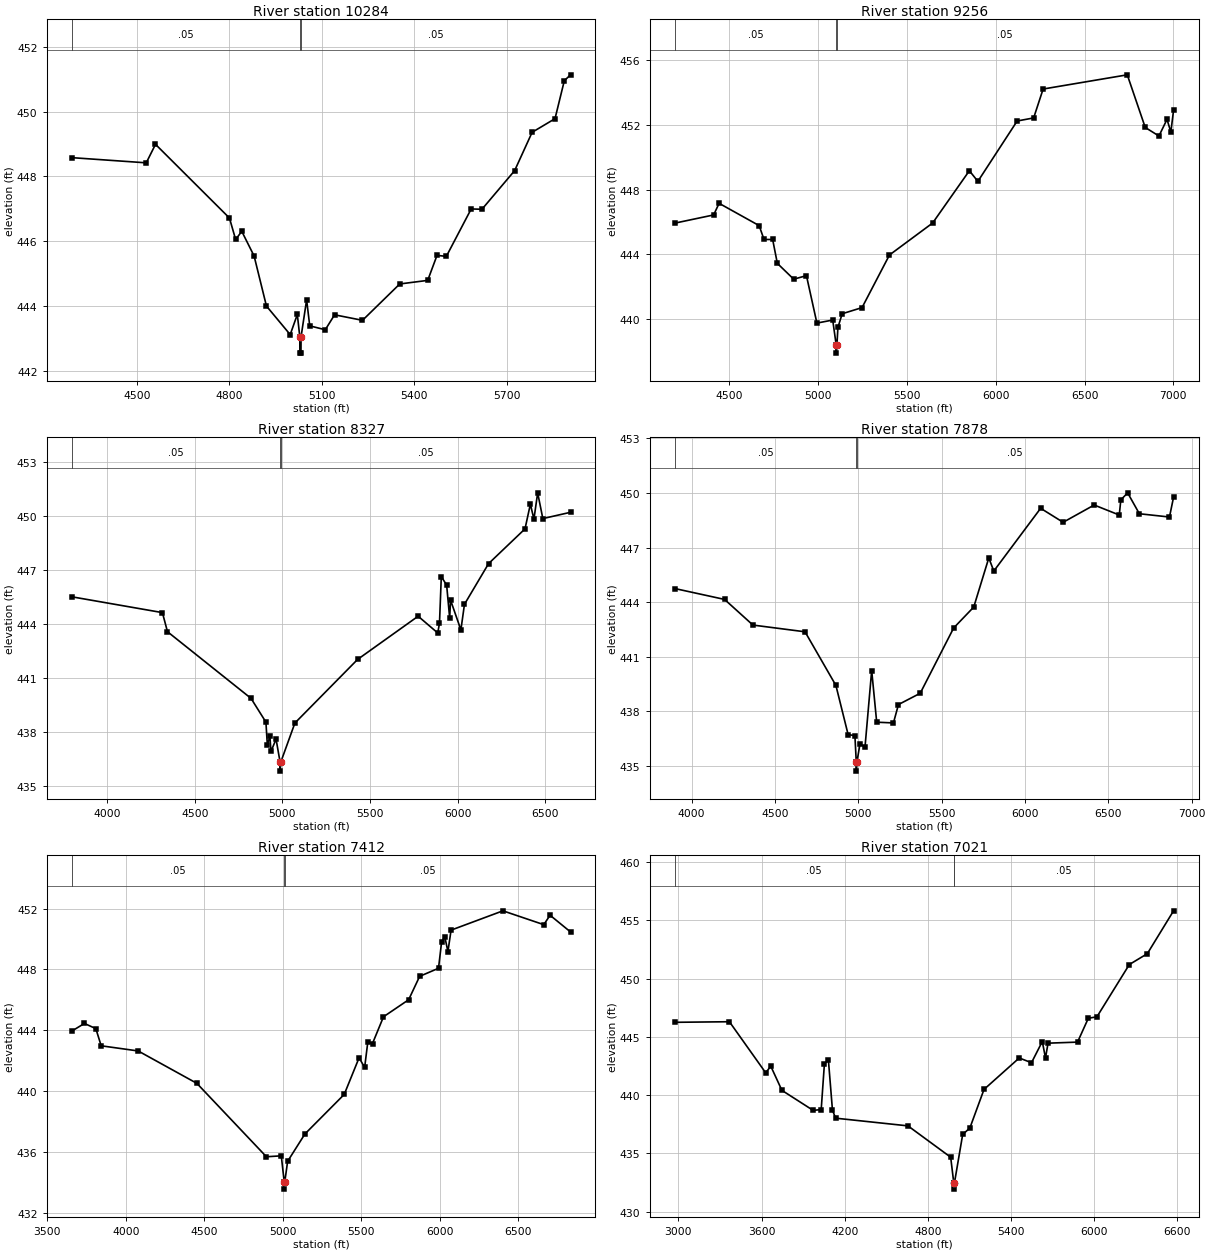
Type RM Length L Ch R = 1,10284,1028,1028,1028
BEGIN DESCRIPTION:
Big Cottonwood Creek Trib 2 13.0
END DESCRIPTION:
XS GIS Cut Line= 3
      2660688.22      6912452.38      2659976.82      6912450.60
      2659075.96      6912561.00
#Sta/Elev= 30
  4288.6  448.58  4530.8  448.42  4560.8  448.99  4800.8  446.72  4820.8  446.06
  4840.8  446.31  4880.8  445.55  4920.8  444.01  4997.9  443.13  5021.0  443.75
  5029.1  443.06  5029.3  442.56  5032.8  442.56  5033.1  443.06  5051.2  444.20
  5061.3  443.40  5111.7  443.28  5141.9  443.74  5232.5  443.57  5353.4  444.69
  5444.1  444.80  5474.3  445.57  5504.6  445.54  5585.2  447.00  5620.1  446.99
  5726.2  448.18  5782.9  449.36  5857.2  449.78  5887.4  450.95  5907.6  451.13
#Mann=3,-1,0
  4288.6    0.05       0  5029.1    0.04       0  5033.1    0.05       0
Bank Sta=5029.1,5033.1
Exp/Cntr=0.3,0.1

Type RM Length L Ch R = 1,9256,929,929,929
BEGIN DESCRIPTION:
Big Cottonwood Creek Trib 2 12.0
END DESCRIPTION:
XS GIS Cut Line= 3
      2660410.47      6911836.07      2659626.00      6911661.00
      2657771.96      6912426.17
#Sta/Elev= 30
  4191.7  445.92  4411.4  446.43  4442.2  447.15  4667.6  445.77  4695.1  444.91
  4743.7  444.91  4770.1  443.43  4862.3  442.45  4934.0  442.67  4992.9  439.73
  5081.9  439.92  5101.6  438.37  5101.9  437.87  5105.6  438.37  5111.2  439.46
  5135.2  440.31  5247.1  440.69  5401.5  443.95  5644.6  445.93  5851.4  449.17
  5899.3  448.51  6120.6  452.25  6213.4  452.44  6266.7  454.23  6740.6  455.11
  6841.7  451.85  6918.9  451.32  6964.4  452.35  6986.0  451.56  7001.2  452.92
#Mann=3,-1,0
  4191.7    0.05       0  5101.6    0.05       0  5105.6    0.05       0
Bank Sta=5101.6,5105.6
Exp/Cntr=0.3,0.1

Type RM Length L Ch R = 1,8327,449,449,449
BEGIN DESCRIPTION:
Big Cottonwood Creek Trib 2 11.0
END DESCRIPTION:
XS GIS Cut Line= 3
      2660319.26      6911744.89      2659376.00      6911011.00
      2657750.44      6911310.78
#Sta/Elev= 30
  3796.7  445.53  4315.0  444.65  4343.9  443.59  4820.8  439.89  4905.9  438.57
  4914.0  437.30  4928.5  437.78  4934.8  436.94  4963.8  437.63  4986.7  436.35
  4986.9  435.85  4990.7  436.35  5071.3  438.52  5429.1  442.05  5774.8  444.45
  5886.7  443.52  5896.7  444.06  5907.0  446.65  5937.5  446.18  5954.8  444.35
  5959.9  445.34  6018.9  443.69  6039.2  445.11  6176.9  447.37  6384.9  449.30
  6415.4  450.67  6435.8  449.84  6457.1  451.30  6486.6  449.87  6644.8  450.22
#Mann=3,-1,0
  3796.7    0.05       0  4986.7    0.04       0  4990.7    0.05       0
Bank Sta=4986.7,4990.7
Exp/Cntr=0.3,0.1

Type RM Length L Ch R = 1,7878,466,466,466
BEGIN DESCRIPTION:
Big Cottonwood Creek Trib 2 10.0
END DESCRIPTION:
XS GIS Cut Line= 4
      2660040.56      6911452.64      2659612.27      6910647.16
      2659426.00      6910611.00      2657541.54      6910772.69
#Sta/Elev= 30
  3898.0  444.75  4197.6  444.15  4367.8  442.74  4680.4  442.37  4865.7  439.42
  4938.9  436.72  4979.6  436.66  4987.8  435.21  4988.1  434.71  4991.8  435.21
  5010.1  436.21  5040.2  436.03  5080.3  440.24  5110.4  437.40  5210.8  437.36
  5240.9  438.37  5371.4  438.99  5572.1  442.58  5692.6  443.73  5782.9  446.43
  5813.0  445.71  6094.0  449.16  6228.9  448.39  6415.2  449.34  6565.7  448.79
  6575.0  449.62  6615.9  450.01  6686.2  448.86  6866.9  448.68  6891.4  449.77
#Mann=3,-1,0
  3898.0    0.05       0  4987.8    0.03       0  4991.8    0.05       0
Bank Sta=4987.8,4991.8
Exp/Cntr=0.3,0.1

Type RM Length L Ch R = 1,7412,391,391,391
BEGIN DESCRIPTION:
Big Cottonwood Creek Trib 2 9.0
END DESCRIPTION:
XS GIS Cut Line= 4
      2660010.53      6911289.64      2659720.93      6910241.21
      2659476.00      6910161.00      2657645.70      6910104.29
#Sta/Elev= 30
  3655.0  443.94  3736.6  444.45  3809.2  444.11  3843.3  442.98  4078.9  442.64
  4452.4  440.51  4895.2  435.68  4989.9  435.74  5008.4  434.05  5008.7  433.55
  5012.4  434.05  5030.4  435.38  5140.5  437.18  5390.6  439.78  5485.2  442.19
  5520.7  441.56  5540.7  443.22  5570.7  443.13  5640.7  444.89  5800.8  446.01
  5870.8  447.55  5990.9  448.08  6010.9  449.83  6030.9  450.15  6050.9  449.18
  6070.9  450.59  6401.1  451.86  6661.2  450.95  6701.2  451.57  6831.6  450.47
#Mann=3,-1,0
  3655.0    0.05       0  5008.4    0.03       0  5012.4    0.05       0
Bank Sta=5008.4,5012.4
Exp/Cntr=0.3,0.1

Type RM Length L Ch R = 1,7021,661,661,661
BEGIN DESCRIPTION:
Big Cottonwood Creek Trib 2 8.0
END DESCRIPTION:
XS GIS Cut Line= 4
      2661326.21      6910690.21      2660075.25      6909950.95
      2659522.52      6909785.27      2657999.08      6909410.29
#Sta/Elev= 30
  2973.3  446.25  3368.5  446.30  3630.0  441.92  3667.1  442.48  3747.1  440.41
  3972.5  438.69  4030.6  438.76  4053.8  442.69  4082.6  443.01  4111.9  438.70
  4135.1  438.02  4656.5  437.36  4964.6  434.67  4987.3  432.43  4987.6  431.93
  4991.3  432.43  5051.3  436.63  5102.8  437.17  5205.1  440.49  5459.3  443.19
  5547.5  442.78  5625.4  444.60  5648.6  443.19  5666.9  444.46  5879.7  444.55
  5957.5  446.60  6019.4  446.72  6253.3  451.21  6383.0  452.14  6572.3  455.82
#Mann=3,-1,0
  2973.3    0.05       0  4987.3    0.03       0  4991.3    0.05       0
Bank Sta=4987.3,4991.3
Exp/Cntr=0.3,0.1

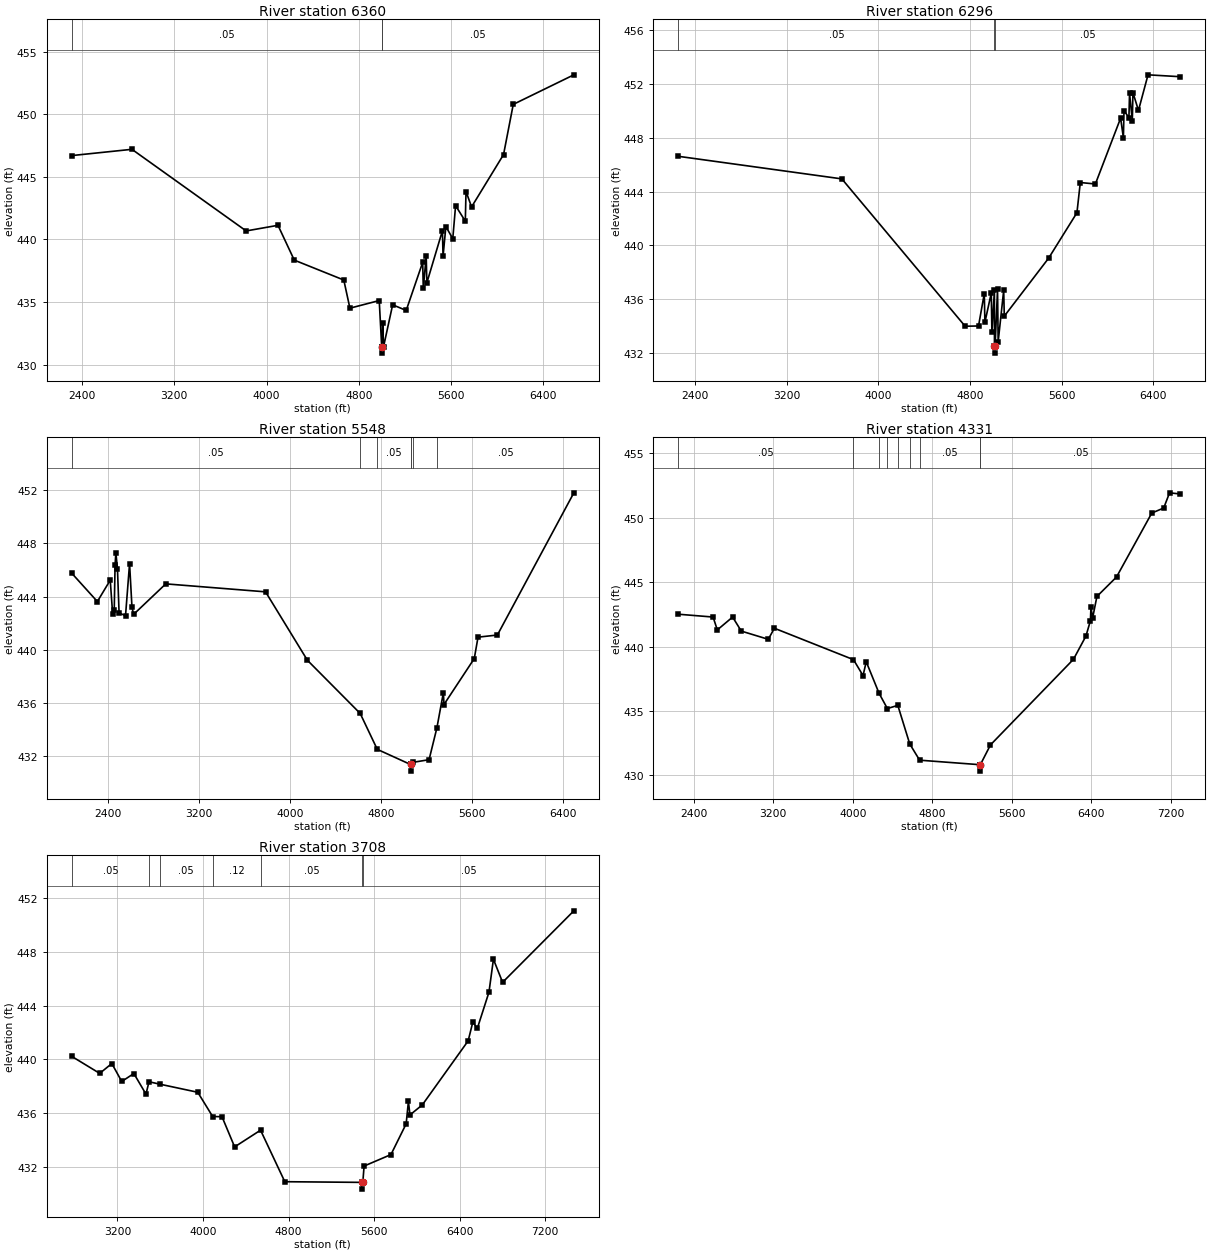
Type RM Length L Ch R = 1,6360,64,64,64
BEGIN DESCRIPTION:
Mapping XS bef77189
END DESCRIPTION:
XS GIS Cut Line= 6
      2661621.38      6910902.90      2660518.95      6909735.37
      2660297.60      6909522.69      2660028.50      6909366.44
      2659603.15      6909188.49      2658044.95      6908593.86
#Sta/Elev= 30
  2311.5  446.69  2833.1  447.19  3823.5  440.67  4099.3  441.12  4240.5  438.34
  4669.9  436.75  4722.9  434.50  4977.1  435.11  4998.6  431.41  4999.4  430.91
  5004.0  431.41  5006.6  433.33  5014.7  431.43  5093.4  434.77  5210.9  434.32
  5353.8  438.16  5359.1  436.10  5384.5  438.67  5389.8  436.52  5525.1  440.69
  5530.4  438.64  5554.9  441.02  5614.7  440.05  5639.2  442.69  5723.4  441.45
  5729.5  443.82  5777.7  442.59  6054.9  446.77  6139.1  450.78  6664.4  453.14
#Mann=3,-1,0
  2311.5    0.05       0  4998.6    0.03       0  5004.0    0.05       0
Bank Sta=4998.6,5004
Exp/Cntr=0.3,0.1

Type RM Length L Ch R = 1,6296,748,748,748
BEGIN DESCRIPTION:
Mapping XS a1827473
END DESCRIPTION:
XS GIS Cut Line= 5
      2661682.17      6910850.84      2660853.15      6909961.06
      2660366.56      6909402.99      2659616.17      6909127.73
      2658110.53      6908520.26
#Sta/Elev= 30
  2254.7  446.63  3681.8  444.95  4757.3  433.99  4874.0  434.01  4924.3  436.42
  4929.6  434.28  4985.3  436.47  4990.6  433.55  5012.8  436.67  5012.9  432.49
  5013.7  431.99  5018.3  432.49  5039.8  436.73  5045.2  432.83  5093.5  436.66
  5098.8  434.74  5485.2  439.05  5732.3  442.43  5761.8  444.68  5893.3  444.57
  6113.5  449.47  6137.6  448.00  6143.0  450.02  6185.9  449.51  6191.3  451.33
  6215.4  449.27  6220.8  451.37  6269.1  450.04  6352.4  452.69  6634.1  452.55
#Mann=3,-1,0
  2254.7    0.05       0  5012.9    0.03       0  5018.3    0.05       0
Bank Sta=5012.9,5018.3
Exp/Cntr=0.3,0.1

Type RM Length L Ch R = 1,5548,1217,1217,1217
BEGIN DESCRIPTION:
Mapping XS 7636acfc
END DESCRIPTION:
XS GIS Cut Line= 3
      2661995.51      6910589.53      2659898.29      6908589.53
      2658384.39      6908533.98
#Sta/Elev= 30
  2079.3  445.76  2304.2  443.63  2417.4  445.24  2438.5  442.71  2452.6  443.03
  2459.9  446.37  2466.8  447.30  2480.9  446.10  2495.1  442.78  2551.7  442.56
  2587.3  446.49  2608.3  443.22  2622.5  442.66  2905.6  444.96  3782.5  444.36
  4150.5  439.21  4614.3  435.21  4764.3  432.51  5056.9  431.37  5057.7  430.87
  5062.3  431.37  5076.8  431.53  5219.7  431.73  5288.4  434.12  5345.5  436.78
  5350.6  435.88  5617.0  439.34  5650.0  440.95  5820.1  441.11  6492.2  451.81
#Mann=7,-1,0
  2079.3    0.05       0  4614.3    0.12       0  4764.3    0.05       0
  5056.9    0.03       0  5062.3    0.05       0  5076.8    0.12       0
  5288.4    0.05       0
Bank Sta=5056.9,5062.3
Exp/Cntr=0.3,0.1

Type RM Length L Ch R = 1,4331,623,623,623
BEGIN DESCRIPTION:
Mapping XS a53e2465
END DESCRIPTION:
XS GIS Cut Line= 4
      2661465.54      6909591.03      2660719.01      6907507.67
      2659868.31      6907498.99      2658120.77      6908443.56
#Sta/Elev= 30
  2243.9  442.51  2594.5  442.29  2637.0  441.29  2791.0  442.29  2877.9  441.20
  3149.4  440.56  3211.0  441.42  4006.7  438.98  4102.9  437.74  4134.8  438.82
  4264.4  436.36  4347.6  435.18  4452.5  435.43  4572.7  432.43  4672.0  431.17
  5277.2  430.82  5278.1  430.32  5282.8  430.82  5384.9  432.36  6219.7  439.01
  6344.8  440.81  6389.8  442.00  6395.5  443.08  6411.7  442.20  6455.4  443.89
  6652.4  445.40  7007.3  450.37  7127.3  450.76  7185.9  451.94  7294.2  451.85
#Mann=9,-1,0
  2243.9    0.05       0  4006.7    0.12       0  4264.4    0.05       0
  4347.6    0.12       0  4452.5    0.05       0  4572.7     0.1       0
  4672.0    0.05       0  5277.2    0.03       0  5282.8    0.05       0
Bank Sta=5277.2,5282.8
Exp/Cntr=0.3,0.1

Type RM Length L Ch R = 1,3708,0,0,0
BEGIN DESCRIPTION:
Big Cottonwood Creek Trib 2 1.0
END DESCRIPTION:
XS GIS Cut Line= 4
      2661144.86      6908414.64      2660779.63      6906931.11
      2660076.00      6906911.00      2658085.77      6908360.38
#Sta/Elev= 30
  2772.9  440.23  3034.1  438.97  3147.4  439.70  3240.1  438.37  3353.4  438.96
  3466.7  437.43  3494.8  438.35  3596.2  438.17  3950.7  437.57  4090.3  435.77
  4177.3  435.76  4295.4  433.52  4537.8  434.76  4764.5  430.94  5488.2  430.89
  5489.1  430.39  5493.8  430.89  5505.7  432.10  5756.8  432.95  5899.0  435.23
  5920.1  436.89  5934.5  435.89  6049.7  436.63  6478.5  441.38  6522.5  442.78
  6564.2  442.30  6673.2  444.99  6714.9  447.43  6800.7  445.72  7466.7  451.02
#Mann=7,-1,0
  2772.9    0.05       0  3494.8    0.12       0  3596.2    0.05       0
  4090.3    0.12       0  4537.8    0.05       0  5488.2    0.03       0
  5493.8    0.05       0
Bank Sta=5488.2,5493.8
Exp/Cntr=0.3,0.1

Chan Stop Cuts=-1