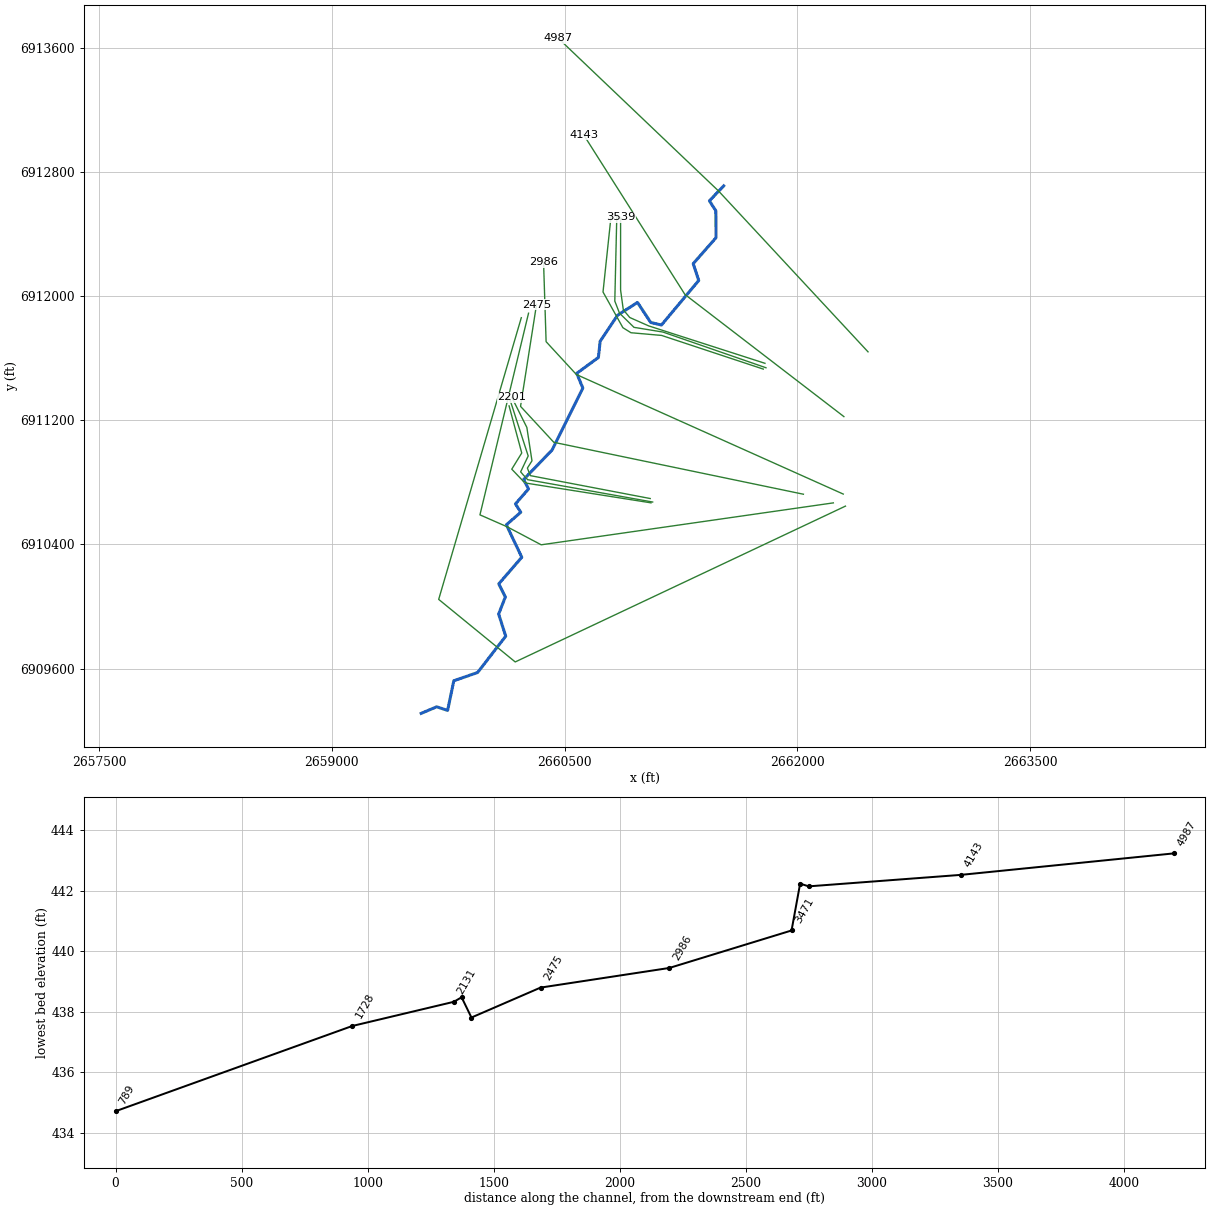
--- Big Cottonwood Creek Trib 2_1.prj (project) ---

Proj Title=Big Cottonwood Creek Trib 2_1 Base Level Engineering
Current Plan=p01
Default Exp/Contr=0.3,0.1
English Units
Geom File=g01
Flow File=f01
Plan File=p01
BEGIN DESCRIPTION:
Big Cottonwood Creek Trib 2_1
END DESCRIPTION:

--- Big Cottonwood Creek Trib 2_1.p01 (plan) ---

Plan Title=Multiple Run
Short Identifier=Multiple
Geom File=g01
Flow File=f01
Subcritical Flow
K Sum by GR= 0
Std Step Tol= 0.01
Critical Tol= 0.01
Num of Std Step Trials= 20
Max Error Tol= 0.3
Flow Tol Ratio= 0.001
Split Flow NTrial= 30
Split Flow Tol= 0.02
Split Flow Ratio= 0.02
Log Output Level= 0
Friction Slope Method= 1
Unsteady Friction Slope Method= 2
Unsteady Bridges Friction Slope Method= 1
Parabolic Critical Depth
Global Vel Dist=  1 , 1 , 1
Global Log Level= 0
CheckData=True
Encroach Param= -1, 0, 0, 0
BEGIN DESCRIPTION:
Multiple Run
END DESCRIPTION:

--- Big Cottonwood Creek Trib 2_1.f01 (steady flow) ---

Flow Title=Multiple
Number of Profiles=7
Profile Names=10-year,25-year,50-year,1pct_min,100-year,1pct_plu,500-year
River Rch & RM= Big Cottonwood C,Reach-1,4987
     389     505     596     349     696    1389     949
River Rch & RM= Big Cottonwood C,Reach-1,2986
     392     511     604     354     706    1409     967
River Rch & RM= Big Cottonwood C,Reach-1,2162
     416     544     643     378     753    1503    1033
Boundary for River Rch & Prof#=Big Cottonwood C,Reach-1,1
Up Type=0
Dn Type=3
Dn Slope=0.005
Boundary for River Rch & Prof#=Big Cottonwood C,Reach-1,2
Up Type=0
Dn Type=3
Dn Slope=0.005
Boundary for River Rch & Prof#=Big Cottonwood C,Reach-1,3
Up Type=0
Dn Type=3
Dn Slope=0.005
Boundary for River Rch & Prof#=Big Cottonwood C,Reach-1,4
Up Type=0
Dn Type=3
Dn Slope=0.005
Boundary for River Rch & Prof#=Big Cottonwood C,Reach-1,5
Up Type=0
Dn Type=3
Dn Slope=0.005
Boundary for River Rch & Prof#=Big Cottonwood C,Reach-1,6
Up Type=0
Dn Type=3
Dn Slope=0.005
Boundary for River Rch & Prof#=Big Cottonwood C,Reach-1,7
Up Type=0
Dn Type=3
Dn Slope=0.005

--- Big Cottonwood Creek Trib 2_1.g01 (geometry) ---

Geom Title=Existing Conditions

River Reach=Big Cottonwood C,Reach-1
Reach XY= 30
      2661526.00      6912711.00      2661433.70      6912614.41
      2661475.02      6912550.36      2661475.99      6912376.36
      2661329.16      6912209.35      2661364.89      6912100.95
      2661124.54      6911814.00      2661055.54      6911830.26
      2660970.13      6911959.50      2660842.64      6911877.71
      2660729.63      6911709.50      2660718.14      6911604.81
      2660578.67      6911502.50      2660617.92      6911407.72
      2660420.17      6911008.69      2660235.57      6910817.59
      2660267.98      6910757.66      2660183.59      6910660.99
      2660218.06      6910607.44      2660125.08      6910526.43
      2660224.42      6910317.05      2660076.01      6910145.64
      2660118.40      6910061.01      2660075.25      6909950.95
      2660120.91      6909808.70      2659939.65      6909574.26
      2659786.33      6909521.17      2659746.49      6909330.16
      2659676.08      6909353.41      2659576.00      6909311.00

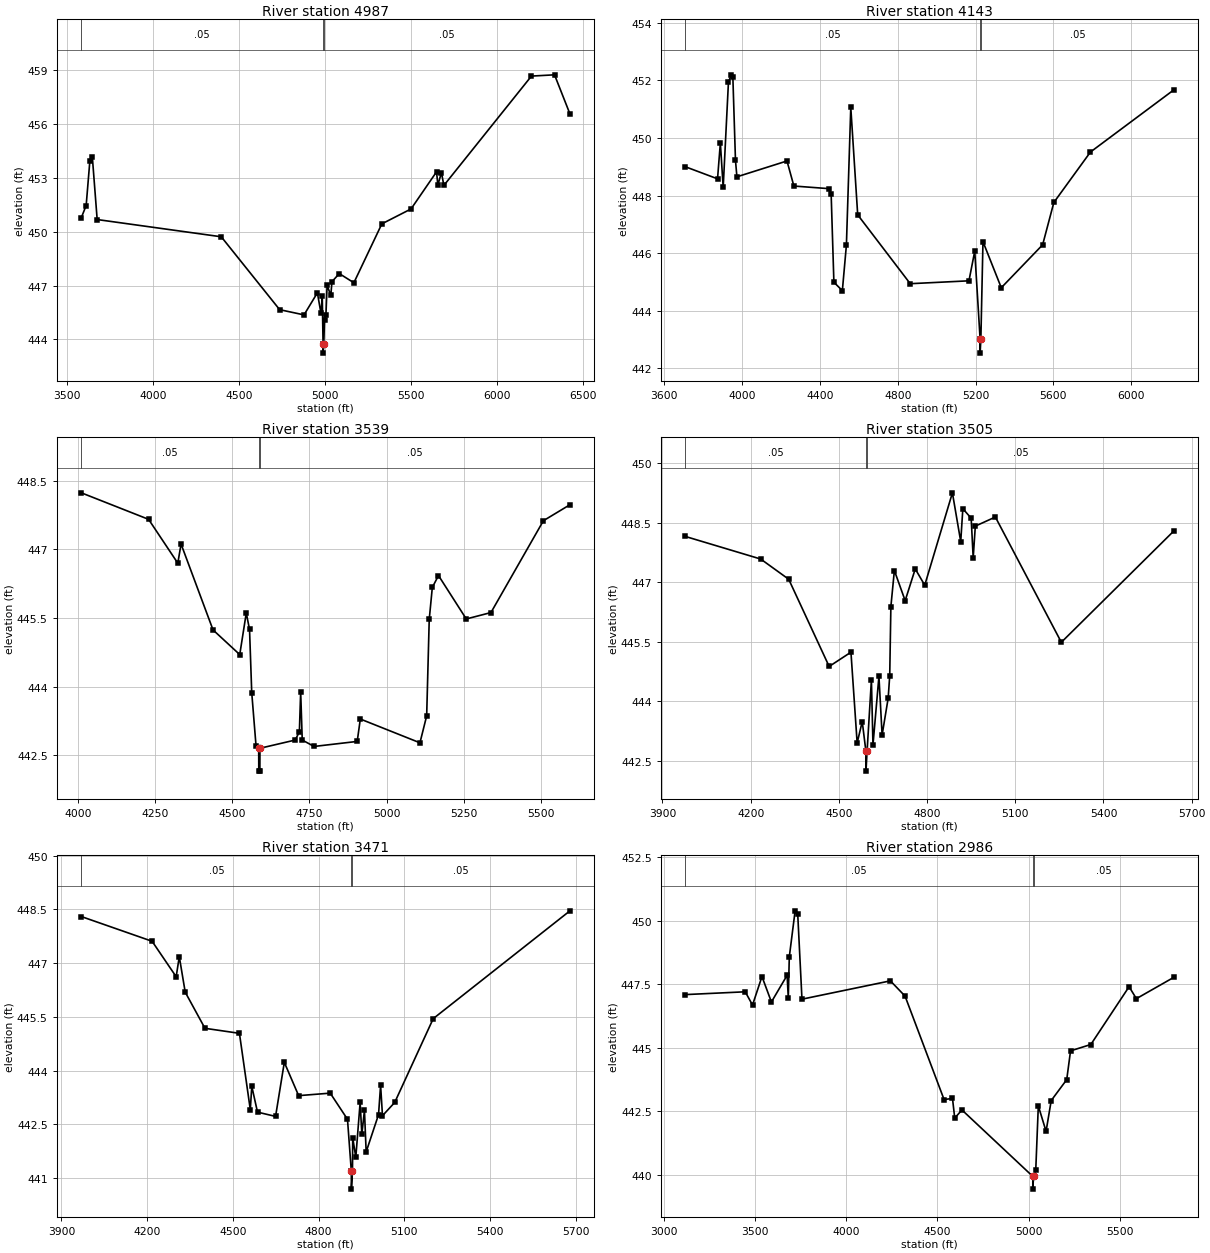
Type RM Length L Ch R = 1,4987,844,844,844
BEGIN DESCRIPTION:
Big Cottonwood Creek Trib 2_1 4.0
END DESCRIPTION:
XS GIS Cut Line= 3
      2662455.96      6911641.06      2661492.48      6912677.78
      2660459.98      6913661.64
#Sta/Elev= 30
  3584.7  450.79  3612.7  451.46  3634.2  453.95  3648.4  454.19  3676.7  450.68
  4398.4  449.72  4738.0  445.66  4879.7  445.37  4957.4  446.60  4978.4  445.45
  4985.7  446.41  4990.5  443.74  4990.8  443.24  4994.5  443.74  4998.8  445.10
  5007.0  445.34  5013.9  447.02  5035.3  446.45  5042.2  447.22  5084.7  447.67
  5169.6  447.16  5332.2  450.44  5502.0  451.27  5650.5  453.34  5657.7  452.60
  5678.8  453.29  5693.0  452.58  6202.2  458.67  6336.5  458.74  6426.2  456.56
#Mann=3,-1,0
  3584.7    0.05       0  4990.5    0.03       0  4994.5    0.05       0
Bank Sta=4990.5,4994.5
Exp/Cntr=0.3,0.1

Type RM Length L Ch R = 1,4143,604,604,604
BEGIN DESCRIPTION:
Big Cottonwood Creek Trib 2_1 3.0
END DESCRIPTION:
XS GIS Cut Line= 3
      2662300.47      6911223.62      2661275.89      6912010.86
      2660622.61      6913040.62
#Sta/Elev= 30
  3707.9  449.00  3873.6  448.58  3888.1  449.83  3902.6  448.28  3929.7  451.94
  3944.2  452.19  3952.4  452.10  3965.8  449.22  3973.2  448.65  4230.6  449.20
  4266.0  448.33  4444.5  448.24  4457.6  448.05  4471.7  444.99  4515.2  444.70
  4536.0  446.28  4558.5  451.06  4594.1  447.33  4864.1  444.94  5166.0  445.04
  5195.7  446.07  5223.2  443.03  5223.4  442.53  5227.2  443.03  5238.0  446.40
  5332.1  444.80  5544.7  446.29  5602.3  447.76  5790.4  449.51  6219.5  451.67
#Mann=3,-1,0
  3707.9    0.05       0  5223.2    0.03       0  5227.2    0.05       0
Bank Sta=5223.2,5227.2
Exp/Cntr=0.3,0.1

Type RM Length L Ch R = 1,3539,34,34,34
BEGIN DESCRIPTION:
Mapping XS 250580e7
END DESCRIPTION:
XS GIS Cut Line= 6
      2661791.82      6911567.19      2661041.79      6911808.52
      2660920.26      6911862.34      2660878.60      6911912.68
      2660861.23      6912039.42      2660861.23      6912507.04
#Sta/Elev= 30
  4010.9  448.24  4228.8  447.66  4323.5  446.70  4334.0  447.12  4437.6  445.24
  4524.2  444.70  4545.3  445.61  4555.9  445.25  4563.0  443.87  4577.0  442.70
  4585.6  442.65  4585.9  442.15  4589.4  442.15  4589.6  442.65  4703.8  442.83
  4717.4  443.01  4721.6  443.89  4726.7  442.83  4765.1  442.69  4904.8  442.80
  4914.9  443.29  5108.1  442.77  5129.9  443.36  5138.2  445.47  5148.2  446.17
  5168.2  446.43  5258.2  445.48  5338.2  445.62  5508.2  447.63  5594.2  447.98
#Mann=3,-1,0
  4010.9    0.05       0  4585.6    0.04       0  4589.6    0.05       0
Bank Sta=4585.6,4589.6
Exp/Cntr=0.3,0.1

Type RM Length L Ch R = 1,3505,34,34,34
BEGIN DESCRIPTION:
Mapping XS 3460210a
END DESCRIPTION:
XS GIS Cut Line= 6
      2661798.32      6911538.54      2661134.24      6911768.59
      2660947.61      6911798.97      2660854.29      6911890.11
      2660823.91      6911968.24      2660836.93      6912523.81
#Sta/Elev= 30
  3977.8  448.16  4234.2  447.59  4329.5  447.08  4467.1  444.88  4541.2  445.24
  4562.3  442.95  4579.6  443.49  4592.1  442.74  4592.3  442.24  4596.1  442.74
  4610.8  444.54  4616.1  442.90  4636.4  444.63  4647.2  443.15  4667.8  444.08
  4673.1  444.65  4677.0  446.39  4688.9  447.30  4725.6  446.54  4759.9  447.34
  4792.2  446.93  4886.3  449.26  4914.6  448.03  4921.8  448.86  4950.1  448.62
  4957.0  447.62  4964.2  448.42  5032.4  448.65  5256.8  445.49  5639.7  448.30
#Mann=3,-1,0
  3977.8    0.05       0  4592.1    0.03       0  4596.1    0.05       0
Bank Sta=4592.1,4596.1
Exp/Cntr=0.3,0.1

Type RM Length L Ch R = 1,3471,485,485,485
BEGIN DESCRIPTION:
Mapping XS 62dbf7c5
END DESCRIPTION:
XS GIS Cut Line= 6
      2661780.93      6911529.87      2661125.56      6911746.88
      2660928.07      6911764.25      2660875.99      6911796.80
      2660747.95      6912026.83      2660799.97      6912516.62
#Sta/Elev= 30
  3969.9  448.30  4217.4  447.61  4301.6  446.62  4312.5  447.18  4333.2  446.19
  4402.3  445.18  4522.9  445.04  4560.9  442.91  4566.1  443.56  4586.1  442.84
  4649.3  442.72  4679.9  444.23  4730.0  443.30  4840.5  443.37  4900.9  442.64
  4914.3  441.19  4914.5  440.69  4918.3  441.19  4919.2  442.12  4930.0  441.58
  4945.1  443.11  4951.1  442.22  4960.2  442.89  4966.2  441.73  5009.5  442.77
  5016.7  443.59  5023.3  442.74  5066.1  443.11  5200.8  445.45  5679.1  448.46
#Mann=3,-1,0
  3969.9    0.05       0  4914.3    0.03       0  4918.3    0.05       0
Bank Sta=4914.3,4918.3
Exp/Cntr=0.3,0.1

Type RM Length L Ch R = 1,2986,511,511,511
BEGIN DESCRIPTION:
Big Cottonwood Creek Trib 2_1 2.0
END DESCRIPTION:
XS GIS Cut Line= 4
      2662296.37      6910724.37      2660576.29      6911494.96
      2660381.17      6911706.53      2660364.83      6912217.06
#Sta/Elev= 30
  3115.2  447.09  3444.3  447.20  3484.4  446.68  3536.2  447.80  3588.1  446.80
  3674.4  447.85  3680.8  446.96  3686.3  448.57  3718.3  450.38  3732.7  450.24
  3755.9  446.91  4241.5  447.63  4322.1  447.03  4536.2  442.97  4582.6  443.01
  4594.9  442.24  4634.4  442.56  5023.6  439.95  5023.8  439.45  5027.6  439.95
  5039.8  440.19  5053.9  442.72  5096.5  441.72  5124.8  442.93  5209.9  443.75
  5230.9  444.88  5342.3  445.13  5552.4  447.40  5592.4  446.93  5798.6  447.77
#Mann=3,-1,0
  3115.2    0.05       0  5023.6    0.03       0  5027.6    0.05       0
Bank Sta=5023.6,5027.6
Exp/Cntr=0.3,0.1

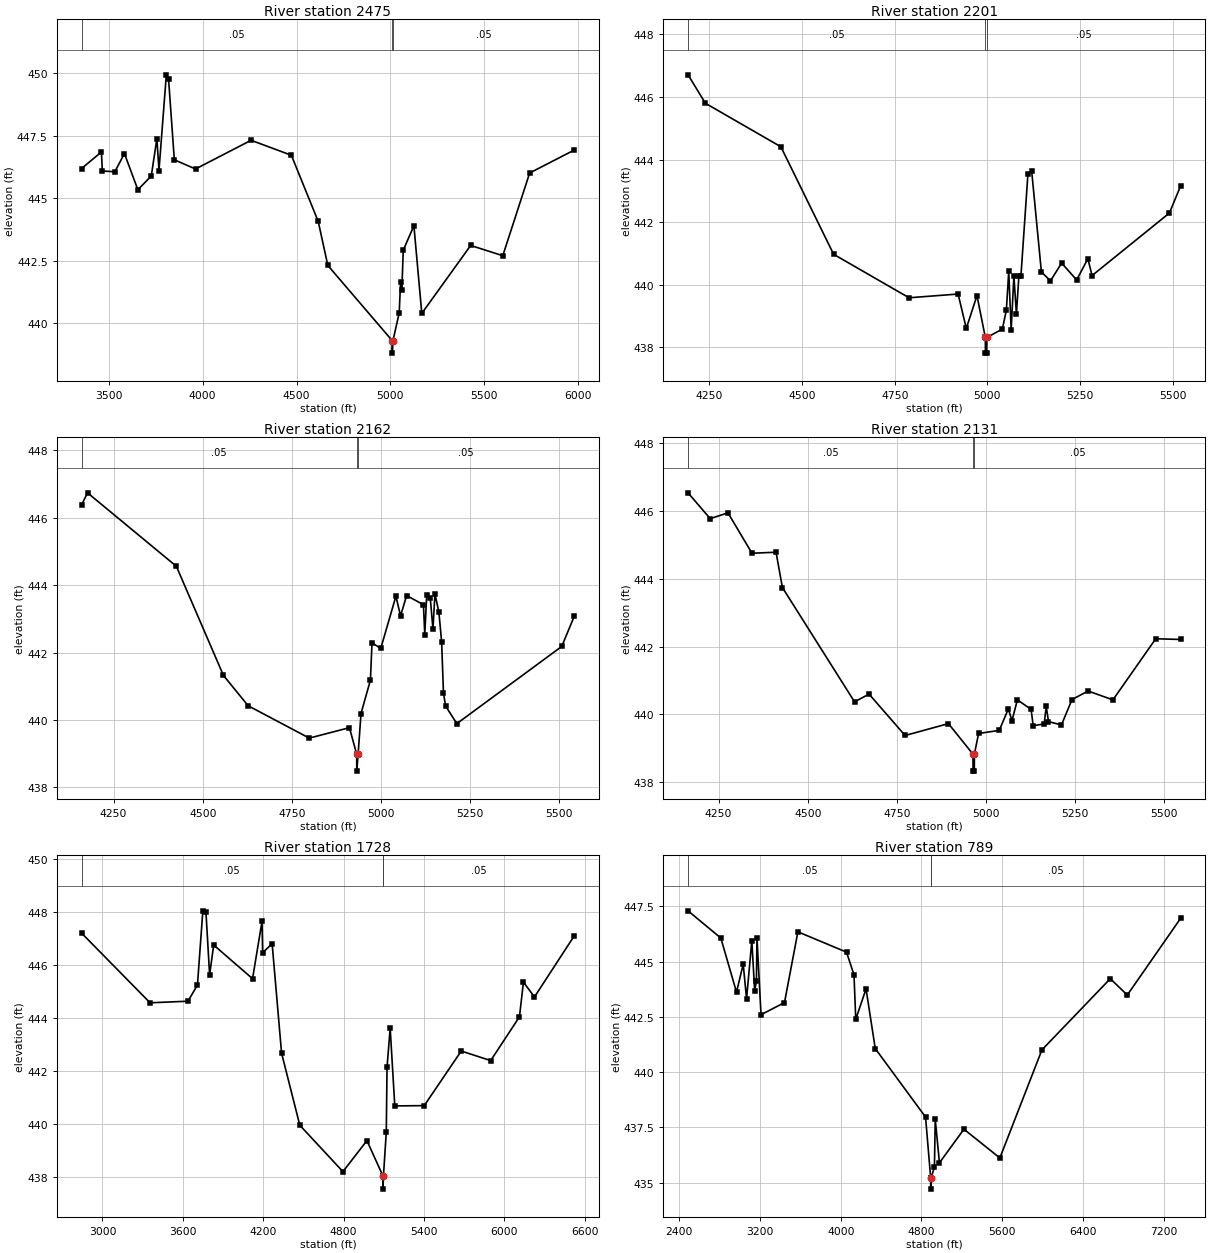
Type RM Length L Ch R = 1,2475,274,274,274
BEGIN DESCRIPTION:
Mapping XS 99263428
END DESCRIPTION:
XS GIS Cut Line= 4
      2662039.45      6910723.44      2660430.90      6911058.02
      2660216.43      6911289.65      2660319.38      6911945.96
#Sta/Elev= 30
  3355.8  446.19  3461.5  446.85  3466.6  446.09  3533.0  446.06  3584.0  446.79
  3655.5  445.34  3727.0  445.89  3756.9  447.39  3767.9  446.11  3807.0  449.94
  3819.0  449.77  3849.6  446.54  3962.4  446.17  4258.2  447.32  4472.7  446.72
  4615.7  444.07  4666.7  442.31  5009.5  439.30  5009.8  438.80  5013.5  439.30
  5046.7  440.41  5054.0  441.64  5060.8  441.33  5068.2  442.92  5124.9  443.90
  5166.9  440.39  5427.2  443.11  5598.1  442.70  5741.0  446.01  5978.8  446.93
#Mann=3,-1,0
  3355.8    0.05       0  5009.5    0.03       0  5013.5    0.05       0
Bank Sta=5009.5,5013.5
Exp/Cntr=0.3,0.1

Type RM Length L Ch R = 1,2201,39,39,39
BEGIN DESCRIPTION:
Mapping XS 6b19985d
END DESCRIPTION:
XS GIS Cut Line= 6
      2661052.16      6910695.68      2660279.64      6910843.24
      2660260.54      6910891.85      2660290.05      6910938.72
      2660257.07      6911154.00      2660159.86      6911348.42
#Sta/Elev= 30
  4192.1  446.71  4239.1  445.80  4442.7  444.41  4585.2  440.97  4788.9  439.58
  4921.2  439.70  4943.3  438.60  4972.1  439.65  4994.7  438.31  4995.0  437.81
  4998.5  437.81  4998.7  438.31  5040.7  438.58  5051.5  439.19  5057.9  440.43
  5064.4  438.55  5071.8  440.28  5078.6  439.06  5085.3  440.28  5090.8  440.28
  5109.7  443.54  5119.8  443.63  5146.0  440.41  5170.4  440.12  5200.7  440.69
  5241.2  440.15  5271.5  440.83  5282.8  440.29  5491.6  442.29  5522.3  443.17
#Mann=3,-1,0
  4192.1    0.05       0  4994.7    0.03       0  4998.7    0.05       0
Bank Sta=4994.7,4998.7
Exp/Cntr=0.3,0.1

Type RM Length L Ch R = 1,2162,31,31,31
BEGIN DESCRIPTION:
Mapping XS 5f332942
END DESCRIPTION:
XS GIS Cut Line= 6
      2661067.86      6910673.09      2660262.28      6910817.20
      2660233.63      6910848.16      2660217.14      6910867.54
      2660265.75      6910969.97      2660147.70      6911334.55
#Sta/Elev= 30
  4160.1  446.38  4176.9  446.74  4426.1  444.56  4558.2  441.32  4627.6  440.42
  4799.1  439.46  4911.8  439.77  4932.1  438.98  4932.3  438.48  4936.1  438.98
  4944.2  440.19  4970.6  441.18  4975.1  442.29  4999.6  442.12  5042.1  443.67
  5055.2  443.09  5072.2  443.69  5119.4  443.42  5123.1  442.53  5128.6  443.71
  5138.6  443.61  5146.1  442.69  5151.6  443.74  5162.7  443.20  5170.4  442.32
  5175.6  440.80  5181.6  440.41  5213.1  439.89  5507.4  442.18  5542.7  443.08
#Mann=3,-1,0
  4160.1    0.05       0  4932.1    0.03       0  4936.1    0.05       0
Bank Sta=4932.1,4936.1
Exp/Cntr=0.3,0.1

Type RM Length L Ch R = 1,2131,403,403,403
BEGIN DESCRIPTION:
Mapping XS aff10a6a
END DESCRIPTION:
XS GIS Cut Line= 6
      2661057.44      6910667.89      2660259.24      6910793.90
      2660234.50      6910806.78      2660159.85      6910884.91
      2660224.08      6910989.07      2660142.48      6911292.91
#Sta/Elev= 30
  4164.3  446.53  4226.5  445.77  4276.3  445.94  4343.7  444.75  4411.2  444.78
  4429.0  443.74  4631.5  440.37  4672.0  440.60  4773.2  439.38  4894.7  439.73
  4963.5  438.83  4963.8  438.33  4967.3  438.33  4967.5  438.83  4979.3  439.44
  5037.2  439.53  5062.6  440.16  5073.1  439.82  5088.1  440.43  5126.6  440.15
  5132.4  439.67  5163.2  439.72  5169.1  440.24  5175.3  439.79  5211.7  439.69
  5241.3  440.44  5286.5  440.69  5356.1  440.43  5476.1  442.23  5546.4  442.21
#Mann=3,-1,0
  4164.3    0.05       0  4963.5    0.03       0  4967.5    0.05       0
Bank Sta=4963.5,4967.5
Exp/Cntr=0.3,0.1

Type RM Length L Ch R = 1,1728,939,939,939
BEGIN DESCRIPTION:
Mapping XS 6a05bed4
END DESCRIPTION:
XS GIS Cut Line= 5
      2662232.40      6910667.68      2660349.40      6910397.45
      2660130.64      6910513.26      2659954.77      6910590.47
      2660267.91      6911890.19
#Sta/Elev= 30
  2844.0  447.19  3355.6  444.56  3638.5  444.62  3709.2  445.23  3749.6  448.03
  3772.9  447.97  3800.1  445.61  3830.4  446.74  4120.6  445.47  4191.2  447.63
  4196.2  446.45  4266.8  446.79  4337.3  442.66  4473.4  439.94  4795.4  438.19
  4974.5  439.36  5093.9  438.03  5094.2  437.53  5097.9  438.03  5119.0  439.68
  5124.7  442.13  5148.1  443.60  5182.5  440.67  5402.4  440.68  5678.6  442.74
  5898.5  442.38  6113.2  444.03  6143.0  445.34  6225.3  444.78  6522.8  447.09
#Mann=3,-1,0
  2844.0    0.05       0  5093.9    0.03       0  5097.9    0.05       0
Bank Sta=5093.9,5097.9
Exp/Cntr=0.3,0.1

Type RM Length L Ch R = 1,789,0,0,0
BEGIN DESCRIPTION:
Big Cottonwood Creek Trib 2_1 1.0
END DESCRIPTION:
XS GIS Cut Line= 4
      2662310.53      6910646.79      2660182.11      6909642.51
      2659688.83      6910045.72      2660221.29      6911861.08
#Sta/Elev= 30
  2487.0  447.30  2812.0  446.07  2967.5  443.62  3033.8  444.89  3067.0  443.32
  3119.2  445.94  3147.5  443.68  3164.7  444.13  3170.2  446.08  3210.3  442.60
  3442.9  443.15  3575.6  446.35  4057.8  445.43  4131.6  444.40  4148.9  442.39
  4251.0  443.77  4342.1  441.07  4840.5  437.97  4891.5  435.21  4891.7  434.71
  4895.5  435.21  4928.6  435.72  4936.5  437.87  4978.2  435.90  5220.8  437.42
  5576.9  436.12  5993.7  441.01  6671.1  444.23  6839.2  443.49  7369.4  446.97
#Mann=3,-1,0
  2487.0    0.05       0  4891.5    0.03       0  4895.5    0.05       0
Bank Sta=4891.5,4895.5
Exp/Cntr=0.3,0.1

Chan Stop Cuts=-1