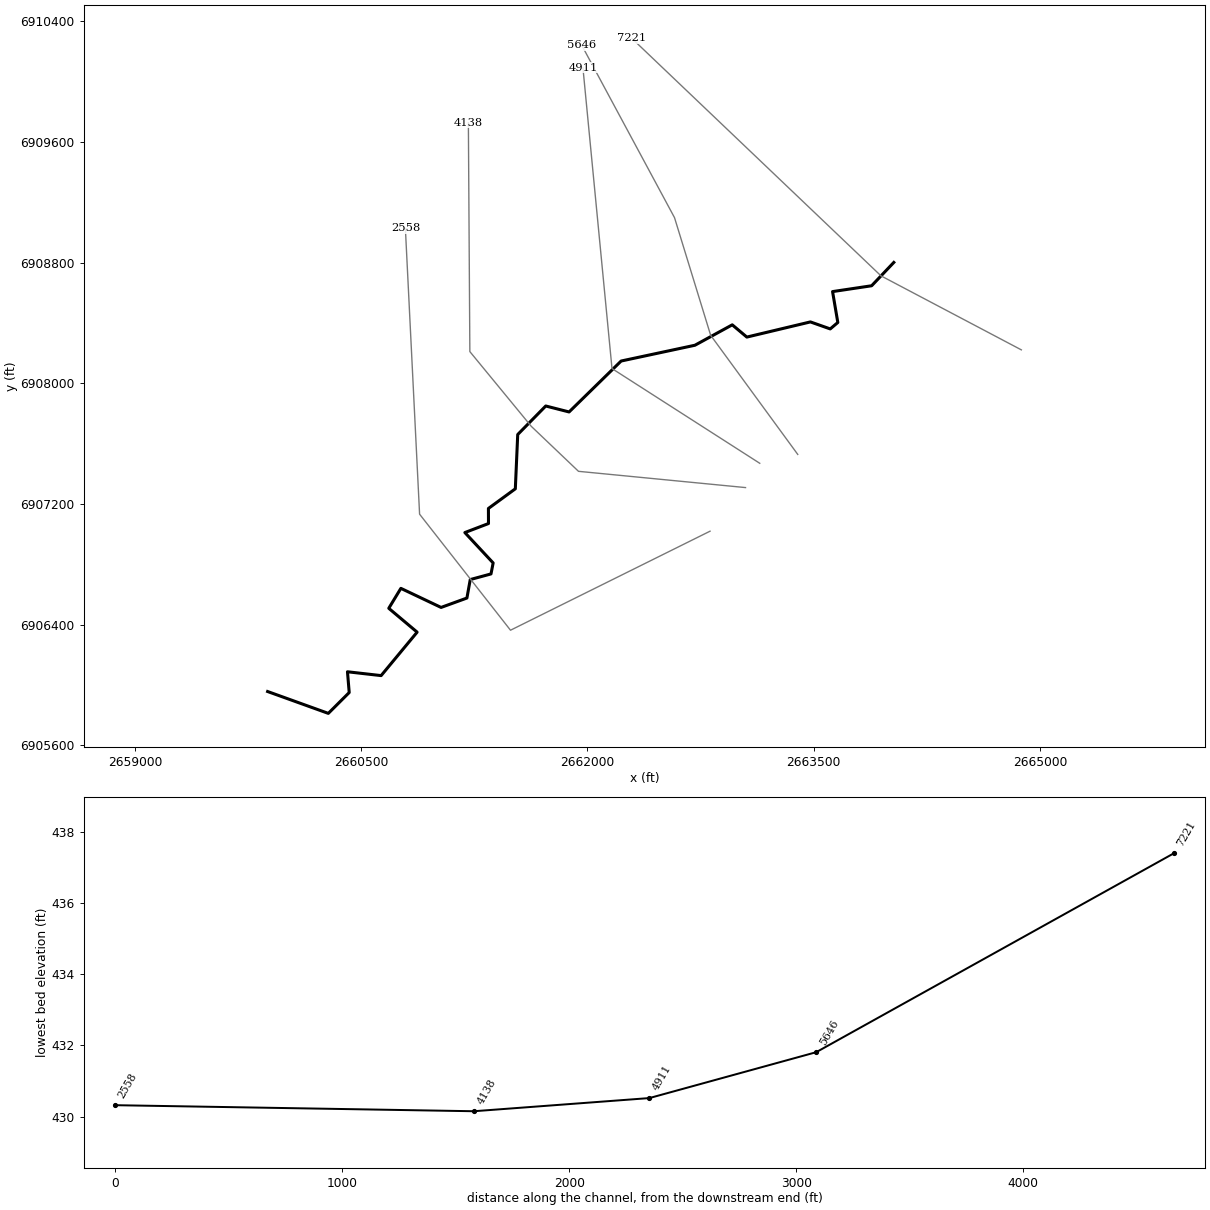
--- Big Cottonwood Creek Trib 2_2.prj (project) ---

Proj Title=Big Cottonwood Creek Trib 2_2 Base Level Engineering
Current Plan=p01
Default Exp/Contr=0.3,0.1
English Units
Geom File=g01
Flow File=f01
Plan File=p01
BEGIN DESCRIPTION:
Big Cottonwood Creek Trib 2_2
END DESCRIPTION:

--- Big Cottonwood Creek Trib 2_2.p01 (plan) ---

Plan Title=Multiple Run
Short Identifier=Multiple
Geom File=g01
Flow File=f01
Subcritical Flow
K Sum by GR= 0
Std Step Tol= 0.01
Critical Tol= 0.01
Num of Std Step Trials= 20
Max Error Tol= 0.3
Flow Tol Ratio= 0.001
Split Flow NTrial= 30
Split Flow Tol= 0.02
Split Flow Ratio= 0.02
Log Output Level= 0
Friction Slope Method= 1
Unsteady Friction Slope Method= 2
Unsteady Bridges Friction Slope Method= 1
Parabolic Critical Depth
Global Vel Dist=  1 , 1 , 1
Global Log Level= 0
CheckData=True
Encroach Param= -1, 0, 0, 0
BEGIN DESCRIPTION:
Multiple Run
END DESCRIPTION:

--- Big Cottonwood Creek Trib 2_2.f01 (steady flow) ---

Flow Title=Multiple
Number of Profiles=7
Profile Names=10-year,25-year,50-year,1pct_min,100-year,1pct_plu,500-year
River Rch & RM= Big Cottonwood C,Reach-1,7221
     453     594     705     414     827    1650    1138
Boundary for River Rch & Prof#=Big Cottonwood C,Reach-1,1
Up Type=0
Dn Type=3
Dn Slope=0.005
Boundary for River Rch & Prof#=Big Cottonwood C,Reach-1,2
Up Type=0
Dn Type=3
Dn Slope=0.005
Boundary for River Rch & Prof#=Big Cottonwood C,Reach-1,3
Up Type=0
Dn Type=3
Dn Slope=0.005
Boundary for River Rch & Prof#=Big Cottonwood C,Reach-1,4
Up Type=0
Dn Type=3
Dn Slope=0.005
Boundary for River Rch & Prof#=Big Cottonwood C,Reach-1,5
Up Type=0
Dn Type=3
Dn Slope=0.005
Boundary for River Rch & Prof#=Big Cottonwood C,Reach-1,6
Up Type=0
Dn Type=3
Dn Slope=0.005
Boundary for River Rch & Prof#=Big Cottonwood C,Reach-1,7
Up Type=0
Dn Type=3
Dn Slope=0.005

--- Big Cottonwood Creek Trib 2_2.g01 (geometry) ---

Geom Title=Existing Conditions

River Reach=Big Cottonwood C,Reach-1
Reach XY= 30
      2664030.69      6908801.41      2663883.78      6908646.77
      2663624.76      6908608.11      2663659.55      6908403.21
      2663609.29      6908360.68      2663477.85      6908407.08
      2663056.45      6908306.56      2662959.80      6908387.75
      2662712.37      6908252.43      2662223.20      6908147.84
      2661878.24      6907810.26      2661723.53      6907849.77
      2661537.75      6907660.71      2661521.86      6907300.80
      2661343.51      6907170.49      2661343.96      6907070.54
      2661187.34      6907010.75      2661374.81      6906809.40
      2661360.65      6906736.57      2661223.07      6906699.27
      2661200.92      6906576.76      2661029.77      6906514.47
      2660763.16      6906640.95      2660682.96      6906508.77
      2660870.96      6906350.63      2660632.32      6906062.59
      2660409.24      6906088.00      2660420.72      6905950.40
      2660282.17      6905812.22      2659879.87      6905957.13

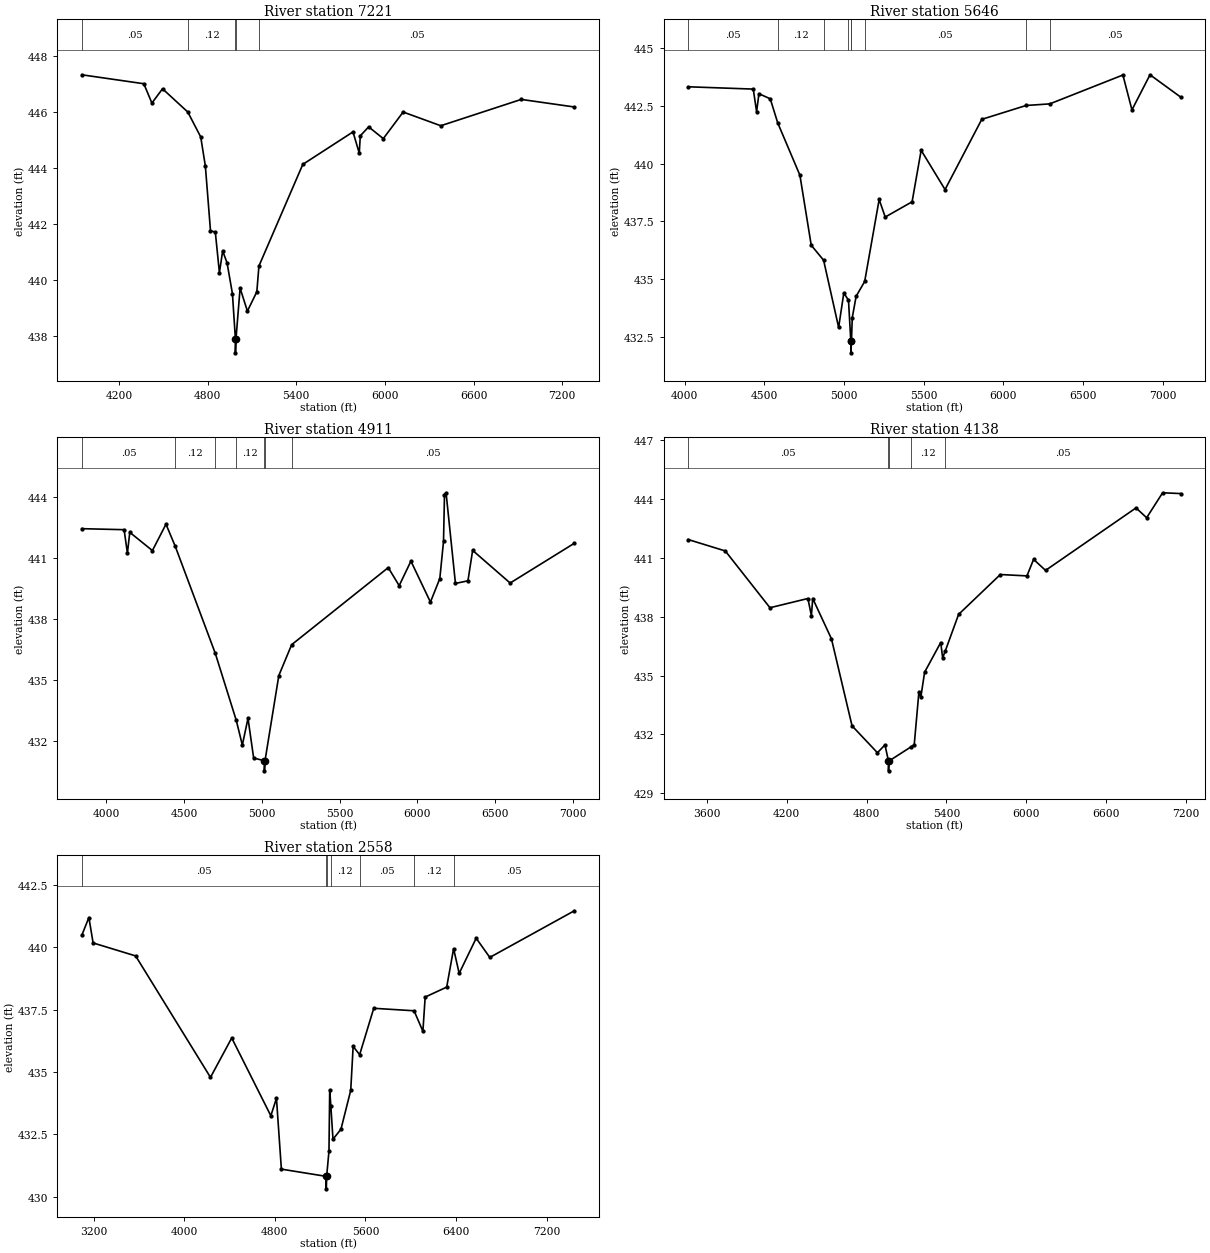
Type RM Length L Ch R = 1,7221,1575,1575,1575
BEGIN DESCRIPTION:
Big Cottonwood Creek Trib 2_2 3.0
END DESCRIPTION:
XS GIS Cut Line= 3
      2664876.08      6908221.80      2663945.64      6908712.50
      2662293.96      6910286.84
#Sta/Elev= 30
  3948.1  447.33  4368.3  447.01  4423.0  446.32  4494.8  446.83  4665.8  446.00
  4753.4  445.11  4784.8  444.07  4819.5  441.76  4852.2  441.71  4879.9  440.26
  4901.9  441.04  4931.8  440.61  4968.0  439.51  4988.0  437.90  4988.3  437.40
  4992.0  437.90  5019.9  439.71  5069.3  438.89  5133.1  439.58  5147.3  440.50
  5444.2  444.13  5783.9  445.29  5826.4  444.53  5833.3  445.15  5889.9  445.47
  5989.0  445.05  6123.3  446.00  6378.0  445.51  6922.5  446.45  7281.8  446.18
#Mann=5,-1,0
  3948.1    0.05       0  4665.8    0.12       0  4988.0    0.07       0
  4992.0    0.12       0  5147.3    0.05       0
Bank Sta=4988,4992
Exp/Cntr=0.3,0.1

Type RM Length L Ch R = 1,5646,735,735,735
BEGIN DESCRIPTION:
Mapping XS beeb4de7
END DESCRIPTION:
XS GIS Cut Line= 4
      2663393.90      6907528.86      2662816.75      6908318.16
      2662577.07      6909098.26      2661962.15      6910240.91
#Sta/Elev= 30
  4022.2  443.33  4430.6  443.23  4451.5  442.25  4466.1  443.03  4537.2  442.81
  4583.9  441.77  4723.3  439.50  4794.3  436.47  4872.0  435.82  4966.4  432.91
  4998.7  434.40  5028.2  434.09  5042.8  432.31  5043.1  431.81  5046.8  432.31
  5051.8  433.33  5076.2  434.26  5129.8  434.90  5220.7  438.45  5258.6  437.69
  5427.4  438.35  5484.2  440.58  5634.2  438.88  5864.6  441.92  6142.6  442.52
  6291.6  442.59  6750.4  443.84  6807.2  442.33  6920.6  443.85  7113.7  442.88
#Mann=9,-1,0
  4022.2    0.05       0  4583.9    0.12       0  4872.0    0.05       0
  5028.2    0.12       0  5042.8    0.03       0  5046.8    0.12       0
  5129.8    0.05       0  6142.6    0.12       0  6291.6    0.05       0
Bank Sta=5042.8,5046.8
Exp/Cntr=0.3,0.1

Type RM Length L Ch R = 1,4911,773,773,773
BEGIN DESCRIPTION:
Big Cottonwood Creek Trib 2_2 2.0
END DESCRIPTION:
XS GIS Cut Line= 3
      2663141.98      6907470.02      2662162.68      6908097.87
      2661969.98      6910091.60
#Sta/Elev= 30
  3842.3  442.46  4114.7  442.41  4135.9  441.25  4151.1  442.28  4296.5  441.38
  4383.9  442.68  4442.9  441.60  4700.9  436.31  4835.6  433.01  4874.7  431.79
  4911.0  433.11  4947.4  431.15  5016.4  431.02  5016.6  430.52  5020.4  431.02
  5109.2  435.22  5191.7  436.74  5812.5  440.54  5882.8  439.65  5958.3  440.86
  6083.7  438.84  6144.0  440.00  6167.8  441.83  6174.1  444.14  6184.2  444.23
  6244.5  439.76  6324.8  439.89  6355.0  441.39  6596.1  439.78  7008.6  441.74
#Mann=7,-1,0
  3842.3    0.05       0  4442.9    0.12       0  4700.9    0.05       0
  4835.6    0.12       0  5016.4    0.07       0  5020.4    0.12       0
  5191.7    0.05       0
Bank Sta=5016.4,5020.4
Exp/Cntr=0.3,0.1

Type RM Length L Ch R = 1,4138,1580,1580,1580
BEGIN DESCRIPTION:
Mapping XS dc4febd0
END DESCRIPTION:
XS GIS Cut Line= 5
      2663047.80      6907308.92      2661940.58      6907416.70
      2661627.04      6907715.54      2661220.42      6908210.34
      2661210.63      6909727.57
#Sta/Elev= 30
  3459.4  441.92  3738.2  441.34  4074.1  438.45  4359.3  438.92  4385.6  438.05
  4395.6  438.92  4536.3  436.87  4691.2  432.44  4882.1  431.07  4938.7  431.47
  4965.0  430.65  4965.3  430.15  4969.0  430.65  5132.1  431.36  5158.6  431.47
  5193.8  434.16  5208.1  433.89  5236.8  435.17  5358.0  436.68  5372.4  435.90
  5391.6  436.24  5492.2  438.11  5806.1  440.14  6006.1  440.07  6056.1  440.91
  6146.1  440.35  6826.1  443.53  6906.1  443.03  7026.1  444.30  7162.7  444.26
#Mann=5,-1,0
  3459.4    0.05       0  4965.0    0.03       0  4969.0    0.05       0
  5132.1    0.12       0  5391.6    0.05       0
Bank Sta=4965,4969
Exp/Cntr=0.3,0.1

Type RM Length L Ch R = 1,2558,0,0,0
BEGIN DESCRIPTION:
Big Cottonwood Creek Trib 2_2 1.0
END DESCRIPTION:
XS GIS Cut Line= 4
      2662812.63      6907019.89      2661489.87      6906363.40
      2660887.29      6907132.55      2660793.05      6909026.62
#Sta/Elev= 30
  3094.7  440.48  3157.9  441.20  3195.2  440.18  3570.6  439.66  4231.7  434.79
  4419.4  436.37  4764.7  433.25  4814.4  433.95  4857.8  431.11  5253.7  430.82
  5253.9  430.32  5257.7  430.82  5278.2  431.84  5284.6  434.28  5294.9  433.63
  5313.5  432.31  5384.0  432.71  5470.3  434.27  5491.6  436.03  5549.1  435.70
  5673.6  437.56  6029.7  437.46  6107.6  436.64  6127.7  438.01  6317.9  438.41
  6378.7  439.95  6428.0  438.96  6578.2  440.37  6698.4  439.60  7444.9  441.47
#Mann=7,-1,0
  3094.7    0.05       0  5253.7    0.03       0  5257.7    0.05       0
  5294.9    0.12       0  5549.1    0.05       0  6029.7    0.12       0
  6378.7    0.05       0
Bank Sta=5253.7,5257.7
Exp/Cntr=0.3,0.1

Chan Stop Cuts=-1