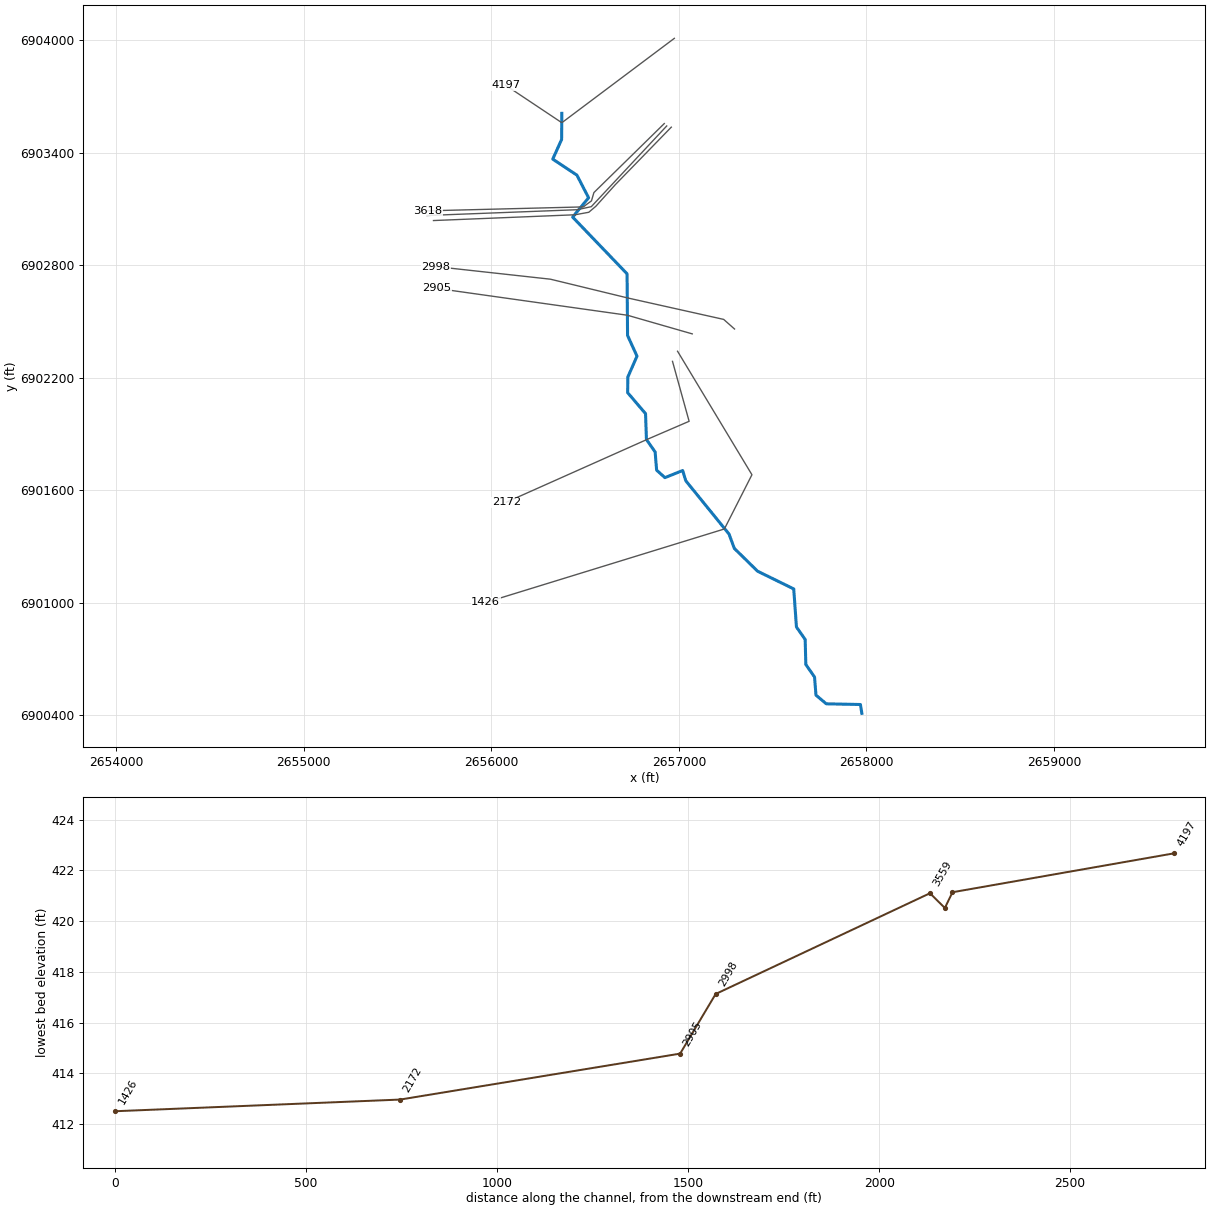
--- Big Cottonwood Creek Trib 3.prj (project) ---

Proj Title=Big Cottonwood Creek Trib 3 Base Level Engineering
Current Plan=p01
Default Exp/Contr=0.3,0.1
English Units
Geom File=g01
Flow File=f01
Plan File=p01
BEGIN DESCRIPTION:
Big Cottonwood Creek Trib 3
END DESCRIPTION:

--- Big Cottonwood Creek Trib 3.p01 (plan) ---

Plan Title=Multiple Run
Short Identifier=Multiple
Geom File=g01
Flow File=f01
Subcritical Flow
K Sum by GR= 0
Std Step Tol= 0.01
Critical Tol= 0.01
Num of Std Step Trials= 20
Max Error Tol= 0.3
Flow Tol Ratio= 0.001
Split Flow NTrial= 30
Split Flow Tol= 0.02
Split Flow Ratio= 0.02
Log Output Level= 0
Friction Slope Method= 1
Unsteady Friction Slope Method= 2
Unsteady Bridges Friction Slope Method= 1
Parabolic Critical Depth
Global Vel Dist=  1 , 1 , 1
Global Log Level= 0
CheckData=True
Encroach Param= -1, 0, 0, 0
BEGIN DESCRIPTION:
Multiple Run
END DESCRIPTION:

--- Big Cottonwood Creek Trib 3.f01 (steady flow) ---

Flow Title=Multiple
Number of Profiles=7
Profile Names=10-year,25-year,50-year,1pct_min,100-year,1pct_plu,500-year
River Rch & RM= Big Cottonwood C,Reach-1,4197
     515     684     819     486     970    1935    1360
Boundary for River Rch & Prof#=Big Cottonwood C,Reach-1,1
Up Type=0
Dn Type=3
Dn Slope=0.005
Boundary for River Rch & Prof#=Big Cottonwood C,Reach-1,2
Up Type=0
Dn Type=3
Dn Slope=0.005
Boundary for River Rch & Prof#=Big Cottonwood C,Reach-1,3
Up Type=0
Dn Type=3
Dn Slope=0.005
Boundary for River Rch & Prof#=Big Cottonwood C,Reach-1,4
Up Type=0
Dn Type=3
Dn Slope=0.005
Boundary for River Rch & Prof#=Big Cottonwood C,Reach-1,5
Up Type=0
Dn Type=3
Dn Slope=0.005
Boundary for River Rch & Prof#=Big Cottonwood C,Reach-1,6
Up Type=0
Dn Type=3
Dn Slope=0.005
Boundary for River Rch & Prof#=Big Cottonwood C,Reach-1,7
Up Type=0
Dn Type=3
Dn Slope=0.005

--- Big Cottonwood Creek Trib 3.g01 (geometry) ---

Geom Title=Existing Conditions

River Reach=Big Cottonwood C,Reach-1
Reach XY= 30
      2656376.00      6903611.00      2656374.81      6903471.47
      2656327.54      6903366.85      2656456.38      6903281.47
      2656518.69      6903160.91      2656433.61      6903057.67
      2656723.94      6902755.15      2656726.52      6902426.22
      2656776.81      6902316.03      2656728.17      6902205.02
      2656726.94      6902121.48      2656822.44      6902009.53
      2656827.23      6901871.51      2656873.64      6901805.02
      2656881.52      6901708.02      2656925.70      6901668.26
      2657020.38      6901706.19      2657036.89      6901651.67
      2657267.82      6901367.04      2657295.79      6901290.91
      2657419.94      6901169.14      2657612.78      6901074.67
      2657627.22      6900871.51      2657673.73      6900805.06
      2657677.23      6900671.51      2657723.64      6900605.02
      2657731.40      6900508.29      2657786.27      6900461.98
      2657968.30      6900458.30      2657976.00      6900411.00

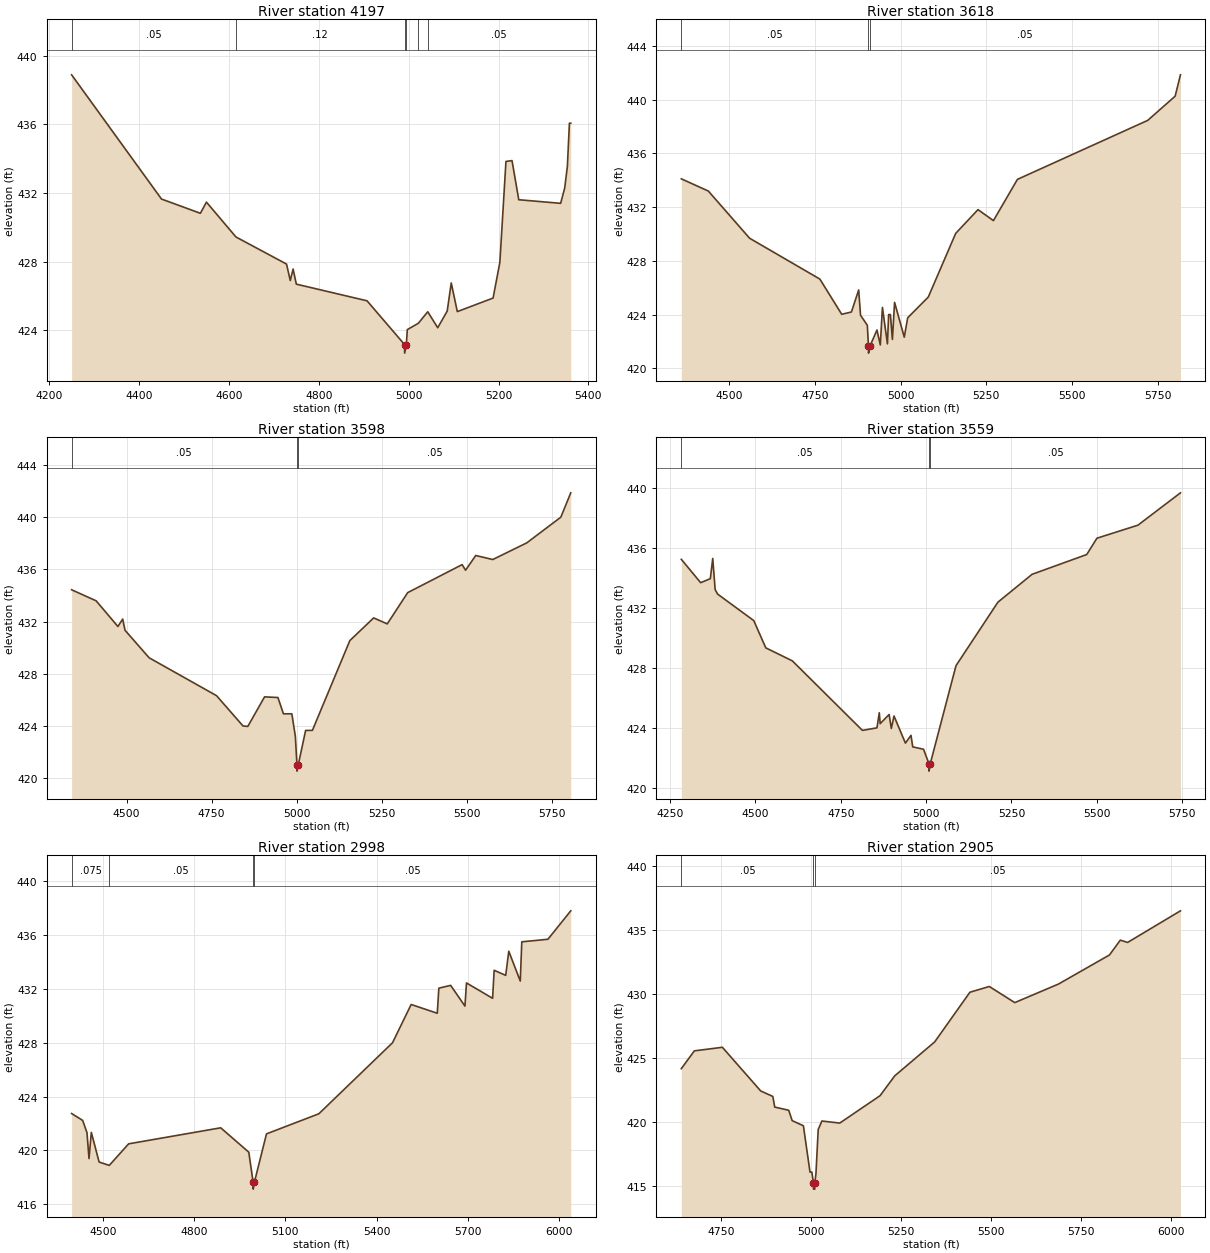
Type RM Length L Ch R = 1,4197,579,579,579
BEGIN DESCRIPTION:
Big Cottonwood Creek Trib 3 3.0
END DESCRIPTION:
XS GIS Cut Line= 3
      2656976.03      6904011.03      2656376.00      6903561.00
      2656076.00      6903761.00
#Sta/Elev= 30
  4250.1  438.89  4450.1  431.65  4536.6  430.82  4550.1  431.47  4615.7  429.44
  4728.3  427.86  4736.6  426.90  4742.9  427.57  4750.1  426.69  4907.4  425.72
  4990.9  423.17  4991.1  422.67  4994.9  423.17  4997.0  424.04  5021.6  424.41
  5042.5  425.08  5064.7  424.15  5085.8  425.12  5094.8  426.76  5108.3  425.09
  5187.9  425.88  5203.0  427.97  5216.5  433.84  5230.0  433.89  5245.0  431.61
  5338.2  431.40  5347.2  432.29  5353.2  433.56  5357.7  436.07  5360.7  436.07
#Mann=6,-1,0
  4250.1    0.05       0  4615.7    0.12       0  4990.9    0.03       0
  4994.9    0.12       0  5021.6    0.12       0  5042.5    0.05       0
Bank Sta=4990.9,4994.9
Exp/Cntr=0.3,0.1

Type RM Length L Ch R = 1,3618,20,20,20
BEGIN DESCRIPTION:
Mapping XS 788e571b
END DESCRIPTION:
XS GIS Cut Line= 6
      2656922.25      6903556.40      2656547.03      6903188.43
      2656534.00      6903144.16      2656505.36      6903123.32
      2656491.04      6903112.04      2655660.54      6903091.16
#Sta/Elev= 30
  4360.3  434.11  4439.2  433.20  4559.5  429.69  4764.5  426.65  4828.2  424.03
  4856.5  424.20  4877.7  425.84  4883.1  423.96  4903.0  423.21  4906.2  421.64
  4906.5  421.14  4910.2  421.64  4931.0  422.86  4940.8  421.75  4947.0  424.54
  4961.6  421.83  4965.1  424.01  4970.2  424.01  4976.1  422.16  4982.4  424.92
  5010.7  422.33  5020.7  423.77  5080.7  425.31  5160.7  430.05  5225.8  431.82
  5270.8  431.00  5340.8  434.07  5720.9  438.46  5800.9  440.26  5816.4  441.85
#Mann=3,-1,0
  4360.3    0.05       0  4906.2    0.04       0  4910.2    0.05       0
Bank Sta=4906.2,4910.2
Exp/Cntr=0.3,0.1

Type RM Length L Ch R = 1,3598,39,39,39
BEGIN DESCRIPTION:
Mapping XS a88dc323
END DESCRIPTION:
XS GIS Cut Line= 4
      2656935.42      6903543.78      2656533.14      6903113.34
      2656457.87      6903097.04      2655656.84      6903066.23
#Sta/Elev= 30
  4338.5  434.44  4410.7  433.59  4474.6  431.62  4488.7  432.19  4495.6  431.33
  4566.4  429.22  4764.7  426.31  4842.4  423.99  4856.6  423.95  4905.9  426.22
  4945.2  426.17  4961.4  424.92  4986.1  424.92  4996.4  423.20  5001.1  421.02
  5001.3  420.52  5005.1  421.02  5026.6  423.64  5046.6  423.65  5156.7  430.54
  5226.7  432.28  5266.7  431.82  5326.8  434.22  5486.9  436.37  5496.9  435.94
  5526.9  437.07  5577.0  436.76  5677.0  438.04  5777.1  440.01  5806.3  441.88
#Mann=3,-1,0
  4338.5    0.05       0  5001.1    0.04       0  5005.1    0.05       0
Bank Sta=5001.1,5005.1
Exp/Cntr=0.3,0.1

Type RM Length L Ch R = 1,3559,561,561,561
BEGIN DESCRIPTION:
Mapping XS de0ba725
END DESCRIPTION:
XS GIS Cut Line= 6
      2656959.77      6903537.37      2656661.17      6903230.53
      2656557.44      6903115.51      2656519.68      6903083.39
      2656446.32      6903070.08      2655691.52      6903039.27
#Sta/Elev= 30
  4282.7  435.24  4339.4  433.68  4367.7  433.95  4374.8  435.30  4381.8  433.22
  4389.0  432.92  4495.0  431.15  4530.2  429.33  4608.1  428.46  4813.4  423.82
  4856.0  423.99  4862.8  425.00  4865.4  424.27  4891.6  424.88  4898.1  423.95
  4905.9  424.78  4939.4  422.97  4955.7  423.49  4960.8  422.72  4992.5  422.56
  5008.2  421.60  5008.5  421.10  5012.2  421.60  5087.6  428.14  5210.4  432.38
  5310.5  434.24  5470.6  435.56  5500.6  436.65  5620.7  437.52  5745.3  439.68
#Mann=3,-1,0
  4282.7    0.05       0  5008.2    0.04       0  5012.2    0.05       0
Bank Sta=5008.2,5012.2
Exp/Cntr=0.3,0.1

Type RM Length L Ch R = 1,2998,93,93,93
BEGIN DESCRIPTION:
Mapping XS 46386729
END DESCRIPTION:
XS GIS Cut Line= 5
      2657297.02      6902460.89      2657239.06      6902512.10
      2656726.05      6902626.69      2656315.25      6902726.51
      2655703.40      6902793.88
#Sta/Elev= 30
  4397.0  422.74  4433.3  422.23  4447.5  421.32  4454.2  419.40  4461.8  421.34
  4487.4  419.14  4520.8  418.89  4584.5  420.49  4887.3  421.68  4979.6  419.87
  4993.9  417.63  4994.1  417.13  4997.9  417.63  5037.8  421.23  5209.9  422.72
  5452.2  427.99  5513.5  430.83  5599.4  430.18  5604.5  432.04  5643.3  432.25
  5690.4  430.71  5695.4  432.43  5781.3  431.29  5786.4  433.37  5824.4  432.99
  5834.5  434.78  5872.3  432.57  5877.3  435.48  5963.2  435.67  6038.3  437.78
#Mann=4,-1,0
  4397.0   0.075       0  4520.8    0.05       0  4993.9    0.03       0
  4997.9    0.05       0
Bank Sta=4993.9,4997.9
Exp/Cntr=0.3,0.1

Type RM Length L Ch R = 1,2905,733,733,733
BEGIN DESCRIPTION:
Mapping XS 73056f1e
END DESCRIPTION:
XS GIS Cut Line= 3
      2657071.55      6902434.84      2656725.96      6902534.24
      2655710.88      6902677.24
#Sta/Elev= 30
  4640.4  424.19  4676.5  425.58  4754.3  425.86  4860.6  422.45  4894.3  422.02
  4899.5  421.19  4938.4  420.94  4947.9  420.13  4979.1  419.73  4997.4  416.11
  5002.5  416.11  5006.8  415.28  5007.1  414.78  5010.6  414.78  5010.8  415.28
  5013.9  415.99  5020.2  419.44  5030.3  420.10  5080.0  419.94  5191.8  422.08
  5232.5  423.63  5343.3  426.28  5441.0  430.16  5494.8  430.61  5565.5  429.35
  5686.7  430.80  5828.1  433.07  5858.3  434.23  5878.5  434.05  6025.1  436.52
#Mann=3,-1,0
  4640.4    0.05       0  5006.8    0.03       0  5010.8    0.05       0
Bank Sta=5006.8,5010.8
Exp/Cntr=0.3,0.1

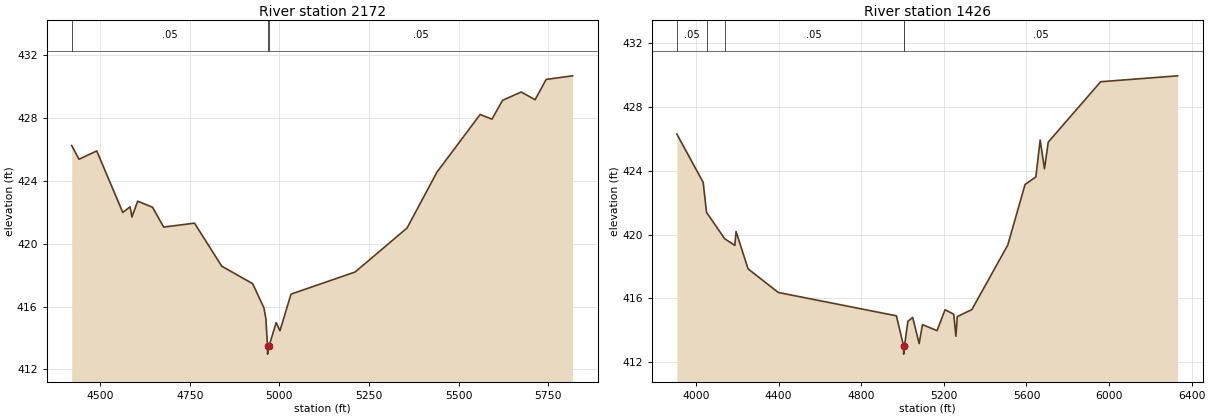
Type RM Length L Ch R = 1,2172,746,746,746
BEGIN DESCRIPTION:
Mapping XS 291d7e25
END DESCRIPTION:
XS GIS Cut Line= 4
      2656966.23      6902288.28      2657054.81      6901968.64
      2656831.44      6901872.36      2656080.69      6901537.41
#Sta/Elev= 30
  4420.7  426.25  4441.2  425.38  4490.5  425.91  4563.2  421.99  4583.5  422.35
  4588.7  421.70  4604.7  422.71  4646.2  422.32  4677.3  421.06  4763.2  421.31
  4839.2  418.57  4925.3  417.46  4956.9  415.92  4962.3  415.23  4966.9  413.47
  4967.1  412.97  4970.9  413.47  4991.0  414.98  5001.6  414.46  5032.4  416.79
  5211.3  418.20  5356.1  421.00  5439.6  424.56  5560.0  428.23  5592.9  427.93
  5622.5  429.13  5674.5  429.66  5713.3  429.17  5744.1  430.46  5817.7  430.69
#Mann=3,-1,0
  4420.7    0.05       0  4966.9    0.03       0  4970.9    0.05       0
Bank Sta=4966.9,4970.9
Exp/Cntr=0.3,0.1

Type RM Length L Ch R = 1,1426,0,0,0
BEGIN DESCRIPTION:
Big Cottonwood Creek Trib 3 1.0
END DESCRIPTION:
XS GIS Cut Line= 4
      2656993.17      6902342.23      2657389.86      6901683.65
      2657242.95      6901394.45      2655969.87      6901002.33
#Sta/Elev= 30
  3906.8  426.30  4034.5  423.27  4050.8  421.39  4138.5  419.74  4187.9  419.32
  4193.8  420.19  4252.0  417.85  4398.5  416.37  4970.2  414.91  5005.3  413.01
  5005.5  412.51  5009.3  413.01  5025.8  414.56  5049.1  414.81  5080.5  413.17
  5096.4  414.36  5167.0  413.98  5206.1  415.29  5247.9  415.01  5258.4  413.63
  5265.1  414.86  5335.7  415.30  5509.5  419.34  5593.2  423.13  5645.6  423.61
  5666.5  425.92  5687.4  424.12  5705.6  425.79  5959.5  429.57  6332.1  429.94
#Mann=5,-1,0
  3906.8    0.05       0  4050.8   0.075       0  4138.5    0.05       0
  5005.3    0.03       0  5009.3    0.05       0
Bank Sta=5005.3,5009.3
Exp/Cntr=0.3,0.1

Chan Stop Cuts=-1