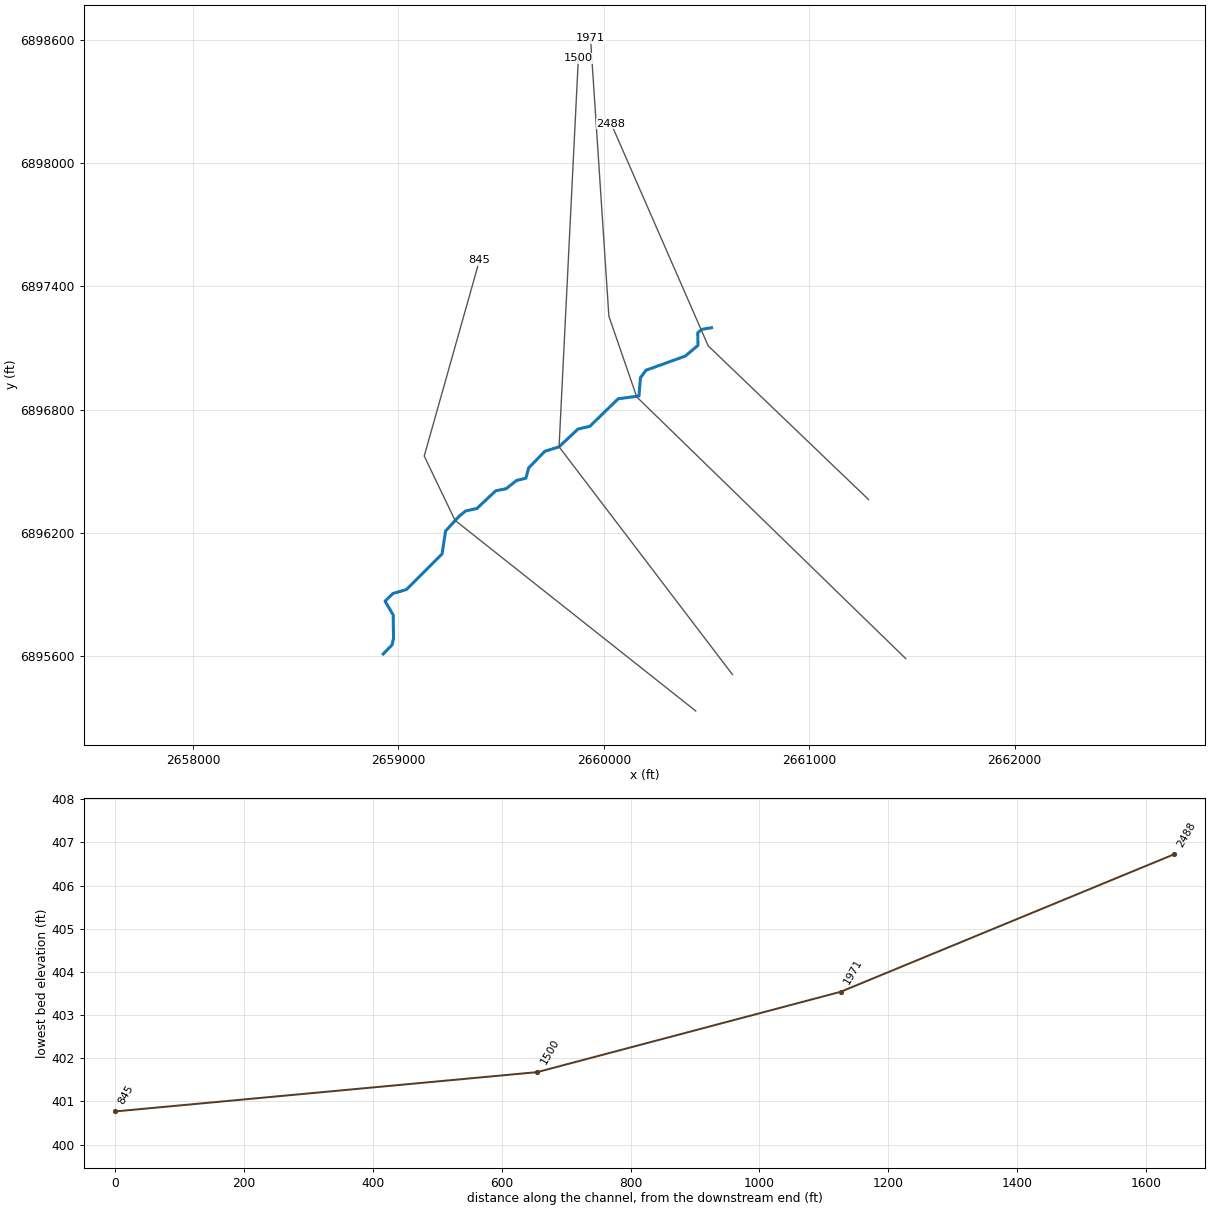
--- Big Cottonwood Creek Trib 4.prj (project) ---

Proj Title=Big Cottonwood Creek Trib 4 Base Level Engineering
Current Plan=p01
Default Exp/Contr=0.3,0.1
English Units
Geom File=g01
Flow File=f01
Plan File=p01
BEGIN DESCRIPTION:
Big Cottonwood Creek Trib 4
END DESCRIPTION:

--- Big Cottonwood Creek Trib 4.p01 (plan) ---

Plan Title=Multiple Run
Short Identifier=Multiple
Geom File=g01
Flow File=f01
Subcritical Flow
K Sum by GR= 0
Std Step Tol= 0.01
Critical Tol= 0.01
Num of Std Step Trials= 20
Max Error Tol= 0.3
Flow Tol Ratio= 0.001
Split Flow NTrial= 30
Split Flow Tol= 0.02
Split Flow Ratio= 0.02
Log Output Level= 0
Friction Slope Method= 1
Unsteady Friction Slope Method= 2
Unsteady Bridges Friction Slope Method= 1
Parabolic Critical Depth
Global Vel Dist=  1 , 1 , 1
Global Log Level= 0
CheckData=True
Encroach Param= -1, 0, 0, 0
BEGIN DESCRIPTION:
Multiple Run
END DESCRIPTION:

--- Big Cottonwood Creek Trib 4.f01 (steady flow) ---

Flow Title=Multiple
Number of Profiles=7
Profile Names=10-year,25-year,50-year,1pct_min,100-year,1pct_plu,500-year
River Rch & RM= Big Cottonwood C,Reach-1,2488
     502     666     796     472     942    1880    1320
Boundary for River Rch & Prof#=Big Cottonwood C,Reach-1,1
Up Type=0
Dn Type=3
Dn Slope=0.005
Boundary for River Rch & Prof#=Big Cottonwood C,Reach-1,2
Up Type=0
Dn Type=3
Dn Slope=0.005
Boundary for River Rch & Prof#=Big Cottonwood C,Reach-1,3
Up Type=0
Dn Type=3
Dn Slope=0.005
Boundary for River Rch & Prof#=Big Cottonwood C,Reach-1,4
Up Type=0
Dn Type=3
Dn Slope=0.005
Boundary for River Rch & Prof#=Big Cottonwood C,Reach-1,5
Up Type=0
Dn Type=3
Dn Slope=0.005
Boundary for River Rch & Prof#=Big Cottonwood C,Reach-1,6
Up Type=0
Dn Type=3
Dn Slope=0.005
Boundary for River Rch & Prof#=Big Cottonwood C,Reach-1,7
Up Type=0
Dn Type=3
Dn Slope=0.005

--- Big Cottonwood Creek Trib 4.g01 (geometry) ---

Geom Title=Existing Conditions

River Reach=Big Cottonwood C,Reach-1
Reach XY= 30
      2660524.08      6897198.79      2660477.20      6897190.98
      2660457.24      6897174.49      2660458.10      6897112.86
      2660396.47      6897060.77      2660205.52      6896991.98
      2660178.19      6896955.42      2660170.89      6896866.12
      2660069.88      6896853.11      2659932.05      6896719.16
      2659873.72      6896705.13      2659782.04      6896619.18
      2659712.76      6896597.38      2659634.28      6896516.77
      2659620.39      6896466.59      2659574.15      6896454.76
      2659524.29      6896415.18      2659473.71      6896405.15
      2659382.04      6896319.18      2659327.63      6896307.03
      2659295.76      6896281.42      2659229.61      6896209.51
      2659212.60      6896097.70      2659039.18      6895924.63
      2658973.15      6895905.15      2658935.01      6895868.02
      2658974.62      6895800.57      2658976.27      6895685.91
      2658968.58      6895654.65      2658926.00      6895611.00

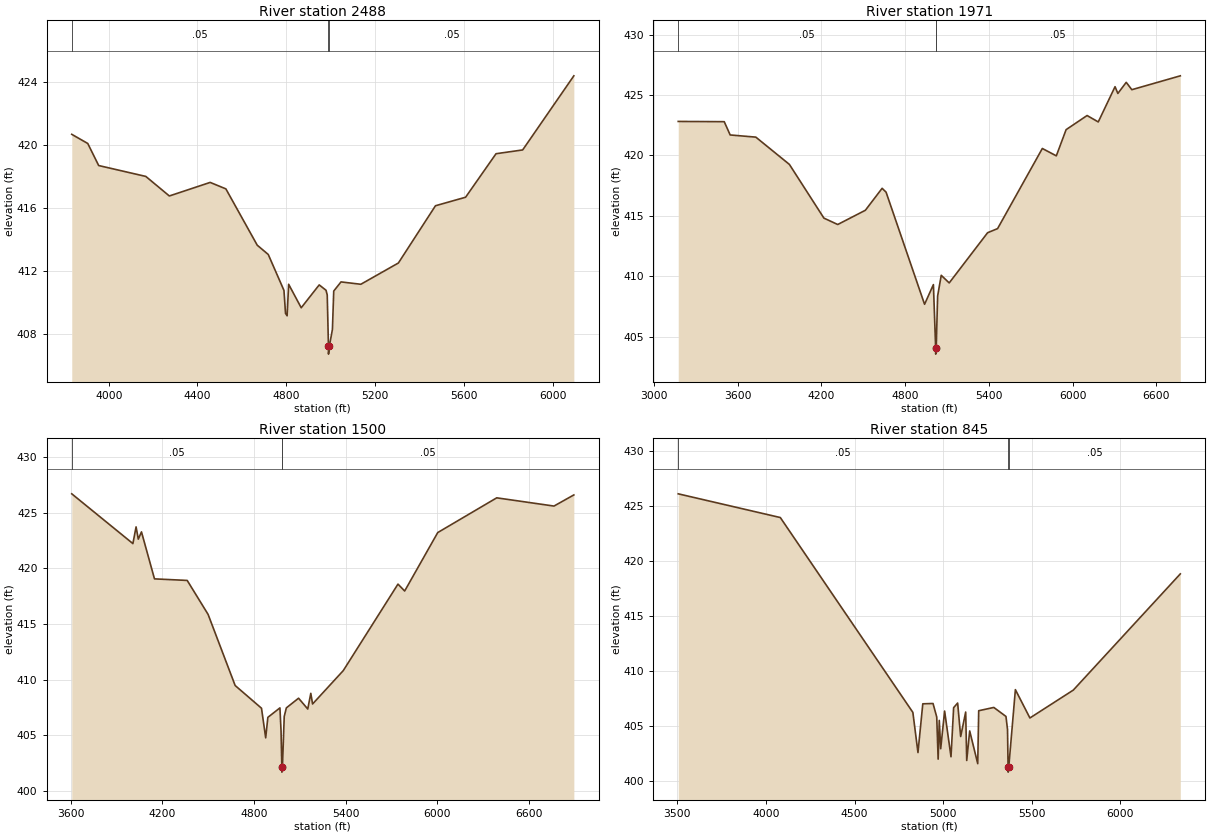
Type RM Length L Ch R = 1,2488,517,517,517
BEGIN DESCRIPTION:
Big Cottonwood Creek Trib 4 5.0
END DESCRIPTION:
XS GIS Cut Line= 3
      2661288.88      6896362.32      2660508.08      6897110.39
      2660035.40      6898192.21
#Sta/Elev= 30
  3833.6  420.66  3905.6  420.08  3954.9  418.68  4167.2  417.99  4273.2  416.75
  4457.2  417.61  4527.9  417.20  4669.1  413.63  4718.8  413.04  4789.6  410.76
  4796.5  409.31  4803.7  409.15  4810.7  411.15  4867.3  409.66  4948.3  411.11
  4979.1  410.77  4984.5  410.47  4990.0  407.22  4990.2  406.72  4994.0  407.22
  5007.9  408.29  5013.8  410.72  5046.5  411.30  5135.9  411.15  5305.1  412.50
  5472.1  416.13  5607.8  416.67  5745.0  419.43  5865.0  419.67  6095.5  424.37
#Mann=3,-1,0
  3833.6    0.05       0  4990.0    0.04       0  4994.0    0.05       0
Bank Sta=4990,4994
Exp/Cntr=0.3,0.1

Type RM Length L Ch R = 1,1971,471,471,471
BEGIN DESCRIPTION:
Big Cottonwood Creek Trib 4 4.0
END DESCRIPTION:
XS GIS Cut Line= 4
      2661469.70      6895588.38      2660160.36      6896861.70
      2660024.55      6897254.88      2659935.07      6898607.65
#Sta/Elev= 30
  3173.6  422.82  3503.3  422.80  3545.8  421.70  3729.7  421.52  3970.2  419.26
  4217.6  414.81  4316.6  414.28  4514.7  415.46  4634.8  417.28  4663.1  416.96
  4938.9  407.67  5002.3  409.30  5018.4  404.04  5018.7  403.54  5022.4  404.04
  5032.5  408.35  5058.4  410.07  5115.5  409.44  5390.7  413.60  5462.2  413.94
  5782.9  420.58  5883.1  419.97  5953.3  422.14  6103.6  423.31  6183.8  422.78
  6304.0  425.70  6324.1  425.14  6384.2  426.06  6424.3  425.45  6771.7  426.60
#Mann=3,-1,0
  3173.6    0.05       0  5018.4    0.03       0  5022.4    0.05       0
Bank Sta=5018.4,5022.4
Exp/Cntr=0.3,0.1

Type RM Length L Ch R = 1,1500,655,655,655
BEGIN DESCRIPTION:
Big Cottonwood Creek Trib 4 3.0
END DESCRIPTION:
XS GIS Cut Line= 3
      2660626.03      6895510.96      2659782.06      6896619.19
      2659876.00      6898510.96
#Sta/Elev= 30
  3607.0  426.68  4007.2  422.21  4028.0  423.71  4042.6  422.61  4063.4  423.26
  4148.6  419.04  4362.8  418.90  4499.5  415.85  4676.7  409.46  4849.2  407.42
  4876.6  404.76  4890.8  406.60  4969.8  407.45  4977.1  405.39  4982.3  402.18
  4982.6  401.68  4986.3  402.18  4998.0  406.68  5011.8  407.45  5091.9  408.32
  5152.0  407.35  5172.0  408.76  5183.6  407.80  5384.6  410.80  5742.7  418.57
  5786.5  417.95  6003.0  423.20  6389.3  426.32  6764.0  425.58  6894.1  426.58
#Mann=3,-1,0
  3607.0    0.05       0  4982.3    0.05       0  4986.3    0.05       0
Bank Sta=4982.3,4986.3
Exp/Cntr=0.3,0.1

Type RM Length L Ch R = 1,845,0,0,0
BEGIN DESCRIPTION:
Big Cottonwood Creek Trib 4 2.0
END DESCRIPTION:
XS GIS Cut Line= 4
      2660447.47      6895333.56      2659275.67      6896261.31
      2659125.70      6896574.11      2659394.72      6897527.49
#Sta/Elev= 30
  3505.4  426.11  4081.2  423.95  4828.9  406.21  4857.7  402.55  4884.9  406.99
  4942.6  407.02  4963.5  405.79  4971.5  401.95  4977.9  405.48  4985.9  402.90
  5008.0  406.33  5044.0  402.17  5058.9  406.64  5081.5  407.06  5098.6  404.01
  5126.8  406.24  5132.7  401.83  5149.5  404.52  5194.8  401.54  5200.3  406.36
  5285.4  406.66  5354.1  405.84  5362.8  404.65  5366.0  401.27  5366.3  400.77
  5370.0  401.27  5407.2  408.28  5489.1  405.70  5734.0  408.24  6337.5  418.82
#Mann=3,-1,0
  3505.4    0.05       0  5366.0    0.05       0  5370.0    0.05       0
Bank Sta=5366,5370
Exp/Cntr=0.3,0.1

Chan Stop Cuts=-1