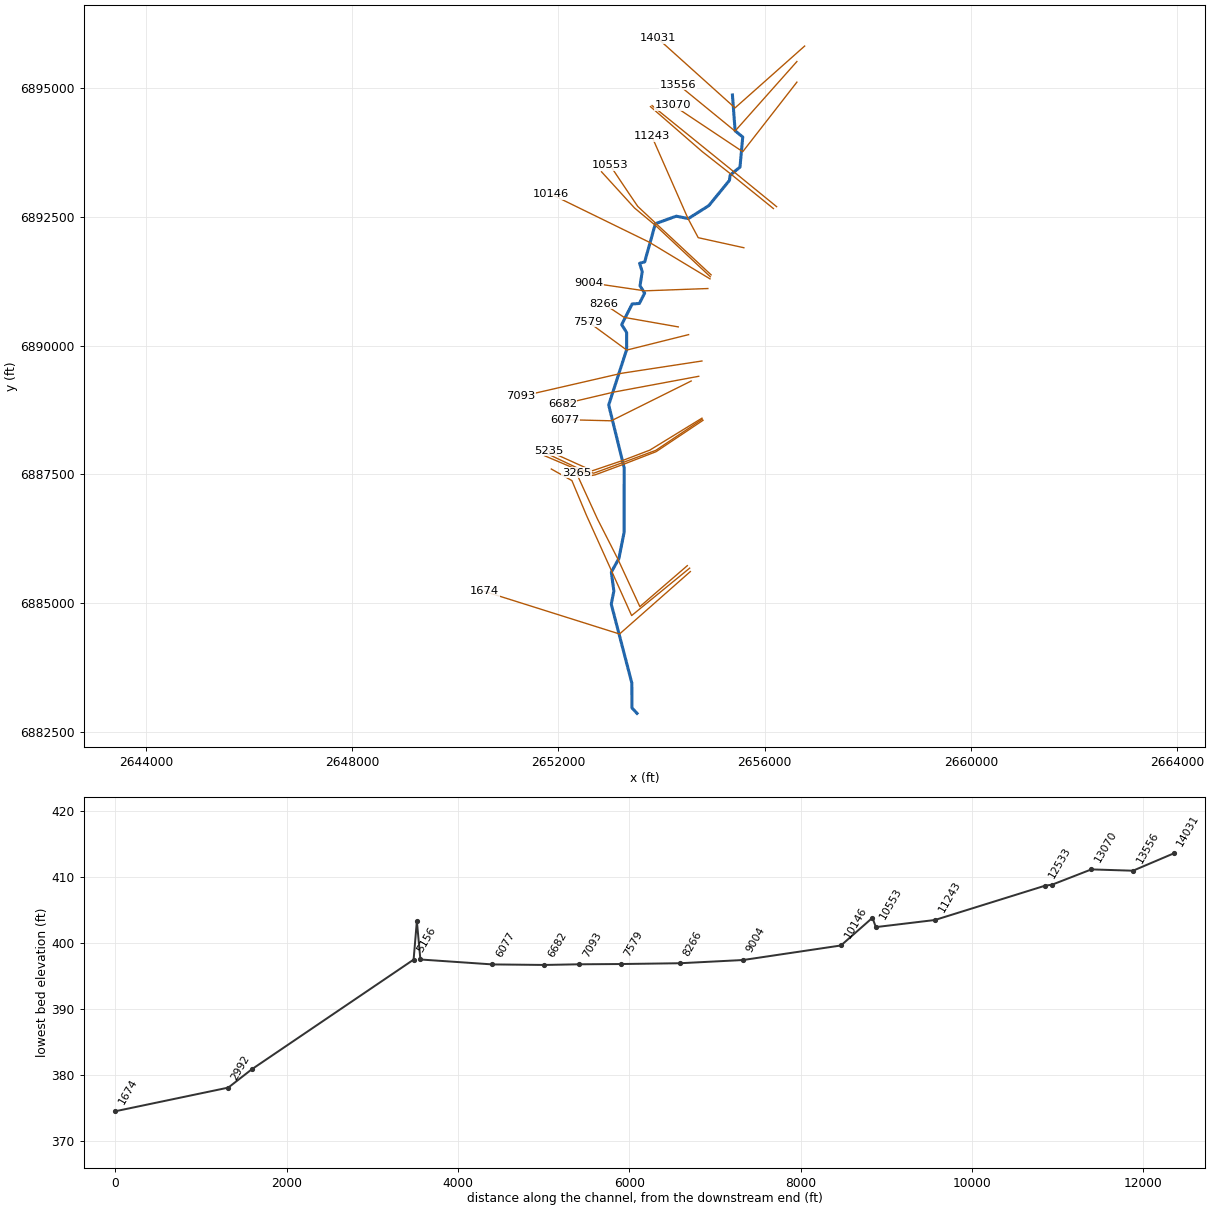
--- Big Cottonwood Creek Trib 5.prj (project) ---

Proj Title=Big Cottonwood Creek Trib 5 Base Level Engineering
Current Plan=p01
Default Exp/Contr=0.3,0.1
English Units
Geom File=g01
Flow File=f01
Plan File=p01
BEGIN DESCRIPTION:
Big Cottonwood Creek Trib 5
END DESCRIPTION:

--- Big Cottonwood Creek Trib 5.p01 (plan) ---

Plan Title=Multiple Run
Short Identifier=Multiple
Geom File=g01
Flow File=f01
Subcritical Flow
K Sum by GR= 0
Std Step Tol= 0.01
Critical Tol= 0.01
Num of Std Step Trials= 20
Max Error Tol= 0.3
Flow Tol Ratio= 0.001
Split Flow NTrial= 30
Split Flow Tol= 0.02
Split Flow Ratio= 0.02
Log Output Level= 0
Friction Slope Method= 1
Unsteady Friction Slope Method= 2
Unsteady Bridges Friction Slope Method= 1
Parabolic Critical Depth
Global Vel Dist=  1 , 1 , 1
Global Log Level= 0
CheckData=True
Encroach Param= -1, 0, 0, 0
BEGIN DESCRIPTION:
Multiple Run
END DESCRIPTION:

--- Big Cottonwood Creek Trib 5.f01 (steady flow) ---

Flow Title=Multiple
Number of Profiles=7
Profile Names=10-year,25-year,50-year,1pct_min,100-year,1pct_plu,500-year
River Rch & RM= Big Cottonwood C,Reach-1,14031
     477     629     749     442     883    1761    1226
River Rch & RM= Big Cottonwood C,Reach-1,12608
     624     836    1006     600    1197    2389    1697
River Rch & RM= Big Cottonwood C,Reach-1,10553
     741     999    1207     722    1440    2873    2051
River Rch & RM= Big Cottonwood C,Reach-1,6077
    1054    1451    1778    1077    2149    4288    3146
River Rch & RM= Big Cottonwood C,Reach-1,1674
    1200    1661    2044    1243    2479    4947    3654
Boundary for River Rch & Prof#=Big Cottonwood C,Reach-1,1
Up Type=0
Dn Type=3
Dn Slope=0.005
Boundary for River Rch & Prof#=Big Cottonwood C,Reach-1,2
Up Type=0
Dn Type=3
Dn Slope=0.005
Boundary for River Rch & Prof#=Big Cottonwood C,Reach-1,3
Up Type=0
Dn Type=3
Dn Slope=0.005
Boundary for River Rch & Prof#=Big Cottonwood C,Reach-1,4
Up Type=0
Dn Type=3
Dn Slope=0.005
Boundary for River Rch & Prof#=Big Cottonwood C,Reach-1,5
Up Type=0
Dn Type=3
Dn Slope=0.005
Boundary for River Rch & Prof#=Big Cottonwood C,Reach-1,6
Up Type=0
Dn Type=3
Dn Slope=0.005
Boundary for River Rch & Prof#=Big Cottonwood C,Reach-1,7
Up Type=0
Dn Type=3
Dn Slope=0.005

--- Big Cottonwood Creek Trib 5.g01 (geometry) ---

Geom Title=Existing Conditions

River Reach=Big Cottonwood C,Reach-1
Reach XY= 30
      2655376.00      6894861.00      2655427.98      6894166.67
      2655575.67      6894045.97      2655522.46      6893462.47
      2655331.26      6893305.53      2655318.12      6893204.88
      2654917.52      6892714.51      2654519.91      6892462.79
      2654286.51      6892509.80      2653881.71      6892363.59
      2653674.43      6891622.56      2653576.46      6891595.35
      2653626.36      6891431.15      2653583.73      6891157.35
      2653674.07      6891016.98      2653570.91      6890816.04
      2653431.45      6890805.81      2653227.78      6890404.87
      2653324.94      6890250.56      2653324.78      6889921.50
      2652976.29      6888845.88      2653276.43      6887626.18
      2653275.48      6886376.22      2653173.92      6885866.86
      2653027.22      6885600.50      2653076.32      6885236.04
      2653026.07      6884981.03      2653424.78      6883450.50
      2653428.02      6882966.84      2653526.00      6882861.00

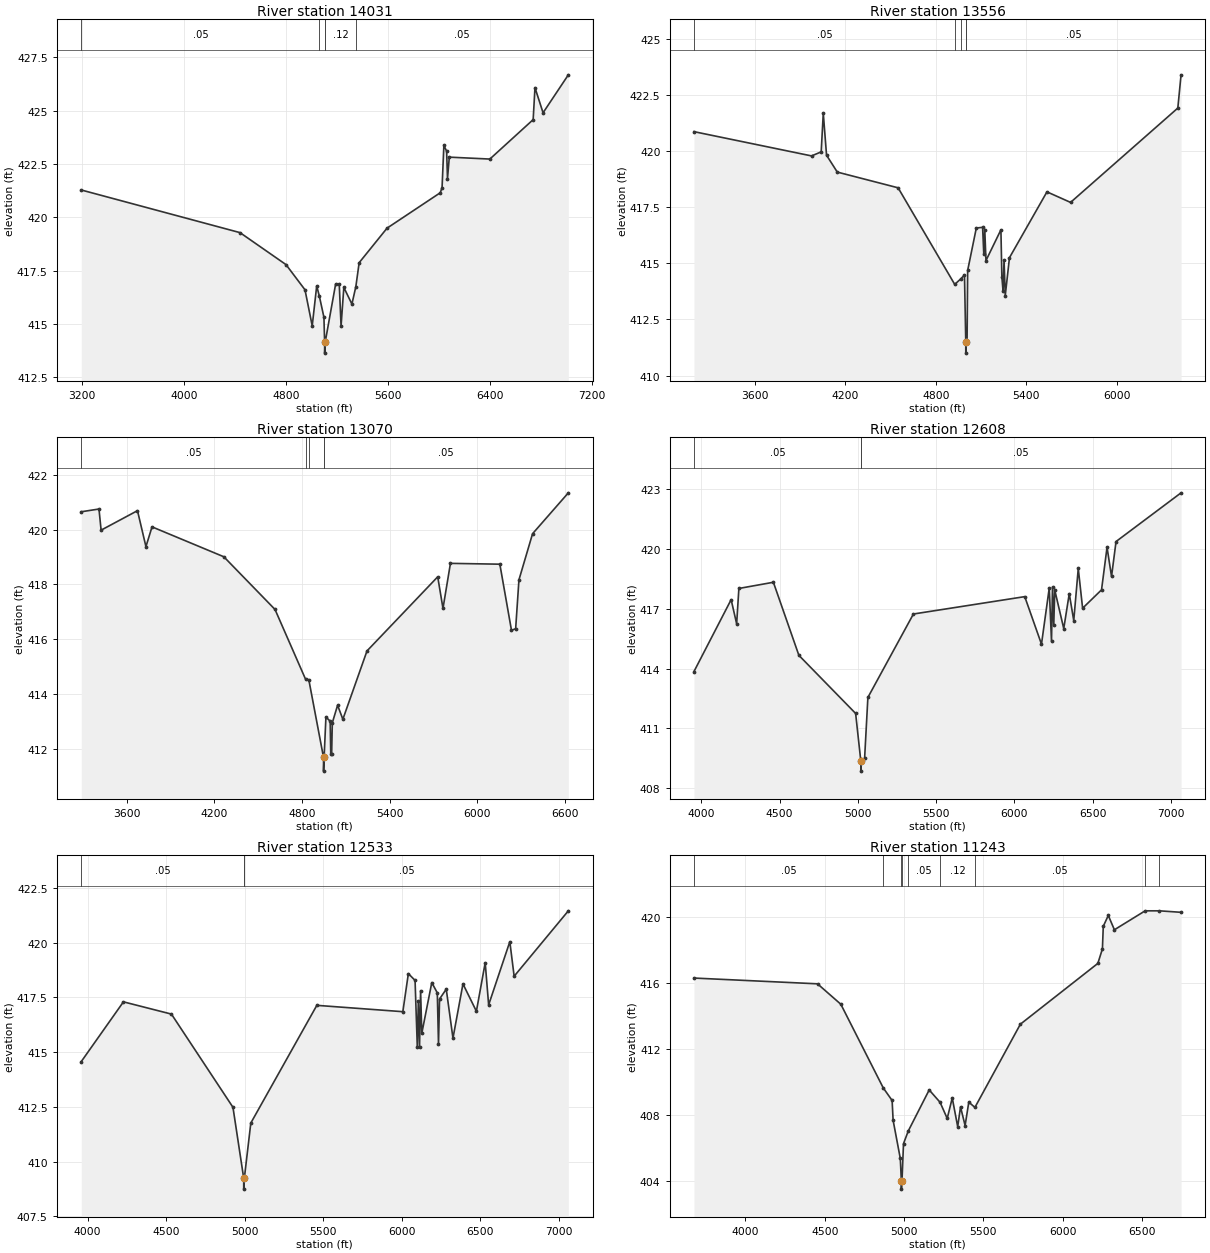
Type RM Length L Ch R = 1,14031,475,475,475
BEGIN DESCRIPTION:
Big Cottonwood Creek Trib 5 20.0
END DESCRIPTION:
XS GIS Cut Line= 3
      2656775.99      6895810.99      2655426.00      6894611.00
      2653925.98      6895961.02
#Sta/Elev= 30
  3193.8  421.28  4440.2  419.28  4801.4  417.78  4950.3  416.60  5007.1  414.91
  5042.3  416.78  5063.2  416.30  5099.1  415.31  5104.5  414.13  5104.8  413.63
  5108.5  414.13  5191.0  416.87  5219.4  416.86  5233.6  414.90  5255.3  416.71
  5318.8  415.93  5349.7  416.75  5375.6  417.87  5594.6  419.49  6012.4  421.15
  6026.6  421.39  6040.8  423.37  6062.5  423.10  6069.2  421.81  6083.4  422.82
  6401.8  422.73  6741.9  424.58  6756.1  426.08  6819.6  424.90  7018.1  426.68
#Mann=5,-1,0
  3193.8    0.05       0  5063.2    0.12       0  5104.5    0.03       0
  5108.5    0.12       0  5349.7    0.05       0
Bank Sta=5104.5,5108.5
Exp/Cntr=0.3,0.1

Type RM Length L Ch R = 1,13556,486,486,486
BEGIN DESCRIPTION:
Big Cottonwood Creek Trib 5 19.0
END DESCRIPTION:
XS GIS Cut Line= 3
      2656626.00      6895511.00      2655426.00      6894161.00
      2654326.00      6895061.00
#Sta/Elev= 30
  3198.0  420.86  3976.9  419.78  4040.9  419.96  4054.7  421.68  4076.4  419.81
  4147.5  419.06  4550.6  418.36  4925.7  414.06  4966.3  414.31  4990.4  414.48
  4998.9  411.50  4999.1  411.00  5002.9  411.50  5007.5  411.50  5011.4  414.68
  5068.8  416.57  5110.5  416.60  5118.4  415.40  5124.8  416.50  5132.7  415.12
  5231.8  416.49  5238.2  414.39  5246.1  413.75  5252.6  415.16  5260.5  413.56
  5288.5  415.25  5536.9  418.18  5693.3  417.71  6404.0  421.91  6425.5  423.39
#Mann=5,-1,0
  3198.0    0.05       0  4925.7    0.12       0  4966.3    0.05       0
  4998.9    0.03       0  5002.9    0.05       0
Bank Sta=4998.9,5002.9
Exp/Cntr=0.3,0.1

Type RM Length L Ch R = 1,13070,462,462,462
BEGIN DESCRIPTION:
Big Cottonwood Creek Trib 5 18.0
END DESCRIPTION:
XS GIS Cut Line= 3
      2656625.98      6895110.98      2655576.00      6893761.00
      2654226.03      6894660.98
#Sta/Elev= 30
  3289.9  420.65  3411.1  420.75  3425.6  419.98  3674.5  420.69  3732.4  419.38
  3774.0  420.10  4265.4  419.01  4615.6  417.09  4824.4  414.55  4846.8  414.53
  4947.5  411.70  4947.7  411.20  4951.5  411.70  4963.9  413.17  4992.9  413.02
  4997.0  411.84  5003.1  411.84  5007.6  412.96  5043.7  413.60  5079.8  413.09
  5245.0  415.58  5728.8  418.28  5764.8  417.13  5815.9  418.77  6153.9  418.74
  6233.5  416.33  6262.1  416.39  6284.6  418.17  6377.8  419.85  6622.6  421.34
#Mann=5,-1,0
  3289.9    0.05       0  4824.4    0.12       0  4846.8    0.05       0
  4947.5    0.03       0  4951.5    0.05       0
Bank Sta=4947.5,4951.5
Exp/Cntr=0.3,0.1

Type RM Length L Ch R = 1,12608,75,75,75
BEGIN DESCRIPTION:
Mapping XS 056c4bab
END DESCRIPTION:
XS GIS Cut Line= 3
      2656232.87      6892694.23      2655409.97      6893366.09
      2653817.30      6894656.89
#Sta/Elev= 30
  3952.9  413.85  4190.3  417.45  4225.5  416.24  4239.8  418.01  4460.2  418.32
  4623.2  414.66  4985.8  411.75  5019.0  409.36  5019.3  408.86  5023.0  409.36
  5043.3  409.52  5064.1  412.55  5355.0  416.73  6066.4  417.60  6173.4  415.22
  6223.0  418.03  6237.4  415.37  6243.8  418.08  6251.8  416.16  6258.2  417.93
  6315.7  416.00  6350.9  417.75  6379.6  416.40  6408.4  419.01  6436.2  417.02
  6557.1  417.94  6592.3  420.07  6621.0  418.61  6649.8  420.36  7065.3  422.80
#Mann=3,-1,0
  3952.9    0.05       0  5019.0    0.03       0  5023.0    0.05       0
Bank Sta=5019,5023
Exp/Cntr=0.3,0.1

Type RM Length L Ch R = 1,12533,1290,1290,1290
BEGIN DESCRIPTION:
Mapping XS ef2d94b5
END DESCRIPTION:
XS GIS Cut Line= 4
      2656170.35      6892657.79      2655347.47      6893324.43
      2654784.97      6893767.14      2653785.49      6894636.47
#Sta/Elev= 30
  3960.1  414.57  4228.4  417.30  4533.8  416.74  4925.4  412.48  4993.8  409.24
  4994.0  408.74  4997.8  409.24  5039.0  411.76  5459.1  417.14  6006.4  416.85
  6041.5  418.59  6084.2  418.28  6098.5  415.23  6105.1  417.34  6112.7  415.25
  6119.4  417.81  6127.0  415.86  6190.6  418.18  6225.7  417.71  6233.3  415.36
  6240.0  417.43  6282.7  417.88  6325.4  415.64  6389.0  418.12  6474.5  416.87
  6530.5  419.09  6552.4  417.16  6687.2  420.05  6714.7  418.47  7059.6  421.46
#Mann=3,-1,0
  3960.1    0.05       0  4993.8    0.03       0  4997.8    0.05       0
Bank Sta=4993.8,4997.8
Exp/Cntr=0.3,0.1

Type RM Length L Ch R = 1,11243,690,690,690
BEGIN DESCRIPTION:
Big Cottonwood Creek Trib 5 15.0
END DESCRIPTION:
XS GIS Cut Line= 4
      2655597.51      6891897.34      2654712.81      6892092.35
      2654515.34      6892461.74      2653811.75      6894061.12
#Sta/Elev= 30
  3675.2  416.32  4454.3  415.97  4601.4  414.73  4869.1  409.65  4924.9  408.89
  4931.1  407.69  4976.5  405.37  4983.1  404.01  4983.3  403.51  4987.1  404.01
  4996.7  406.27  5026.8  407.04  5158.7  409.53  5227.3  408.78  5272.3  407.80
  5304.2  409.04  5338.5  407.30  5356.3  408.50  5385.2  407.37  5408.5  408.79
  5447.1  408.47  5733.8  413.52  6222.5  417.21  6251.3  418.09  6256.7  419.46
  6288.3  420.12  6326.8  419.25  6520.8  420.40  6611.2  420.40  6747.3  420.31
#Mann=9,-1,0
  3675.2    0.05       0  4869.1    0.12       0  4983.1    0.07       0
  4987.1    0.12       0  5026.8    0.05       0  5227.3    0.12       0
  5447.1    0.05       0  6520.8   0.075       0  6611.2    0.05       0
Bank Sta=4983.1,4987.1
Exp/Cntr=0.3,0.1

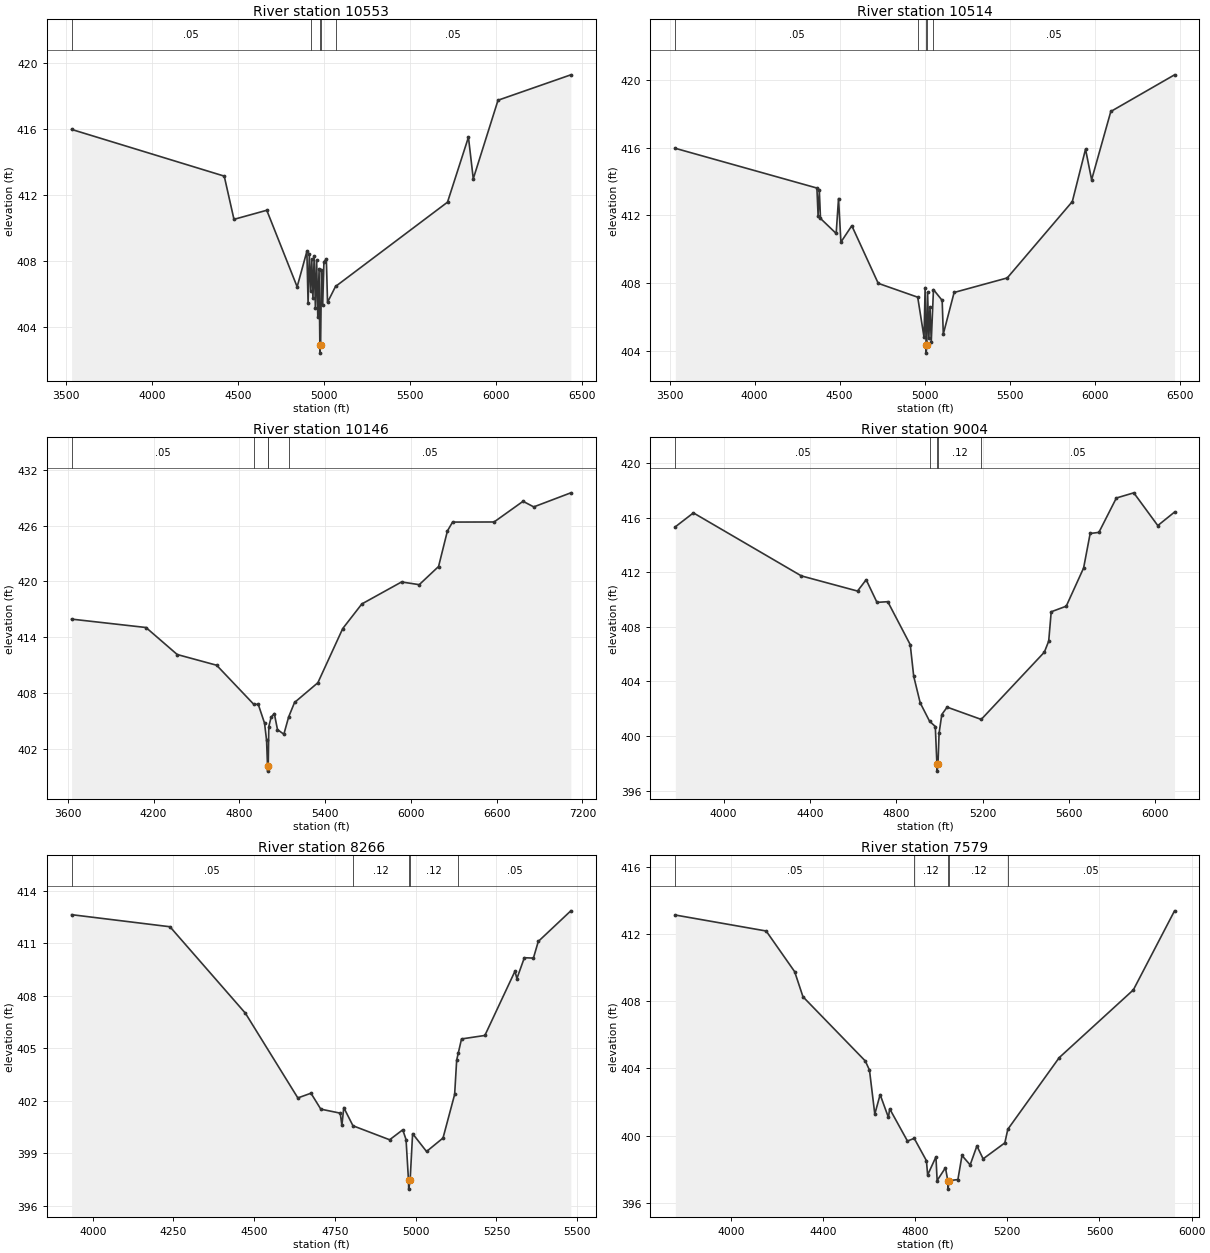
Type RM Length L Ch R = 1,10553,39,39,39
BEGIN DESCRIPTION:
Mapping XS de907d04
END DESCRIPTION:
XS GIS Cut Line= 5
      2654962.02      6891371.33      2653883.92      6892376.51
      2653540.17      6892699.43      2653373.51      6892944.22
      2653003.81      6893496.16
#Sta/Elev= 30
  3531.5  415.99  4419.9  413.16  4476.6  410.54  4667.6  411.09  4844.4  406.45
  4901.1  408.60  4908.0  405.45  4915.3  408.43  4923.0  406.22  4929.5  408.11
  4936.3  405.75  4943.6  408.31  4950.5  405.19  4957.8  408.06  4964.6  404.62
  4972.0  407.51  4976.6  402.93  4977.0  402.43  4981.0  402.93  4986.1  407.49
  4993.0  405.33  5000.3  407.97  5014.4  408.13  5021.3  405.51  5067.7  406.47
  5719.7  411.58  5841.6  415.52  5869.7  413.00  6013.8  417.76  6437.6  419.30
#Mann=5,-1,0
  3531.5    0.05       0  4923.0    0.12       0  4976.6    0.07       0
  4981.0    0.12       0  5067.7    0.05       0
Bank Sta=4976.6,4981
Exp/Cntr=0.3,0.1

Type RM Length L Ch R = 1,10514,368,368,368
BEGIN DESCRIPTION:
Mapping XS 8d172067
END DESCRIPTION:
XS GIS Cut Line= 4
      2654946.44      6891334.83      2653883.92      6892329.64
      2653477.67      6892668.18      2652837.02      6893371.34
#Sta/Elev= 30
  3534.0  415.97  4366.5  413.62  4373.4  411.99  4380.7  413.48  4387.6  411.82
  4479.8  410.93  4493.6  413.00  4507.7  410.42  4571.7  411.39  4727.1  407.98
  4959.3  407.16  4996.4  404.79  5002.9  407.73  5008.5  404.35  5008.9  403.85
  5012.9  404.35  5017.2  407.45  5025.0  404.77  5031.6  406.58  5038.9  404.52
  5051.9  407.61  5103.1  406.97  5109.7  404.98  5173.4  407.44  5485.8  408.30
  5868.5  412.82  5946.2  415.92  5982.0  414.11  6094.8  418.15  6469.6  420.32
#Mann=5,-1,0
  3534.0    0.05       0  4959.3    0.12       0  5008.5    0.07       0
  5012.9    0.12       0  5051.9    0.05       0
Bank Sta=5008.5,5012.9
Exp/Cntr=0.3,0.1

Type RM Length L Ch R = 1,10146,1142,1142,1142
BEGIN DESCRIPTION:
Mapping XS ce15f5e7
END DESCRIPTION:
XS GIS Cut Line= 3
      2654941.19      6891293.19      2653758.92      6892006.72
      2651863.06      6892933.82
#Sta/Elev= 30
  3627.3  415.96  4147.3  415.06  4365.8  412.16  4641.4  411.01  4901.4  406.81
  4932.5  406.81  4976.6  404.79  4990.8  402.93  4997.5  400.14  4998.1  399.64
  5002.3  400.14  5006.3  404.42  5022.6  405.43  5044.8  405.82  5067.1  404.10
  5111.6  403.60  5145.0  405.45  5186.3  407.01  5349.5  409.13  5523.5  414.95
  5657.1  417.59  5934.8  419.95  6058.5  419.66  6193.6  421.61  6255.6  425.43
  6291.6  426.38  6581.9  426.39  6784.5  428.61  6859.3  428.01  7118.6  429.52
#Mann=5,-1,0
  3627.3    0.05       0  4901.4    0.12       0  4997.5    0.07       0
  5002.3    0.12       0  5145.0    0.05       0
Bank Sta=4997.5,5002.3
Exp/Cntr=0.3,0.1

Type RM Length L Ch R = 1,9004,738,738,738
BEGIN DESCRIPTION:
Big Cottonwood Creek Trib 5 11.0
END DESCRIPTION:
XS GIS Cut Line= 3
      2654899.56      6891105.68      2653676.00      6891061.00
      2652599.25      6891220.00
#Sta/Elev= 30
  3776.6  415.34  3860.2  416.36  4360.5  411.74  4620.7  410.63  4660.7  411.46
  4710.8  409.80  4760.8  409.85  4864.9  406.70  4880.9  404.39  4910.9  402.44
  4954.4  401.09  4981.0  400.70  4988.5  397.93  4989.1  397.43  4993.4  397.93
  4998.5  400.21  5011.1  401.58  5035.8  402.12  5193.8  401.22  5486.2  406.15
  5506.4  406.96  5518.0  409.11  5587.6  409.52  5668.1  412.32  5698.5  414.85
  5738.9  414.93  5819.8  417.45  5900.6  417.83  6011.8  415.43  6089.4  416.42
#Mann=5,-1,0
  3776.6    0.05       0  4954.4    0.12       0  4988.5    0.07       0
  4993.4    0.12       0  5193.8    0.05       0
Bank Sta=4988.5,4993.4
Exp/Cntr=0.3,0.1

Type RM Length L Ch R = 1,8266,687,687,687
BEGIN DESCRIPTION:
Big Cottonwood Creek Trib 5 10.0
END DESCRIPTION:
XS GIS Cut Line= 3
      2654326.01      6890361.00      2653276.64      6890545.73
      2652876.00      6890811.00
#Sta/Elev= 30
  3934.5  412.62  4239.1  411.93  4472.7  406.99  4635.1  402.15  4675.7  402.42
  4706.2  401.51  4766.4  401.28  4771.5  400.58  4777.3  401.60  4805.8  400.56
  4919.4  399.76  4960.0  400.33  4970.2  399.77  4977.8  397.44  4978.4  396.94
  4982.8  397.44  4990.5  400.11  5033.7  399.09  5084.7  399.86  5120.7  402.35
  5127.0  404.31  5131.9  404.71  5142.0  405.52  5214.3  405.72  5307.5  409.39
  5313.5  408.97  5336.6  410.16  5364.7  410.14  5379.7  411.09  5480.5  412.84
#Mann=5,-1,0
  3934.5    0.05       0  4805.8    0.12       0  4977.8    0.07       0
  4982.8    0.12       0  5131.9    0.05       0
Bank Sta=4977.8,4982.8
Exp/Cntr=0.3,0.1

Type RM Length L Ch R = 1,7579,486,486,486
BEGIN DESCRIPTION:
Big Cottonwood Creek Trib 5 9.0
END DESCRIPTION:
XS GIS Cut Line= 3
      2654525.99      6890211.00      2653326.00      6889911.00
      2652575.98      6890461.01
#Sta/Elev= 30
  3758.8  413.12  4153.1  412.17  4276.8  409.75  4312.8  408.26  4583.4  404.44
  4601.5  403.90  4624.6  401.28  4647.8  402.44  4683.9  401.08  4689.1  401.60
  4766.4  399.68  4795.7  399.84  4848.8  398.51  4854.0  397.66  4890.1  398.74
  4895.2  397.33  4931.3  398.09  4941.6  397.32  4942.3  396.82  4946.8  397.32
  4985.4  397.39  5003.1  398.82  5038.6  398.26  5067.9  399.39  5094.9  398.62
  5189.1  399.57  5202.1  400.38  5425.2  404.64  5747.1  408.67  5925.8  413.37
#Mann=5,-1,0
  3758.8    0.05       0  4795.7    0.12       0  4941.6    0.07       0
  4946.8    0.12       0  5202.1    0.05       0
Bank Sta=4941.6,4946.8
Exp/Cntr=0.3,0.1

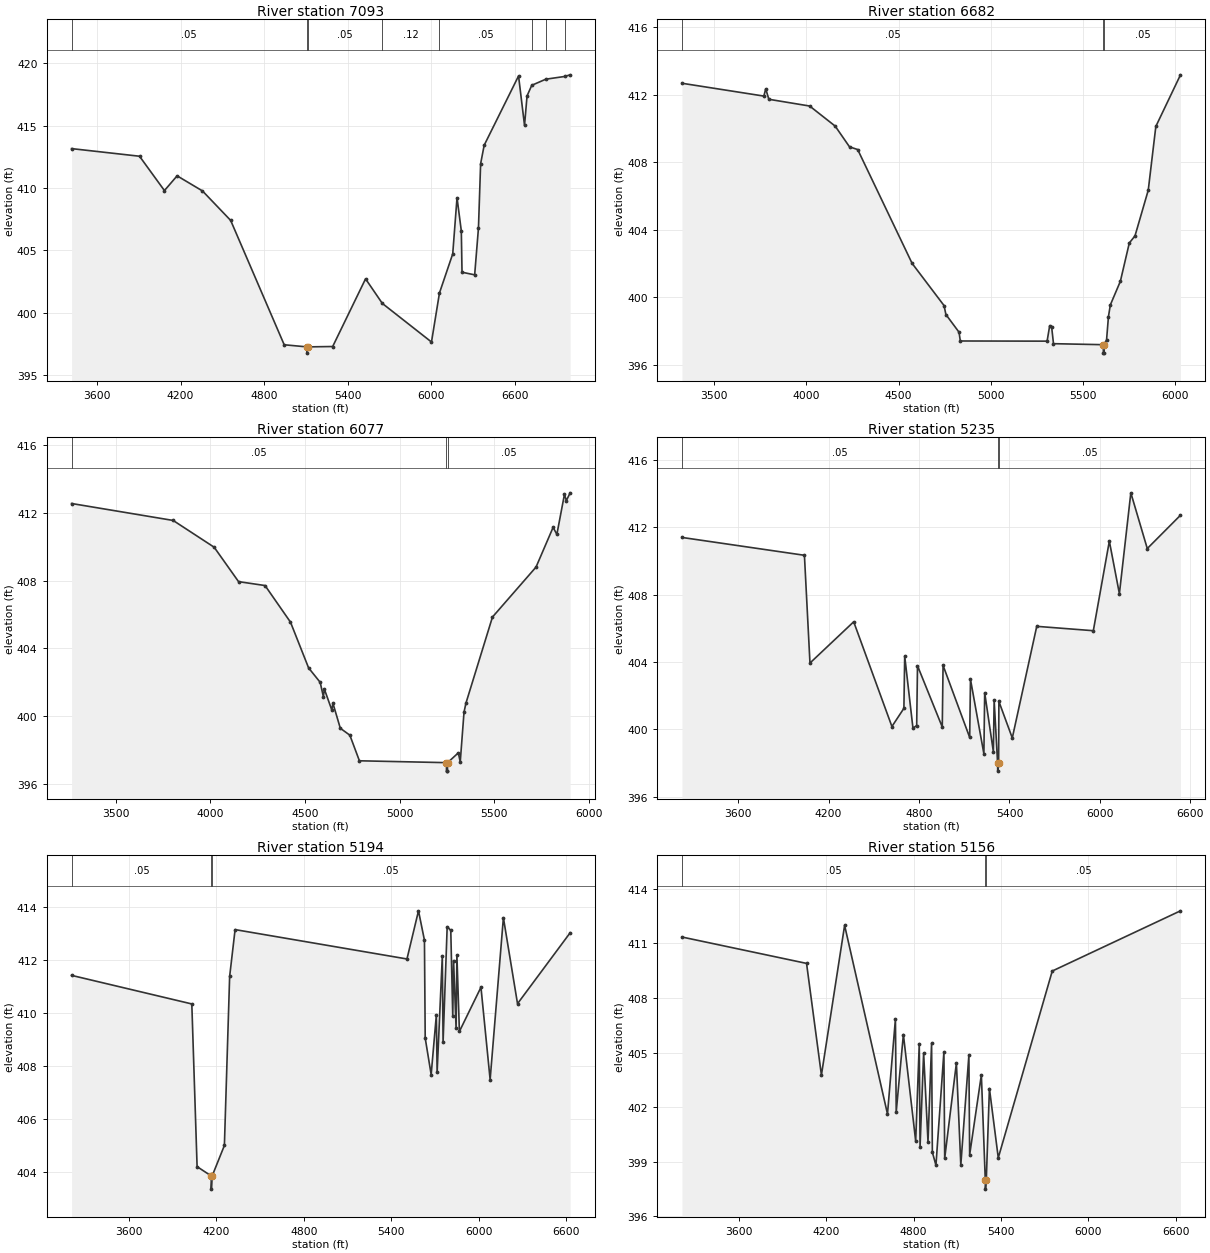
Type RM Length L Ch R = 1,7093,411,411,411
BEGIN DESCRIPTION:
Big Cottonwood Creek Trib 5 8.0
END DESCRIPTION:
XS GIS Cut Line= 3
      2654784.98      6889699.43      2653226.00      6889461.00
      2651274.51      6889011.92
#Sta/Elev= 30
  3417.5  413.16  3905.2  412.55  4084.1  409.80  4175.2  410.98  4357.3  409.77
  4559.6  407.41  4944.0  397.45  5106.7  397.28  5107.4  396.78  5112.0  397.28
  5292.2  397.31  5528.2  402.73  5648.7  400.76  6001.6  397.67  6058.9  401.60
  6154.1  404.73  6184.9  409.23  6215.7  406.57  6220.8  403.26  6311.6  403.05
  6338.8  406.80  6354.4  411.95  6379.9  413.43  6626.7  418.98  6669.6  415.02
  6687.7  417.38  6721.4  418.23  6822.4  418.72  6959.0  418.94  6997.1  419.07
#Mann=8,-1,0
  3417.5    0.05       0  5106.7    0.03       0  5112.0    0.05       0
  5648.7    0.12       0  6058.9    0.05       0  6721.4   0.075       0
  6822.4     0.1       0  6959.0   0.075       0
Bank Sta=5106.7,5112
Exp/Cntr=0.3,0.1

Type RM Length L Ch R = 1,6682,605,605,605
BEGIN DESCRIPTION:
Big Cottonwood Creek Trib 5 7.0
END DESCRIPTION:
XS GIS Cut Line= 3
      2654722.44      6889402.55      2653076.15      6889095.94
      2652075.97      6888860.99
#Sta/Elev= 30
  3325.4  412.68  3769.3  411.92  3779.5  412.35  3796.4  411.73  4017.6  411.33
  4155.9  410.14  4233.6  408.91  4277.9  408.75  4572.9  402.00  4745.9  399.50
  4756.0  398.97  4827.2  397.92  4834.1  397.40  5304.5  397.39  5318.6  398.31
  5328.9  398.25  5339.1  397.24  5609.0  397.18  5609.7  396.68  5613.5  396.68
  5614.3  397.18  5626.8  397.47  5637.0  398.85  5647.3  399.54  5701.6  400.94
  5750.0  403.21  5780.8  403.63  5852.7  406.34  5893.8  410.12  6027.4  413.18
#Mann=3,-1,0
  3325.4    0.05       0  5609.0    0.03       0  5614.3    0.05       0
Bank Sta=5609,5614.3
Exp/Cntr=0.3,0.1

Type RM Length L Ch R = 1,6077,842,842,842
BEGIN DESCRIPTION:
Big Cottonwood Creek Trib 5 6.0
END DESCRIPTION:
XS GIS Cut Line= 3
      2654575.96      6889310.98      2653025.85      6888538.78
      2652126.02      6888561.00
#Sta/Elev= 30
  3268.2  412.55  3804.4  411.55  4020.9  409.97  4149.6  407.94  4289.5  407.71
  4423.8  405.55  4519.4  402.85  4580.5  402.00  4597.3  401.16  4602.9  401.59
  4642.1  400.36  4647.7  400.77  4686.8  399.29  4737.2  398.88  4787.6  397.37
  5246.5  397.26  5247.6  396.76  5252.2  396.76  5253.3  397.26  5309.9  397.84
  5319.9  397.30  5339.9  400.24  5350.0  400.77  5490.0  405.85  5720.1  408.80
  5810.1  411.14  5830.1  410.73  5870.1  413.09  5880.1  412.72  5900.1  413.18
#Mann=3,-1,0
  3268.2    0.05       0  5246.5    0.03       0  5253.3    0.05       0
Bank Sta=5246.5,5253.3
Exp/Cntr=0.3,0.1

Type RM Length L Ch R = 1,5235,41,41,41
BEGIN DESCRIPTION:
Mapping XS 0aa72706
END DESCRIPTION:
XS GIS Cut Line= 5
      2654784.95      6888590.04      2653774.55      6887970.26
      2653243.30      6887767.14      2652659.97      6887569.22
      2651805.79      6887954.64
#Sta/Elev= 30
  3227.3  411.39  4039.8  410.33  4076.6  403.93  4366.7  406.38  4620.2  400.16
  4699.7  401.24  4705.0  404.34  4759.8  400.06  4784.5  400.22  4789.9  403.77
  4954.2  400.13  4959.5  403.79  5136.1  399.51  5141.4  402.96  5230.3  398.54
  5235.6  402.17  5293.1  398.67  5298.4  401.72  5321.1  398.01  5322.2  397.51
  5328.0  398.01  5329.8  401.65  5418.7  399.48  5581.0  406.11  5956.3  405.85
  6062.5  411.17  6129.2  408.05  6205.1  414.04  6314.2  410.73  6534.5  412.71
#Mann=3,-1,0
  3227.3    0.05       0  5321.1    0.03       0  5328.0    0.05       0
Bank Sta=5321.1,5328
Exp/Cntr=0.3,0.1

Type RM Length L Ch R = 1,5194,38,38,38
BEGIN DESCRIPTION:
Mapping XS 1cf52260
END DESCRIPTION:
XS GIS Cut Line= 6
      2654790.17      6888569.22      2653889.13      6887965.05
      2653227.67      6887720.26      2652686.01      6887522.34
      2652462.05      6887579.64      2651722.45      6887928.60
#Sta/Elev= 30
  3209.7  411.43  4033.4  410.35  4069.6  404.20  4166.1  403.85  4167.2  403.35
  4173.0  403.85  4256.6  405.00  4292.6  411.39  4329.9  413.16  5507.5  412.05
  5586.5  413.87  5627.3  412.76  5632.5  409.06  5673.3  407.68  5709.0  409.94
  5714.1  407.76  5749.8  412.17  5754.9  408.90  5783.0  413.27  5807.7  413.13
  5821.3  409.88  5826.8  411.99  5844.0  409.44  5849.6  412.20  5866.8  409.31
  6014.5  410.98  6077.3  407.49  6168.2  413.61  6265.0  410.36  6625.5  413.04
#Mann=3,-1,0
  3209.7    0.05       0  4166.1    0.04       0  4173.0    0.05       0
Bank Sta=4166.1,4173
Exp/Cntr=0.3,0.1

Type RM Length L Ch R = 1,5156,1891,1891,1891
BEGIN DESCRIPTION:
Mapping XS 303d5d12
END DESCRIPTION:
XS GIS Cut Line= 6
      2654805.77      6888548.37      2653894.34      6887939.01
      2653248.51      6887689.01      2652717.26      6887491.09
      2652639.13      6887475.47      2651732.88      6887860.89
#Sta/Elev= 30
  3210.8  411.35  4065.7  409.90  4167.7  403.76  4326.8  411.99  4621.0  401.62
  4675.5  406.85  4680.8  401.73  4730.0  405.99  4814.4  400.13  4839.0  405.49
  4844.4  399.83  4868.9  404.97  4898.9  400.10  4923.5  405.50  4928.8  399.52
  4953.4  398.80  5008.0  405.03  5013.4  399.18  5093.7  404.42  5124.0  398.82
  5179.3  404.84  5184.7  399.38  5265.0  403.77  5291.9  397.99  5293.0  397.49
  5298.8  397.99  5320.3  403.02  5381.0  399.21  5751.4  409.48  6631.1  412.79
#Mann=3,-1,0
  3210.8    0.05       0  5291.9    0.04       0  5298.8    0.05       0
Bank Sta=5291.9,5298.8
Exp/Cntr=0.3,0.1

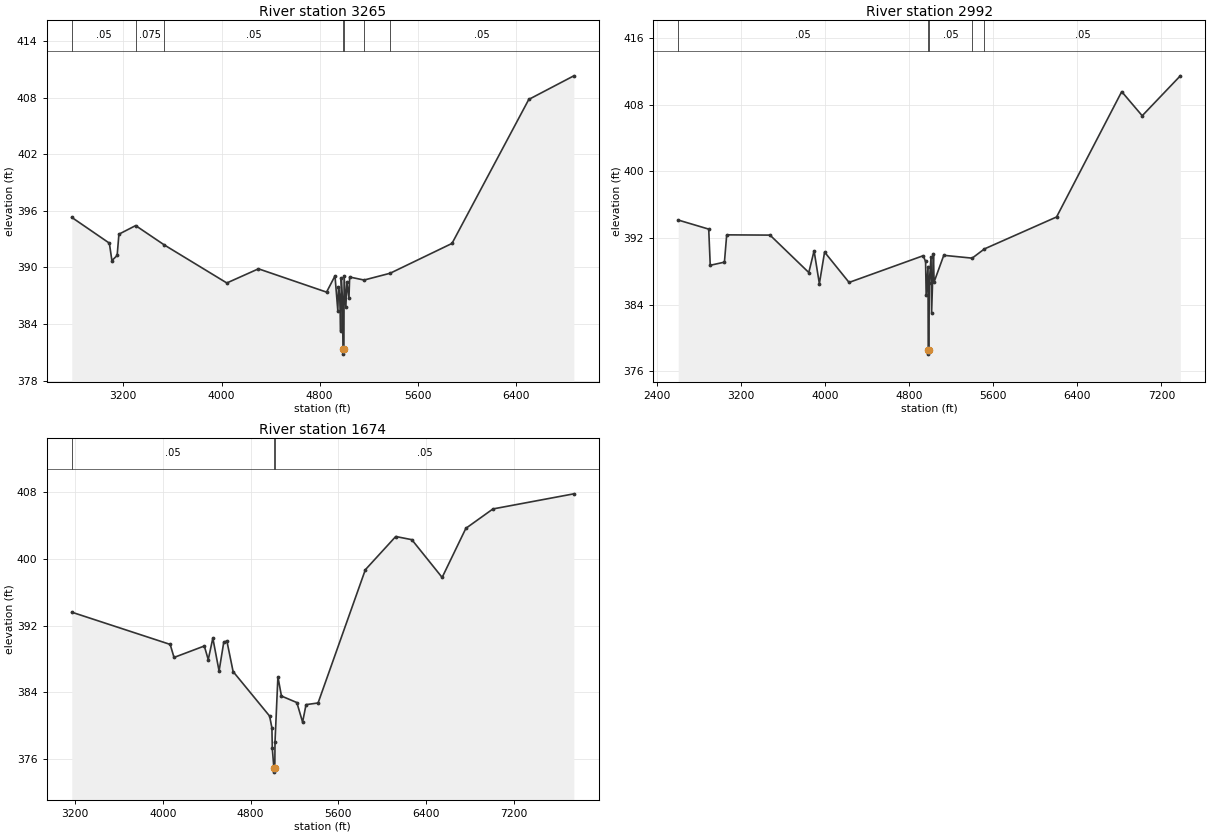
Type RM Length L Ch R = 1,3265,273,273,273
BEGIN DESCRIPTION:
Mapping XS 882cdd5a
END DESCRIPTION:
XS GIS Cut Line= 5
      2654501.00      6885727.76      2653580.86      6884932.63
      2653153.78      6885856.24      2652757.94      6886634.02
      2652348.21      6887529.88
#Sta/Elev= 30
  2779.7  395.30  3086.0  392.57  3106.8  390.72  3149.6  391.27  3163.9  393.52
  3300.3  394.43  3534.9  392.37  4043.3  388.35  4301.1  389.85  4856.0  387.38
  4924.8  389.10  4947.8  385.42  4953.3  387.88  4963.5  386.92  4970.7  383.26
  4976.2  388.86  4985.6  386.76  4990.0  381.31  4991.1  380.81  4997.3  381.31
  4999.1  389.09  5013.2  385.82  5021.9  388.44  5038.5  386.76  5044.2  388.98
  5161.8  388.66  5374.0  389.38  5878.2  392.54  6504.0  407.80  6871.2  410.30
#Mann=7,-1,0
  2779.7    0.05       0  3300.3   0.075       0  3534.9    0.05       0
  4990.0    0.05       0  4997.3    0.05       0  5161.8   0.075       0
  5374.0    0.05       0
Bank Sta=4990,4997.3
Exp/Cntr=0.3,0.1

Type RM Length L Ch R = 1,2992,1318,1318,1318
BEGIN DESCRIPTION:
Mapping XS 19874e81
END DESCRIPTION:
XS GIS Cut Line= 6
      2654546.10      6885679.12      2653421.14      6884759.02
      2653035.72      6885616.65      2652542.67      6886710.40
      2652262.72      6887378.74      2651863.85      6887602.76
#Sta/Elev= 30
  2604.7  394.16  2894.7  393.07  2909.1  388.72  3044.1  389.10  3065.6  392.38
  3477.6  392.35  3846.6  387.85  3896.7  390.46  3947.1  386.51  3996.6  390.31
  4229.6  386.66  4934.2  389.87  4957.4  389.18  4962.8  385.17  4980.5  388.56
  4982.4  378.54  4983.5  378.04  4989.7  378.54  4992.1  386.57  5009.2  389.75
  5014.6  383.02  5032.3  390.11  5037.8  386.70  5130.3  389.92  5400.5  389.58
  5517.1  390.69  6203.2  394.53  6822.8  409.60  7017.7  406.70  7380.1  411.50
#Mann=5,-1,0
  2604.7    0.05       0  4982.4    0.03       0  4989.7    0.05       0
  5400.5   0.075       0  5517.1    0.05       0
Bank Sta=4982.4,4989.7
Exp/Cntr=0.3,0.1

Type RM Length L Ch R = 1,1674,0,0,0
BEGIN DESCRIPTION:
Big Cottonwood Creek Trib 5 1.0
END DESCRIPTION:
XS GIS Cut Line= 3
      2654560.04      6885613.19      2653186.89      6884401.37
      2650566.94      6885227.78
#Sta/Elev= 30
  3168.6  393.60  4066.0  389.74  4101.1  388.18  4377.2  389.55  4413.2  387.92
  4455.0  390.49  4511.9  386.56  4554.6  390.00  4583.0  390.16  4639.9  386.49
  4972.9  381.16  4993.8  379.74  4997.3  377.30  5011.7  374.95  5013.0  374.45
  5020.3  374.95  5021.9  378.03  5048.4  385.86  5080.7  383.56  5221.1  382.78
  5273.6  380.44  5305.0  382.53  5414.7  382.73  5845.7  398.68  6122.9  402.66
  6269.7  402.28  6546.1  397.76  6762.5  403.64  7009.5  405.96  7747.2  407.77
#Mann=3,-1,0
  3168.6    0.05       0  5011.7    0.04       0  5020.3    0.05       0
Bank Sta=5011.7,5020.3
Exp/Cntr=0.3,0.1

Chan Stop Cuts=-1