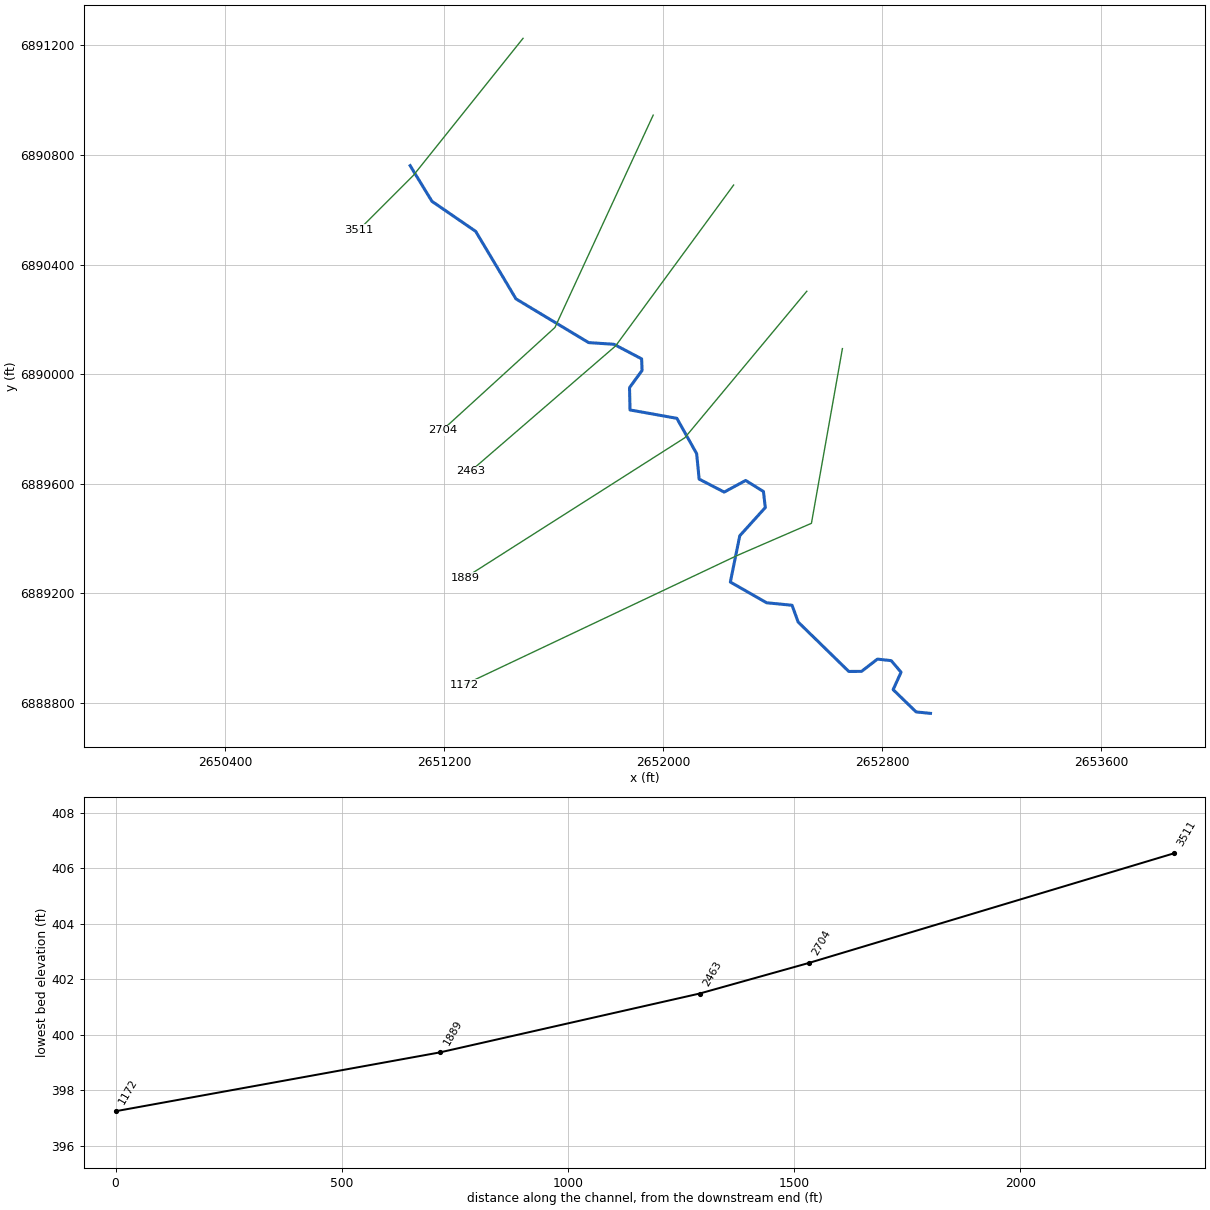
--- Big Cottonwood Creek Trib 5_1.prj (project) ---

Proj Title=Big Cottonwood Creek Trib 5_1 Base Level Engineering
Current Plan=p01
Default Exp/Contr=0.3,0.1
English Units
Geom File=g01
Flow File=f01
Plan File=p01
BEGIN DESCRIPTION:
Big Cottonwood Creek Trib 5_1
END DESCRIPTION:

--- Big Cottonwood Creek Trib 5_1.p01 (plan) ---

Plan Title=Multiple Run
Short Identifier=Multiple
Geom File=g01
Flow File=f01
Subcritical Flow
K Sum by GR= 0
Std Step Tol= 0.01
Critical Tol= 0.01
Num of Std Step Trials= 20
Max Error Tol= 0.3
Flow Tol Ratio= 0.001
Split Flow NTrial= 30
Split Flow Tol= 0.02
Split Flow Ratio= 0.02
Log Output Level= 0
Friction Slope Method= 1
Unsteady Friction Slope Method= 2
Unsteady Bridges Friction Slope Method= 1
Parabolic Critical Depth
Global Vel Dist=  1 , 1 , 1
Global Log Level= 0
CheckData=True
Encroach Param= -1, 0, 0, 0
BEGIN DESCRIPTION:
Multiple Run
END DESCRIPTION:

--- Big Cottonwood Creek Trib 5_1.f01 (steady flow) ---

Flow Title=Multiple
Number of Profiles=7
Profile Names=10-year,25-year,50-year,1pct_min,100-year,1pct_plu,500-year
River Rch & RM= Big Cottonwood C,Reach-1,3511
     356     460     541     315     629    1255     850
Boundary for River Rch & Prof#=Big Cottonwood C,Reach-1,1
Up Type=0
Dn Type=3
Dn Slope=0.005
Boundary for River Rch & Prof#=Big Cottonwood C,Reach-1,2
Up Type=0
Dn Type=3
Dn Slope=0.005
Boundary for River Rch & Prof#=Big Cottonwood C,Reach-1,3
Up Type=0
Dn Type=3
Dn Slope=0.005
Boundary for River Rch & Prof#=Big Cottonwood C,Reach-1,4
Up Type=0
Dn Type=3
Dn Slope=0.005
Boundary for River Rch & Prof#=Big Cottonwood C,Reach-1,5
Up Type=0
Dn Type=3
Dn Slope=0.005
Boundary for River Rch & Prof#=Big Cottonwood C,Reach-1,6
Up Type=0
Dn Type=3
Dn Slope=0.005
Boundary for River Rch & Prof#=Big Cottonwood C,Reach-1,7
Up Type=0
Dn Type=3
Dn Slope=0.005

--- Big Cottonwood Creek Trib 5_1.g01 (geometry) ---

Geom Title=Existing Conditions

River Reach=Big Cottonwood C,Reach-1
Reach XY= 30
      2651076.00      6890761.00      2651155.58      6890630.76
      2651315.35      6890521.00      2651462.44      6890274.49
      2651727.58      6890114.83      2651820.06      6890108.68
      2651921.24      6890055.42      2651922.81      6890013.11
      2651877.08      6889950.35      2651878.82      6889868.95
      2652049.90      6889838.30      2652122.14      6889709.34
      2652131.26      6889616.41      2652222.66      6889569.05
      2652301.11      6889611.44      2652365.96      6889571.11
      2652372.90      6889512.69      2652279.62      6889409.50
      2652245.13      6889240.58      2652377.65      6889164.86
      2652470.53      6889155.74      2652492.74      6889094.55
      2652677.63      6888914.13      2652724.27      6888914.37
      2652782.20      6888959.19      2652832.68      6888953.52
      2652868.53      6888911.28      2652839.61      6888847.65
      2652923.44      6888766.31      2652976.00      6888761.00

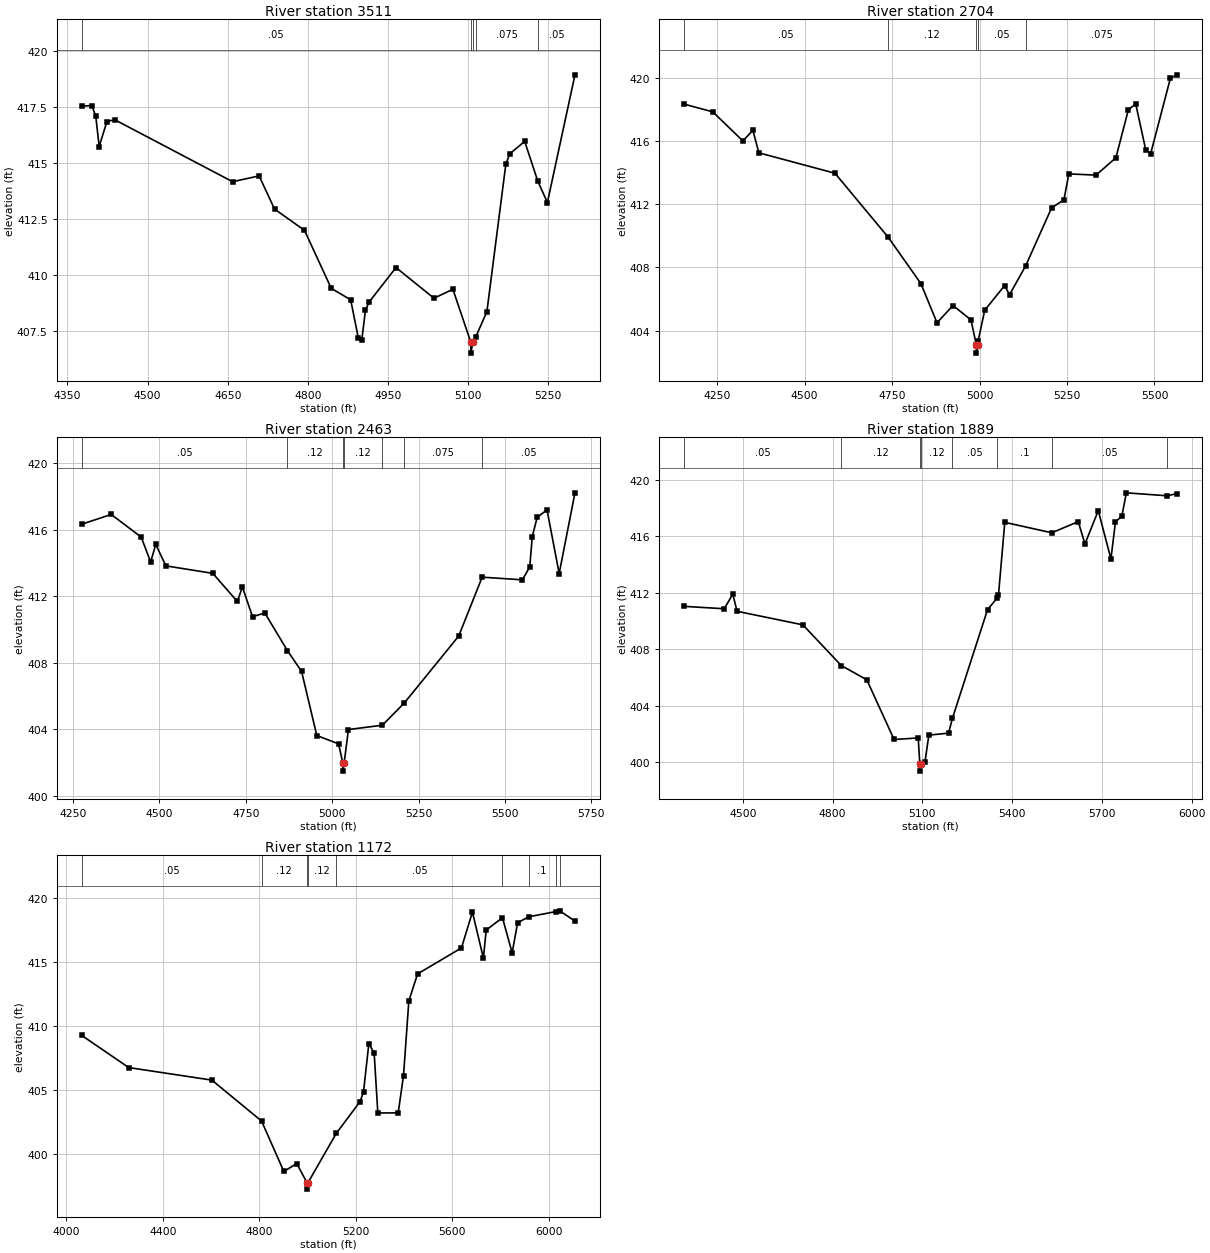
Type RM Length L Ch R = 1,3511,807,807,807
BEGIN DESCRIPTION:
Big Cottonwood Creek Trib 5_1 4.0
END DESCRIPTION:
XS GIS Cut Line= 3
      2651488.22      6891225.82      2651088.20      6890725.80
      2650888.19      6890525.79
#Sta/Elev= 30
  4376.6  417.55  4395.6  417.58  4403.1  417.11  4409.5  415.75  4423.9  416.86
  4438.3  416.95  4659.2  414.18  4708.8  414.44  4737.6  412.96  4793.7  412.01
  4843.8  409.42  4880.1  408.91  4894.5  407.20  4900.9  407.11  4907.8  408.46
  4915.3  408.83  4964.9  410.35  5036.0  408.98  5071.4  409.38  5104.7  407.03
  5105.0  406.53  5108.7  407.03  5113.9  407.24  5135.0  408.38  5170.4  414.95
  5177.5  415.42  5205.7  415.98  5230.2  414.21  5248.2  413.25  5299.8  418.95
#Mann=5,-1,0
  4376.6    0.05       0  5104.7    0.05       0  5108.7    0.05       0
  5113.9   0.075       0  5230.2    0.05       0
Bank Sta=5104.7,5108.7
Exp/Cntr=0.3,0.1

Type RM Length L Ch R = 1,2704,241,241,241
BEGIN DESCRIPTION:
Mapping XS be1a44ce
END DESCRIPTION:
XS GIS Cut Line= 3
      2651963.40      6890945.29      2651604.67      6890170.04
      2651193.79      6889795.20
#Sta/Elev= 30
  4155.0  418.32  4237.3  417.83  4323.5  415.99  4351.9  416.67  4369.1  415.24
  4586.6  413.95  4739.0  409.90  4832.4  406.97  4878.3  404.50  4924.1  405.59
  4975.5  404.68  4990.9  403.08  4991.1  402.58  4994.9  403.08  4995.8  403.34
  5014.7  405.29  5071.5  406.85  5085.6  406.27  5131.8  408.10  5205.9  411.76
  5241.1  412.27  5255.2  413.91  5332.9  413.83  5389.7  414.93  5425.5  417.97
  5446.4  418.33  5474.8  415.45  5489.0  415.18  5545.7  419.97  5565.4  420.17
#Mann=6,-1,0
  4155.0    0.05       0  4739.0    0.12       0  4990.9    0.03       0
  4994.9    0.12       0  4995.8    0.05       0  5131.8   0.075       0
Bank Sta=4990.9,4994.9
Exp/Cntr=0.3,0.1

Type RM Length L Ch R = 1,2463,574,574,574
BEGIN DESCRIPTION:
Mapping XS 896edc48
END DESCRIPTION:
XS GIS Cut Line= 3
      2652257.12      6890690.08      2651826.17      6890102.63
      2651296.98      6889645.60
#Sta/Elev= 30
  4274.8  416.32  4360.5  416.91  4447.3  415.55  4474.7  414.05  4489.4  415.11
  4518.7  413.82  4654.5  413.37  4725.5  411.68  4740.2  412.55  4769.5  410.76
  4805.0  410.99  4870.3  408.73  4911.5  407.47  4955.5  403.62  5018.5  403.12
  5030.7  401.98  5031.0  401.48  5034.7  401.98  5047.0  403.98  5145.4  404.24
  5209.2  405.59  5366.2  409.60  5434.0  413.14  5550.5  412.98  5571.8  413.76
  5579.0  415.58  5593.2  416.73  5621.7  417.19  5656.9  413.36  5702.6  418.21
#Mann=7,-1,0
  4274.8    0.05       0  4870.3    0.12       0  5030.7    0.07       0
  5034.7    0.12       0  5145.4    0.05       0  5209.2   0.075       0
  5434.0    0.05       0
Bank Sta=5030.7,5034.7
Exp/Cntr=0.3,0.1

Type RM Length L Ch R = 1,1889,717,717,717
BEGIN DESCRIPTION:
Big Cottonwood Creek Trib 5_1 2.0
END DESCRIPTION:
XS GIS Cut Line= 3
      2652524.37      6890302.46      2652078.75      6889767.17
      2651275.53      6889255.60
#Sta/Elev= 30
  4303.5  411.03  4437.9  410.86  4466.6  411.89  4480.9  410.68  4700.9  409.72
  4829.1  406.84  4914.4  405.83  5005.7  401.60  5086.3  401.71  5091.7  399.86
  5092.0  399.36  5095.7  399.86  5109.0  400.02  5121.8  401.91  5187.7  402.05
  5200.8  403.11  5318.0  410.80  5349.8  411.61  5354.4  411.80  5375.6  416.98
  5532.7  416.24  5621.1  417.03  5643.5  415.45  5688.0  417.81  5730.3  414.39
  5745.5  417.02  5766.7  417.41  5781.9  419.07  5917.9  418.86  5952.3  419.02
#Mann=8,-1,0
  4303.5    0.05       0  4829.1    0.12       0  5091.7    0.07       0
  5095.7    0.12       0  5200.8    0.05       0  5349.8     0.1       0
  5532.7    0.05       0  5917.9     0.1       0
Bank Sta=5091.7,5095.7
Exp/Cntr=0.3,0.1

Type RM Length L Ch R = 1,1172,0,0,0
BEGIN DESCRIPTION:
Big Cottonwood Creek Trib 5_1 1.0
END DESCRIPTION:
XS GIS Cut Line= 4
      2652654.38      6890092.97      2652541.23      6889454.98
      2652270.09      6889337.48      2651273.31      6888865.54
#Sta/Elev= 30
  4063.0  409.26  4258.6  406.74  4603.3  405.76  4809.5  402.56  4901.9  398.62
  4955.4  399.24  4998.0  397.74  4998.3  397.24  5002.0  397.74  5119.4  401.60
  5217.9  404.08  5232.3  404.84  5254.4  408.62  5276.5  407.87  5291.7  403.19
  5376.1  403.20  5398.2  406.11  5420.3  411.95  5456.5  414.06  5638.5  416.09
  5684.0  418.89  5729.5  415.30  5741.2  417.49  5808.6  418.45  5848.7  415.71
  5871.5  418.06  5916.9  418.52  6029.6  418.93  6046.1  418.99  6109.3  418.19
#Mann=9,-1,0
  4063.0    0.05       0  4809.5    0.12       0  4998.0    0.07       0
  5002.0    0.12       0  5119.4    0.05       0  5808.6   0.075       0
  5916.9     0.1       0  6029.6   0.075       0  6046.1    0.05       0
Bank Sta=4998,5002
Exp/Cntr=0.3,0.1

Chan Stop Cuts=-1