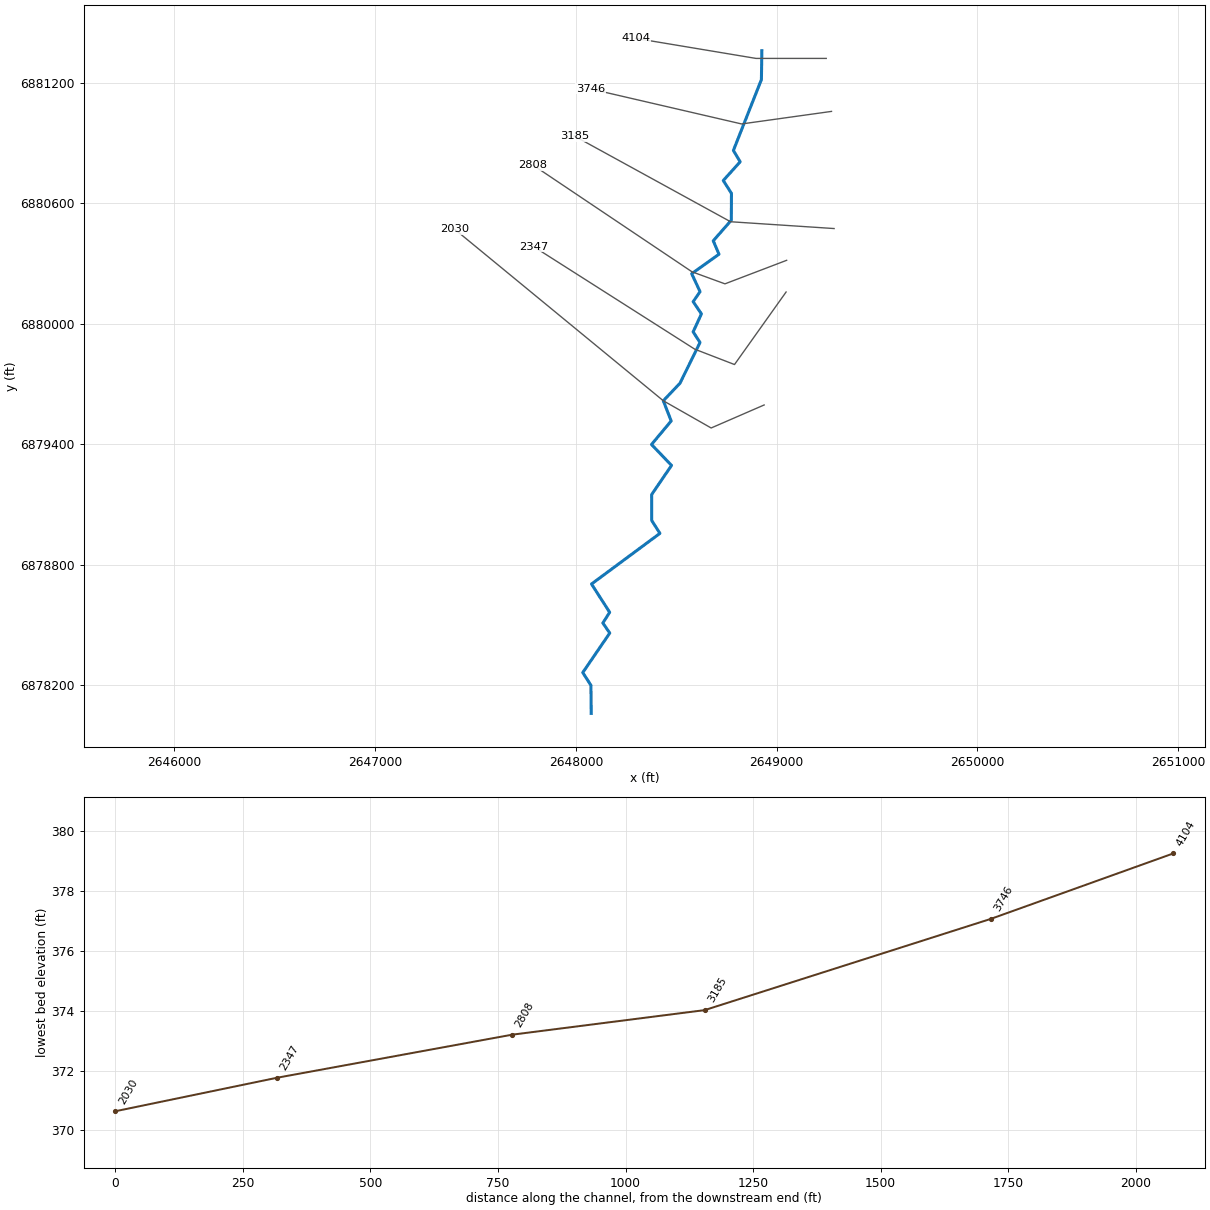
--- Big Cottonwood Creek Trib 6.prj (project) ---

Proj Title=Big Cottonwood Creek Trib 6 Base Level Engineering
Current Plan=p01
Default Exp/Contr=0.3,0.1
English Units
Geom File=g01
Flow File=f01
Plan File=p01
Y Axis Title=Elevation
X Axis Title(PF)=Main Channel Distance
X Axis Title(XS)=Station
BEGIN DESCRIPTION:
Big Cottonwood Creek Trib 6
END DESCRIPTION:
DSS Export Rating Curves= 0
DSS Export Rating Curve Sorted= 0
DSS Export Volume Flow Curves= 0
DXF OffsetX= 0
DXF OffsetY= 0
DXF ScaleX= 1
DXF ScaleY= 10

--- Big Cottonwood Creek Trib 6.p01 (plan) ---

Plan Title=Multiple Run
Short Identifier=Multiple
Geom File=g01
Flow File=f01
Subcritical Flow
K Sum by GR= 0
Std Step Tol= 0.01
Critical Tol= 0.01
Num of Std Step Trials= 20
Max Error Tol= 0.3
Flow Tol Ratio= 0.001
Split Flow NTrial= 30
Split Flow Tol= 0.02
Split Flow Ratio= 0.02
Log Output Level= 0
Friction Slope Method= 1
Unsteady Friction Slope Method= 2
Unsteady Bridges Friction Slope Method= 1
Parabolic Critical Depth
Global Vel Dist=  1 , 1 , 1
Global Log Level= 0
CheckData=True
Encroach Param= -1, 0, 0, 0
BEGIN DESCRIPTION:
Multiple Run
END DESCRIPTION:

--- Big Cottonwood Creek Trib 6.f01 (steady flow) ---

Flow Title=Multiple
Program Version=4.10
Number of Profiles= 7
Profile Names=10-year,25-year,50-year,1pct_min,100-year,1pct_plu,500-year
River Rch & RM=Big Cottonwood C,Reach-1         ,4104
     455     598     711     420     838    1671    1161
Boundary for River Rch & Prof#=Big Cottonwood C,Reach-1         , 1
Up Type= 0
Dn Type= 3
Dn Slope=0.00331
Boundary for River Rch & Prof#=Big Cottonwood C,Reach-1         , 2
Up Type= 0
Dn Type= 3
Dn Slope=0.00331
Boundary for River Rch & Prof#=Big Cottonwood C,Reach-1         , 3
Up Type= 0
Dn Type= 3
Dn Slope=0.00331
Boundary for River Rch & Prof#=Big Cottonwood C,Reach-1         , 4
Up Type= 0
Dn Type= 3
Dn Slope=0.00331
Boundary for River Rch & Prof#=Big Cottonwood C,Reach-1         , 5
Up Type= 0
Dn Type= 3
Dn Slope=0.00331
Boundary for River Rch & Prof#=Big Cottonwood C,Reach-1         , 6
Up Type= 0
Dn Type= 3
Dn Slope=0.00331
Boundary for River Rch & Prof#=Big Cottonwood C,Reach-1         , 7
Up Type= 0
Dn Type= 3
Dn Slope=0.00331
DSS Import GetInterval= 0
DSS Import GetPeak= 0
DSS Import FillOption= 0

--- Big Cottonwood Creek Trib 6.g01 (geometry) ---

Geom Title=Existing Conditions

River Reach=Big Cottonwood C,Reach-1
Reach XY= 30
      2648926.00      6881361.00      2648923.78      6881216.92
      2648784.28      6880864.22      2648817.98      6880807.66
      2648733.82      6880714.42      2648774.62      6880650.56
      2648773.93      6880516.86      2648684.02      6880414.32
      2648712.49      6880347.32      2648576.58      6880250.51
      2648618.17      6880160.92      2648583.82      6880111.08
      2648625.03      6880050.36      2648583.84      6879960.91
      2648617.99      6879907.67      2648518.10      6879704.83
      2648435.17      6879617.72      2648474.33      6879517.05
      2648376.40      6879399.98      2648476.14      6879295.76
      2648377.04      6879150.56      2648377.38      6879021.43
      2648418.31      6878957.33      2648077.51      6878705.13
      2648168.00      6878564.33      2648134.05      6878511.00
      2648168.45      6878461.00      2648034.04      6878264.32
      2648074.66      6878200.59      2648076.00      6878061.00

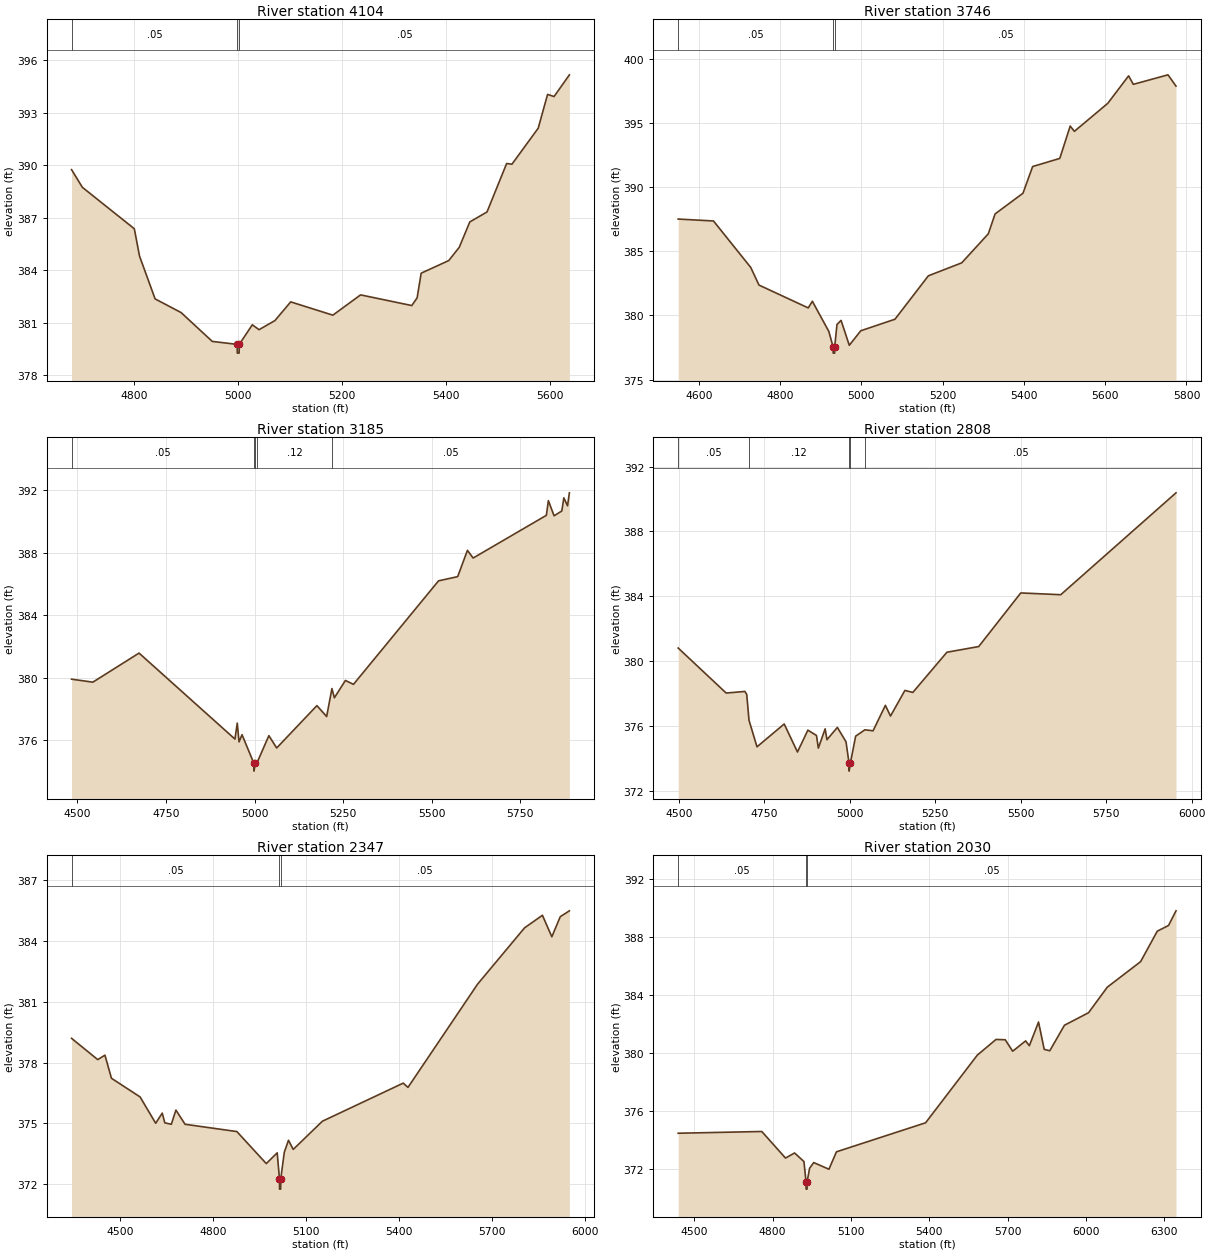
Type RM Length L Ch R = 1,4104,358,358,358
BEGIN DESCRIPTION:
Big Cottonwood Creek Trib 6 2.0
END DESCRIPTION:
XS GIS Cut Line= 3
      2649246.79      6881322.46      2648896.83      6881322.46
      2648296.86      6881422.45
#Sta/Elev= 30
  4679.3  389.75  4700.1  388.74  4800.1  386.37  4810.1  384.81  4840.1  382.36
  4890.1  381.58  4950.1  379.93  4998.1  379.76  4998.3  379.26  5001.8  379.26
  5002.1  379.76  5027.2  380.88  5040.2  380.60  5070.7  381.12  5101.1  382.19
  5182.2  381.43  5235.6  382.59  5334.2  381.98  5344.4  382.42  5352.2  383.83
  5405.2  384.55  5425.5  385.31  5445.8  386.76  5478.9  387.33  5516.7  390.10
  5526.9  390.06  5577.5  392.12  5595.5  394.05  5608.0  393.93  5637.5  395.17
#Mann=3,-1,0
  4679.3    0.05       0  4998.1    0.03       0  5002.1    0.05       0
Bank Sta=4998.1,5002.1
Exp/Cntr=0.3,0.1

Type RM Length L Ch R = 1,3746,561,561,561
BEGIN DESCRIPTION:
Mapping XS 77f8298e
END DESCRIPTION:
XS GIS Cut Line= 3
      2649272.92      6881058.60      2648825.05      6880996.11
      2648072.42      6881170.59
#Sta/Elev= 30
  4549.5  387.51  4636.4  387.36  4728.1  383.74  4748.3  382.37  4869.5  380.59
  4879.6  381.11  4920.0  378.77  4930.6  377.57  4930.9  377.07  4934.4  377.07
  4934.6  377.57  4940.2  379.30  4950.3  379.62  4970.5  377.68  4998.7  378.81
  5082.9  379.71  5165.0  383.09  5247.1  384.10  5312.5  386.36  5329.2  387.91
  5397.8  389.52  5421.6  391.60  5488.3  392.23  5514.0  394.75  5524.3  394.34
  5606.4  396.52  5657.7  398.66  5669.3  398.00  5754.6  398.74  5774.3  397.86
#Mann=3,-1,0
  4549.5    0.05       0  4930.6    0.03       0  4934.6    0.05       0
Bank Sta=4930.6,4934.6
Exp/Cntr=0.3,0.1

Type RM Length L Ch R = 1,3185,377,377,377
BEGIN DESCRIPTION:
Mapping XS 73cf8da9
END DESCRIPTION:
XS GIS Cut Line= 3
      2649285.98      6880475.27      2648770.36      6880509.13
      2647991.90      6880936.11
#Sta/Elev= 30
  4483.7  379.90  4543.8  379.71  4674.1  381.57  4944.7  376.07  4951.2  377.09
  4956.2  375.89  4964.7  376.35  4998.1  374.52  4998.4  374.02  5002.1  374.52
  5008.0  374.61  5040.4  376.29  5062.4  375.50  5175.9  378.21  5203.4  377.51
  5218.3  379.30  5225.2  378.71  5256.3  379.82  5279.1  379.57  5519.1  386.19
  5573.1  386.46  5600.6  388.14  5616.7  387.65  5823.3  390.38  5829.0  391.32
  5845.1  390.35  5866.9  390.66  5872.6  391.50  5883.0  390.99  5888.3  391.82
#Mann=5,-1,0
  4483.7    0.05       0  4998.1    0.03       0  5002.1    0.05       0
  5008.0    0.12       0  5218.3    0.05       0
Bank Sta=4998.1,5002.1
Exp/Cntr=0.3,0.1

Type RM Length L Ch R = 1,2808,461,461,461
BEGIN DESCRIPTION:
Mapping XS 853632a8
END DESCRIPTION:
XS GIS Cut Line= 4
      2649049.52      6880317.10      2648742.21      6880199.91
      2648578.15      6880259.81      2647786.52      6880791.03
#Sta/Elev= 30
  4497.4  380.80  4637.9  378.02  4692.7  378.12  4698.1  377.93  4704.7  376.34
  4728.1  374.70  4807.7  376.11  4846.5  374.38  4877.0  375.73  4902.2  375.40
  4907.6  374.62  4927.5  375.81  4932.8  375.14  4963.3  375.90  4988.6  375.01
  4997.4  373.70  4997.7  373.20  5001.4  373.70  5016.8  375.36  5043.8  375.75
  5067.8  375.69  5103.8  377.26  5118.8  376.60  5160.9  378.18  5184.2  378.06
  5283.9  380.54  5376.9  380.89  5500.0  384.20  5617.0  384.09  5954.3  390.38
#Mann=5,-1,0
  4497.4    0.05       0  4704.7    0.12       0  4997.4    0.07       0
  5001.4    0.12       0  5043.8    0.05       0
Bank Sta=4997.4,5001.4
Exp/Cntr=0.3,0.1

Type RM Length L Ch R = 1,2347,317,317,317
BEGIN DESCRIPTION:
Mapping XS 18c38730
END DESCRIPTION:
XS GIS Cut Line= 4
      2649046.72      6880159.21      2648789.79      6879798.12
      2648591.88      6879874.51      2647790.41      6880384.54
#Sta/Elev= 30
  4343.4  379.20  4427.8  378.15  4451.1  378.37  4472.0  377.23  4564.3  376.31
  4614.7  375.01  4635.8  375.51  4644.2  375.03  4665.1  374.96  4679.9  375.66
  4709.4  374.96  4876.4  374.60  4971.3  373.02  5006.5  373.55  5013.9  372.26
  5014.1  371.76  5017.6  371.76  5017.9  372.26  5029.4  373.58  5042.9  374.17
  5058.2  373.72  5152.2  375.11  5412.9  376.99  5428.2  376.78  5652.5  381.87
  5804.1  384.65  5861.7  385.27  5892.1  384.21  5919.2  385.20  5948.7  385.49
#Mann=3,-1,0
  4343.4    0.05       0  5013.9    0.03       0  5017.9    0.05       0
Bank Sta=5013.9,5017.9
Exp/Cntr=0.3,0.1

Type RM Length L Ch R = 1,2030,0,0,0
BEGIN DESCRIPTION:
Big Cottonwood Creek Trib 6 1.0
END DESCRIPTION:
XS GIS Cut Line= 4
      2648937.40      6879596.75      2648673.47      6879482.15
      2648435.17      6879617.72      2647395.89      6880471.80
#Sta/Elev= 30
  4438.1  374.49  4758.5  374.61  4849.3  372.78  4884.0  373.13  4919.9  372.54
  4928.0  371.14  4928.3  370.64  4931.8  370.64  4932.0  371.14  4941.6  372.08
  4957.4  372.47  5015.7  372.01  5044.4  373.21  5385.9  375.21  5584.0  379.87
  5655.7  380.95  5690.9  380.93  5719.5  380.14  5769.1  380.85  5783.4  380.52
  5818.6  382.15  5840.3  380.27  5861.6  380.17  5917.9  381.93  6010.1  382.79
  6081.9  384.55  6209.6  386.31  6273.5  388.41  6316.5  388.80  6345.2  389.81
#Mann=3,-1,0
  4438.1    0.05       0  4928.0    0.04       0  4932.0    0.05       0
Bank Sta=4928,4932
Exp/Cntr=0.3,0.1

Chan Stop Cuts=-1