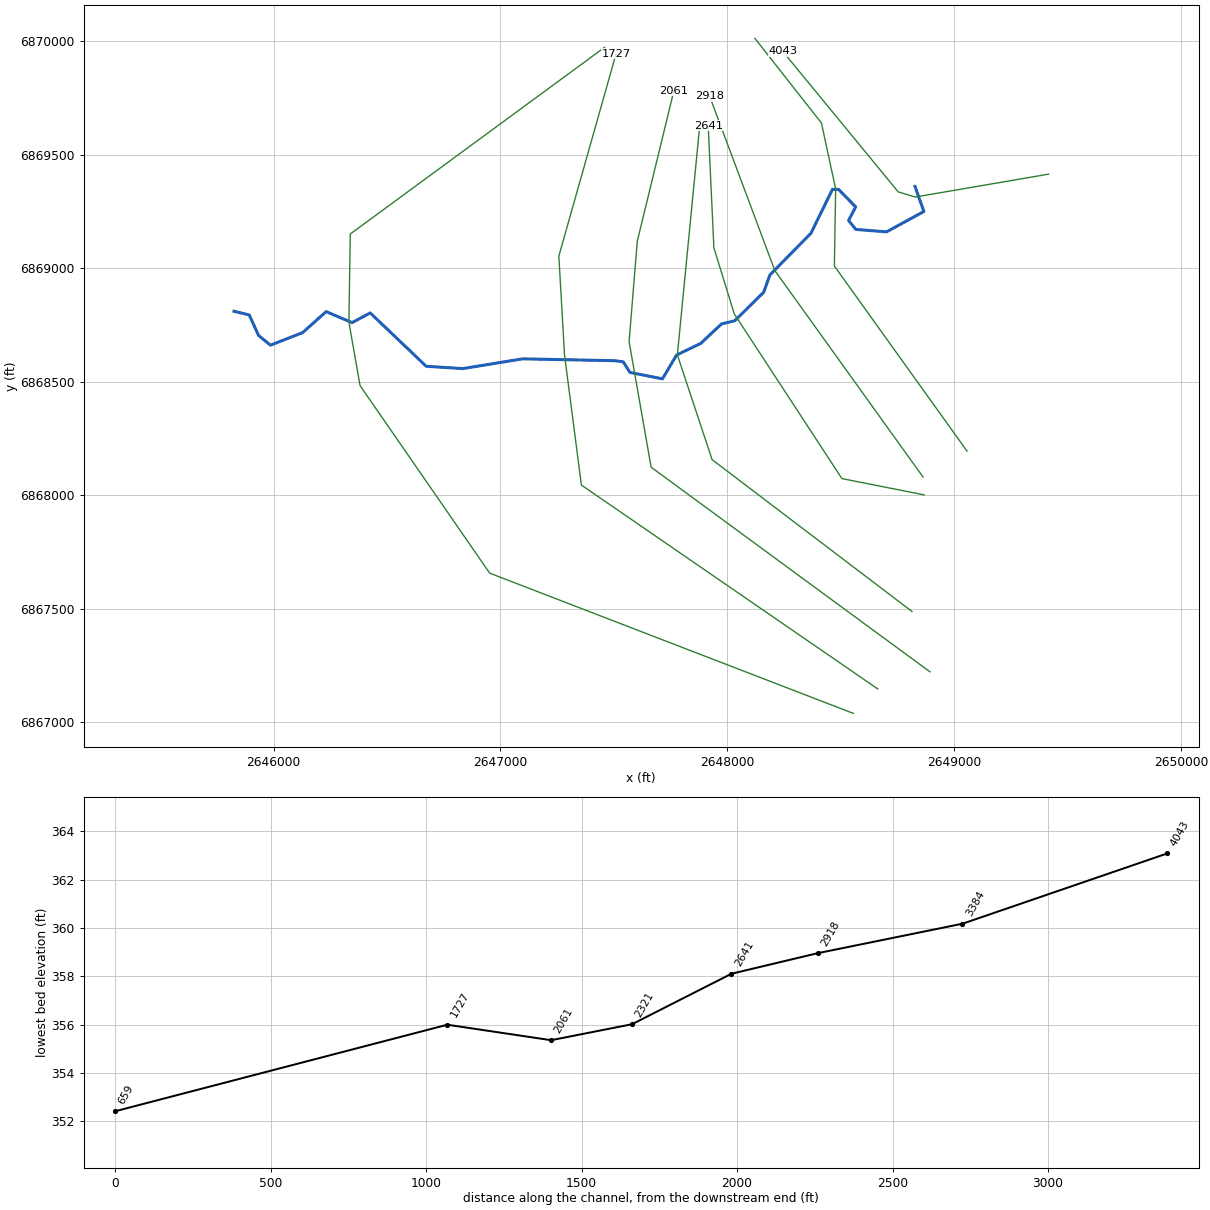
--- Big Cottonwood Creek Trib 7_1.prj (project) ---

Proj Title=Big Cottonwood Creek Trib 7_1 Base Level Engineering
Current Plan=p01
Default Exp/Contr=0.3,0.1
English Units
Geom File=g01
Flow File=f01
Plan File=p01
Y Axis Title=Elevation
X Axis Title(PF)=Main Channel Distance
X Axis Title(XS)=Station
BEGIN DESCRIPTION:
Big Cottonwood Creek Trib 7_1
END DESCRIPTION:
DSS Export Rating Curves= 0
DSS Export Rating Curve Sorted= 0
DSS Export Volume Flow Curves= 0
DXF OffsetX= 0
DXF OffsetY= 0
DXF ScaleX= 1
DXF ScaleY= 10

--- Big Cottonwood Creek Trib 7_1.p01 (plan) ---

Plan Title=Multiple Run
Short Identifier=Multiple
Geom File=g01
Flow File=f01
Subcritical Flow
K Sum by GR= 0
Std Step Tol= 0.01
Critical Tol= 0.01
Num of Std Step Trials= 20
Max Error Tol= 0.3
Flow Tol Ratio= 0.001
Split Flow NTrial= 30
Split Flow Tol= 0.02
Split Flow Ratio= 0.02
Log Output Level= 0
Friction Slope Method= 1
Unsteady Friction Slope Method= 2
Unsteady Bridges Friction Slope Method= 1
Parabolic Critical Depth
Global Vel Dist=  1 , 1 , 1
Global Log Level= 0
CheckData=True
Encroach Param= -1, 0, 0, 0
BEGIN DESCRIPTION:
Multiple Run
END DESCRIPTION:

--- Big Cottonwood Creek Trib 7_1.f01 (steady flow) ---

Flow Title=Multiple
Number of Profiles=7
Profile Names=10-year,25-year,50-year,1pct_min,100-year,1pct_plu,500-year
River Rch & RM= Big Cottonwood C,Reach-1,4043
     425     558     663     391     780    1556    1078
Boundary for River Rch & Prof#=Big Cottonwood C,Reach-1,1
Up Type=0
Dn Type=3
Dn Slope=0.005
Boundary for River Rch & Prof#=Big Cottonwood C,Reach-1,2
Up Type=0
Dn Type=3
Dn Slope=0.005
Boundary for River Rch & Prof#=Big Cottonwood C,Reach-1,3
Up Type=0
Dn Type=3
Dn Slope=0.005
Boundary for River Rch & Prof#=Big Cottonwood C,Reach-1,4
Up Type=0
Dn Type=3
Dn Slope=0.005
Boundary for River Rch & Prof#=Big Cottonwood C,Reach-1,5
Up Type=0
Dn Type=3
Dn Slope=0.005
Boundary for River Rch & Prof#=Big Cottonwood C,Reach-1,6
Up Type=0
Dn Type=3
Dn Slope=0.005
Boundary for River Rch & Prof#=Big Cottonwood C,Reach-1,7
Up Type=0
Dn Type=3
Dn Slope=0.005

--- Big Cottonwood Creek Trib 7_1.g01 (geometry) ---

Geom Title=Existing Conditions
Program Version=4.10

River Reach=Big Cottonwood C,Reach-1
Reach XY= 30
        2648826.        6869361.      2648865.15      6869250.62
      2648701.08      6869160.76      2648565.49      6869171.47
      2648533.46      6869210.76      2648564.75      6869271.04
      2648489.28      6869347.64      2648462.32      6869347.74
      2648367.86      6869154.94      2648186.78      6868970.68
      2648159.35      6868894.33      2648032.05      6868769.16
      2647973.72      6868755.13      2647882.04      6868669.14
      2647775.92       6868618.3      2647713.42      6868513.17
      2647570.36      6868541.65       2647540.5      6868588.17
      2647505.78      6868593.04      2647097.44      6868601.37
      2646833.56      6868558.31      2646672.67      6868568.59
      2646426.09      6868803.65       2646346.2      6868760.81
      2646232.04      6868809.37      2646128.29      6868716.84
      2645986.47      6868661.53      2645934.03      6868704.58
      2645893.23      6868794.64        2645826.        6868811.

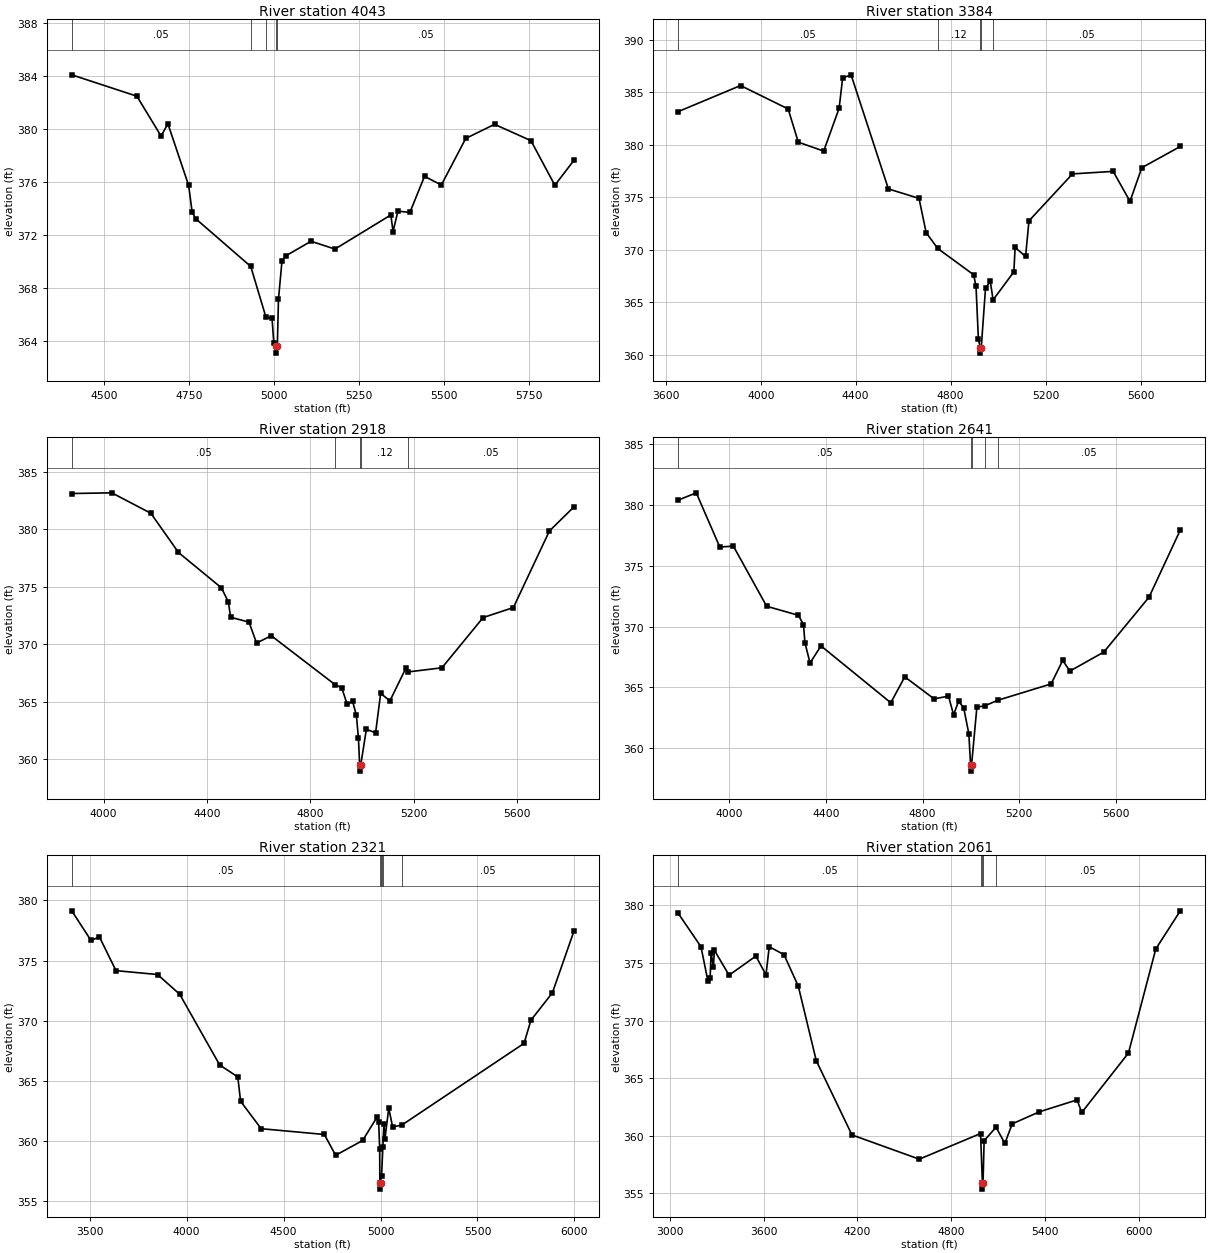
Type RM Length L Ch R = 1 ,4043    ,659,659,659
BEGIN DESCRIPTION:
Big Cottonwood Creek Trib 7_1 7.0
END DESCRIPTION:
XS GIS Cut Line= 4
      2649414.67      6869415.03      2648827.31      6869314.22
       2648752.3       6869336.6      2648243.16      6869956.35
#Sta/Elev= 30
    4406  384.06  4597.4  382.45  4668.5  379.45  4688.7  380.37  4749.6  375.73
  4759.9  373.73  4769.9  373.23  4932.3  369.62    4977  365.79  4994.8  365.73
  5000.1  363.86  5006.4  363.59  5006.6  363.09  5010.4  363.59  5013.8  367.16
  5024.2  370.05  5034.6  370.41  5109.6  371.52  5179.9  370.93  5344.2   373.5
  5350.7  372.25    5365  373.79  5400.2  373.69  5443.2  376.41  5492.7  375.76
  5564.5  379.27  5649.2  380.33  5756.1   379.1  5826.4  375.74  5882.3  377.61
#Mann= 5 ,-1 , 0
    4406     .05       0  4932.3     .12       0    4977     .05       0
  5006.4     .03       0  5010.4     .05       0
Bank Sta=5006.4,5010.4
XS Rating Curve= 0 ,0
Exp/Cntr=0.3,0.1

Type RM Length L Ch R = 1 ,3384    ,466,466,466
BEGIN DESCRIPTION:
Mapping XS 44f55874
END DESCRIPTION:
XS GIS Cut Line= 5
      2649055.42      6868194.69      2648470.91      6869010.16
      2648476.62      6869349.45      2648413.89      6869640.28
      2648120.59      6870013.31
#Sta/Elev= 30
  3652.7  383.17  3915.2  385.65  4115.7  383.42  4158.4  380.26  4265.3  379.41
  4330.4  383.49  4345.1  386.37  4380.7  386.67  4537.9  375.81  4666.9  374.91
  4696.9  371.65  4745.7  370.14  4896.9  367.64  4906.9  366.55  4916.9  361.52
  4924.9  360.68  4925.1  360.18  4928.9  360.68  4946.9  366.35  4966.9  367.02
  4978.9  365.25  5066.4  367.92  5071.5  370.24  5115.7  369.38  5129.9  372.77
  5313.3  377.24  5484.6  377.48  5555.5  374.63  5605.2  377.83  5767.4  379.85
#Mann= 5 ,-1 , 0
  3652.7     .05       0  4745.7     .12       0  4924.9     .04       0
  4928.9     .12       0  4978.9     .05       0
Bank Sta=4924.9,4928.9
XS Rating Curve= 0 ,0
Exp/Cntr=0.3,0.1

Type RM Length L Ch R = 1 ,2918    ,277,277,277
BEGIN DESCRIPTION:
Mapping XS 789164ef
END DESCRIPTION:
XS GIS Cut Line= 3
      2648861.54      6868080.64       2648208.6       6868990.2
      2647920.83      6869759.48
#Sta/Elev= 30
  3877.3  383.11  4032.1  383.17  4183.1  381.39  4289.9  377.98  4455.7  374.91
  4482.7  373.68  4491.3  372.35  4562.5  371.92  4591.7   370.1  4648.5  370.74
  4895.3  366.48  4921.1  366.21    4942  364.77  4962.9  365.04  4977.6  363.81
  4985.6  361.81  4990.3  359.46  4990.6  358.96  4994.3  359.46  5016.2   362.6
  5051.9  362.29  5071.5  365.73  5107.1  365.07  5168.6   367.9  5177.7  367.59
  5308.4  367.95  5467.6  372.32  5584.6  373.19  5723.8  379.85  5818.3  381.94
#Mann= 5 ,-1 , 0
  3877.3     .05       0  4895.3     .12       0  4990.3     .07       0
  4994.3     .12       0  5177.7     .05       0
Bank Sta=4990.3,4994.3
XS Rating Curve= 0 ,0
Exp/Cntr=0.3,0.1

Type RM Length L Ch R = 1 ,2641    ,320,320,320
BEGIN DESCRIPTION:
Mapping XS 099ab3b1
END DESCRIPTION:
XS GIS Cut Line= 5
      2648866.72        6868002.      2648504.02      6868073.82
      2648029.93      6868799.32      2647940.14      6869090.24
      2647915.07      6869627.48
#Sta/Elev= 30
  3788.5  380.42  3863.1  381.02  3960.5  376.56  4016.8  376.63  4154.7  371.68
    4286  370.94  4307.1  370.17  4313.1  368.68  4334.2  367.01  4379.5  368.42
  4668.5  363.74  4726.4  365.87  4847.7  364.06  4907.4  364.28  4928.5  362.75
  4949.6  363.88  4970.6  363.29  4991.7  361.18  4998.9  358.61  4999.1  358.11
  5002.9  358.61  5024.9  363.37  5059.6   363.5    5111  363.94  5332.3  365.29
  5380.2  367.22  5410.2  366.35  5550.4  367.91  5737.7  372.43  5867.2  377.96
#Mann= 5 ,-1 , 0
  3788.5     .05       0  4998.9     .05       0  5002.9     .05       0
  5059.6     .12       0    5111     .05       0
Bank Sta=4998.9,5002.9
XS Rating Curve= 0 ,0
Exp/Cntr=0.3,0.1

Type RM Length L Ch R = 1 ,2321    ,260,260,260
BEGIN DESCRIPTION:
Big Cottonwood Creek Trib 7_1 4.0
END DESCRIPTION:
XS GIS Cut Line= 4
      2648812.93      6867488.37      2647932.15      6868157.36
      2647779.23      6868618.84        2647876.      6869611.04
#Sta/Elev= 30
  3407.8  379.14  3506.9  376.68  3550.5  376.97  3635.8  374.17    3850  373.85
  3964.4  372.21  4170.3  366.34  4263.9  365.34  4278.4  363.32  4384.5  361.04
  4710.4  360.56  4768.5  358.83  4907.5  360.06  4981.2  361.98  4990.4  361.56
  4995.7  359.34  4996.5  356.52  4996.8  356.02  5000.5  356.52  5005.3  357.12
  5012.1  359.53  5017.7  361.47  5022.7   360.2  5042.4  362.74  5062.5  361.18
  5110.7  361.35    5740  368.13  5775.8  370.06  5886.3  372.33  5996.9  377.43
#Mann= 6 ,-1 , 0
  3407.8     .05       0  4996.5     .07       0  5000.5     .05       0
  5005.3     .05       0  5012.1     .12       0  5110.7     .05       0
Bank Sta=4996.5,5000.5
XS Rating Curve= 0 ,0
Exp/Cntr=0.3,0.1

Type RM Length L Ch R = 1 ,2061    ,334,334,334
BEGIN DESCRIPTION:
Mapping XS 248c5520
END DESCRIPTION:
XS GIS Cut Line= 5
      2648891.91      6867222.62      2647663.58      6868124.11
      2647566.61      6868677.21      2647602.53      6869118.97
      2647764.15       6869783.4
#Sta/Elev= 30
  3053.4  379.31  3198.9  376.41  3242.8  373.46  3257.5   373.7  3263.7  375.91
  3278.3  374.62  3284.5  376.11  3378.6  373.94    3550   375.6  3614.8  373.97
  3635.6  376.41  3729.8  375.73  3821.6  372.98  3936.6  366.51  4164.7  360.07
  4595.6  357.96  4987.6  360.19  4999.4  355.86  4999.6  355.36  5003.4  355.86
  5010.4  359.56  5086.6  360.74    5143  359.33  5190.1  361.03  5363.1  362.07
  5604.5  363.11  5635.3  362.02  5933.8  367.18  6108.8  376.22  6265.6  379.53
#Mann= 5 ,-1 , 0
  3053.4     .05       0  4987.6     .12       0  4999.4     .07       0
  5003.4     .12       0  5086.6     .05       0
Bank Sta=4999.4,5003.4
XS Rating Curve= 0 ,0
Exp/Cntr=0.3,0.1

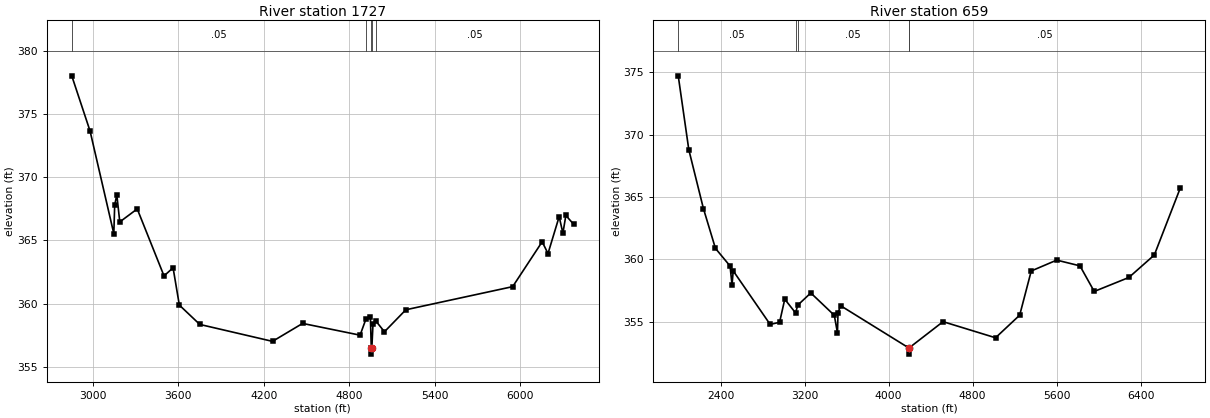
Type RM Length L Ch R = 1 ,1727    ,1068,1068,1068
BEGIN DESCRIPTION:
Mapping XS f496e3ce
END DESCRIPTION:
XS GIS Cut Line= 5
      2648662.03       6867147.2      2647356.38      6868045.31
      2647281.95      6868619.54       2647257.1      6869054.29
      2647509.14      6869945.01
#Sta/Elev= 30
  2851.3  378.02    2980  373.64  3146.5  365.53  3152.6  367.79  3167.5  368.61
  3188.4  366.46  3310.9  367.49  3498.9  362.19  3562.6  362.83  3606.5  359.88
  3749.9  358.35  4260.6  357.01    4472  358.43  4875.4   357.5    4916  358.76
  4947.8  358.94    4954   356.5  4954.3     356    4958   356.5  4966.1  358.38
  4986.8  358.61  5046.6  357.77  5196.8  359.51  5946.7  361.34  6153.8  364.89
  6194.8  363.96  6273.1  366.88  6299.3  365.57  6320.1  366.97  6376.2  366.26
#Mann= 5 ,-1 , 0
  2851.3     .05       0    4916     .12       0    4954     .04       0
    4958     .12       0  4986.8     .05       0
Bank Sta=4954,4958
XS Rating Curve= 0 ,0
Exp/Cntr=0.3,0.1

Type RM Length L Ch R = 1 ,659     ,0,0,0
BEGIN DESCRIPTION:
Mapping XS 8804f834
END DESCRIPTION:
XS GIS Cut Line= 6
      2648554.29      6867039.45      2646952.45       6867657.2
      2646381.39      6868483.26      2646332.12      6868762.89
      2646338.29       6869151.3      2647458.88      6869973.78
#Sta/Elev= 30
    1995  374.71  2095.8  368.79  2234.9  364.08  2349.5  360.89  2488.6  359.48
  2507.6  357.97  2518.6  359.09  2870.7   354.8  2960.6  354.97  3009.9  356.82
  3112.9  355.72  3133.6  356.34  3257.9  357.32  3481.9  355.53  3511.9  354.12
  3517.2  355.73  3541.8   356.3  4190.9  352.92  4191.2  352.42  4194.9  352.92
    4518  355.02  5018.1  353.73  5248.1  355.54  5358.2  359.08    5601  359.95
  5822.4  359.49  5958.3  357.44  6288.5  358.56  6530.9  360.36  6778.5  365.73
#Mann= 5 ,-1 , 0
    1995     .05       0  3112.9     .12       0  3133.6     .05       0
  4190.9     .04       0  4194.9     .05       0
Bank Sta=4190.9,4194.9
XS Rating Curve= 0 ,0
Exp/Cntr=0.3,0.1

Chan Stop Cuts=-1
Use User Specified Reach Order=0
Composite Channel Slope=5