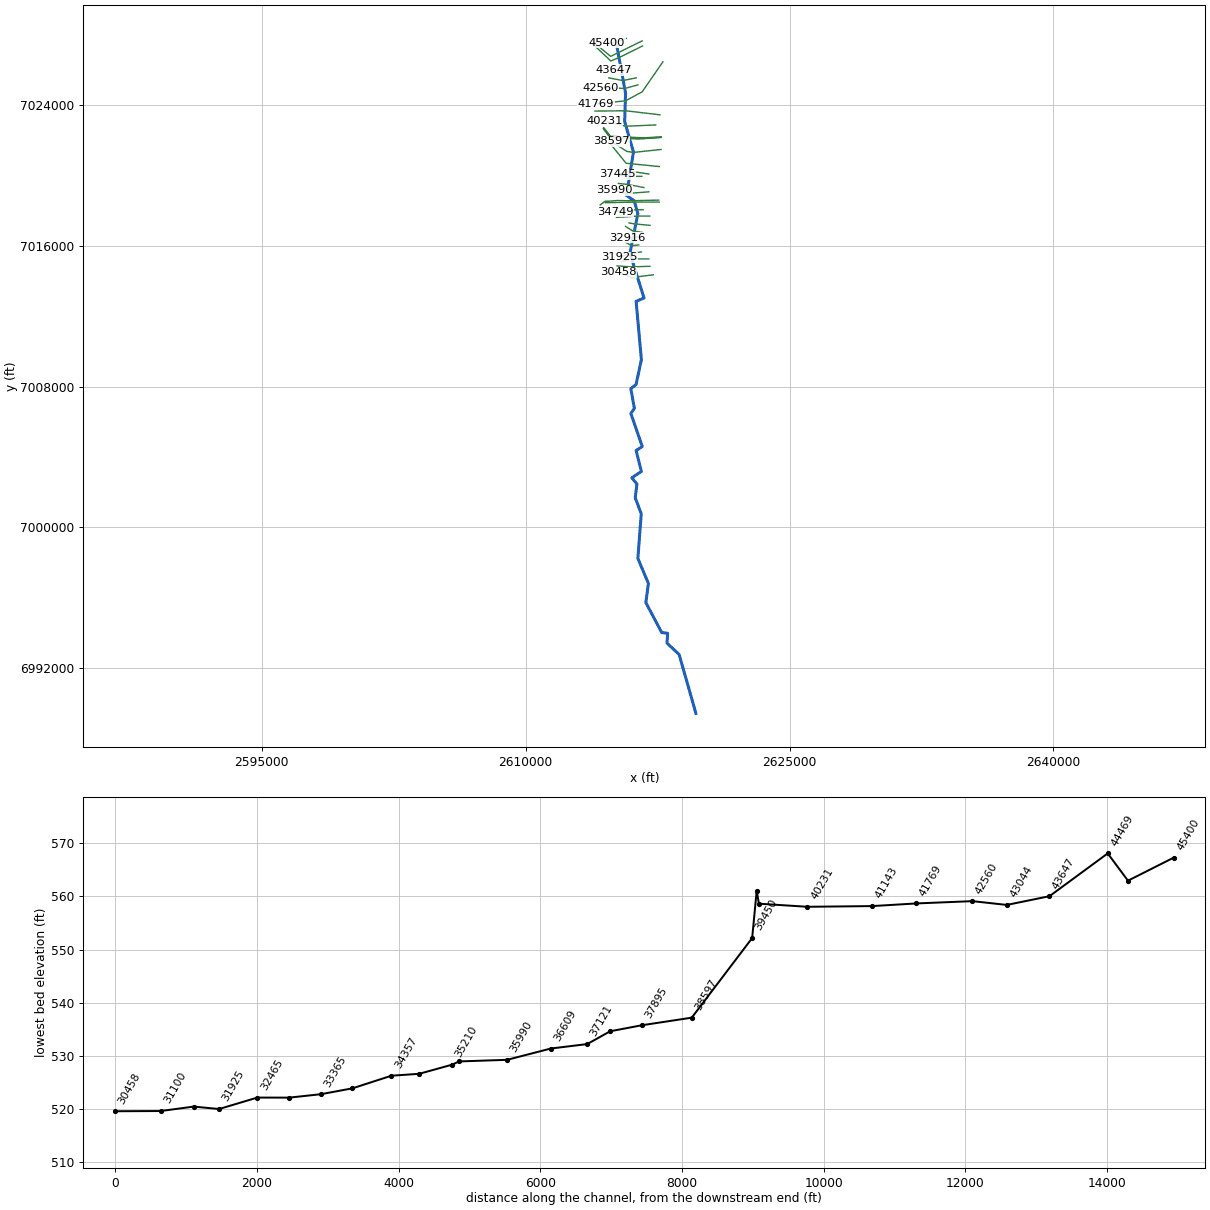
--- Brushy Creek.prj (project) ---

Proj Title=Brushy Creek Base Level Engineering
Current Plan=p01
Default Exp/Contr=0.3,0.1
English Units
Geom File=g01
Flow File=f01
Plan File=p01
Y Axis Title=Elevation
X Axis Title(PF)=Main Channel Distance
X Axis Title(XS)=Station
BEGIN DESCRIPTION:
Brushy Creek
END DESCRIPTION:
DSS Export Rating Curves= 0
DSS Export Rating Curve Sorted= 0
DSS Export Volume Flow Curves= 0
DXF OffsetX= 0
DXF OffsetY= 0
DXF ScaleX= 1
DXF ScaleY= 10

--- Brushy Creek.p01 (plan) ---

Plan Title=Multiple Run
Short Identifier=Multiple
Geom File=g01
Flow File=f01
Subcritical Flow
K Sum by GR= 0
Std Step Tol= 0.01
Critical Tol= 0.01
Num of Std Step Trials= 20
Max Error Tol= 0.3
Flow Tol Ratio= 0.001
Split Flow NTrial= 30
Split Flow Tol= 0.02
Split Flow Ratio= 0.02
Log Output Level= 0
Friction Slope Method= 1
Unsteady Friction Slope Method= 2
Unsteady Bridges Friction Slope Method= 1
Parabolic Critical Depth
Global Vel Dist=  1 , 1 , 1
Global Log Level= 0
CheckData=True
Encroach Param= -1, 0, 0, 0
BEGIN DESCRIPTION:
Multiple Run
END DESCRIPTION:

--- Brushy Creek.f01 (steady flow) ---

Flow Title=Multiple
Program Version=4.10
Number of Profiles= 7
Profile Names=10-year,25-year,50-year,1pct_min,100-year,1pct_plu,500-year
River Rch & RM=Brushy Creek,Reach-1         ,45400
     435     573     682     404     805    1607    1120
River Rch & RM=Brushy Creek,Reach-1         ,44755
     445     586     698     413     824    1644    1147
River Rch & RM=Brushy Creek,Reach-1         ,43647
     484     640     764     453     904    1804    1264
River Rch & RM=Brushy Creek,Reach-1         ,43044
     832    1136    1385     836    1669    3329    2423
River Rch & RM=Brushy Creek,Reach-1         ,37895
     911    1249    1528     925    1845    3682    2694
River Rch & RM=Brushy Creek,Reach-1         ,37121
    1176    1632    2012    1227    2449    4886    3630
River Rch & RM=Brushy Creek,Reach-1         ,35313
    1419    1987    2465    1512    3016    6018    4519
River Rch & RM=Brushy Creek,Reach-1         ,33365
    1697    2391    2977    1830    3652    7287    5505
River Rch & RM=Brushy Creek,Reach-1         ,29692
    1730    2435    3030    1862    3715    7413    5593
River Rch & RM=Brushy Creek,Reach-1         ,26001
    1880    2656    3313    2040    4071    8123    6154
River Rch & RM=Brushy Creek,Reach-1         ,25399
    1896    2675    3333    2050    4091    8163    6170
River Rch & RM=Brushy Creek,Reach-1         ,22350
    2010    2841    3544    2182    4354    8687    6579
River Rch & RM=Brushy Creek,Reach-1         ,20091
    2075    2934    3662    2255    4499    8976    6800
River Rch & RM=Brushy Creek,Reach-1         ,17292
    2086    2948    3677    2263    4515    9009    6817
River Rch & RM=Brushy Creek,Reach-1         ,15943
    2087    2949    3678    2263    4515    9009    6815
River Rch & RM=Brushy Creek,Reach-1         ,14964
    2176    3068    3822    2349    4687    9351    7055
River Rch & RM=Brushy Creek,Reach-1         ,12307
    2306    3257    4062    2499    4986    9948    7519
River Rch & RM=Brushy Creek,Reach-1         ,10209
    2329    3288    4099    2521    5030   10035    7578
River Rch & RM=Brushy Creek,Reach-1         ,6950
    2531    3585    4478    2759    5505   10983    8325
River Rch & RM=Brushy Creek,Reach-1         ,4253
    2522    3569    4455    2743    5473   10919    8265
River Rch & RM=Brushy Creek,Reach-1         ,2369
    2526    3571    4456    2741    5470   10914    8250
River Rch & RM=Brushy Creek,Reach-1         ,1
    4186    6024    7608    4733    9443   18841   14555
Boundary for River Rch & Prof#=Brushy Creek,Reach-1         , 1
Up Type= 0
Dn Type= 1
Dn Known WS=481.79
Boundary for River Rch & Prof#=Brushy Creek,Reach-1         , 2
Up Type= 0
Dn Type= 1
Dn Known WS=482.22
Boundary for River Rch & Prof#=Brushy Creek,Reach-1         , 3
Up Type= 0
Dn Type= 1
Dn Known WS=482.69
Boundary for River Rch & Prof#=Brushy Creek,Reach-1         , 4
Up Type= 0
Dn Type= 1
Dn Known WS=481.84
Boundary for River Rch & Prof#=Brushy Creek,Reach-1         , 5
Up Type= 0
Dn Type= 1
Dn Known WS=483.04
Boundary for River Rch & Prof#=Brushy Creek,Reach-1         , 6
Up Type= 0
Dn Type= 1
Dn Known WS=484.49
Boundary for River Rch & Prof#=Brushy Creek,Reach-1         , 7
Up Type= 0
Dn Type= 1
Dn Known WS=483.88
DSS Import GetInterval= 0
DSS Import GetPeak= 0
DSS Import FillOption= 0

--- Brushy Creek.g01 (geometry) ---

Geom Title=Existing Conditions

River Reach=Brushy Creek,Reach-1
Reach XY= 30
      2615126.00      7027661.00      2615675.75      7024695.78
      2615627.22      7023071.50      2616125.93      7021340.97
      2615726.38      7018876.15      2616167.91      7018567.08
      2616375.94      7017840.97      2615926.10      7015579.19
      2616726.51      7013040.76      2616276.98      7012850.72
      2616576.04      7009530.98      2616272.28      7008112.52
      2615975.43      7007881.43      2616177.18      7006761.00
      2615976.94      7006471.49      2616626.47      7004590.53
      2616276.00      7004361.00      2616574.50      7003172.86
      2616033.07      7002811.00      2616323.98      7002455.16
      2616226.52      7001676.22      2616568.72      7000761.06
      2616376.36      6998226.27      2616975.40      6996800.38
      2616829.75      6995712.55      2617733.68      6994004.47
      2618067.22      6993967.86      2618033.69      6993404.52
      2618722.46      6992759.54      2619674.45      6989409.52

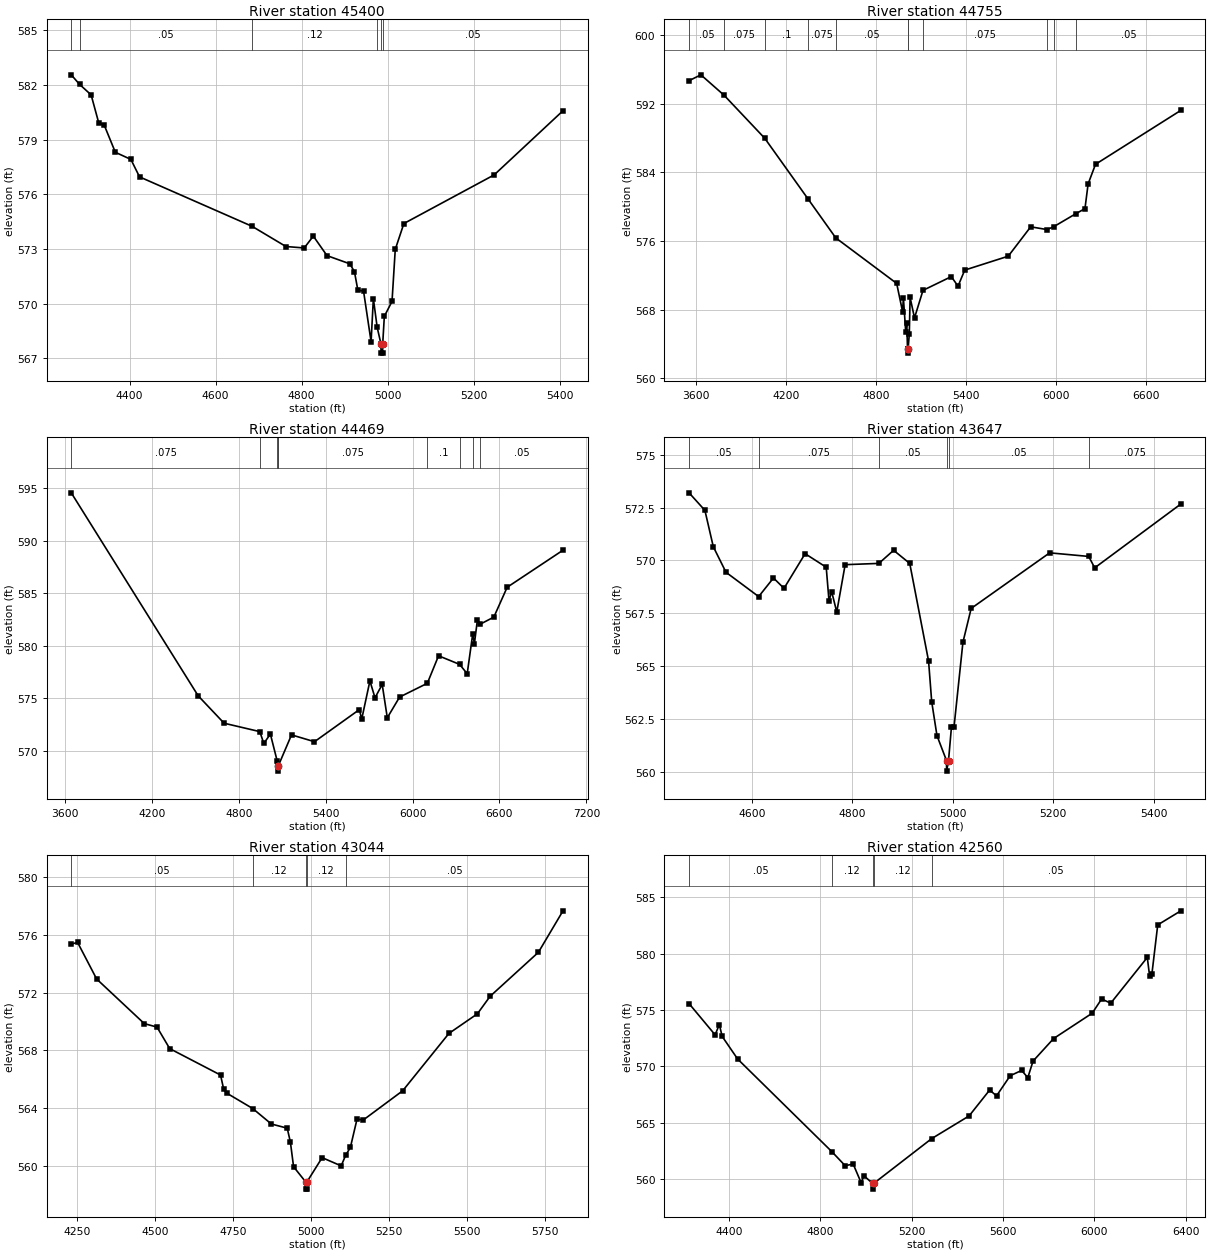
Type RM Length L Ch R = 1,45400,645,645,645
BEGIN DESCRIPTION:
Brushy Creek 83.0
END DESCRIPTION:
XS GIS Cut Line= 3
      2615726.01      7027811.00      2615026.00      7027561.00
      2614626.01      7027561.00
#Sta/Elev= 30
  4264.5  582.55  4283.7  582.03  4310.7  581.45  4328.2  579.93  4341.5  579.77
  4367.0  578.30  4403.1  577.91  4423.3  576.95  4684.8  574.24  4763.6  573.13
  4806.1  573.05  4827.3  573.70  4859.1  572.63  4912.2  572.18  4922.9  571.75
  4930.8  570.74  4944.1  570.68  4961.6  567.91  4966.9  570.27  4975.8  568.69
  4984.6  567.78  4984.8  567.28  4988.3  567.28  4988.6  567.78  4992.4  569.30
  5010.3  570.12  5017.8  572.97  5037.8  574.39  5247.8  577.06  5407.8  580.58
#Mann=6,-1,0
  4264.5   0.075       0  4283.7    0.05       0  4684.8    0.12       0
  4975.8    0.05       0  4984.6   0.035       0  4988.6    0.05       0
Bank Sta=4984.6,4988.6
Exp/Cntr=0.3,0.1

Type RM Length L Ch R = 1,44755,286,286,286
BEGIN DESCRIPTION:
Mapping XS aa2c021b
END DESCRIPTION:
XS GIS Cut Line= 4
      2616624.03      7027669.64      2615326.31      7027027.29
      2614833.02      7026783.14      2613844.72      7027600.80
#Sta/Elev= 30
  3551.8  594.68  3630.5  595.36  3785.5  592.98  4056.7  587.97  4344.5  580.93
  4530.6  576.37  4936.9  571.07  4976.2  567.79  4981.8  569.37  4997.2  565.46
  5004.2  566.45  5009.3  563.45  5009.6  562.95  5013.3  563.45  5021.1  565.14
  5026.6  569.43  5055.9  567.05  5112.5  570.26  5301.4  571.86  5346.2  570.75
  5391.1  572.62  5681.4  574.24  5831.2  577.66  5939.7  577.34  5983.6  577.66
  6132.7  579.19  6193.3  579.78  6214.2  582.65  6263.6  584.94  6832.9  591.22
#Mann=11,-1,0
  3551.8    0.05       0  3785.5   0.075       0  4056.7     0.1       0
  4344.5   0.075       0  4530.6    0.05       0  5009.3    0.05       0
  5013.3    0.05       0  5112.5   0.075       0  5939.7     0.1       0
  5983.6   0.075       0  6132.7    0.05       0
Bank Sta=5009.3,5013.3
Exp/Cntr=0.3,0.1

Type RM Length L Ch R = 1,44469,822,822,822
BEGIN DESCRIPTION:
Mapping XS 585e30a4
END DESCRIPTION:
XS GIS Cut Line= 4
      2616641.39      7027378.84      2615421.80      7026771.21
      2614838.09      7026521.31      2613822.47      7027482.67
#Sta/Elev= 30
  3642.6  594.57  4519.0  575.25  4698.1  572.64  4945.0  571.84  4972.3  570.71
  5017.7  571.61  5064.1  569.08  5068.3  568.58  5068.5  568.08  5072.3  568.58
  5163.8  571.53  5322.4  570.88  5632.6  573.94  5648.4  573.02  5705.1  576.67
  5740.3  575.06  5790.0  576.33  5825.2  573.16  5910.2  575.13  6101.7  576.44
  6179.2  579.06  6324.7  578.24  6377.0  577.35  6415.0  581.13  6426.7  580.22
  6447.8  582.49  6464.3  582.05  6561.0  582.74  6652.9  585.58  7038.6  589.11
#Mann=9,-1,0
  3642.6   0.075       0  4945.0    0.05       0  5064.1   0.075       0
  5068.3    0.05       0  5072.3   0.075       0  6101.7     0.1       0
  6324.7   0.075       0  6415.0     0.1       0  6464.3    0.05       0
Bank Sta=5068.3,5072.3
Exp/Cntr=0.3,0.1

Type RM Length L Ch R = 1,43647,603,603,603
BEGIN DESCRIPTION:
Brushy Creek 79.0
END DESCRIPTION:
XS GIS Cut Line= 3
      2615926.01      7026111.00      2615425.99      7025950.99
      2614975.97      7026011.00
#Sta/Elev= 30
  4475.0  573.20  4506.5  572.37  4523.2  570.65  4548.5  569.44  4613.5  568.29
  4643.0  569.17  4664.0  568.68  4706.0  570.32  4748.0  569.68  4753.6  568.08
  4758.8  568.53  4769.0  567.56  4785.7  569.80  4852.8  569.86  4882.2  570.48
  4914.3  569.86  4951.8  565.24  4958.0  563.32  4968.5  561.71  4987.5  560.53
  4987.7  560.03  4991.5  560.53  4997.4  562.13  5002.5  562.13  5020.2  566.13
  5036.6  567.73  5192.9  570.36  5270.6  570.19  5282.5  569.65  5454.0  572.67
#Mann=6,-1,0
  4475.0    0.05       0  4613.5   0.075       0  4852.8    0.05       0
  4987.5    0.03       0  4991.5    0.05       0  5270.6   0.075       0
Bank Sta=4987.5,4991.5
Exp/Cntr=0.3,0.1

Type RM Length L Ch R = 1,43044,484,484,484
BEGIN DESCRIPTION:
Brushy Creek 78.0
END DESCRIPTION:
XS GIS Cut Line= 3
      2616275.96      7025560.99      2615526.00      7025411.00
      2614725.95      7025561.01
#Sta/Elev= 30
  4230.1  575.36  4250.5  575.47  4311.6  572.94  4464.6  569.85  4505.4  569.61
  4546.2  568.12  4709.4  566.29  4719.6  565.30  4729.8  565.03  4812.8  563.97
  4872.5  562.90  4923.5  562.61  4933.7  561.64  4943.9  559.94  4982.7  558.89
  4983.0  558.39  4986.5  558.39  4986.8  558.89  5035.6  560.57  5096.7  560.00
  5111.0  560.73  5126.3  561.28  5147.5  563.23  5167.9  563.18  5294.2  565.20
  5442.6  569.17  5534.1  570.53  5574.8  571.74  5730.0  574.79  5808.9  577.66
#Mann=5,-1,0
  4230.1    0.05       0  4812.8    0.12       0  4982.7    0.07       0
  4986.8    0.12       0  5111.0    0.05       0
Bank Sta=4982.7,4986.8
Exp/Cntr=0.3,0.1

Type RM Length L Ch R = 1,42560,791,791,791
BEGIN DESCRIPTION:
Brushy Creek 77.0
END DESCRIPTION:
XS GIS Cut Line= 3
      2616376.01      7025161.00      2615626.00      7024961.00
      2614249.18      7025009.54
#Sta/Elev= 30
  4224.6  575.57  4338.5  572.80  4357.2  573.71  4369.5  572.66  4437.4  570.65
  4850.3  562.42  4908.3  561.18  4943.3  561.33  4978.2  559.67  4990.5  560.29
  5028.8  559.60  5029.1  559.10  5032.9  559.60  5286.9  563.58  5451.1  565.60
  5541.2  567.90  5571.2  567.38  5631.2  569.17  5681.2  569.64  5708.3  569.00
  5731.3  570.47  5821.3  572.47  5990.3  574.72  6031.5  575.98  6071.5  575.61
  6231.6  579.67  6241.6  578.05  6251.6  578.17  6277.3  582.56  6378.5  583.81
#Mann=5,-1,0
  4224.6    0.05       0  4850.3    0.12       0  5028.8    0.07       0
  5032.9    0.12       0  5286.9    0.05       0
Bank Sta=5028.8,5032.9
Exp/Cntr=0.3,0.1

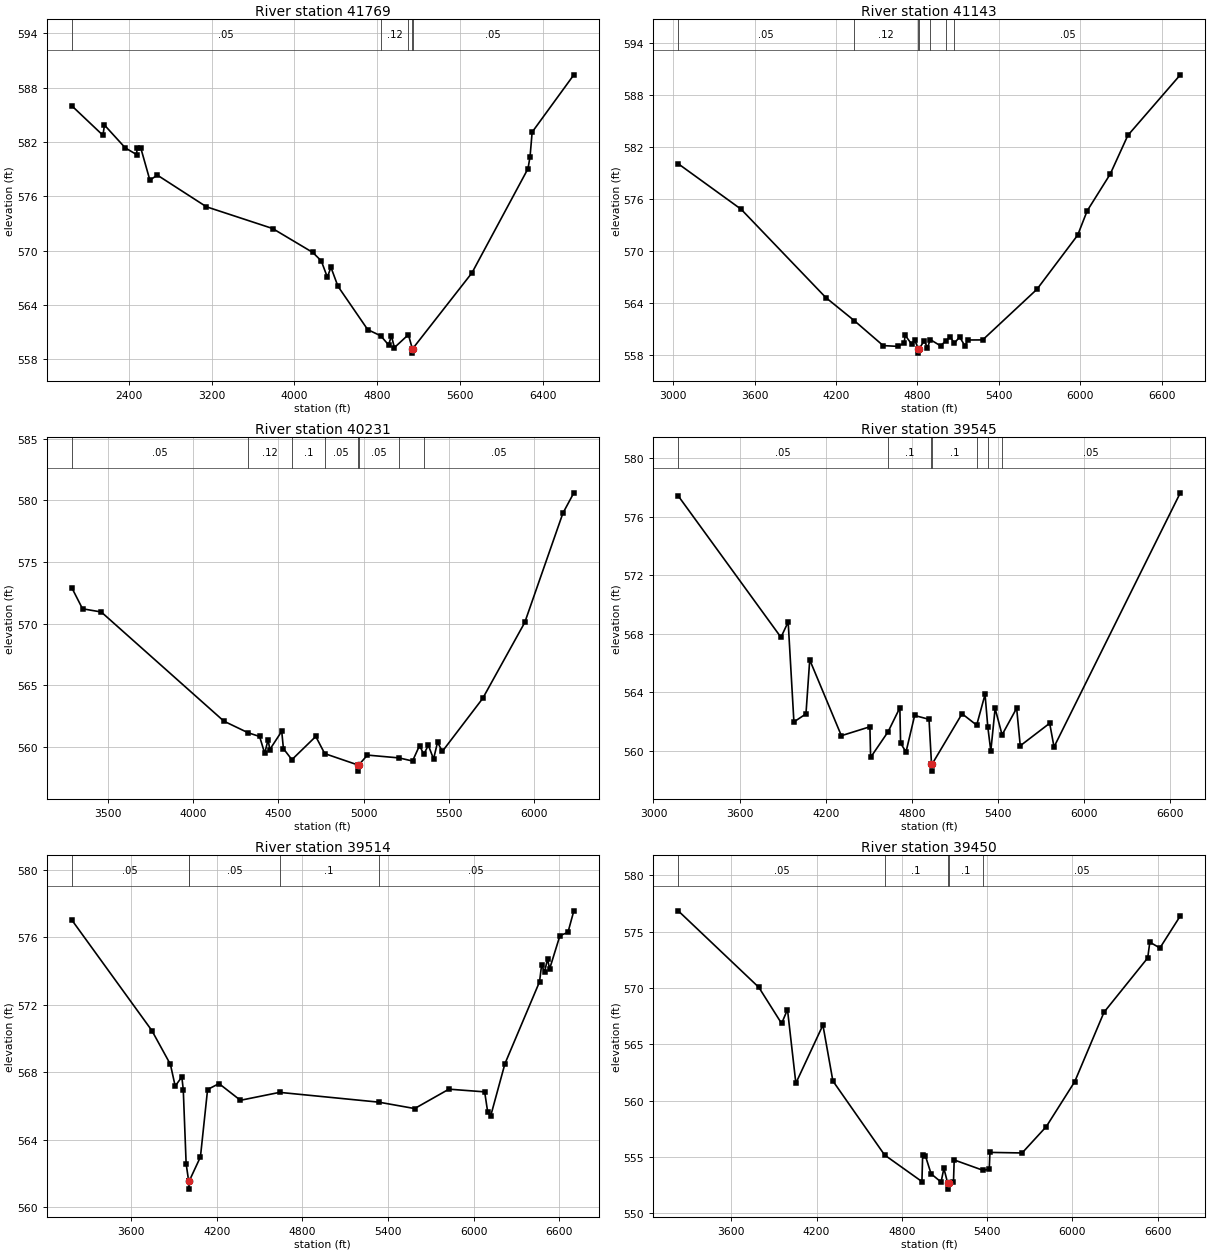
Type RM Length L Ch R = 1,41769,626,626,626
BEGIN DESCRIPTION:
Brushy Creek 75.0
END DESCRIPTION:
XS GIS Cut Line= 4
      2617800.25      7026476.04      2616619.71      7024766.00
      2615676.09      7024255.96      2613985.12      7024088.92
#Sta/Elev= 30
  1849.4  586.00  2150.3  582.74  2165.2  583.87  2365.9  581.35  2475.3  580.61
  2481.5  581.38  2517.4  581.28  2603.9  577.78  2675.6  578.34  3150.1  574.84
  3789.0  572.44  4177.9  569.79  4259.7  568.86  4318.1  567.06  4352.9  568.15
  4420.4  566.06  4707.9  561.27  4834.2  560.58  4909.2  559.58  4937.2  560.56
  4966.0  559.28  5101.0  560.71  5138.6  559.17  5139.0  558.67  5142.9  559.17
  5715.1  567.54  6256.2  579.05  6276.3  580.39  6296.4  583.09  6699.2  589.42
#Mann=5,-1,0
  1849.4    0.05       0  4834.2    0.12       0  5101.0    0.05       0
  5138.6    0.07       0  5142.9    0.05       0
Bank Sta=5138.6,5142.9
Exp/Cntr=0.3,0.1

Type RM Length L Ch R = 1,41143,912,912,912
BEGIN DESCRIPTION:
Brushy Creek 73.0
END DESCRIPTION:
XS GIS Cut Line= 3
      2617626.02      7023461.00      2615676.33      7023690.87
      2613939.62      7023672.82
#Sta/Elev= 30
  3036.8  580.08  3500.0  574.82  4124.3  564.60  4333.2  561.94  4547.2  559.04
  4658.0  558.95  4702.8  559.37  4708.3  560.25  4758.7  559.17  4778.8  559.69
  4806.5  558.67  4807.1  558.17  4811.6  558.67  4849.3  559.58  4873.7  558.80
  4894.2  559.74  4970.1  559.01  5010.8  559.63  5040.3  560.07  5071.4  559.31
  5110.3  560.04  5150.3  558.99  5170.3  559.69  5280.3  559.70  5680.4  565.56
  5980.4  571.82  6050.4  574.63  6220.4  578.89  6350.4  583.37  6736.8  590.37
#Mann=7,-1,0
  3036.8    0.05       0  4333.2    0.12       0  4806.5    0.07       0
  4811.6    0.12       0  4894.2     0.1       0  5010.8    0.12       0
  5071.4    0.05       0
Bank Sta=4806.5,4811.6
Exp/Cntr=0.3,0.1

Type RM Length L Ch R = 1,40231,686,686,686
BEGIN DESCRIPTION:
Brushy Creek 72.0
END DESCRIPTION:
XS GIS Cut Line= 3
      2617389.15      7022883.74      2615676.00      7022811.00
      2614476.02      7023111.00
#Sta/Elev= 30
  3284.9  572.91  3348.1  571.20  3458.2  570.94  4179.2  562.09  4321.5  561.15
  4389.0  560.85  4419.1  559.48  4439.1  560.60  4449.1  559.79  4519.2  561.27
  4529.2  559.86  4579.0  558.97  4719.3  560.85  4772.0  559.46  4966.9  558.54
  4967.7  558.04  4972.2  558.54  5022.8  559.34  5209.6  559.11  5288.2  558.86
  5329.4  560.11  5354.5  559.40  5381.0  560.14  5411.9  559.02  5435.1  560.38
  5463.4  559.64  5700.5  563.93  5947.9  570.09  6172.1  578.95  6236.5  580.60
#Mann=8,-1,0
  3284.9    0.05       0  4321.5    0.12       0  4579.0     0.1       0
  4772.0    0.05       0  4966.9    0.03       0  4972.2    0.05       0
  5209.6     0.1       0  5354.5    0.05       0
Bank Sta=4966.9,4972.2
Exp/Cntr=0.3,0.1

Type RM Length L Ch R = 1,39545,31,31,31
BEGIN DESCRIPTION:
Mapping XS 5d88f67f
END DESCRIPTION:
XS GIS Cut Line= 5
      2617700.47      7022209.58      2616705.54      7022149.49
      2615875.65      7022189.57      2614818.50      7022239.96
      2614440.93      7022721.68
#Sta/Elev= 30
  3172.4  577.42  3888.2  567.76  3938.3  568.81  3978.3  561.98  4062.3  562.53
  4088.5  566.22  4309.0  561.04  4507.7  561.65  4512.8  559.56  4634.5  561.31
  4716.5  562.95  4721.5  560.53  4759.4  559.93  4819.4  562.42  4919.6  562.16
  4936.9  559.12  4937.6  558.62  4942.3  559.12  5149.8  562.54  5251.7  561.76
  5310.0  563.86  5329.4  561.62  5350.1  559.99  5380.1  562.90  5428.7  561.10
  5530.2  562.92  5555.2  560.35  5760.3  561.89  5790.5  560.27  6670.4  577.63
#Mann=7,-1,0
  3172.4    0.05       0  4634.5     0.1       0  4936.9    0.07       0
  4942.3     0.1       0  5251.7    0.05       0  5329.4     0.1       0
  5428.7    0.05       0
Bank Sta=4936.9,4942.3
Exp/Cntr=0.3,0.1

Type RM Length L Ch R = 1,39514,64,64,64
BEGIN DESCRIPTION:
Mapping XS dfeb9573
END DESCRIPTION:
XS GIS Cut Line= 5
      2617696.13      7022183.54      2616684.17      7022116.91
      2615882.12      7022158.82      2614809.82      7022209.58
      2614424.60      7022707.33
#Sta/Elev= 30
  3182.7  577.04  3744.0  570.48  3874.3  568.47  3907.8  567.18  3954.5  567.73
  3964.5  566.96  3984.6  562.57  4001.9  561.57  4002.7  561.07  4007.4  561.57
  4084.8  562.98  4134.9  566.98  4215.0  567.33  4365.3  566.34  4640.1  566.81
  5335.2  566.23  5586.8  565.85  5827.0  567.00  6077.6  566.84  6099.3  565.62
  6120.1  565.42  6219.7  568.51  6462.3  573.37  6476.8  574.36  6497.6  573.95
  6518.5  574.73  6532.9  574.13  6605.4  576.11  6661.5  576.30  6702.9  577.58
#Mann=5,-1,0
  3182.7    0.05       0  4001.9    0.07       0  4007.4    0.05       0
  4640.1     0.1       0  5335.2    0.05       0
Bank Sta=4001.9,4007.4
Exp/Cntr=0.3,0.1

Type RM Length L Ch R = 1,39450,853,853,853
BEGIN DESCRIPTION:
Mapping XS 5a03267e
END DESCRIPTION:
XS GIS Cut Line= 6
      2617691.72      7022170.51      2616394.21      7022081.26
      2615922.24      7022109.44      2615119.47      7022141.15
      2614770.75      7022179.20      2614414.85      7022669.65
#Sta/Elev= 30
  3226.6  576.86  3793.8  570.07  3954.2  566.86  3995.5  568.10  4054.4  561.56
  4244.9  566.72  4315.0  561.76  4679.0  555.19  4941.7  552.83  4946.7  555.15
  4966.2  555.11  5006.2  553.52  5076.3  552.79  5096.3  554.00  5123.6  552.66
  5124.4  552.16  5129.1  552.66  5163.7  552.78  5168.8  554.75  5374.0  553.82
  5415.5  553.95  5420.5  555.42  5646.7  555.37  5817.0  557.71  6016.8  561.69
  6223.2  567.86  6530.8  572.68  6545.5  574.08  6616.6  573.56  6760.2  576.41
#Mann=5,-1,0
  3226.6    0.05       0  4679.0     0.1       0  5123.6    0.07       0
  5129.1     0.1       0  5374.0    0.05       0
Bank Sta=5123.6,5129.1
Exp/Cntr=0.3,0.1

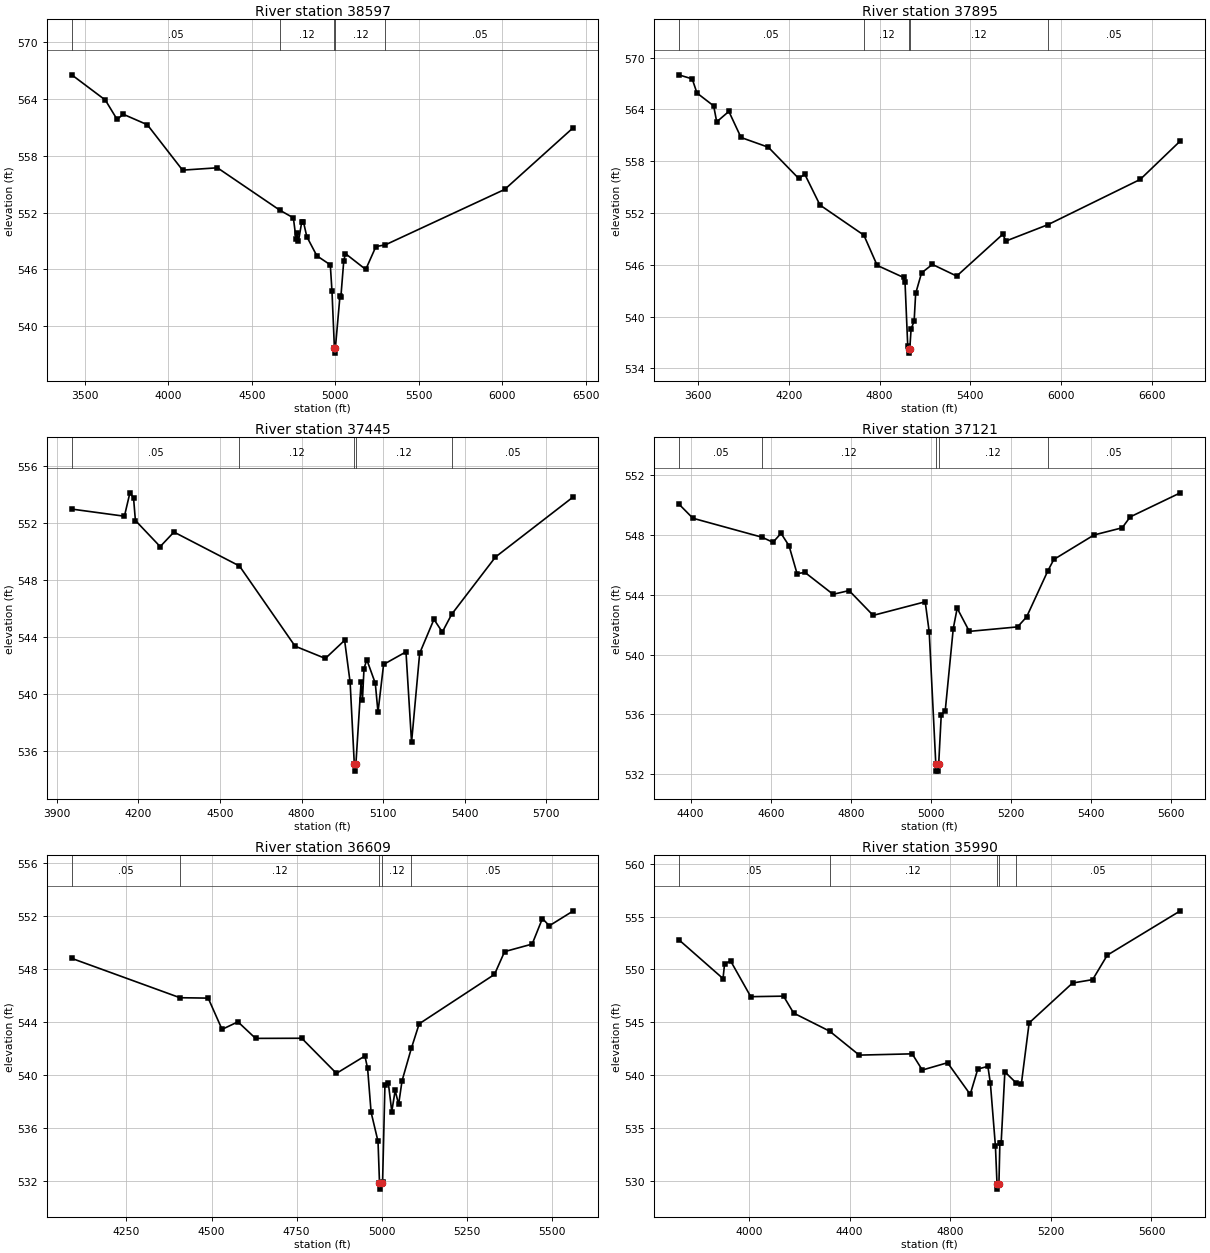
Type RM Length L Ch R = 1,38597,702,702,702
BEGIN DESCRIPTION:
Brushy Creek 68.0
END DESCRIPTION:
XS GIS Cut Line= 4
      2617696.10      7021489.09      2616126.45      7021321.19
      2615747.29      7021380.52      2614869.72      7021943.68
#Sta/Elev= 30
  3421.4  566.52  3622.6  563.86  3693.0  561.82  3730.4  562.36  3874.1  561.26
  4085.3  556.47  4294.0  556.72  4666.0  552.27  4749.0  551.44  4765.4  549.20
  4770.4  549.80  4779.2  548.95  4799.3  551.01  4809.4  551.03  4829.5  549.46
  4889.8  547.44  4970.3  546.49  4980.3  543.72  4995.0  537.68  4995.8  537.18
  5000.5  537.68  5028.4  543.24  5033.5  543.09  5051.1  546.94  5061.2  547.67
  5182.6  546.00  5243.4  548.41  5300.7  548.60  6015.1  554.44  6426.5  560.96
#Mann=5,-1,0
  3421.4    0.05       0  4666.0    0.12       0  4995.0    0.07       0
  5000.5    0.12       0  5300.7    0.05       0
Bank Sta=4995,5000.5
Exp/Cntr=0.3,0.1

Type RM Length L Ch R = 1,37895,450,450,450
BEGIN DESCRIPTION:
Brushy Creek 67.0
END DESCRIPTION:
XS GIS Cut Line= 4
      2617596.28      7020516.87      2616074.18      7020667.12
      2615706.14      7020707.50      2614812.02      7021809.96
#Sta/Elev= 30
  3470.5  568.01  3559.8  567.54  3591.4  565.90  3701.9  564.41  3722.0  562.56
  3802.4  563.77  3882.8  560.75  4063.6  559.62  4264.6  556.00  4304.8  556.49
  4405.3  552.92  4695.7  549.43  4783.6  545.93  4958.0  544.53  4968.0  543.98
  4985.9  536.63  4993.6  536.26  4994.6  535.76  4999.5  536.26  5008.2  538.56
  5028.3  539.46  5038.4  542.67  5077.5  545.06  5149.1  546.04  5310.0  544.69
  5614.7  549.53  5635.6  548.75  5914.4  550.65  6524.3  555.89  6789.7  560.35
#Mann=5,-1,0
  3470.5    0.05       0  4695.7    0.12       0  4993.6    0.07       0
  4999.5    0.12       0  5914.4    0.05       0
Bank Sta=4993.6,4999.5
Exp/Cntr=0.3,0.1

Type RM Length L Ch R = 1,37445,324,324,324
BEGIN DESCRIPTION:
Brushy Creek 66.0
END DESCRIPTION:
XS GIS Cut Line= 3
      2616997.29      7020091.53      2615964.90      7020251.45
      2615187.44      7020065.48
#Sta/Elev= 30
  3955.3  552.99  4148.9  552.49  4169.1  554.13  4182.4  553.79  4189.3  552.19
  4280.4  550.36  4331.0  551.38  4571.9  549.00  4776.3  543.38  4887.6  542.52
  4958.4  543.79  4978.7  540.84  4994.0  535.12  4994.9  534.62  4999.9  535.12
  5018.9  540.85  5024.0  539.62  5029.7  541.81  5040.0  542.43  5071.2  540.78
  5081.1  538.75  5101.7  542.10  5184.0  542.98  5204.5  536.64  5234.3  542.88
  5286.8  545.26  5317.6  544.37  5352.2  545.62  5513.0  549.63  5799.4  553.85
#Mann=5,-1,0
  3955.3    0.05       0  4571.9    0.12       0  4994.0    0.07       0
  4999.9    0.12       0  5352.2    0.05       0
Bank Sta=4994,4999.9
Exp/Cntr=0.3,0.1

Type RM Length L Ch R = 1,37121,512,512,512
BEGIN DESCRIPTION:
Brushy Creek 65.0
END DESCRIPTION:
XS GIS Cut Line= 3
      2616601.42      7019960.97      2615901.43      7019960.97
      2615351.39      7020010.97
#Sta/Elev= 30
  4370.1  550.09  4405.5  549.13  4578.1  547.86  4605.5  547.52  4625.5  548.12
  4645.5  547.29  4665.5  545.43  4685.5  545.50  4755.5  544.04  4795.5  544.29
  4855.5  542.63  4985.5  543.54  4995.5  541.52  5011.9  532.71  5013.0  532.21
  5018.1  532.21  5019.2  532.71  5025.5  535.97  5035.5  536.25  5055.5  541.74
  5065.3  543.11  5095.6  541.56  5216.1  541.86  5238.7  542.53  5291.3  545.59
  5306.5  546.37  5406.9  548.01  5477.2  548.49  5497.3  549.22  5622.4  550.83
#Mann=5,-1,0
  4370.1    0.05       0  4578.1    0.12       0  5011.9    0.07       0
  5019.2    0.12       0  5291.3    0.05       0
Bank Sta=5011.9,5019.2
Exp/Cntr=0.3,0.1

Type RM Length L Ch R = 1,36609,619,619,619
BEGIN DESCRIPTION:
Brushy Creek 64.0
END DESCRIPTION:
XS GIS Cut Line= 3
      2616719.58      7019323.29      2615825.30      7019495.94
      2615265.59      7019557.66
#Sta/Elev= 30
  4089.2  548.80  4407.2  545.83  4490.1  545.80  4530.8  543.44  4577.5  544.01
  4629.3  542.76  4765.0  542.77  4866.9  540.12  4950.5  541.43  4958.5  540.50
  4968.7  537.19  4989.1  534.98  4993.4  531.88  4994.5  531.38  5000.8  531.88
  5002.5  531.91  5009.4  539.23  5019.4  539.39  5029.5  537.24  5039.5  538.83
  5049.6  537.77  5059.7  539.56  5086.9  542.00  5110.0  543.86  5331.3  547.59
  5361.0  549.31  5442.0  549.88  5472.1  551.81  5492.3  551.26  5563.1  552.39
#Mann=5,-1,0
  4089.2    0.05       0  4407.2    0.12       0  4993.4    0.07       0
  5000.8    0.12       0  5086.9    0.05       0
Bank Sta=4993.4,5000.8
Exp/Cntr=0.3,0.1

Type RM Length L Ch R = 1,35990,677,677,677
BEGIN DESCRIPTION:
Brushy Creek 63.0
END DESCRIPTION:
XS GIS Cut Line= 3
      2617001.64      7019080.24      2615725.79      7018981.06
      2615035.51      7019167.04
#Sta/Elev= 30
  3720.3  552.82  3896.5  549.14  3902.7  550.52  3926.6  550.81  4006.8  547.43
  4137.2  547.48  4177.3  545.88  4320.6  544.17  4438.1  541.91  4648.7  542.03
  4688.9  540.50  4789.2  541.19  4879.4  538.20  4909.5  540.59  4949.6  540.85
  4959.7  539.23  4979.7  533.30  4986.0  529.75  4987.1  529.25  4993.6  529.75
  4997.4  533.65  5002.5  533.65  5017.2  540.33  5062.6  539.27  5082.6  539.16
  5113.7  544.95  5286.3  548.72  5366.2  549.04  5424.4  551.35  5714.9  555.54
#Mann=5,-1,0
  3720.3    0.05       0  4320.6    0.12       0  4986.0    0.07       0
  4993.6    0.12       0  5062.6    0.05       0
Bank Sta=4986,4993.6
Exp/Cntr=0.3,0.1

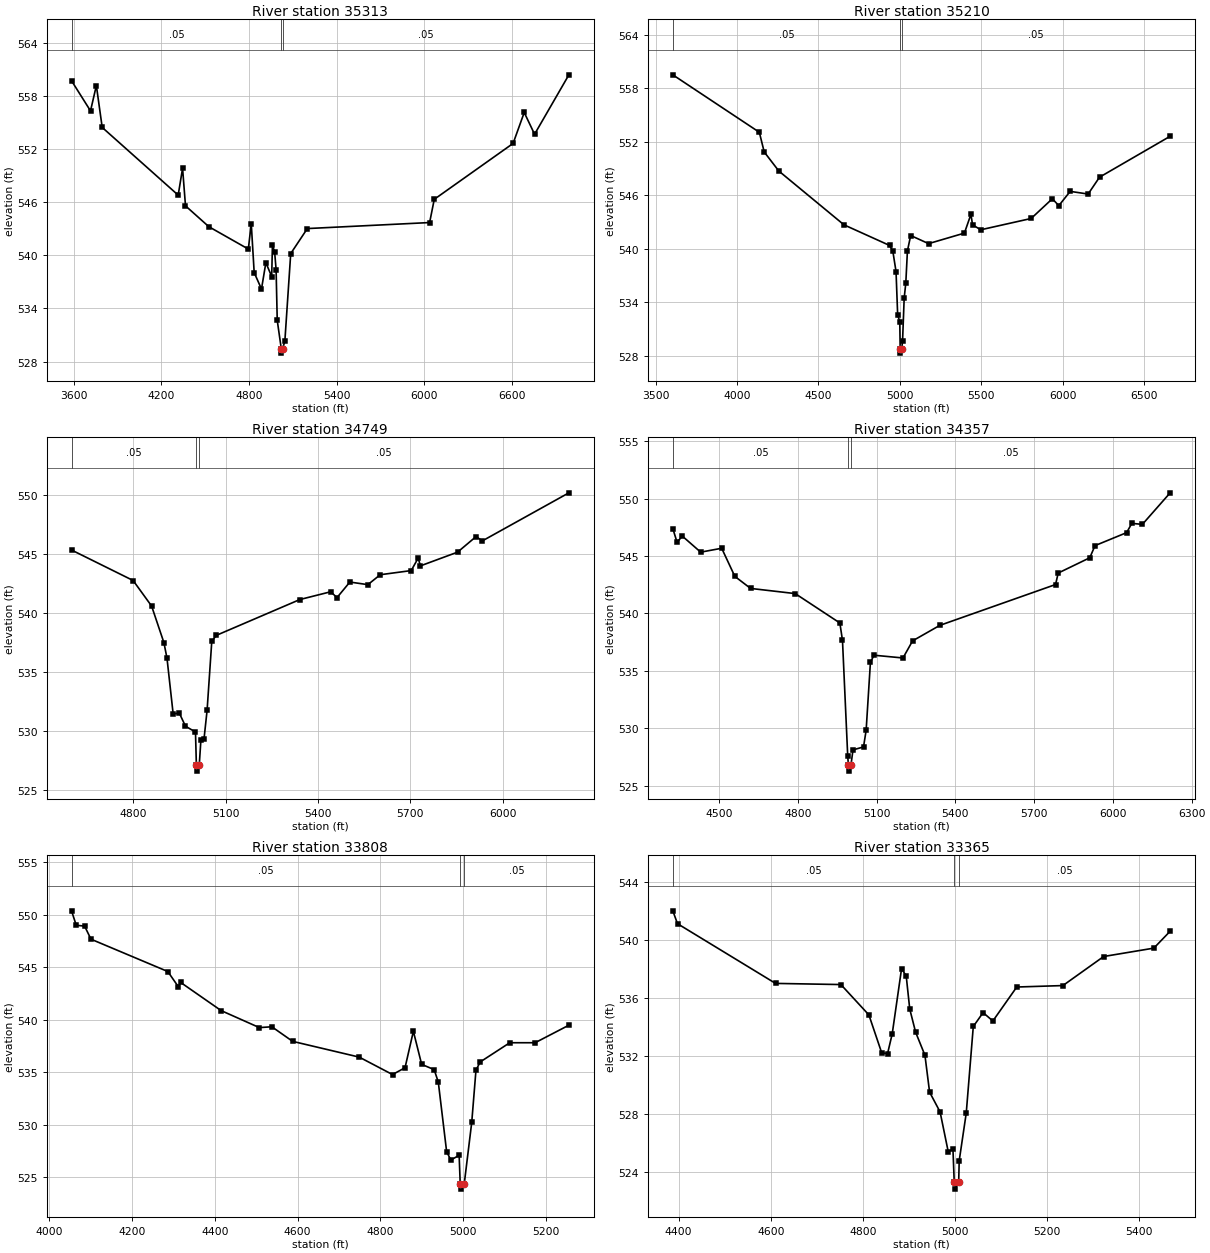
Type RM Length L Ch R = 1,35313,103,103,103
BEGIN DESCRIPTION:
Mapping XS c27c3a82
END DESCRIPTION:
XS GIS Cut Line= 6
      2617565.92      7018607.15      2615877.53      7018572.43
      2615211.92      7018586.47      2614736.03      7018546.38
      2614519.02      7018546.38      2614234.07      7018334.83
#Sta/Elev= 30
  3586.2  559.76  3716.1  556.35  3756.1  559.22  3796.1  554.48  4316.2  546.82
  4346.2  549.86  4366.2  545.61  4526.2  543.25  4796.3  540.72  4816.3  543.60
  4836.3  538.06  4886.3  536.20  4916.3  539.18  4956.2  537.61  4961.2  541.16
  4976.3  540.40  4986.3  538.40  4994.1  532.66  5021.8  529.45  5023.1  528.95
  5030.9  529.45  5046.3  530.31  5086.4  540.21  5200.1  543.04  6037.1  543.72
  6068.9  546.35  6608.4  552.67  6684.6  556.17  6755.5  553.71  6990.3  560.43
#Mann=3,-1,0
  3586.2    0.05       0  5021.8    0.03       0  5030.9    0.05       0
Bank Sta=5021.8,5030.9
Exp/Cntr=0.3,0.1

Type RM Length L Ch R = 1,35210,461,461,461
BEGIN DESCRIPTION:
Brushy Creek 62.0
END DESCRIPTION:
XS GIS Cut Line= 3
      2617587.60      7018494.30      2616193.10      7018494.51
      2614532.07      7018459.58
#Sta/Elev= 30
  3605.5  559.53  4137.1  553.09  4167.1  550.88  4257.1  548.74  4657.1  542.71
  4937.1  540.40  4957.1  539.79  4977.1  537.47  4987.1  532.59  5000.0  531.86
  5002.6  528.82  5003.9  528.32  5011.7  528.82  5017.1  529.63  5027.1  534.48
  5037.1  536.18  5047.1  539.79  5067.1  541.51  5177.1  540.60  5397.2  541.78
  5437.2  543.88  5447.2  542.72  5497.2  542.15  5807.3  543.42  5937.3  545.63
  5977.3  544.86  6047.3  546.46  6157.4  546.16  6227.4  548.05  6661.4  552.64
#Mann=3,-1,0
  3605.5    0.05       0  5002.6    0.03       0  5011.7    0.05       0
Bank Sta=5002.6,5011.7
Exp/Cntr=0.3,0.1

Type RM Length L Ch R = 1,34749,392,392,392
BEGIN DESCRIPTION:
Brushy Creek 61.0
END DESCRIPTION:
XS GIS Cut Line= 3
      2616676.01      7018061.00      2616276.00      7018061.00
      2615065.93      7017951.77
#Sta/Elev= 30
  4599.6  545.33  4799.6  542.75  4859.6  540.59  4899.6  537.49  4909.6  536.17
  4929.6  531.46  4949.6  531.53  4969.6  530.42  5002.1  529.93  5005.0  527.12
  5006.4  526.62  5014.3  527.12  5019.7  529.26  5029.7  529.32  5039.8  531.77
  5055.0  537.61  5069.9  538.11  5341.0  541.14  5441.4  541.80  5461.5  541.30
  5503.4  542.62  5561.9  542.40  5602.0  543.24  5702.5  543.59  5725.1  544.64
  5732.6  543.99  5853.1  545.15  5913.3  546.47  5933.4  546.10  6214.6  550.17
#Mann=3,-1,0
  4599.6    0.05       0  5005.0    0.03       0  5014.3    0.05       0
Bank Sta=5005,5014.3
Exp/Cntr=0.3,0.1

Type RM Length L Ch R = 1,34357,549,549,549
BEGIN DESCRIPTION:
Brushy Creek 60.0
END DESCRIPTION:
XS GIS Cut Line= 3
      2617052.17      7017701.05      2616376.17      7017700.85
      2615160.42      7017625.13
#Sta/Elev= 30
  4324.0  547.40  4340.2  546.20  4360.2  546.74  4430.2  545.34  4510.2  545.68
  4560.2  543.23  4620.2  542.18  4790.2  541.73  4960.2  539.17  4970.2  537.65
  4990.2  527.54  4992.9  526.76  4994.2  526.26  5002.3  526.76  5010.2  528.11
  5050.3  528.37  5060.3  529.82  5076.6  535.75  5090.3  536.36  5200.6  536.12
  5237.2  537.61  5340.8  538.96  5781.7  542.52  5791.7  543.52  5911.9  544.85
  5932.0  545.91  6052.2  547.04  6072.2  547.85  6112.3  547.76  6218.1  550.51
#Mann=3,-1,0
  4324.0    0.05       0  4992.9    0.03       0  5002.3    0.05       0
Bank Sta=4992.9,5002.3
Exp/Cntr=0.3,0.1

Type RM Length L Ch R = 1,33808,443,443,443
BEGIN DESCRIPTION:
Brushy Creek 59.0
END DESCRIPTION:
XS GIS Cut Line= 3
      2617067.35      7017171.54      2616126.00      7017261.00
      2615876.05      7017310.99
#Sta/Elev= 30
  4054.4  550.39  4065.8  549.01  4085.9  548.94  4101.3  547.69  4286.8  544.61
  4312.4  543.15  4317.5  543.58  4415.5  540.89  4507.8  539.27  4537.9  539.35
  4588.1  537.96  4748.9  536.46  4829.2  534.80  4859.4  535.45  4879.5  538.92
  4899.5  535.77  4929.7  535.27  4939.7  534.08  4959.8  527.46  4969.9  526.66
  4990.0  527.11  4992.6  524.39  4994.0  523.89  5002.3  524.39  5020.4  530.25
  5030.6  535.21  5040.8  536.00  5112.2  537.83  5173.4  537.83  5254.9  539.50
#Mann=3,-1,0
  4054.4    0.05       0  4992.6    0.03       0  5002.3    0.05       0
Bank Sta=4992.6,5002.3
Exp/Cntr=0.3,0.1

Type RM Length L Ch R = 1,33365,449,449,449
BEGIN DESCRIPTION:
Brushy Creek 58.0
END DESCRIPTION:
XS GIS Cut Line= 3
      2616676.05      7016760.99      2616076.00      7016861.00
      2615676.02      7017110.99
#Sta/Elev= 30
  4387.4  542.04  4397.6  541.15  4610.5  537.02  4752.4  536.94  4813.2  534.84
  4841.1  532.21  4853.8  532.17  4863.9  533.54  4884.2  538.05  4894.3  537.52
  4901.9  535.25  4914.6  533.65  4934.9  532.05  4945.0  529.50  4967.8  528.13
  4985.6  525.36  4995.7  525.58  4998.5  523.29  4999.9  522.79  5008.2  523.29
  5009.3  524.75  5024.6  528.05  5039.9  534.04  5061.2  535.00  5082.4  534.42
  5134.3  536.77  5234.5  536.87  5323.0  538.88  5432.0  539.46  5467.4  540.63
#Mann=3,-1,0
  4387.4    0.05       0  4998.5    0.03       0  5008.2    0.05       0
Bank Sta=4998.5,5008.2
Exp/Cntr=0.3,0.1

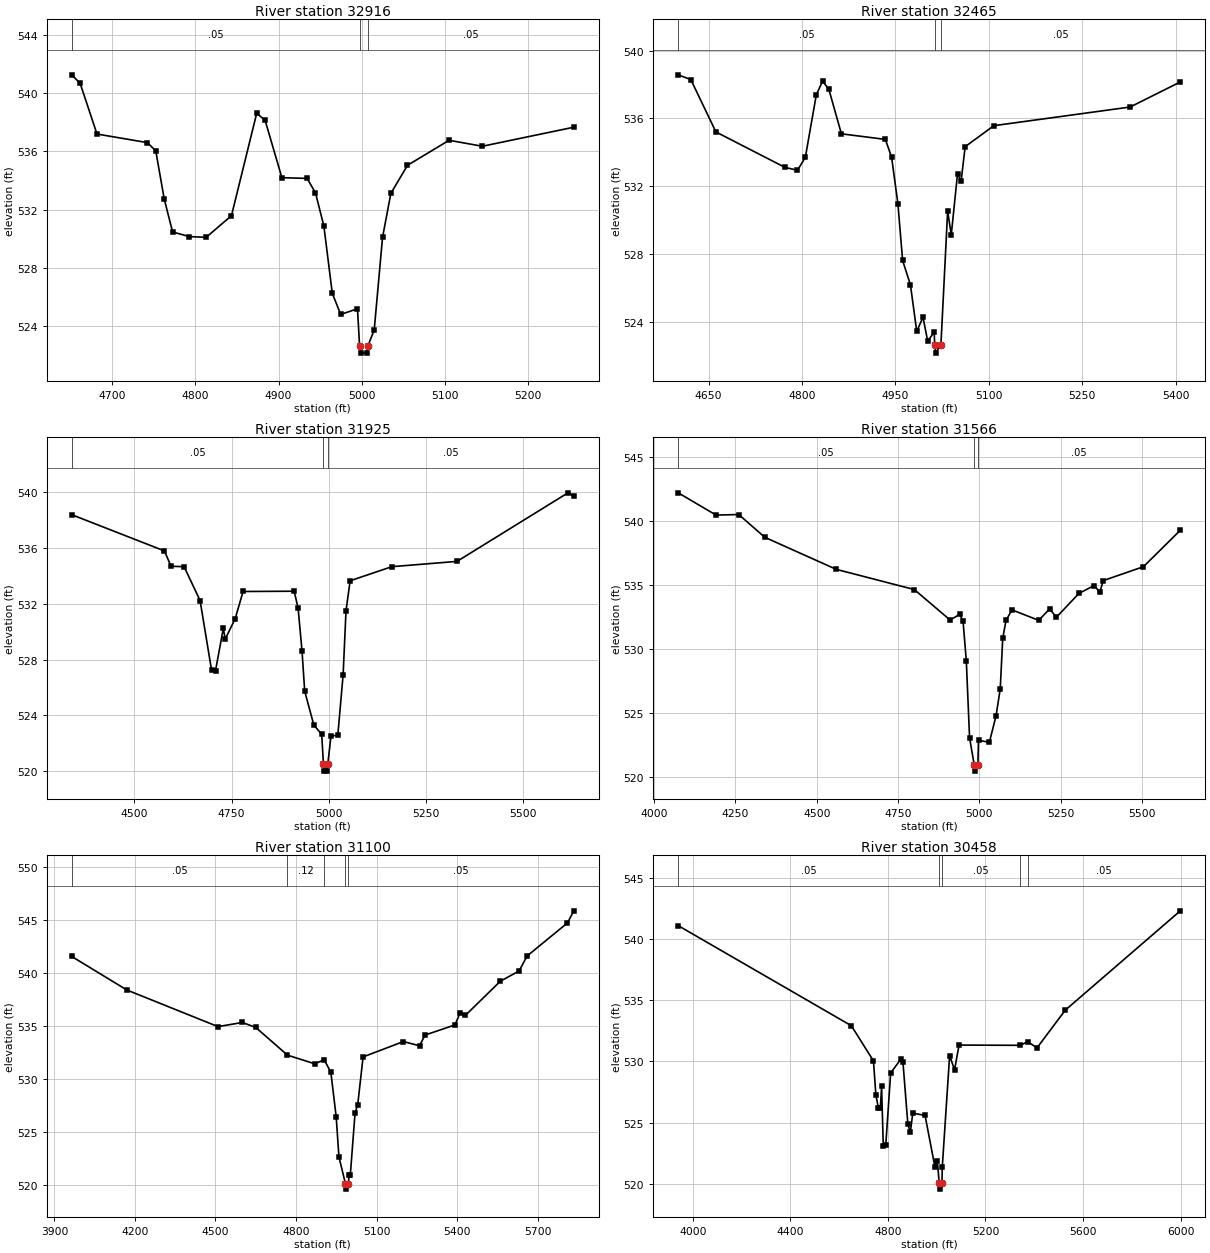
Type RM Length L Ch R = 1,32916,451,451,451
BEGIN DESCRIPTION:
Brushy Creek 57.0
END DESCRIPTION:
XS GIS Cut Line= 3
      2616376.02      7016511.00      2616026.00      7016461.00
      2615775.98      7016461.00
#Sta/Elev= 30
  4651.4  541.27  4661.5  540.68  4681.7  537.20  4742.3  536.61  4752.4  536.04
  4762.5  532.75  4772.6  530.47  4792.8  530.15  4813.0  530.10  4843.4  531.59
  4873.7  538.62  4883.8  538.15  4904.0  534.20  4934.3  534.15  4944.4  533.16
  4954.5  530.87  4964.6  526.25  4974.7  524.80  4994.9  525.19  4997.4  522.64
  4998.8  522.14  5006.0  522.14  5007.4  522.64  5015.0  523.73  5025.0  530.09
  5035.0  533.12  5055.0  535.05  5105.0  536.77  5145.0  536.36  5255.0  537.67
#Mann=3,-1,0
  4651.4    0.05       0  4997.4    0.03       0  5007.4    0.05       0
Bank Sta=4997.4,5007.4
Exp/Cntr=0.3,0.1

Type RM Length L Ch R = 1,32465,540,540,540
BEGIN DESCRIPTION:
Brushy Creek 56.0
END DESCRIPTION:
XS GIS Cut Line= 3
      2616426.00      7016061.00      2616026.00      7016011.00
      2615676.02      7016210.99
#Sta/Elev= 30
  4601.4  538.57  4621.6  538.29  4661.9  535.20  4772.7  533.11  4792.9  532.94
  4805.5  533.70  4823.1  537.39  4833.2  538.20  4843.3  537.71  4863.4  535.09
  4934.0  534.76  4944.0  533.71  4954.1  530.97  4961.7  527.62  4974.3  526.17
  4984.4  523.43  4994.4  524.27  5002.0  522.85  5012.4  523.40  5013.2  522.65
  5014.6  522.15  5023.2  522.65  5034.0  530.53  5039.8  529.13  5049.9  532.74
  5055.6  532.28  5062.1  534.33  5108.2  535.57  5327.0  536.67  5407.6  538.15
#Mann=3,-1,0
  4601.4    0.05       0  5013.2    0.03       0  5023.2    0.05       0
Bank Sta=5013.2,5023.2
Exp/Cntr=0.3,0.1

Type RM Length L Ch R = 1,31925,359,359,359
BEGIN DESCRIPTION:
Brushy Creek 55.0
END DESCRIPTION:
XS GIS Cut Line= 3
      2616581.73      7015663.34      2615927.95      7015567.26
      2615331.76      7015363.35
#Sta/Elev= 30
  4339.2  538.40  4577.5  535.80  4594.3  534.70  4628.0  534.67  4669.1  532.24
  4698.7  527.23  4708.9  527.22  4728.8  530.24  4733.8  529.48  4759.4  530.94
  4779.6  532.89  4911.0  532.91  4921.1  531.70  4931.2  528.62  4938.1  525.74
  4961.5  523.31  4981.8  522.64  4986.3  520.50  4987.8  520.00  4996.0  520.00
  4997.5  520.50  5005.6  522.53  5023.2  522.57  5036.9  526.93  5044.3  531.50
  5054.9  533.66  5162.1  534.67  5329.7  535.05  5615.0  539.97  5630.1  539.73
#Mann=3,-1,0
  4339.2    0.05       0  4986.3    0.03       0  4997.5    0.05       0
Bank Sta=4986.3,4997.5
Exp/Cntr=0.3,0.1

Type RM Length L Ch R = 1,31566,466,466,466
BEGIN DESCRIPTION:
Brushy Creek 54.0
END DESCRIPTION:
XS GIS Cut Line= 3
      2617002.25      7015261.81      2616076.00      7015261.00
      2615476.02      7015111.00
#Sta/Elev= 30
  4073.9  542.23  4190.2  540.49  4260.2  540.53  4340.2  538.75  4560.2  536.24
  4800.2  534.66  4910.2  532.28  4940.2  532.72  4950.2  532.17  4960.2  529.09
  4970.2  523.06  4984.5  520.95  4986.1  520.45  4995.8  520.95  4997.7  522.87
  5031.1  522.70  5051.7  524.78  5064.6  526.89  5072.3  530.87  5082.6  532.26
  5100.7  533.07  5183.1  532.25  5216.6  533.15  5237.2  532.49  5306.8  534.36
  5353.2  534.97  5371.2  534.46  5381.5  535.36  5505.2  536.45  5618.6  539.30
#Mann=3,-1,0
  4073.9    0.05       0  4984.5    0.03       0  4995.8    0.05       0
Bank Sta=4984.5,4995.8
Exp/Cntr=0.3,0.1

Type RM Length L Ch R = 1,31100,642,642,642
BEGIN DESCRIPTION:
Brushy Creek 53.0
END DESCRIPTION:
XS GIS Cut Line= 3
      2617060.91      7014842.98      2616026.00      7014811.00
      2615192.34      7014864.68
#Sta/Elev= 30
  3964.5  541.58  4169.5  538.42  4509.4  534.96  4599.7  535.35  4649.7  534.89
  4768.1  532.27  4869.8  531.45  4905.0  531.83  4929.9  530.65  4949.9  526.41
  4959.9  522.68  4984.3  520.12  4985.8  519.62  4995.6  520.12  4997.4  520.96
  5002.4  520.96  5020.0  526.79  5030.0  527.60  5050.0  532.10  5200.3  533.55
  5260.4  533.15  5280.5  534.16  5392.3  535.12  5410.8  536.21  5430.8  536.01
  5561.1  539.24  5631.2  540.21  5661.3  541.63  5811.6  544.75  5835.3  545.89
#Mann=5,-1,0
  3964.5    0.05       0  4768.1    0.12       0  4905.0    0.05       0
  4984.3    0.03       0  4995.6    0.05       0
Bank Sta=4984.3,4995.6
Exp/Cntr=0.3,0.1

Type RM Length L Ch R = 1,30458,766,766,766
BEGIN DESCRIPTION:
Brushy Creek 52.0
END DESCRIPTION:
XS GIS Cut Line= 3
      2617260.55      7014359.04      2616025.72      7014204.96
      2615266.15      7014500.10
#Sta/Elev= 30
  3939.9  541.09  4649.9  532.92  4740.6  530.05  4750.7  527.24  4760.8  526.21
  4768.9  526.21  4774.0  527.96  4780.9  523.10  4791.0  523.15  4811.2  529.06
  4854.7  530.24  4861.5  529.96  4881.7  524.88  4891.8  524.22  4901.9  525.78
  4952.2  525.60  4992.6  521.40  5002.6  521.91  5010.3  520.08  5011.9  519.58
  5021.7  520.08  5022.8  521.35  5053.0  530.48  5073.2  529.32  5091.7  531.34
  5342.7  531.32  5373.5  531.62  5411.4  531.11  5527.3  534.19  5999.2  542.30
#Mann=5,-1,0
  3939.9    0.05       0  5010.3    0.03       0  5021.7    0.05       0
  5342.7    0.12       0  5373.5    0.05       0
Bank Sta=5010.3,5021.7
Exp/Cntr=0.3,0.1