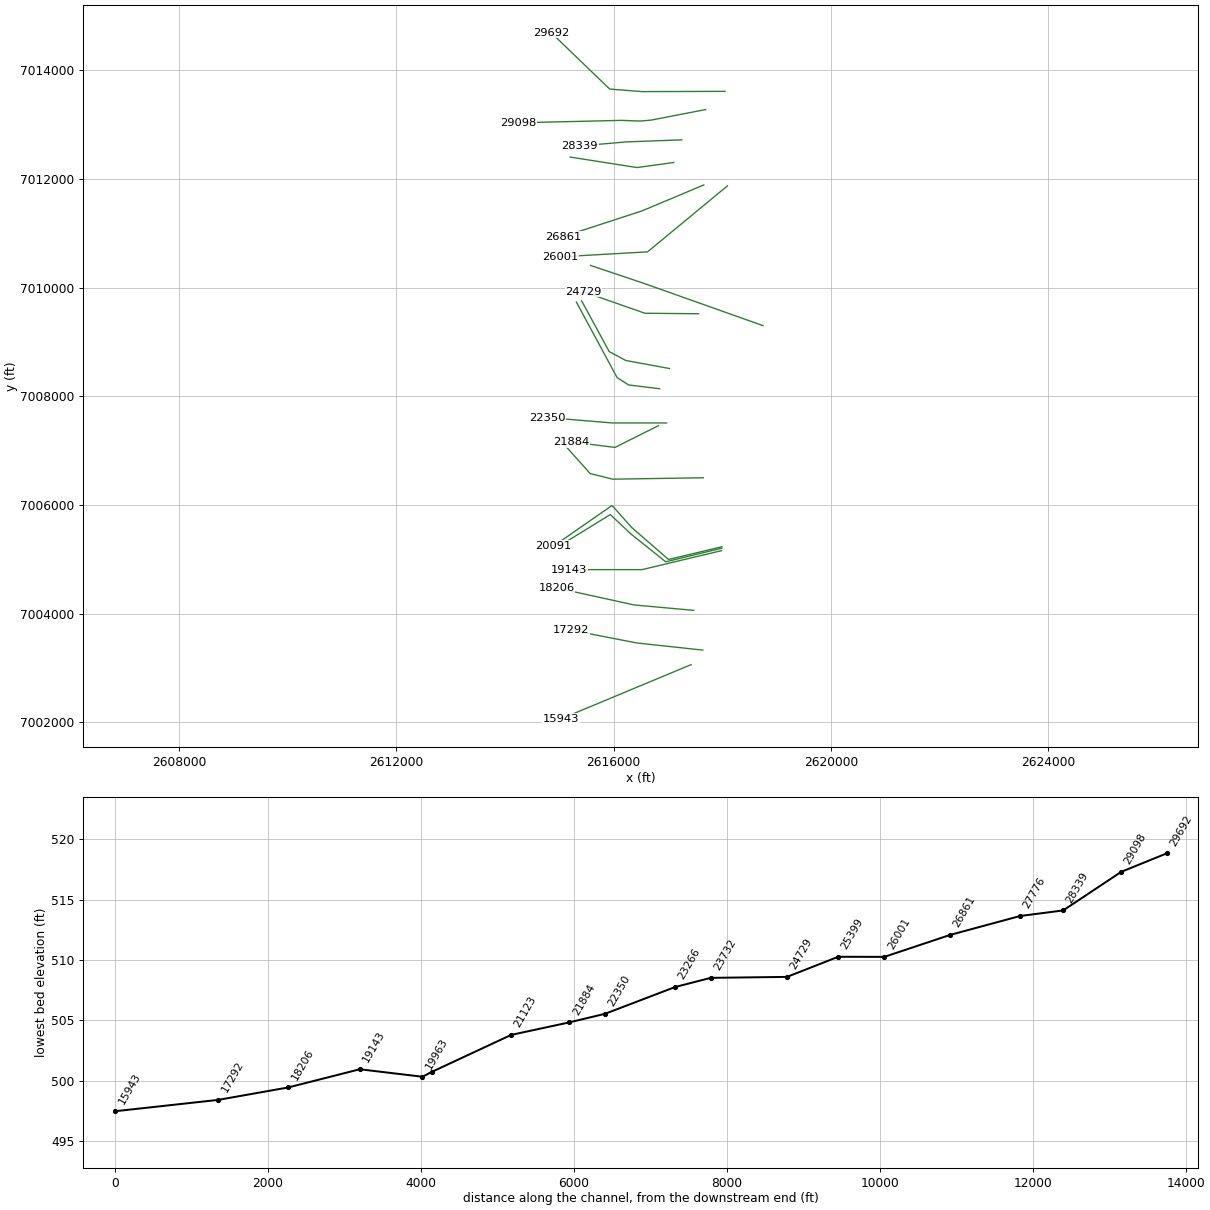
HEC-RAS study Brushy Creek.prj: Brushy Creek Base Level Engineering

--- Brushy Creek.g01 (geometry) --- (continued)

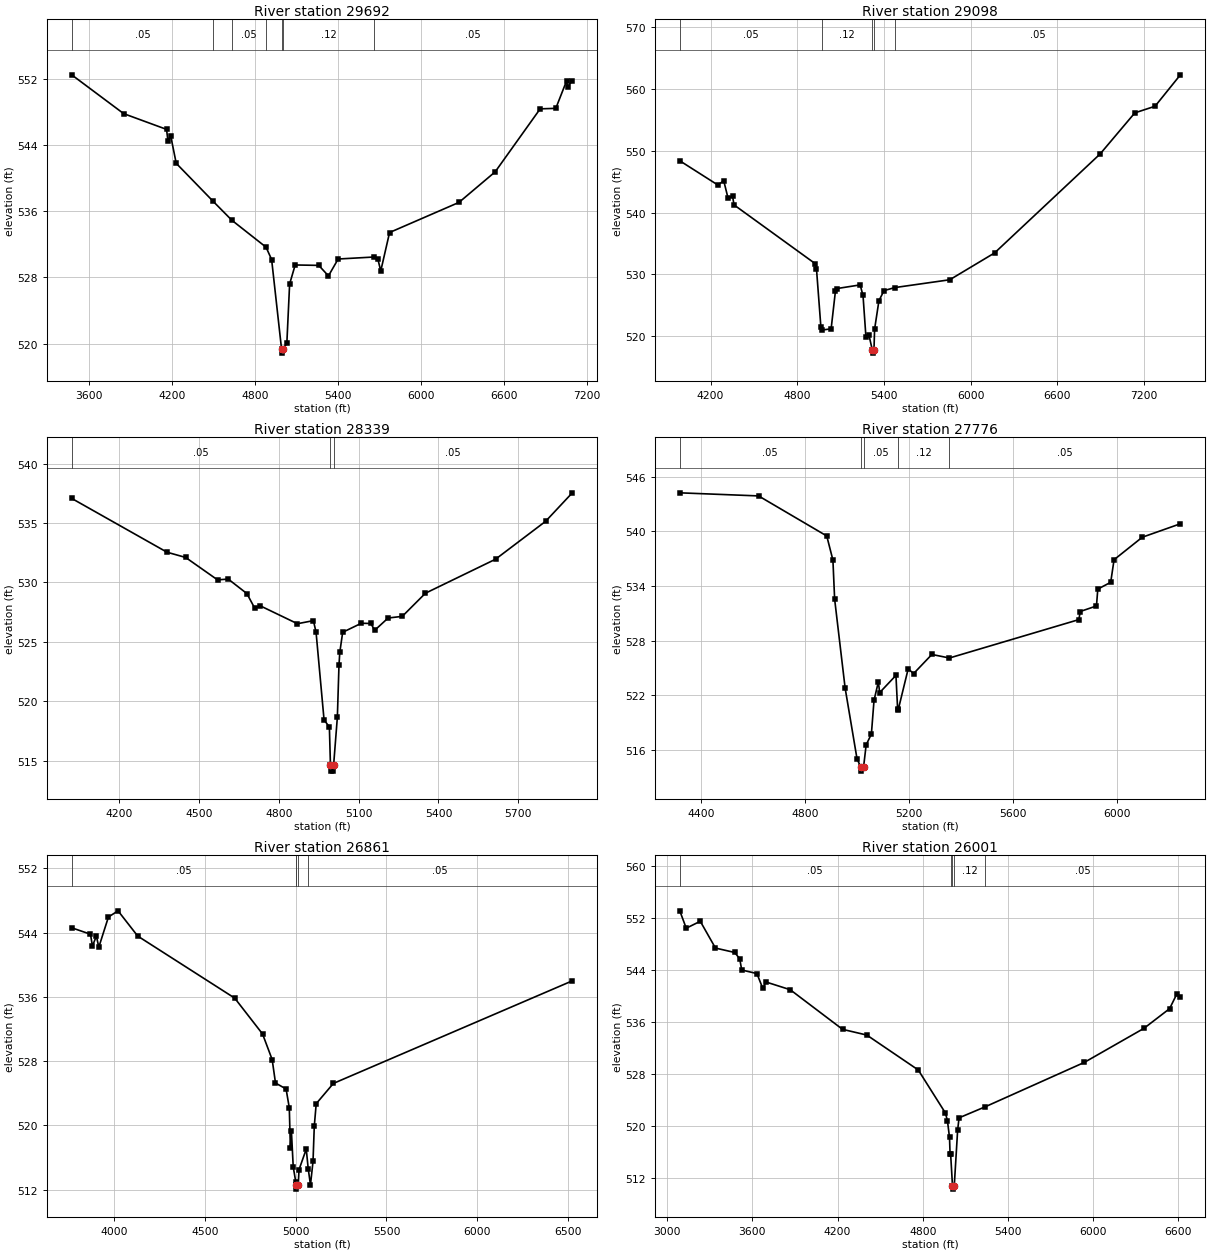
Type RM Length L Ch R = 1,29692,594,594,594
BEGIN DESCRIPTION:
Brushy Creek 50.0
END DESCRIPTION:
XS GIS Cut Line= 4
      2618051.99      7013615.83      2616526.00      7013611.00
      2615928.06      7013658.08      2614851.65      7014695.43
#Sta/Elev= 30
  3474.0  552.46  3850.0  547.77  4160.0  545.87  4170.0  544.50  4190.0  545.09
  4230.0  541.77  4496.9  537.18  4632.5  534.89  4879.6  531.64  4920.0  530.15
  4991.8  519.34  4993.4  518.84  5003.3  519.34  5030.1  520.04  5050.2  527.19
  5090.3  529.49  5260.8  529.44  5331.0  528.17  5401.2  530.21  5658.8  530.45
  5688.1  530.22  5709.4  528.77  5773.0  533.41  6275.2  537.05  6536.8  540.74
  6862.2  548.35  6975.4  548.41  7053.1  551.72  7060.3  550.98  7094.7  551.76
#Mann=7,-1,0
  3474.0    0.05       0  4496.9   0.075       0  4632.5    0.05       0
  4879.6    0.12       0  4991.8    0.07       0  5003.3    0.12       0
  5658.8    0.05       0
Bank Sta=4991.8,5003.3
Exp/Cntr=0.3,0.1

Type RM Length L Ch R = 1,29098,759,759,759
BEGIN DESCRIPTION:
Mapping XS 92993a73
END DESCRIPTION:
XS GIS Cut Line= 5
      2617694.58      7013280.48      2616699.97      7013087.81
      2616489.50      7013068.95      2616148.85      7013081.64
      2614250.76      7013037.43
#Sta/Elev= 30
  3986.9  548.35  4250.3  544.44  4291.0  545.12  4321.2  542.29  4352.1  542.63
  4362.3  541.23  4922.6  531.77  4932.7  530.95  4963.3  521.52  4972.2  521.04
  5034.1  521.23  5064.2  527.38  5074.3  527.73  5234.8  528.32  5254.8  526.61
  5274.9  519.94  5294.9  520.31  5319.1  517.81  5320.7  517.31  5330.6  517.81
  5334.9  521.17  5364.9  525.77  5400.3  527.40  5475.2  527.89  5855.1  529.15
  6165.2  533.48  6895.4  549.45  7135.5  556.08  7275.5  557.15  7450.8  562.22
#Mann=5,-1,0
  3986.9    0.05       0  4972.2    0.12       0  5319.1    0.07       0
  5330.6    0.12       0  5475.2    0.05       0
Bank Sta=5319.1,5330.6
Exp/Cntr=0.3,0.1

Type RM Length L Ch R = 1,28339,563,563,563
BEGIN DESCRIPTION:
Brushy Creek 47.0
END DESCRIPTION:
XS GIS Cut Line= 3
      2617254.02      7012722.75      2616244.90      7012685.86
      2615376.01      7012611.00
#Sta/Elev= 30
  4021.3  537.07  4379.6  532.54  4449.6  532.10  4569.7  530.21  4609.7  530.28
  4679.8  529.06  4709.8  527.81  4729.8  528.03  4869.9  526.52  4929.9  526.78
  4939.9  525.81  4970.0  518.42  4990.0  517.83  4994.0  514.61  4995.7  514.11
  5004.3  514.11  5005.9  514.61  5020.0  518.65  5026.1  523.03  5029.1  524.10
  5040.0  525.80  5110.3  526.56  5145.7  526.54  5160.5  525.97  5210.7  527.00
  5264.1  527.14  5351.2  529.09  5614.6  531.95  5802.8  535.14  5903.2  537.54
#Mann=3,-1,0
  4021.3    0.05       0  4994.0    0.03       0  5005.9    0.05       0
Bank Sta=4994,5005.9
Exp/Cntr=0.3,0.1

Type RM Length L Ch R = 1,27776,915,915,915
BEGIN DESCRIPTION:
Brushy Creek 46.0
END DESCRIPTION:
XS GIS Cut Line= 3
      2617106.47      7012306.09      2616430.34      7012213.10
      2615201.07      7012405.91
#Sta/Elev= 30
  4317.5  544.23  4620.8  543.89  4883.2  539.49  4906.9  536.84  4913.5  532.55
  4953.9  522.78  4999.7  515.00  5013.2  514.15  5014.9  513.65  5025.1  514.15
  5034.8  516.53  5055.0  517.73  5065.1  521.42  5081.8  523.46  5086.9  522.28
  5149.5  524.17  5156.2  520.33  5159.1  520.49  5196.7  524.90  5217.2  524.36
  5287.8  526.47  5355.3  526.08  5853.6  530.30  5858.7  531.19  5921.3  531.80
  5926.4  533.65  5976.1  534.40  5989.0  536.88  6097.6  539.35  6244.3  540.83
#Mann=5,-1,0
  4317.5    0.05       0  5013.2    0.03       0  5025.1    0.05       0
  5159.1    0.12       0  5355.3    0.05       0
Bank Sta=5013.2,5025.1
Exp/Cntr=0.3,0.1

Type RM Length L Ch R = 1,26861,860,860,860
BEGIN DESCRIPTION:
Mapping XS 22ac5809
END DESCRIPTION:
XS GIS Cut Line= 3
      2617661.39      7011892.74      2616524.23      7011415.31
      2615074.59      7010942.22
#Sta/Elev= 30
  3765.6  544.59  3869.1  543.79  3879.9  542.32  3901.6  543.56  3915.0  542.18
  3968.0  545.93  4020.9  546.70  4129.4  543.56  4663.8  535.84  4817.2  531.38
  4870.1  528.20  4888.5  525.28  4946.8  524.54  4964.5  522.20  4970.6  517.14
  4976.0  519.37  4986.2  514.84  5000.4  512.95  5001.4  512.58  5003.1  512.08
  5013.8  512.58  5018.1  514.50  5058.0  517.06  5068.7  514.63  5081.2  512.61
  5095.2  515.52  5102.2  519.91  5112.8  522.71  5207.4  525.23  6523.8  537.99
#Mann=5,-1,0
  3765.6    0.05       0  5000.4    0.12       0  5001.4    0.03       0
  5013.8    0.12       0  5068.7    0.05       0
Bank Sta=5001.4,5013.8
Exp/Cntr=0.3,0.1

Type RM Length L Ch R = 1,26001,602,602,602
BEGIN DESCRIPTION:
Brushy Creek 43.0
END DESCRIPTION:
XS GIS Cut Line= 3
      2618095.39      7011875.36      2616626.00      7010661.00
      2615010.27      7010569.00
#Sta/Elev= 30
  3089.3  553.16  3134.7  550.48  3233.6  551.55  3340.5  547.42  3476.0  546.74
  3511.1  545.77  3525.5  544.04  3632.3  543.49  3673.9  541.19  3696.1  542.19
  3866.8  541.00  4235.4  534.89  4406.1  534.01  4768.2  528.63  4959.7  521.99
  4974.0  520.77  4988.4  518.23  4992.3  515.69  4996.2  515.69  5009.4  510.76
  5011.1  510.26  5021.8  510.76  5045.6  519.35  5055.6  521.25  5240.6  522.96
  5937.1  529.79  6357.8  535.05  6538.0  538.08  6588.1  540.31  6613.9  539.84
#Mann=5,-1,0
  3089.3    0.05       0  4996.2    0.12       0  5009.4    0.07       0
  5021.8    0.12       0  5240.6    0.05       0
Bank Sta=5009.4,5021.8
Exp/Cntr=0.3,0.1

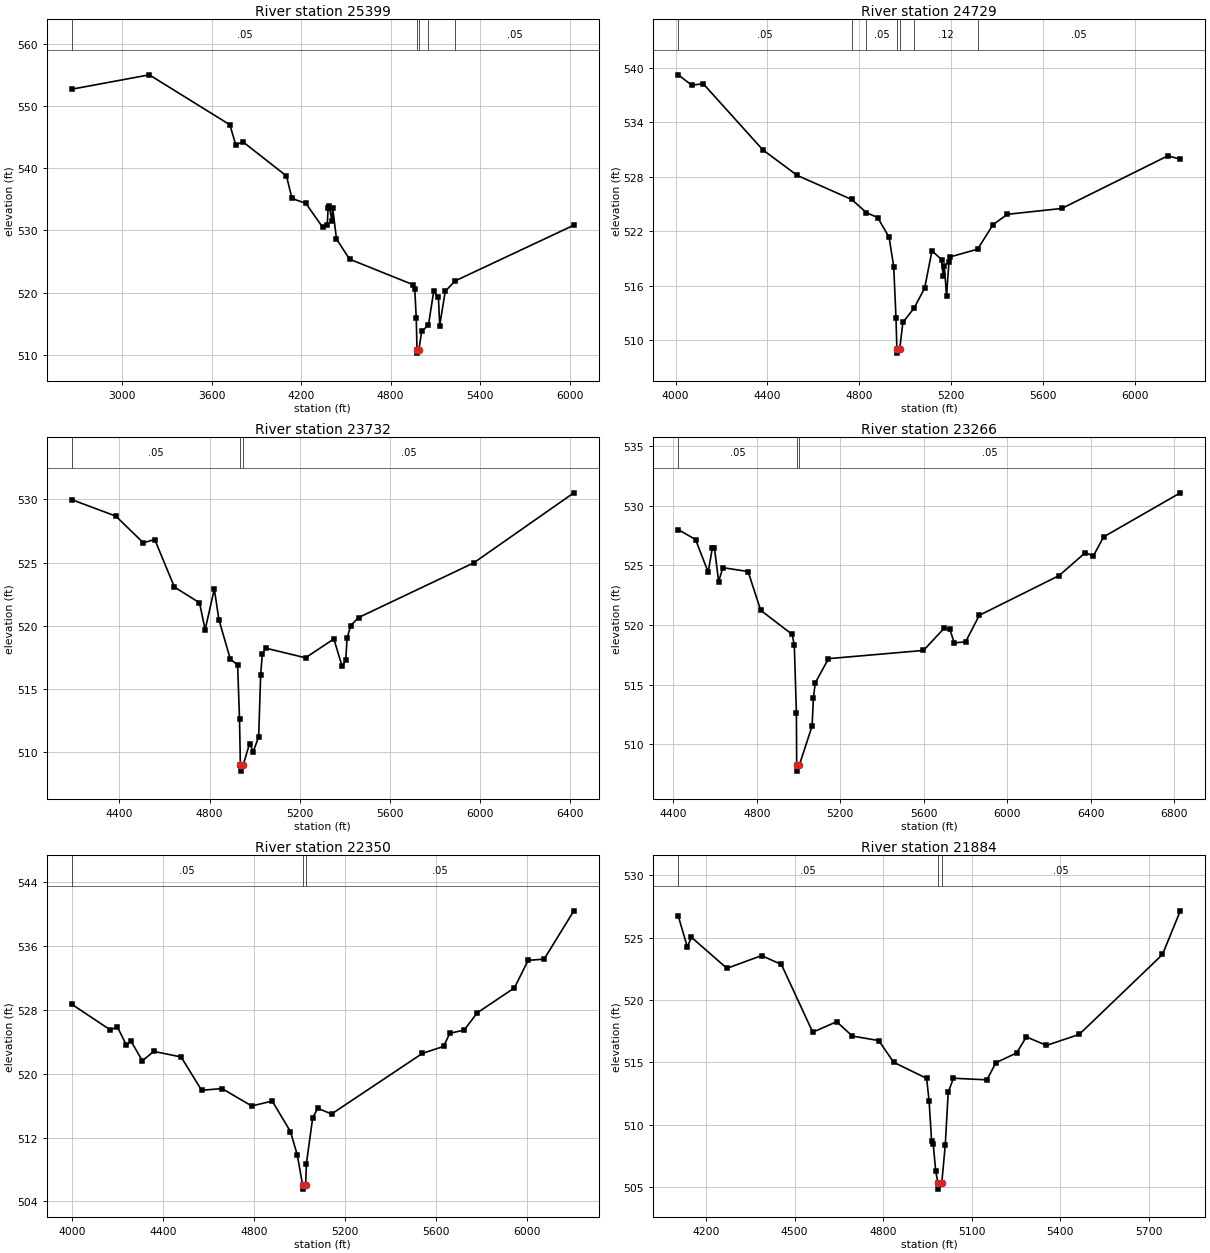
Type RM Length L Ch R = 1,25399,670,670,670
BEGIN DESCRIPTION:
Brushy Creek 42.0
END DESCRIPTION:
XS GIS Cut Line= 3
      2618751.42      7009302.61      2616549.83      7010083.87
      2615576.00      7010411.00
#Sta/Elev= 30
  2663.9  552.70  3183.3  555.01  3723.0  546.98  3762.6  543.74  3810.3  544.24
  4102.1  538.75  4139.2  535.13  4231.9  534.35  4344.7  530.50  4375.6  530.81
  4380.9  533.58  4388.6  533.95  4406.4  531.52  4411.7  533.61  4437.3  528.62
  4524.6  525.38  4951.4  521.26  4961.6  520.63  4971.7  515.85  4976.6  510.77
  4978.3  510.27  4989.1  510.77  5008.0  513.81  5053.0  514.74  5088.4  520.19
  5120.1  519.23  5128.8  514.71  5165.6  520.20  5230.5  521.86  6027.3  530.84
#Mann=5,-1,0
  2663.9    0.05       0  4976.6    0.03       0  4989.1    0.05       0
  5053.0    0.12       0  5230.5    0.05       0
Bank Sta=4976.6,4989.1
Exp/Cntr=0.3,0.1

Type RM Length L Ch R = 1,24729,997,997,997
BEGIN DESCRIPTION:
Brushy Creek 40.0
END DESCRIPTION:
XS GIS Cut Line= 3
      2617564.80      7009521.36      2616576.04      7009530.98
      2615444.79      7009927.40
#Sta/Elev= 30
  4011.2  539.25  4070.0  538.11  4120.0  538.27  4380.0  530.98  4530.0  528.17
  4767.0  525.52  4830.7  524.08  4880.0  523.53  4930.0  521.36  4950.0  518.13
  4960.0  512.46  4963.7  509.10  4965.5  508.60  4976.3  509.10  4990.0  511.98
  5038.1  513.54  5084.8  515.75  5116.6  519.86  5159.0  518.90  5165.3  517.09
  5170.6  518.19  5180.2  514.89  5190.8  518.69  5196.3  519.20  5315.7  520.05
  5382.4  522.74  5445.1  523.89  5682.0  524.53  6144.4  530.33  6198.7  529.96
#Mann=7,-1,0
  4011.2    0.05       0  4767.0    0.12       0  4830.7    0.05       0
  4963.7    0.03       0  4976.3    0.05       0  5038.1    0.12       0
  5315.7    0.05       0
Bank Sta=4963.7,4976.3
Exp/Cntr=0.3,0.1

Type RM Length L Ch R = 1,23732,466,466,466
BEGIN DESCRIPTION:
Brushy Creek 38.0
END DESCRIPTION:
XS GIS Cut Line= 4
      2617028.13      7008513.35      2616226.00      7008661.00
      2615918.71      7008825.86      2615410.96      7009760.63
#Sta/Elev= 30
  4188.6  529.98  4384.0  528.68  4506.0  526.57  4556.8  526.83  4644.2  523.07
  4755.4  521.83  4780.5  519.70  4821.2  522.92  4841.5  520.50  4892.4  517.36
  4924.7  516.92  4933.0  512.63  4936.9  509.02  4938.7  508.52  4949.6  509.02
  4977.7  510.70  4994.0  510.07  5018.0  511.23  5026.9  516.15  5034.3  517.77
  5049.6  518.24  5225.9  517.48  5351.6  518.97  5388.6  516.80  5404.3  517.28
  5410.5  519.04  5426.7  520.03  5461.2  520.66  5972.1  524.98  6416.7  530.52
#Mann=3,-1,0
  4188.6    0.05       0  4936.9    0.04       0  4949.6    0.05       0
Bank Sta=4936.9,4949.6
Exp/Cntr=0.3,0.1

Type RM Length L Ch R = 1,23266,916,916,916
BEGIN DESCRIPTION:
Brushy Creek 37.0
END DESCRIPTION:
XS GIS Cut Line= 4
      2616848.41      7008140.96      2616276.00      7008211.00
      2616064.54      7008346.69      2615314.88      7009736.69
#Sta/Elev= 30
  4423.4  527.99  4506.4  527.16  4566.9  524.43  4587.0  526.44  4597.1  526.44
  4617.2  523.64  4637.4  524.80  4758.3  524.48  4818.7  521.23  4969.9  519.21
  4979.9  518.30  4990.0  512.66  4991.2  508.26  4993.0  507.76  5003.9  508.26
  5065.2  511.54  5071.4  513.89  5080.4  515.15  5143.8  517.18  5599.3  517.87
  5697.4  519.71  5725.0  519.67  5746.9  518.50  5801.2  518.59  5866.9  520.81
  6249.6  524.14  6375.3  526.06  6413.4  525.77  6462.9  527.38  6830.6  531.07
#Mann=3,-1,0
  4423.4    0.05       0  4991.2    0.04       0  5003.9    0.05       0
Bank Sta=4991.2,5003.9
Exp/Cntr=0.3,0.1

Type RM Length L Ch R = 1,22350,466,466,466
BEGIN DESCRIPTION:
Brushy Creek 35.0
END DESCRIPTION:
XS GIS Cut Line= 3
      2616976.02      7007511.00      2615976.00      7007511.00
      2614775.98      7007611.00
#Sta/Elev= 30
  3999.9  528.69  4169.9  525.46  4199.9  525.87  4239.9  523.56  4259.9  524.08
  4309.9  521.61  4359.9  522.79  4479.9  522.09  4569.9  517.92  4659.9  518.13
  4789.9  515.95  4879.9  516.57  4959.9  512.75  4989.9  509.82  5013.3  506.04
  5015.2  505.54  5026.6  506.04  5030.0  508.74  5057.6  514.48  5080.2  515.66
  5140.4  514.95  5539.3  522.54  5632.1  523.41  5659.7  525.06  5722.4  525.45
  5780.1  527.62  5943.2  530.74  6003.4  534.19  6073.6  534.34  6204.1  540.39
#Mann=3,-1,0
  3999.9    0.05       0  5013.3    0.04       0  5026.6    0.05       0
Bank Sta=5013.3,5026.6
Exp/Cntr=0.3,0.1

Type RM Length L Ch R = 1,21884,761,761,761
BEGIN DESCRIPTION:
Brushy Creek 34.0
END DESCRIPTION:
XS GIS Cut Line= 3
      2616825.97      7007460.98      2616026.00      7007061.00
      2615226.02      7007161.00
#Sta/Elev= 30
  4105.6  526.73  4136.3  524.25  4150.3  525.02  4270.5  522.53  4387.9  523.55
  4455.0  522.84  4561.2  517.41  4642.2  518.25  4695.3  517.10  4784.8  516.74
  4835.1  515.00  4946.9  513.71  4955.3  511.89  4963.7  508.71  4969.2  508.47
  4977.6  506.30  4985.0  505.33  4986.9  504.83  4998.3  505.33  5010.1  508.39
  5020.1  512.60  5037.8  513.72  5151.2  513.59  5181.4  514.96  5251.9  515.75
  5284.7  517.04  5352.7  516.35  5463.6  517.23  5745.8  523.64  5806.2  527.14
#Mann=3,-1,0
  4105.6    0.05       0  4985.0    0.04       0  4998.3    0.05       0
Bank Sta=4985,4998.3
Exp/Cntr=0.3,0.1

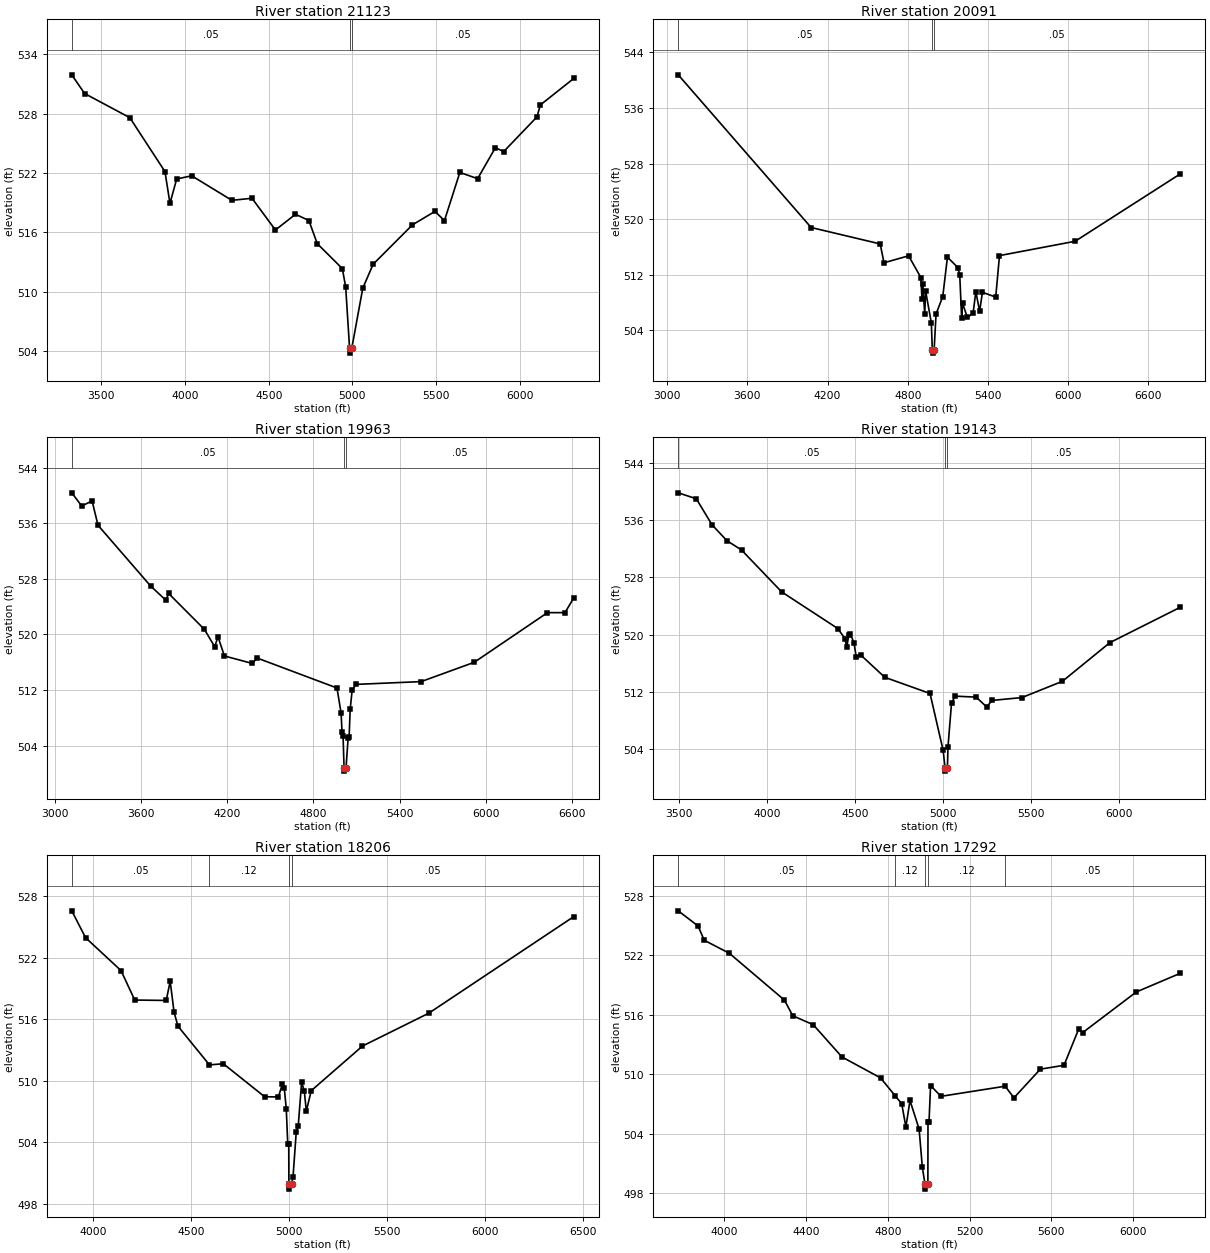
Type RM Length L Ch R = 1,21123,1032,1032,1032
BEGIN DESCRIPTION:
Mapping XS fe02fb8b
END DESCRIPTION:
XS GIS Cut Line= 4
      2617652.75      7006502.11      2615981.69      7006476.07
      2615569.37      7006580.24      2614966.05      7007253.00
#Sta/Elev= 30
  3323.0  531.93  3399.8  530.04  3669.8  527.60  3879.8  522.15  3909.8  518.93
  3949.8  521.40  4039.8  521.72  4279.9  519.24  4399.9  519.45  4539.9  516.24
  4659.9  517.83  4739.9  517.20  4789.9  514.86  4939.9  512.34  4959.9  510.46
  4983.0  504.29  4984.9  503.79  4996.3  504.29  5062.0  510.36  5123.9  512.78
  5358.7  516.76  5493.2  518.12  5550.0  517.19  5642.0  522.06  5748.1  521.43
  5854.3  524.56  5904.1  524.17  6102.5  527.67  6123.4  528.89  6323.2  531.57
#Mann=3,-1,0
  3323.0    0.05       0  4983.0    0.04       0  4996.3    0.05       0
Bank Sta=4983,4996.3
Exp/Cntr=0.3,0.1

Type RM Length L Ch R = 1,20091,128,128,128
BEGIN DESCRIPTION:
Mapping XS 2ce8ca43
END DESCRIPTION:
XS GIS Cut Line= 6
      2617993.38      7005232.21      2617012.51      7004997.85
      2616331.08      7005588.12      2616031.61      7005926.66
      2615969.55      7005990.73      2614896.54      7005245.34
#Sta/Elev= 30
  3082.4  540.75  4077.0  518.80  4593.8  516.44  4622.4  513.73  4806.6  514.73
  4898.7  511.59  4906.4  508.58  4913.0  510.62  4927.2  506.32  4933.8  509.68
  4976.6  505.09  4983.9  501.24  4985.9  500.74  4997.7  501.24  5012.0  506.36
  5062.2  508.88  5097.3  514.54  5175.1  513.04  5189.3  511.97  5203.5  505.74
  5210.2  507.91  5246.2  505.88  5288.9  506.45  5309.7  509.56  5338.2  506.77
  5359.1  509.49  5458.5  508.79  5486.8  514.76  6052.8  516.82  6840.1  526.51
#Mann=3,-1,0
  3082.4    0.05       0  4983.9    0.03       0  4997.7    0.05       0
Bank Sta=4983.9,4997.7
Exp/Cntr=0.3,0.1

Type RM Length L Ch R = 1,19963,820,820,820
BEGIN DESCRIPTION:
Mapping XS 59e969b0
END DESCRIPTION:
XS GIS Cut Line= 5
      2617993.44      7005206.19      2616960.42      7004954.44
      2616320.38      7005466.62      2615939.75      7005824.26
      2615010.34      7005252.47
#Sta/Elev= 30
  3117.0  540.39  3186.4  538.49  3258.5  539.23  3299.6  535.72  3665.9  526.98
  3773.1  524.91  3791.0  525.91  4040.7  520.73  4112.8  518.22  4135.0  519.68
  4180.0  516.90  4373.2  515.83  4408.4  516.60  4963.9  512.29  4992.7  508.67
  4999.1  505.93  5006.4  505.35  5013.2  500.82  5015.2  500.32  5027.0  500.82
  5041.6  505.08  5048.5  505.19  5055.8  509.22  5069.9  512.02  5098.3  512.81
  5550.2  513.21  5919.9  515.99  6429.9  523.14  6551.8  523.14  6613.5  525.28
#Mann=3,-1,0
  3117.0    0.05       0  5013.2    0.03       0  5027.0    0.05       0
Bank Sta=5013.2,5027
Exp/Cntr=0.3,0.1

Type RM Length L Ch R = 1,19143,937,937,937
BEGIN DESCRIPTION:
Brushy Creek 29.0
END DESCRIPTION:
XS GIS Cut Line= 3
      2617987.35      7005160.75      2616526.00      7004811.00
      2615176.02      7004811.00
#Sta/Elev= 30
  3497.4  539.83  3600.1  539.00  3689.3  535.36  3773.4  533.16  3857.5  531.83
  4084.9  525.99  4403.6  520.87  4444.8  519.46  4455.1  518.26  4466.7  520.03
  4475.6  520.12  4496.2  518.83  4508.8  516.87  4537.3  517.10  4671.0  514.05
  4928.0  511.79  5002.5  503.83  5013.1  501.44  5015.1  500.94  5026.9  501.44
  5030.0  504.32  5050.0  510.41  5070.0  511.42  5190.0  511.28  5250.0  509.91
  5280.0  510.82  5450.0  511.22  5680.0  513.49  5950.0  518.90  6350.0  523.84
#Mann=3,-1,0
  3497.4    0.05       0  5013.1    0.03       0  5026.9    0.05       0
Bank Sta=5013.1,5026.9
Exp/Cntr=0.3,0.1

Type RM Length L Ch R = 1,18206,914,914,914
BEGIN DESCRIPTION:
Brushy Creek 27.0
END DESCRIPTION:
XS GIS Cut Line= 3
      2617476.02      7004061.00      2616376.00      7004161.00
      2614952.60      7004473.25
#Sta/Elev= 30
  3891.5  526.60  3961.8  523.98  4142.6  520.77  4212.8  517.89  4373.5  517.85
  4393.6  519.72  4413.7  516.68  4433.7  515.33  4593.9  511.56  4664.7  511.67
  4875.6  508.45  4945.9  508.43  4965.9  509.67  4976.0  509.27  4986.0  507.26
  4993.5  503.88  4998.6  503.88  4999.3  499.93  5001.3  499.43  5013.2  499.93
  5020.5  500.64  5037.0  505.04  5047.2  505.64  5064.3  509.87  5078.0  509.01
  5088.2  507.05  5113.3  509.04  5374.9  513.40  5712.7  516.60  6453.3  526.04
#Mann=4,-1,0
  3891.5    0.05       0  4593.9    0.12       0  4999.3    0.07       0
  5013.2    0.05       0
Bank Sta=4999.3,5013.2
Exp/Cntr=0.3,0.1

Type RM Length L Ch R = 1,17292,1349,1349,1349
BEGIN DESCRIPTION:
Brushy Creek 26.0
END DESCRIPTION:
XS GIS Cut Line= 3
      2617642.31      7003329.49      2616426.00      7003461.00
      2615217.87      7003696.68
#Sta/Elev= 30
  3776.1  526.47  3873.0  524.94  3903.1  523.50  4025.8  522.19  4295.4  517.46
  4335.7  515.89  4436.2  514.98  4576.4  511.73  4765.0  509.62  4836.4  507.82
  4868.7  507.00  4888.9  504.67  4909.0  507.34  4953.6  504.45  4969.3  500.62
  4982.4  498.90  4984.4  498.40  4996.4  498.90  4997.0  505.21  5002.0  505.21
  5009.7  508.84  5060.6  507.76  5374.2  508.78  5417.2  507.61  5546.2  510.50
  5661.8  510.89  5733.1  514.52  5752.6  514.18  6015.6  518.29  6230.4  520.17
#Mann=5,-1,0
  3776.1    0.05       0  4836.4    0.12       0  4982.4    0.07       0
  4996.4    0.12       0  5374.2    0.05       0
Bank Sta=4982.4,4996.4
Exp/Cntr=0.3,0.1

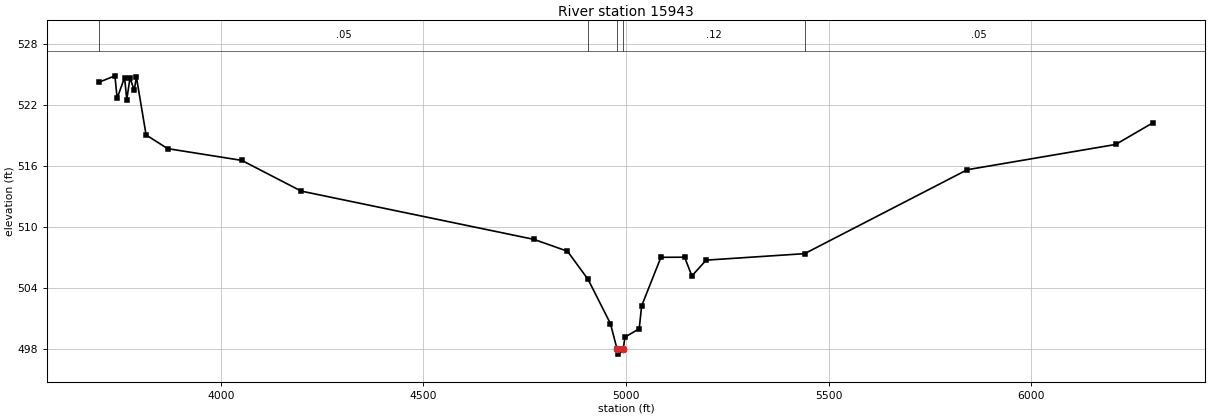
Type RM Length L Ch R = 1,15943,979,979,979
BEGIN DESCRIPTION:
Brushy Creek 24.0
END DESCRIPTION:
XS GIS Cut Line= 3
      2617426.00      7003061.00      2616226.00      7002561.00
      2615026.00      7002061.00
#Sta/Elev= 30
  3700.0  524.29  3738.5  524.91  3743.9  522.69  3762.3  524.74  3767.7  522.57
  3775.8  524.72  3786.1  523.47  3791.5  524.79  3815.4  519.08  3868.5  517.73
  4051.5  516.57  4198.3  513.54  4772.5  508.78  4855.4  507.61  4906.3  504.83
  4961.5  500.47  4977.8  497.96  4979.8  497.46  4993.0  497.96  4997.3  499.14
  5032.5  499.96  5038.5  502.22  5086.1  507.01  5144.6  507.02  5162.5  505.17
  5197.7  506.73  5440.7  507.37  5842.3  515.65  6208.5  518.14  6300.0  520.27
#Mann=5,-1,0
  3700.0    0.05       0  4906.3    0.12       0  4977.8    0.07       0
  4993.0    0.12       0  5440.7    0.05       0
Bank Sta=4977.8,4993
Exp/Cntr=0.3,0.1