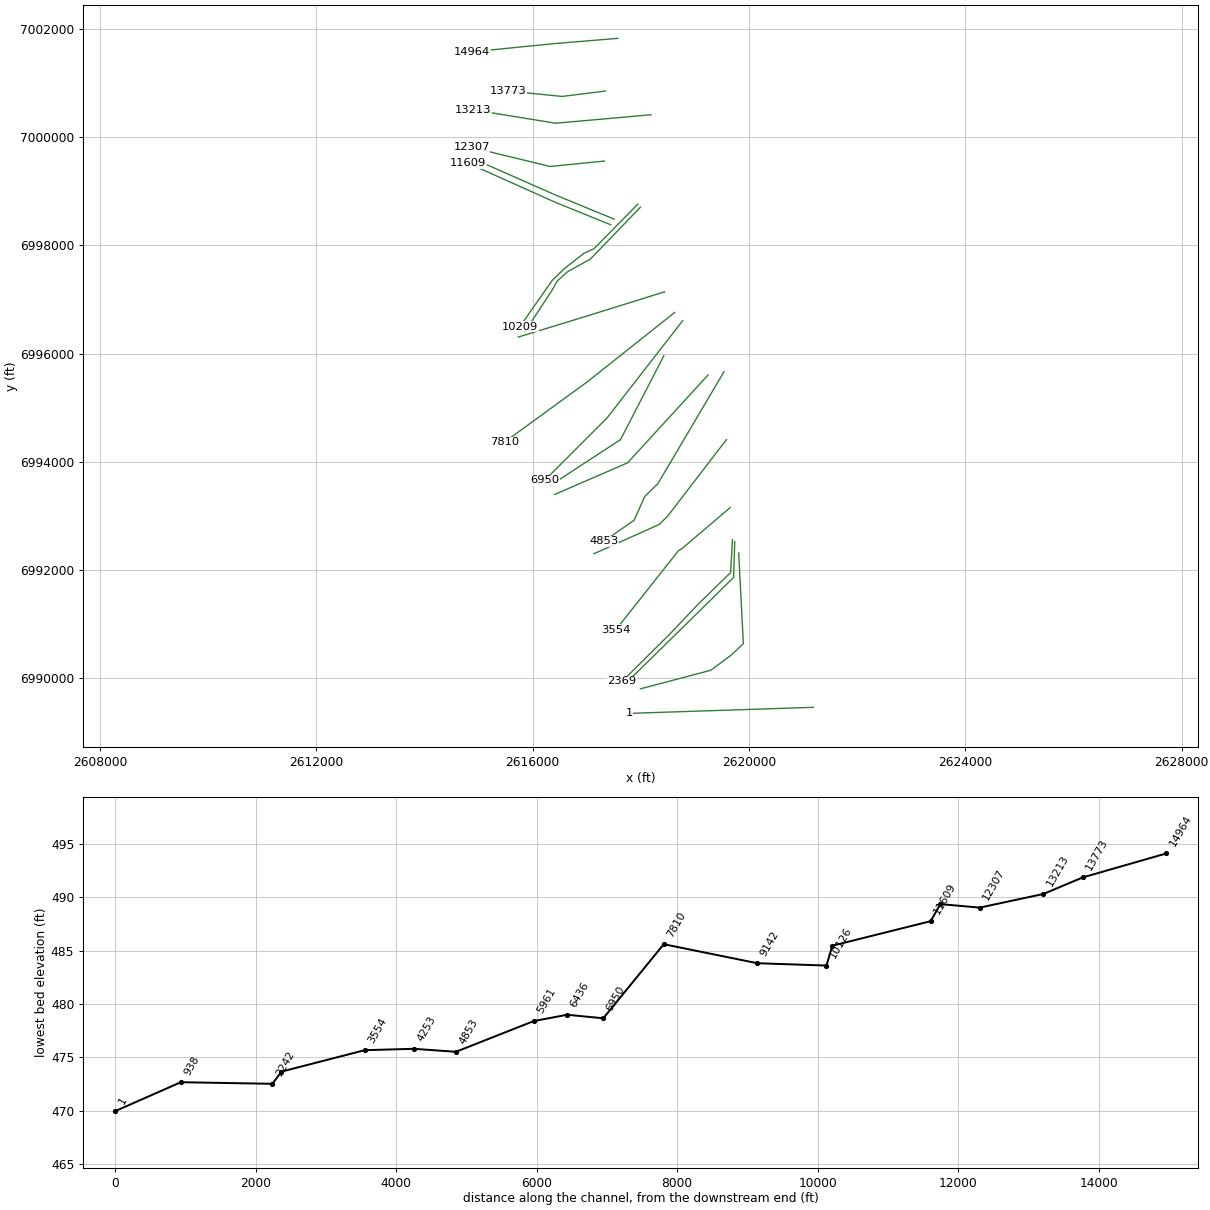
HEC-RAS study Brushy Creek.prj: Brushy Creek Base Level Engineering

--- Brushy Creek.g01 (geometry) --- (continued)

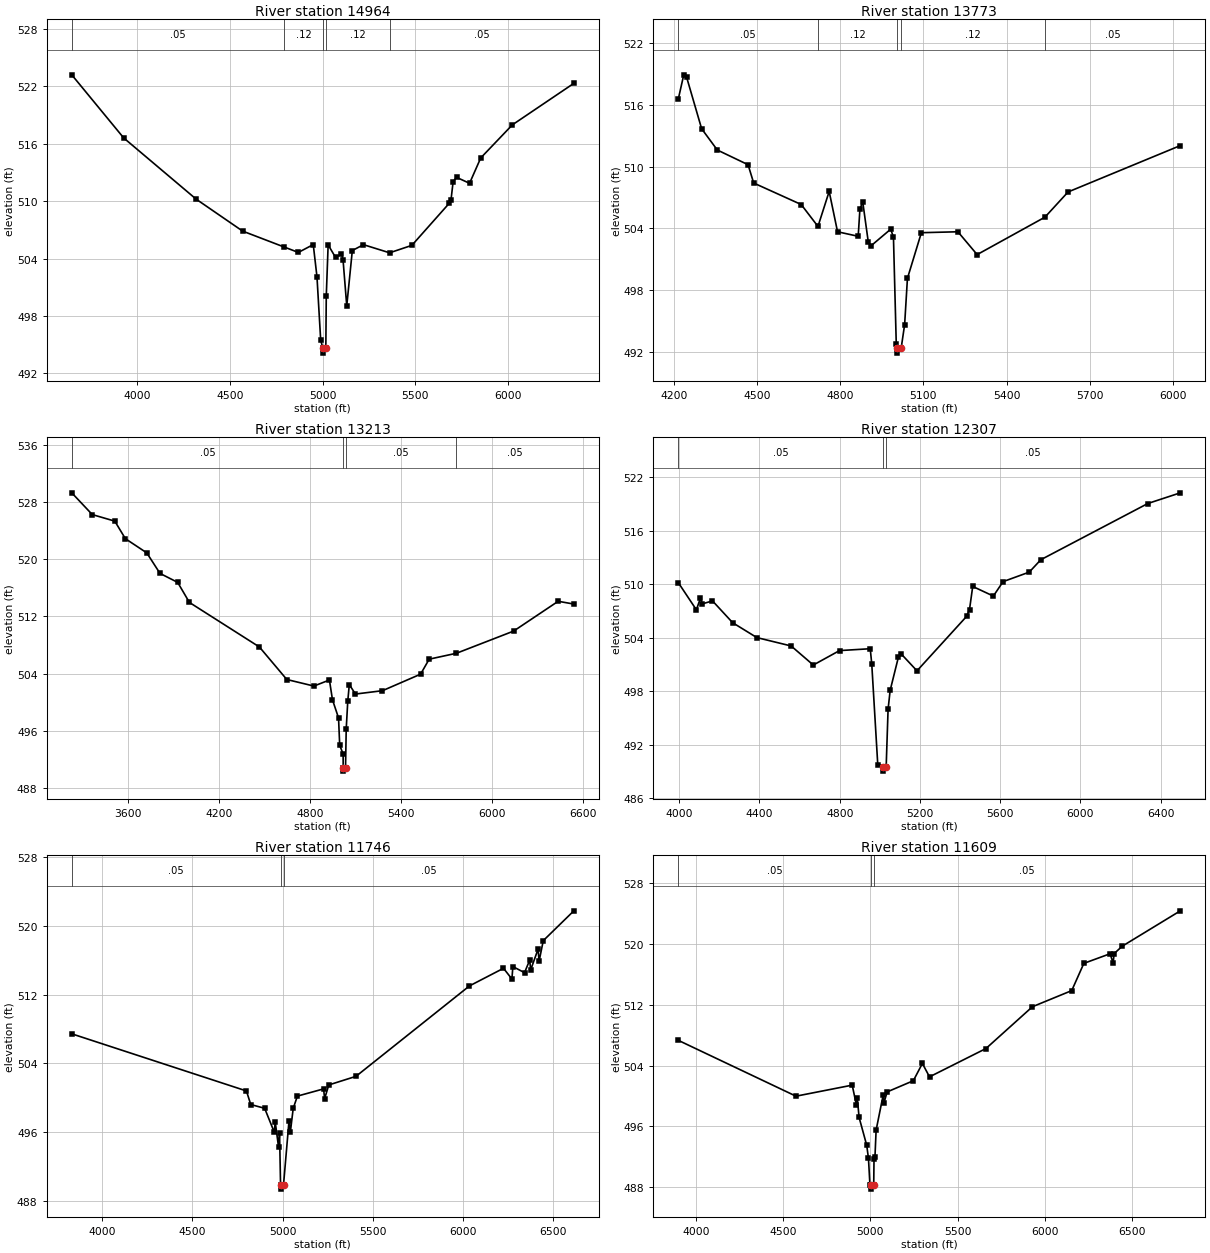
Type RM Length L Ch R = 1,14964,1191,1191,1191
BEGIN DESCRIPTION:
Brushy Creek 23.0
END DESCRIPTION:
XS GIS Cut Line= 3
      2617575.52      7001830.82      2616375.56      7001730.82
      2614875.57      7001580.82
#Sta/Elev= 30
  3645.2  523.21  3925.7  516.61  4317.0  510.21  4567.9  506.87  4792.9  505.20
  4869.0  504.64  4949.4  505.46  4969.5  502.09  4989.6  495.46  5002.0  494.61
  5004.0  494.11  5017.3  494.61  5019.7  500.07  5029.8  505.43  5070.0  504.11
  5101.9  504.50  5110.2  503.89  5130.3  499.05  5160.4  504.84  5220.7  505.45
  5361.8  504.60  5482.0  505.38  5683.0  509.76  5693.1  510.09  5704.9  512.05
  5723.2  512.49  5793.6  511.87  5853.9  514.52  6024.7  517.98  6356.8  522.32
#Mann=5,-1,0
  3645.2    0.05       0  4792.9    0.12       0  5002.0    0.07       0
  5017.3    0.12       0  5361.8    0.05       0
Bank Sta=5002,5017.3
Exp/Cntr=0.3,0.1

Type RM Length L Ch R = 1,13773,560,560,560
BEGIN DESCRIPTION:
Brushy Creek 20.0
END DESCRIPTION:
XS GIS Cut Line= 3
      2617345.76      7000856.31      2616545.79      7000756.31
      2615547.36      7000856.16
#Sta/Elev= 30
  4216.6  516.54  4236.5  518.92  4246.6  518.71  4300.9  513.68  4357.4  511.61
  4468.3  510.18  4488.5  508.40  4659.8  506.31  4720.2  504.18  4760.6  507.58
  4790.8  503.66  4865.2  503.22  4871.4  505.85  4881.5  506.58  4901.6  502.66
  4911.7  502.30  4982.3  503.91  4992.3  503.14  5002.4  492.77  5004.8  492.36
  5006.8  491.86  5020.2  492.36  5032.6  494.64  5042.7  499.13  5092.9  503.57
  5224.6  503.66  5293.9  501.44  5538.3  505.08  5621.6  507.53  6026.2  512.04
#Mann=5,-1,0
  4216.6    0.05       0  4720.2    0.12       0  5004.8    0.07       0
  5020.2    0.12       0  5538.3    0.05       0
Bank Sta=5004.8,5020.2
Exp/Cntr=0.3,0.1

Type RM Length L Ch R = 1,13213,906,906,906
BEGIN DESCRIPTION:
Brushy Creek 18.0
END DESCRIPTION:
XS GIS Cut Line= 3
      2618188.72      7000417.69      2616426.00      7000261.00
      2614903.98      7000507.98
#Sta/Elev= 30
  3229.9  529.34  3365.1  526.29  3513.7  525.37  3583.4  522.91  3724.6  520.92
  3811.8  518.04  3928.5  516.78  4005.7  513.97  4467.5  507.72  4648.2  503.16
  4827.0  502.24  4929.3  503.09  4949.4  500.32  4989.5  497.77  4997.1  493.92
  5019.8  492.73  5020.0  490.81  5022.0  490.31  5035.6  490.81  5040.1  496.22
  5050.2  500.08  5060.4  502.45  5100.9  501.12  5279.3  501.59  5530.8  503.91
  5587.2  506.01  5767.1  506.84  6144.3  509.95  6438.1  514.13  6541.5  513.74
#Mann=4,-1,0
  3229.9    0.05       0  5020.0    0.03       0  5035.6    0.05       0
  5767.1    0.05       0
Bank Sta=5020,5035.6
Exp/Cntr=0.3,0.1

Type RM Length L Ch R = 1,12307,561,561,561
BEGIN DESCRIPTION:
Brushy Creek 16.0
END DESCRIPTION:
XS GIS Cut Line= 3
      2617325.99      6999561.00      2616326.00      6999461.00
      2614870.10      6999813.33
#Sta/Elev= 30
  3995.0  510.20  4085.4  507.14  4105.5  508.43  4115.6  507.81  4165.8  508.14
  4266.3  505.69  4386.9  504.02  4557.8  503.08  4668.3  500.94  4799.0  502.56
  4952.2  502.77  4959.8  501.03  4989.9  489.67  5015.4  489.53  5017.4  489.03
  5031.6  489.53  5041.1  495.97  5051.4  498.09  5092.6  501.83  5107.1  502.17
  5185.2  500.29  5432.1  506.39  5447.0  507.16  5463.0  509.76  5565.9  508.68
  5614.3  510.30  5744.9  511.37  5802.5  512.76  6335.8  519.07  6497.9  520.27
#Mann=3,-1,0
  3995.0    0.05       0  5015.4    0.04       0  5031.6    0.05       0
Bank Sta=5015.4,5031.6
Exp/Cntr=0.3,0.1

Type RM Length L Ch R = 1,11746,137,137,137
BEGIN DESCRIPTION:
Mapping XS 1a0c8998
END DESCRIPTION:
XS GIS Cut Line= 3
      2617508.13      6998487.15      2616426.04      6998932.35
      2614945.66      6999584.36
#Sta/Elev= 30
  3829.9  507.44  4799.7  500.79  4823.6  499.21  4900.9  498.77  4954.2  495.99
  4959.6  497.17  4978.2  494.23  4983.6  495.92  4989.1  489.86  4991.1  489.36
  5005.6  489.86  5036.1  497.32  5043.8  496.04  5059.4  498.76  5082.7  500.19
  5228.2  501.03  5233.7  499.89  5257.0  501.49  5407.9  502.49  6038.1  513.02
  6227.0  515.07  6273.7  513.82  6279.1  515.27  6343.7  514.56  6372.5  516.02
  6377.9  514.88  6419.1  517.31  6424.6  515.89  6447.9  518.29  6617.6  521.76
#Mann=3,-1,0
  3829.9    0.05       0  4989.1    0.03       0  5005.6    0.05       0
Bank Sta=4989.1,5005.6
Exp/Cntr=0.3,0.1

Type RM Length L Ch R = 1,11609,1400,1400,1400
BEGIN DESCRIPTION:
Mapping XS 19f1a636
END DESCRIPTION:
XS GIS Cut Line= 3
      2617445.68      6998382.97      2616425.81      6998795.66
      2614806.81      6999521.85
#Sta/Elev= 30
  3899.8  507.31  4574.0  499.97  4895.8  501.42  4919.9  498.82  4925.3  499.68
  4935.1  497.20  4978.9  493.52  4989.0  491.79  4997.2  488.36  5002.5  488.26
  5004.5  487.76  5019.0  488.26  5020.7  491.67  5026.2  492.02  5032.7  495.50
  5072.6  500.06  5078.1  499.13  5095.8  500.53  5245.8  502.00  5297.6  504.27
  5338.5  502.51  5661.7  506.23  5927.6  511.72  6152.7  513.84  6222.2  517.42
  6372.2  518.68  6389.9  517.47  6395.4  518.70  6441.7  519.67  6774.4  524.32
#Mann=3,-1,0
  3899.8    0.05       0  5002.5    0.05       0  5019.0    0.05       0
Bank Sta=5002.5,5019
Exp/Cntr=0.3,0.1

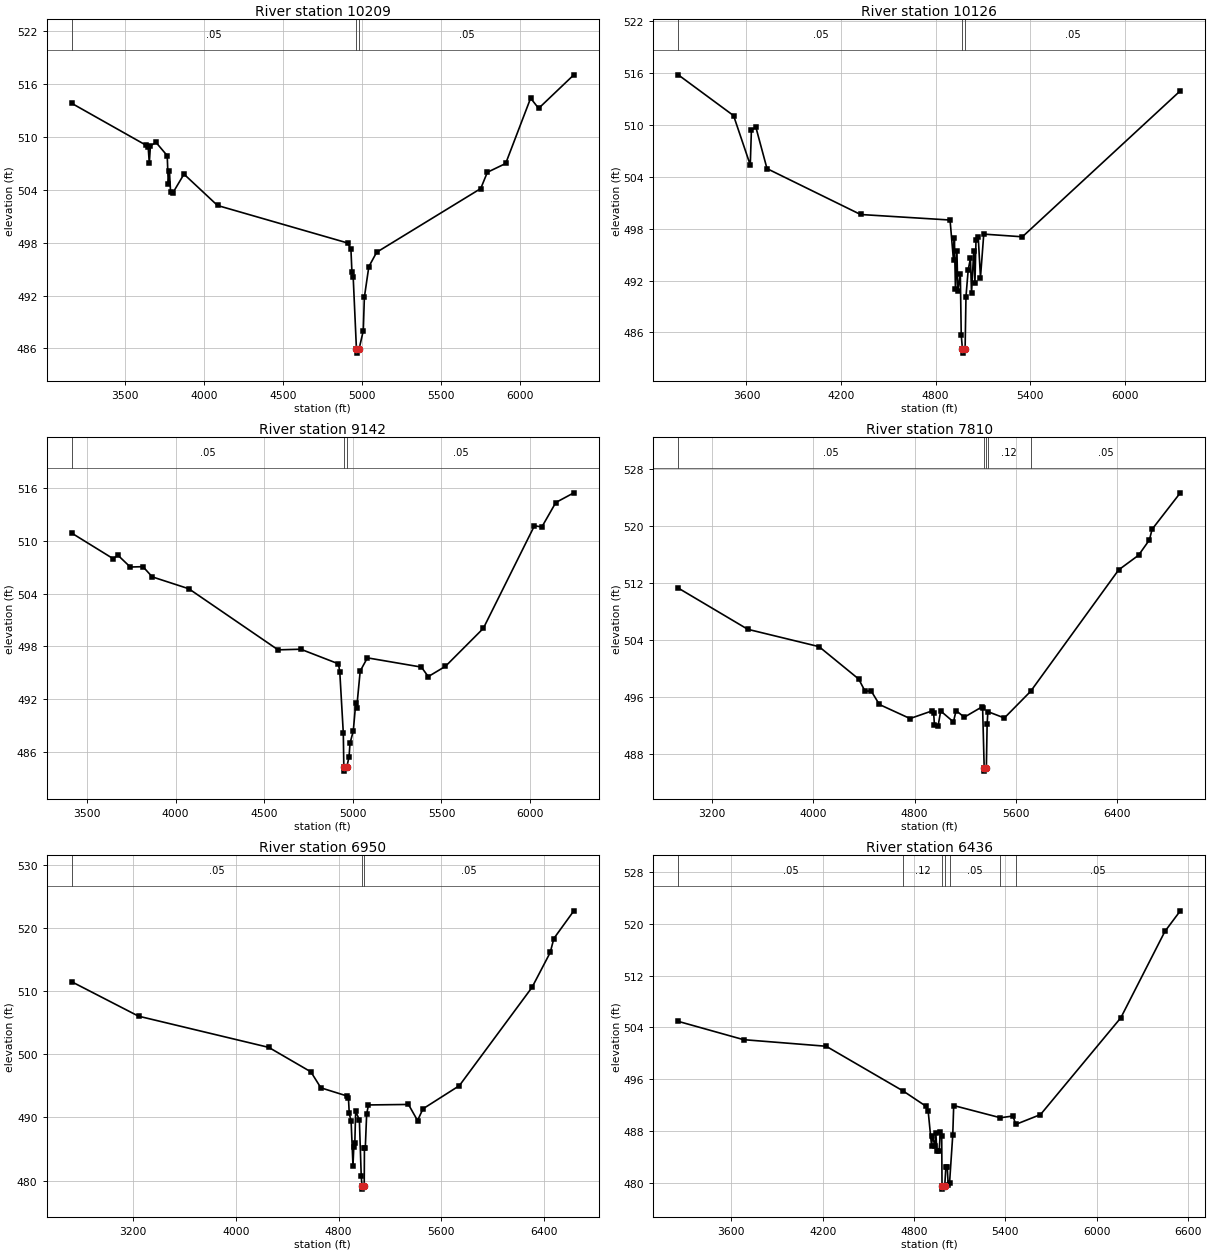
Type RM Length L Ch R = 1,10209,83,83,83
BEGIN DESCRIPTION:
Mapping XS 374a3e12
END DESCRIPTION:
XS GIS Cut Line= 6
      2617945.64      6998764.89      2617133.17      6997938.53
      2616948.35      6997855.53      2616584.56      6997570.47
      2616362.41      6997354.23      2615765.08      6996500.99
#Sta/Elev= 30
  3163.6  513.83  3632.7  509.08  3646.9  508.83  3654.0  507.04  3661.0  509.01
  3696.5  509.39  3767.2  507.89  3774.2  504.65  3781.3  506.17  3788.3  503.80
  3802.5  503.65  3873.2  505.79  4085.3  502.23  4908.1  497.97  4928.9  497.30
  4935.3  494.71  4943.4  494.08  4963.8  485.96  4965.8  485.46  4980.9  485.96
  5007.1  487.99  5014.1  491.82  5042.3  495.28  5091.9  496.92  5749.9  504.15
  5791.8  506.00  5907.7  507.00  6065.5  514.42  6116.1  513.26  6338.8  517.07
#Mann=3,-1,0
  3163.6    0.05       0  4963.8    0.03       0  4980.9    0.05       0
Bank Sta=4963.8,4980.9
Exp/Cntr=0.3,0.1

Type RM Length L Ch R = 1,10126,984,984,984
BEGIN DESCRIPTION:
Mapping XS 70357367
END DESCRIPTION:
XS GIS Cut Line= 6
      2617994.31      6998709.40      2617070.67      6997751.03
      2616647.06      6997514.92      2616452.61      6997341.31
      2616369.28      6997188.53      2615856.10      6996404.89
#Sta/Elev= 30
  3166.7  515.80  3518.0  511.08  3624.0  505.36  3631.2  509.40  3659.5  509.74
  3730.2  504.95  4324.2  499.64  4892.3  499.00  4914.2  494.33  4919.9  496.93
  4926.6  490.97  4935.9  495.46  4941.6  490.81  4957.6  492.71  4963.3  485.71
  4970.8  484.10  4972.8  483.60  4987.9  484.10  4993.4  490.14  5007.6  493.26
  5021.9  494.56  5028.6  490.53  5042.8  495.47  5050.3  491.70  5057.0  496.72
  5071.2  497.05  5085.4  492.34  5106.3  497.37  5351.5  497.06  6354.1  513.95
#Mann=3,-1,0
  3166.7    0.05       0  4970.8    0.03       0  4987.9    0.05       0
Bank Sta=4970.8,4987.9
Exp/Cntr=0.3,0.1

Type RM Length L Ch R = 1,9142,1332,1332,1332
BEGIN DESCRIPTION:
Mapping XS 10258761
END DESCRIPTION:
XS GIS Cut Line= 3
      2618439.48      6997143.20      2616925.55      6996671.19
      2615733.45      6996306.30
#Sta/Elev= 30
  3414.2  510.86  3648.3  507.95  3674.0  508.36  3744.3  507.01  3815.9  507.05
  3868.3  505.89  4074.6  504.54  4578.0  497.60  4706.2  497.67  4918.8  496.01
  4926.2  495.10  4946.1  488.14  4949.0  484.32  4951.0  483.82  4966.2  484.32
  4978.6  485.47  4983.8  486.97  5002.4  488.39  5016.5  491.60  5021.7  491.02
  5041.4  495.19  5082.0  496.69  5386.5  495.64  5425.4  494.56  5522.4  495.73
  5736.0  500.04  6024.4  511.70  6066.2  511.56  6145.0  514.34  6246.7  515.44
#Mann=3,-1,0
  3414.2    0.05       0  4949.0    0.03       0  4966.2    0.05       0
Bank Sta=4949,4966.2
Exp/Cntr=0.3,0.1

Type RM Length L Ch R = 1,7810,860,860,860
BEGIN DESCRIPTION:
Brushy Creek 7.0
END DESCRIPTION:
XS GIS Cut Line= 3
      2618625.99      6996760.99      2617009.43      6995477.71
      2615475.96      6994360.97
#Sta/Elev= 30
  2936.0  511.26  3484.7  505.48  4046.8  503.05  4359.5  498.51  4409.2  496.83
  4458.8  496.82  4522.9  494.94  4764.8  492.97  4936.3  494.03  4950.7  493.80
  4957.1  492.13  4985.9  491.92  5006.7  494.03  5107.1  492.50  5128.0  494.08
  5192.9  493.16  5328.9  494.57  5337.4  494.46  5349.6  486.10  5351.6  485.60
  5366.9  486.10  5372.9  492.14  5378.7  493.94  5508.9  493.05  5716.4  496.79
  6410.6  513.81  6567.4  515.86  6653.2  518.01  6674.3  519.50  6897.0  524.61
#Mann=5,-1,0
  2936.0    0.05       0  5349.6    0.03       0  5366.9    0.05       0
  5378.7    0.12       0  5716.4    0.05       0
Bank Sta=5349.6,5366.9
Exp/Cntr=0.3,0.1

Type RM Length L Ch R = 1,6950,514,514,514
BEGIN DESCRIPTION:
Brushy Creek 6.0
END DESCRIPTION:
XS GIS Cut Line= 3
      2618776.00      6996611.01      2617376.00      6994811.00
      2616226.00      6993661.00
#Sta/Elev= 30
  2724.3  511.47  3243.7  506.03  4257.2  501.09  4584.8  497.22  4662.6  494.69
  4862.6  493.42  4877.1  493.08  4883.4  490.66  4897.9  489.38  4912.4  482.39
  4918.7  485.25  4926.8  485.95  4933.2  490.98  4962.1  489.61  4976.6  480.78
  4982.2  479.16  4984.2  478.66  4999.9  479.16  5001.5  485.16  5008.2  485.16
  5018.8  490.53  5032.9  491.98  5344.1  492.06  5414.8  489.51  5457.2  491.37
  5740.0  495.03  6305.7  510.59  6447.2  516.11  6475.4  518.32  6631.0  522.70
#Mann=3,-1,0
  2724.3    0.05       0  4982.2    0.03       0  4999.9    0.05       0
Bank Sta=4982.2,4999.9
Exp/Cntr=0.3,0.1

Type RM Length L Ch R = 1,6436,475,475,475
BEGIN DESCRIPTION:
Brushy Creek 5.0
END DESCRIPTION:
XS GIS Cut Line= 3
      2618425.99      6995960.97      2617626.00      6994411.00
      2616325.97      6993560.98
#Sta/Elev= 30
  3251.3  504.94  3680.5  502.11  4223.1  501.09  4729.9  494.15  4876.5  491.84
  4893.0  491.01  4915.2  485.68  4920.8  487.28  4937.3  485.60  4943.0  487.71
  4950.5  484.82  4965.1  484.95  4973.0  487.88  4981.7  487.23  4983.8  479.49
  4985.8  478.99  5001.6  479.49  5009.1  482.44  5018.2  482.39  5024.2  479.68
  5033.0  479.87  5054.4  487.40  5060.4  491.92  5367.3  490.03  5449.6  490.30
  5467.8  489.00  5630.4  490.52  6158.2  505.50  6447.7  518.86  6548.8  522.04
#Mann=7,-1,0
  3251.3    0.05       0  4729.9    0.12       0  4983.8    0.07       0
  5001.6    0.12       0  5033.0    0.05       0  5367.3    0.12       0
  5467.8    0.05       0
Bank Sta=4983.8,5001.6
Exp/Cntr=0.3,0.1

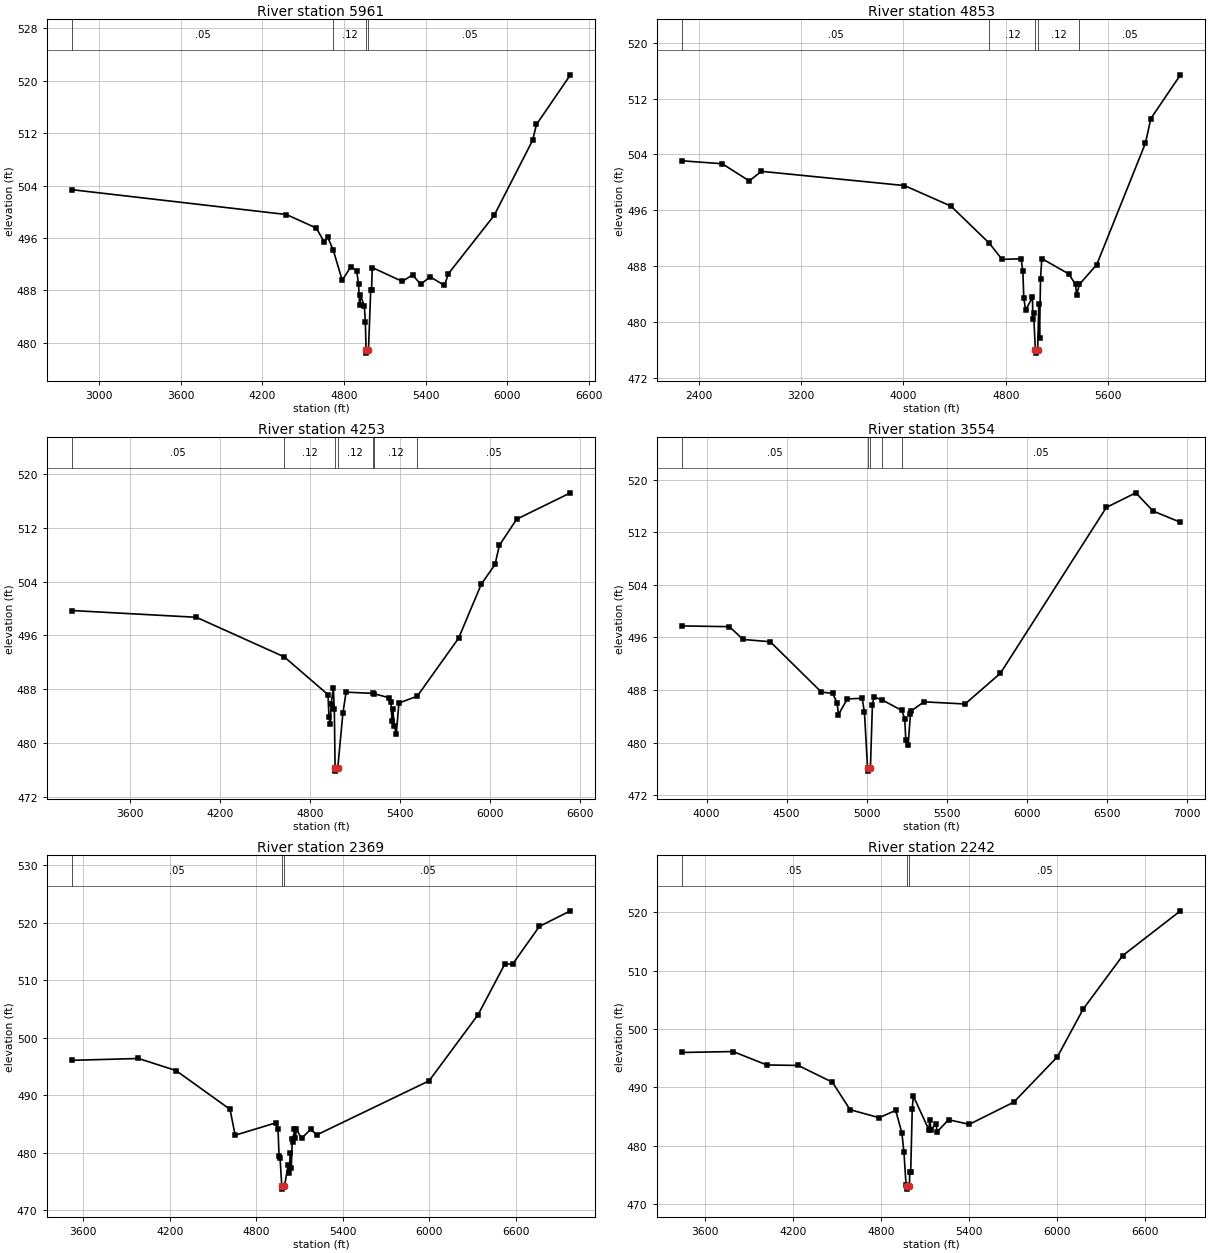
Type RM Length L Ch R = 1,5961,1108,1108,1108
BEGIN DESCRIPTION:
Brushy Creek 3.0
END DESCRIPTION:
XS GIS Cut Line= 3
      2619244.25      6995605.16      2617755.35      6993980.38
      2616411.02      6993396.89
#Sta/Elev= 30
  2796.2  503.37  4376.0  499.57  4595.5  497.51  4652.2  495.45  4680.6  496.08
  4721.6  494.08  4786.7  489.52  4850.2  491.60  4892.7  490.97  4906.9  488.99
  4914.3  485.80  4921.1  487.24  4949.5  485.57  4956.9  483.16  4962.1  478.90
  4964.1  478.40  4979.9  478.90  4996.2  488.01  5002.4  488.01  5007.9  491.47
  5228.2  489.36  5304.5  490.35  5363.6  488.92  5433.9  490.05  5538.7  488.74
  5567.6  490.53  5904.1  499.43  6186.8  510.89  6215.7  513.33  6465.5  520.91
#Mann=4,-1,0
  2796.2    0.05       0  4721.6    0.12       0  4962.1    0.03       0
  4979.9    0.05       0
Bank Sta=4962.1,4979.9
Exp/Cntr=0.3,0.1

Type RM Length L Ch R = 1,4853,600,600,600
BEGIN DESCRIPTION:
Mapping XS 8e7dac97
END DESCRIPTION:
XS GIS Cut Line= 5
      2619537.73      6995664.09      2618315.52      6993594.66
      2618072.46      6993358.55      2617878.02      6992921.05
      2617322.44      6992532.14
#Sta/Elev= 30
  2266.3  503.08  2583.5  502.66  2794.6  500.20  2890.2  501.57  4008.1  499.53
  4372.0  496.58  4672.2  491.25  4770.9  488.95  4919.6  489.04  4933.7  487.22
  4940.7  483.49  4954.8  481.67  5008.6  483.53  5011.8  480.39  5017.2  481.22
  5031.5  476.02  5033.5  475.52  5049.4  476.02  5058.3  482.63  5063.7  477.65
  5071.5  486.10  5081.5  489.07  5290.4  486.89  5345.1  485.39  5353.7  483.83
  5375.6  485.38  5510.8  488.19  5891.8  505.62  5933.7  509.13  6165.5  515.40
#Mann=5,-1,0
  2266.3    0.05       0  4672.2    0.12       0  5031.5    0.07       0
  5049.4    0.12       0  5375.6    0.05       0
Bank Sta=5031.5,5049.4
Exp/Cntr=0.3,0.1

Type RM Length L Ch R = 1,4253,699,699,699
BEGIN DESCRIPTION:
Mapping XS f65900ae
END DESCRIPTION:
XS GIS Cut Line= 4
      2619584.57      6994410.77      2618501.22      6993001.03
      2618341.50      6992841.31      2617133.16      6992299.64
#Sta/Elev= 30
  3211.4  499.70  4043.8  498.69  4629.9  492.80  4922.0  487.18  4928.3  483.85
  4936.5  482.76  4942.8  485.79  4957.4  488.16  4964.1  484.99  4969.2  476.30
  4971.2  475.80  4987.1  476.30  5021.3  484.44  5042.5  487.55  5221.8  487.37
  5226.4  487.34  5331.1  486.70  5341.8  486.04  5348.8  483.26  5354.3  484.99
  5363.7  482.55  5377.5  481.36  5395.2  485.94  5516.8  486.94  5793.5  495.59
  5944.5  503.62  6036.3  506.55  6065.1  509.40  6180.9  513.29  6539.4  517.21
#Mann=7,-1,0
  3211.4    0.05       0  4629.9    0.12       0  4969.2    0.07       0
  4987.1    0.12       0  5221.8    0.05       0  5226.4    0.12       0
  5516.8    0.05       0
Bank Sta=4969.2,4987.1
Exp/Cntr=0.3,0.1

Type RM Length L Ch R = 1,3554,1185,1185,1185
BEGIN DESCRIPTION:
Mapping XS 2beb512d
END DESCRIPTION:
XS GIS Cut Line= 4
      2619654.01      6993153.82      2618765.11      6992396.86
      2618695.67      6992355.19      2617535.95      6990889.92
#Sta/Elev= 30
  3843.9  497.76  4142.9  497.64  4227.4  495.70  4397.7  495.35  4717.2  487.69
  4787.5  487.49  4816.0  486.04  4823.7  484.27  4879.7  486.66  4972.0  486.74
  4986.2  484.66  5005.7  476.17  5007.7  475.67  5023.6  476.17  5036.0  485.66
  5045.4  486.94  5097.0  486.50  5219.5  484.90  5238.0  483.66  5244.7  480.42
  5259.1  479.58  5273.6  484.31  5279.9  484.85  5358.5  486.21  5614.9  485.88
  5836.1  490.56  6498.0  515.78  6682.3  518.00  6789.7  515.23  6961.1  513.52
#Mann=5,-1,0
  3843.9    0.05       0  5005.7    0.03       0  5023.6    0.05       0
  5097.0    0.12       0  5219.5    0.05       0
Bank Sta=5005.7,5023.6
Exp/Cntr=0.3,0.1

Type RM Length L Ch R = 1,2369,127,127,127
BEGIN DESCRIPTION:
Mapping XS 51648d9a
END DESCRIPTION:
XS GIS Cut Line= 5
      2619695.67      6992563.52      2619660.95      6991952.42
      2619056.78      6991362.14      2618535.95      6990813.53
      2617653.98      6989938.51
#Sta/Elev= 30
  3521.0  496.05  3984.3  496.37  4243.7  494.28  4618.4  487.53  4653.9  483.03
  4936.8  485.19  4950.9  484.12  4957.9  479.47  4964.9  479.05  4977.1  474.16
  4979.1  473.66  4995.2  474.16  5021.4  477.83  5028.6  476.45  5035.5  479.96
  5042.8  477.25  5049.7  482.38  5057.0  481.83  5063.9  484.17  5071.1  482.54
  5078.0  484.08  5113.6  482.48  5177.1  484.06  5219.6  483.09  5997.6  492.49
  6337.0  504.00  6520.9  512.74  6577.4  512.82  6761.3  519.33  6976.6  522.04
#Mann=3,-1,0
  3521.0    0.05       0  4977.1    0.04       0  4995.2    0.05       0
Bank Sta=4977.1,4995.2
Exp/Cntr=0.3,0.1

Type RM Length L Ch R = 1,2242,1304,1304,1304
BEGIN DESCRIPTION:
Mapping XS 36fc189a
END DESCRIPTION:
XS GIS Cut Line= 4
      2619737.33      6992521.83      2619716.50      6991862.14
      2619076.13      6991231.05      2617759.58      6989939.91
#Sta/Elev= 30
  3440.9  495.95  3791.9  496.11  4022.0  493.81  4236.4  493.73  4469.8  490.84
  4590.0  486.14  4788.0  484.77  4901.2  486.02  4943.6  482.14  4957.7  478.82
  4971.9  473.27  4977.0  473.02  4979.0  472.52  4995.1  473.02  4996.6  475.41
  5003.6  475.41  5014.2  486.29  5021.3  488.49  5127.4  482.72  5134.5  484.43
  5141.5  482.73  5176.9  483.71  5183.9  482.34  5261.8  484.42  5403.2  483.63
  5707.3  487.44  6004.3  495.21  6181.0  503.42  6449.8  512.56  6844.0  520.24
#Mann=3,-1,0
  3440.9    0.05       0  4977.0    0.04       0  4995.1    0.05       0
Bank Sta=4977,4995.1
Exp/Cntr=0.3,0.1

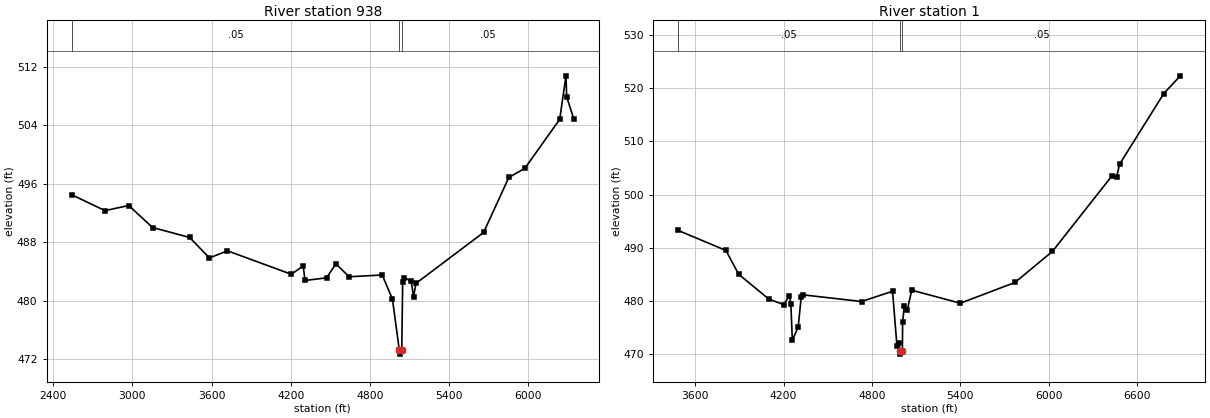
Type RM Length L Ch R = 1,938,937,937,937
BEGIN DESCRIPTION:
Mapping XS bf2a1f48
END DESCRIPTION:
XS GIS Cut Line= 5
      2619809.89      6992312.16      2619896.70      6990636.78
      2619671.00      6990424.10      2619292.05      6990143.95
      2617992.30      6989801.14
#Sta/Elev= 30
  2541.0  494.48  2792.5  492.31  2972.7  493.01  3153.0  490.00  3433.4  488.64
  3583.6  485.84  3720.4  486.81  4204.4  483.60  4293.9  484.74  4308.1  482.75
  4470.7  483.11  4541.8  485.03  4642.0  483.26  4892.5  483.50  4970.2  480.20
  5022.5  473.17  5024.5  472.67  5040.7  473.17  5047.6  482.60  5058.0  483.15
  5112.2  482.67  5130.4  480.47  5147.3  482.34  5660.8  489.33  5851.9  496.86
  5972.7  498.09  6237.0  504.80  6284.7  510.76  6289.9  507.88  6344.2  504.83
#Mann=3,-1,0
  2541.0    0.05       0  5022.5    0.04       0  5040.7    0.05       0
Bank Sta=5022.5,5040.7
Exp/Cntr=0.3,0.1

Type RM Length L Ch R = 1,1,0,0,0
BEGIN DESCRIPTION:
Mapping XS f5de2b56
END DESCRIPTION:
XS GIS Cut Line= 5
      2621189.97      6989459.49      2619690.34      6989410.16
      2619675.43      6989410.51      2619664.72      6989409.31
      2617783.76      6989347.44
#Sta/Elev= 30
  3484.7  493.24  3808.8  489.47  3894.4  485.00  4099.0  480.33  4201.6  479.27
  4239.1  480.97  4249.1  479.45  4259.1  472.56  4299.1  475.05  4319.1  480.68
  4329.1  481.12  4729.3  479.86  4939.5  481.79  4969.5  471.42  4984.8  472.05
  4988.2  470.45  4990.2  469.95  5006.4  470.45  5007.7  475.91  5019.6  479.09
  5039.6  478.30  5069.6  481.99  5399.8  479.54  5770.0  483.44  6024.6  489.29
  6430.3  503.57  6460.3  503.29  6480.3  505.71  6780.5  519.02  6892.8  522.36
#Mann=3,-1,0
  3484.7    0.05       0  4988.2    0.04       0  5006.4    0.05       0
Bank Sta=4988.2,5006.4
Exp/Cntr=0.3,0.1

Chan Stop Cuts=-1