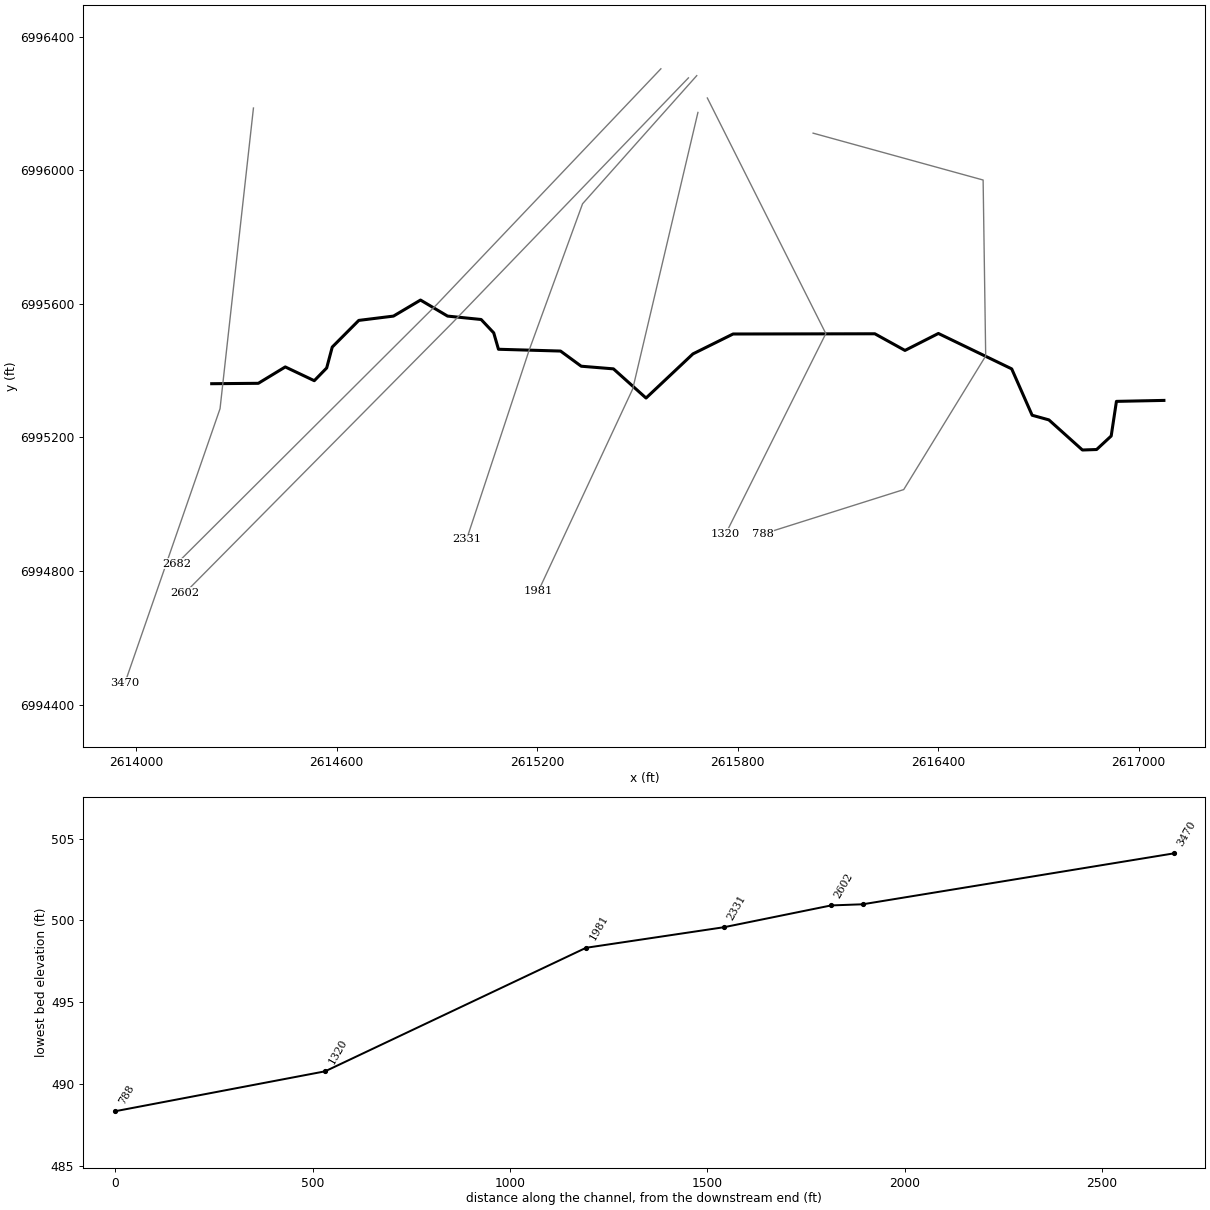
--- Brushy Creek Trib 1.prj (project) ---

Proj Title=Brushy Creek Trib 1 Base Level Engineering
Current Plan=p01
Default Exp/Contr=0.3,0.1
English Units
Geom File=g01
Flow File=f01
Plan File=p01
Y Axis Title=Elevation
X Axis Title(PF)=Main Channel Distance
X Axis Title(XS)=Station
BEGIN DESCRIPTION:
Brushy Creek Trib 1
END DESCRIPTION:
DSS Export Rating Curves= 0
DSS Export Rating Curve Sorted= 0
DSS Export Volume Flow Curves= 0
DXF OffsetX= 0
DXF OffsetY= 0
DXF ScaleX= 1
DXF ScaleY= 10

--- Brushy Creek Trib 1.p01 (plan) ---

Plan Title=Multiple Run
Short Identifier=Multiple
Geom File=g01
Flow File=f01
Subcritical Flow
K Sum by GR= 0
Std Step Tol= 0.01
Critical Tol= 0.01
Num of Std Step Trials= 20
Max Error Tol= 0.3
Flow Tol Ratio= 0.001
Split Flow NTrial= 30
Split Flow Tol= 0.02
Split Flow Ratio= 0.02
Log Output Level= 0
Friction Slope Method= 1
Unsteady Friction Slope Method= 2
Unsteady Bridges Friction Slope Method= 1
Parabolic Critical Depth
Global Vel Dist=  1 , 1 , 1
Global Log Level= 0
CheckData=True
Encroach Param= -1, 0, 0, 0
BEGIN DESCRIPTION:
Multiple Run
END DESCRIPTION:

--- Brushy Creek Trib 1.f01 (steady flow) ---

Flow Title=Multiple
Number of Profiles=7
Profile Names=10-year,25-year,50-year,1pct_min,100-year,1pct_plu,500-year
River Rch & RM= Brushy Creek Tri,Reach-1,3470
     612     825     998     600    1197    2388    1718
Boundary for River Rch & Prof#=Brushy Creek Tri,Reach-1,1
Up Type=0
Dn Type=3
Dn Slope=0.005
Boundary for River Rch & Prof#=Brushy Creek Tri,Reach-1,2
Up Type=0
Dn Type=3
Dn Slope=0.005
Boundary for River Rch & Prof#=Brushy Creek Tri,Reach-1,3
Up Type=0
Dn Type=3
Dn Slope=0.005
Boundary for River Rch & Prof#=Brushy Creek Tri,Reach-1,4
Up Type=0
Dn Type=3
Dn Slope=0.005
Boundary for River Rch & Prof#=Brushy Creek Tri,Reach-1,5
Up Type=0
Dn Type=3
Dn Slope=0.005
Boundary for River Rch & Prof#=Brushy Creek Tri,Reach-1,6
Up Type=0
Dn Type=3
Dn Slope=0.005
Boundary for River Rch & Prof#=Brushy Creek Tri,Reach-1,7
Up Type=0
Dn Type=3
Dn Slope=0.005

--- Brushy Creek Trib 1.g01 (geometry) ---

Geom Title=Existing Conditions
Program Version=4.10

River Reach=Brushy Creek Tri,Reach-1
Reach XY= 30
        2614226.        6995361.      2614365.52      6995362.19
      2614446.21      6995411.21      2614533.01      6995370.03
      2614570.15      6995408.16      2614586.77      6995470.67
      2614666.19      6995550.49      2614770.03      6995563.38
        2614851.       6995611.4      2614931.97      6995563.38
      2615032.43      6995553.21       2615070.1      6995513.18
      2615084.31       6995464.1      2615270.06      6995458.74
      2615331.98      6995413.36      2615428.43      6995405.45
        2615526.      6995318.08      2615666.32      6995450.24
       2615786.5       6995509.8      2616210.79      6995510.46
        2616301.      6995460.61        2616401.       6995511.4
      2616620.42      6995405.42      2616681.59      6995266.61
      2616731.74       6995252.7      2616832.09      6995162.57
      2616874.59        6995164.      2616918.23       6995204.5
       2616933.9      6995308.13        2617076.        6995311.

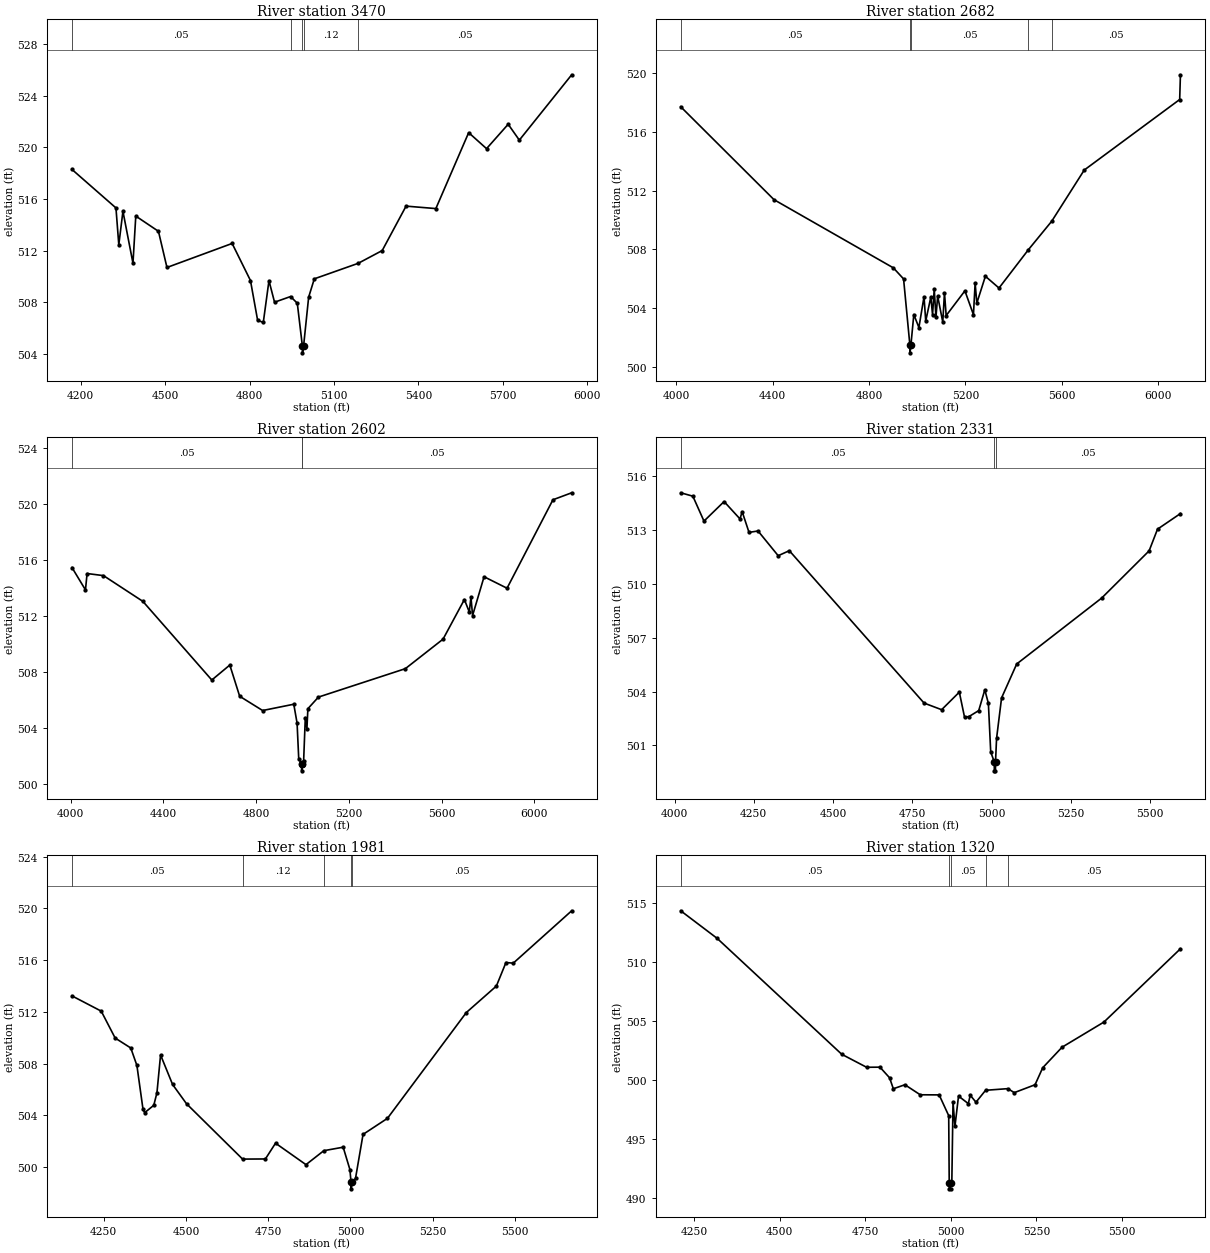
Type RM Length L Ch R = 1 ,3470    ,788,788,788
BEGIN DESCRIPTION:
Brushy Creek Trib 1 6.0
END DESCRIPTION:
XS GIS Cut Line= 3
      2614350.95      6996186.25      2614250.95      6995286.23
      2613966.26      6994465.35
#Sta/Elev= 30
  4169.6  518.29  4325.8  515.31  4335.9  512.46  4350.6  515.05  4386.2  511.03
  4396.2  514.68  4476.7   513.5  4506.9   510.7  4738.3  512.56  4803.4  509.69
  4828.9   506.6    4849  506.45  4869.1  509.68  4888.9  508.01  4945.9  508.45
  4969.7  507.93  4987.9  504.59  4988.1  504.09  4991.9  504.59    5010   508.4
  5030.1  509.82  5185.8  511.02  5271.2  512.01  5355.9  515.45  5461.7  515.26
  5578.2  521.14  5641.7   519.9  5718.5  521.79  5758.1  520.56    5944  525.62
#Mann= 5 ,-1 , 0
  4169.6     .05       0  4945.9     .12       0  4987.9     .07       0
  4991.9     .12       0  5185.8     .05       0
Bank Sta=4987.9,4991.9
XS Rating Curve= 0 ,0
Exp/Cntr=0.3,0.1

Type RM Length L Ch R = 1 ,2682    ,80,80,80
BEGIN DESCRIPTION:
Mapping XS 383aa6ab
END DESCRIPTION:
XS GIS Cut Line= 3
      2615570.43      6996303.66      2614900.17      6995598.69
       2614120.7      6994821.88
#Sta/Elev= 30
  4018.8  517.69  4405.9  511.38    4901  506.75  4943.4     506  4969.7  501.48
    4970  500.98  4973.7  501.48  4985.9  503.58    5007   502.7  5028.2  504.79
  5035.3  503.14  5056.5  504.77  5063.6  503.57  5070.6  505.32  5077.7  503.39
  5084.8  504.84    5106  503.07  5113.1  505.06  5120.1  503.51  5197.9  505.19
  5233.3  503.57  5240.3  505.71  5247.4  504.36  5282.8  506.18  5339.3  505.38
  5461.6  507.99  5558.2  509.92  5692.9  513.39  6088.9  518.18    6092  519.86
#Mann= 5 ,-1 , 0
  4018.8     .05       0  4969.7     .03       0  4973.7     .05       0
  5461.6     .12       0  5558.2     .05       0
Bank Sta=4969.7,4973.7
XS Rating Curve= 0 ,0
Exp/Cntr=0.3,0.1

Type RM Length L Ch R = 1 ,2602    ,271,271,271
BEGIN DESCRIPTION:
Mapping XS d53dfa2b
END DESCRIPTION:
XS GIS Cut Line= 3
      2615652.84      6996276.45      2614945.17      6995542.08
      2614146.94      6994735.83
#Sta/Elev= 30
  4006.3  515.44  4064.5  513.84  4071.5  515.01  4142.2  514.86    4312  513.02
  4609.2   507.4  4686.8  508.47  4729.3  506.24  4828.3  505.22  4962.6  505.67
  4976.8  504.32    4984  501.76  4996.1  501.41  4996.4  500.91  5000.1  501.41
  5005.1  501.64  5012.3  504.72  5019.2  503.91  5023.4  505.35  5068.8  506.18
  5443.5  508.21  5606.1  510.32  5698.1  513.15  5719.3  512.26  5726.4  513.33
  5733.4  512.01    5783  514.78    5882  513.96  6079.9  520.28  6160.7  520.78
#Mann= 3 ,-1 , 0
  4006.3     .05       0  4996.1     .03       0  5000.1     .05       0
Bank Sta=4996.1,5000.1
XS Rating Curve= 0 ,0
Exp/Cntr=0.3,0.1

Type RM Length L Ch R = 1 ,2331    ,350,350,350
BEGIN DESCRIPTION:
Brushy Creek Trib 1 4.0
END DESCRIPTION:
XS GIS Cut Line= 4
      2615677.72      6996283.15      2615335.96      6995899.55
        2615176.        6995461.      2614988.99      6994895.28
#Sta/Elev= 30
  4019.4  515.09  4057.7   514.9  4092.8  513.51  4156.3   514.6  4206.5  513.63
  4213.2  514.04  4234.9  512.88  4263.3  512.96  4326.9  511.58    4362  511.86
  4787.1  503.36  4842.5  502.99  4898.3  503.97  4914.8  502.57  4928.9  502.61
  4959.5  502.94  4978.7   504.1    4990  503.34  4997.3  500.64  5008.5  500.08
  5008.8  499.58  5012.3  499.58  5012.5  500.08  5015.8  501.39  5031.6  503.65
  5079.3  505.54  5347.5  509.22    5497  511.85  5523.5  513.06  5595.8  513.93
#Mann= 3 ,-1 , 0
  4019.4     .05       0  5008.5    .035       0  5012.5     .05       0
Bank Sta=5008.5,5012.5
XS Rating Curve= 0 ,0
Exp/Cntr=0.3,0.1

Type RM Length L Ch R = 1 ,1981    ,661,661,661
BEGIN DESCRIPTION:
Mapping XS 27d78c03
END DESCRIPTION:
XS GIS Cut Line= 3
      2615681.27      6996172.99      2615486.18      6995345.52
      2615203.63      6994740.06
#Sta/Elev= 30
  4153.8  513.24  4242.7  512.06    4285  509.98  4332.5  509.21  4351.1  507.86
  4369.7  504.46  4374.8  504.21  4402.4  504.78    4412  505.75    4423  508.67
  4459.5  506.39  4501.8   504.9  4672.2  500.62  4741.5  500.63  4772.3  501.85
  4864.8  500.19    4919  501.27  4977.8  501.54  4998.3  499.81  5001.7  498.82
    5002  498.32  5005.7  498.82  5015.3  499.13  5038.2  502.53  5112.3  503.77
  5351.9  511.95  5443.3     514  5472.4  515.82  5494.6  515.77  5672.1  519.82
#Mann= 5 ,-1 , 0
  4153.8     .05       0  4672.2     .12       0    4919     .05       0
  5001.7     .03       0  5005.7     .05       0
Bank Sta=5001.7,5005.7
XS Rating Curve= 0 ,0
Exp/Cntr=0.3,0.1

Type RM Length L Ch R = 1 ,1320    ,532,532,532
BEGIN DESCRIPTION:
Brushy Creek Trib 1 2.0
END DESCRIPTION:
XS GIS Cut Line= 3
      2615709.45      6996216.27      2616064.11      6995511.04
      2615764.12      6994911.05
#Sta/Elev= 30
  4210.6  514.33  4317.2  511.99  4681.2  502.17  4753.8  501.07  4792.8  501.08
  4820.9  500.18  4831.9  499.25  4865.7  499.59  4910.5  498.74  4965.8  498.73
  4993.7  496.97  4995.2  491.27  4995.5  490.77    4999  490.77  4999.2  491.27
  5002.8  491.27  5006.3  498.12  5011.9  496.06  5022.4  498.63    5051  497.99
  5056.6   498.7  5073.4  498.11  5101.5  499.12  5166.7  499.26  5185.2  498.92
    5246  499.59  5268.4  501.03  5324.9  502.77  5447.2   504.9  5670.8  511.11
#Mann= 5 ,-1 , 0
  4210.6     .05       0  4995.2     .07       0  4999.2     .05       0
  5101.5     .12       0  5166.7     .05       0
Bank Sta=4995.2,4999.2
XS Rating Curve= 0 ,0
Exp/Cntr=0.3,0.1

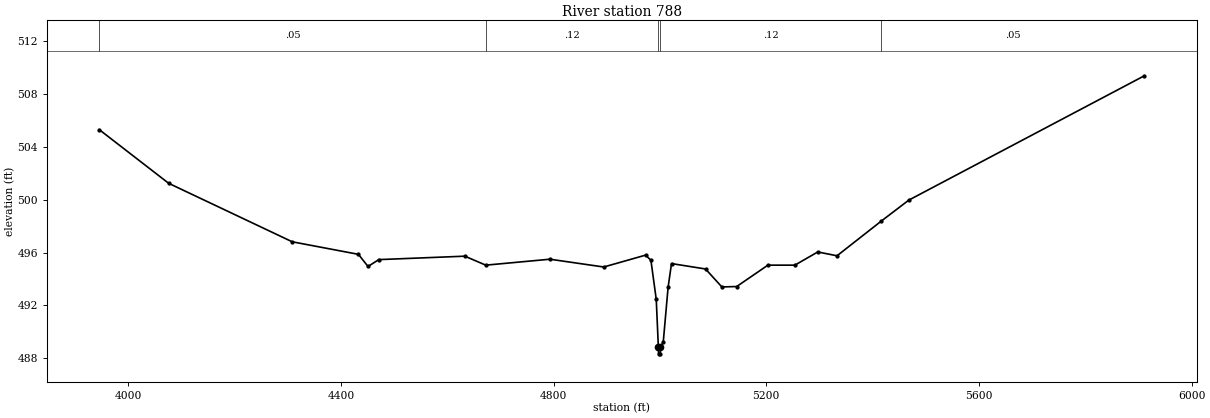
Type RM Length L Ch R = 1 ,788     ,0,0,0
BEGIN DESCRIPTION:
Brushy Creek Trib 1 1.0
END DESCRIPTION:
XS GIS Cut Line= 5
      2616026.01        6996111.      2616534.89       6995970.7
       2616542.6      6995444.02      2616297.23      6995044.08
      2615875.96      6994910.99
#Sta/Elev= 30
  3945.4  505.32  4076.1  501.25  4308.4  496.82  4432.9  495.87  4450.9  494.95
  4471.2  495.47    4633  495.73  4672.4  495.05    4793   495.5  4894.3  494.91
    4973  495.81    4983  495.42    4993  492.46    4997  488.83  4997.3  488.33
  5000.8  488.33    5001  488.83  5006.2  489.23  5015.3  493.37  5021.7  495.17
  5085.7  494.76  5116.4   493.4  5144.3  493.43    5203  495.05  5253.7  495.05
  5296.8  496.05    5333  495.76  5416.6   498.4  5468.1  499.98    5911   509.4
#Mann= 5 ,-1 , 0
  3945.4     .05       0  4672.4     .12       0    4997     .07       0
    5001     .12       0  5416.6     .05       0
Bank Sta=4997,5001
XS Rating Curve= 0 ,0
Exp/Cntr=0.3,0.1

Chan Stop Cuts=-1
Use User Specified Reach Order=0
Composite Channel Slope=5