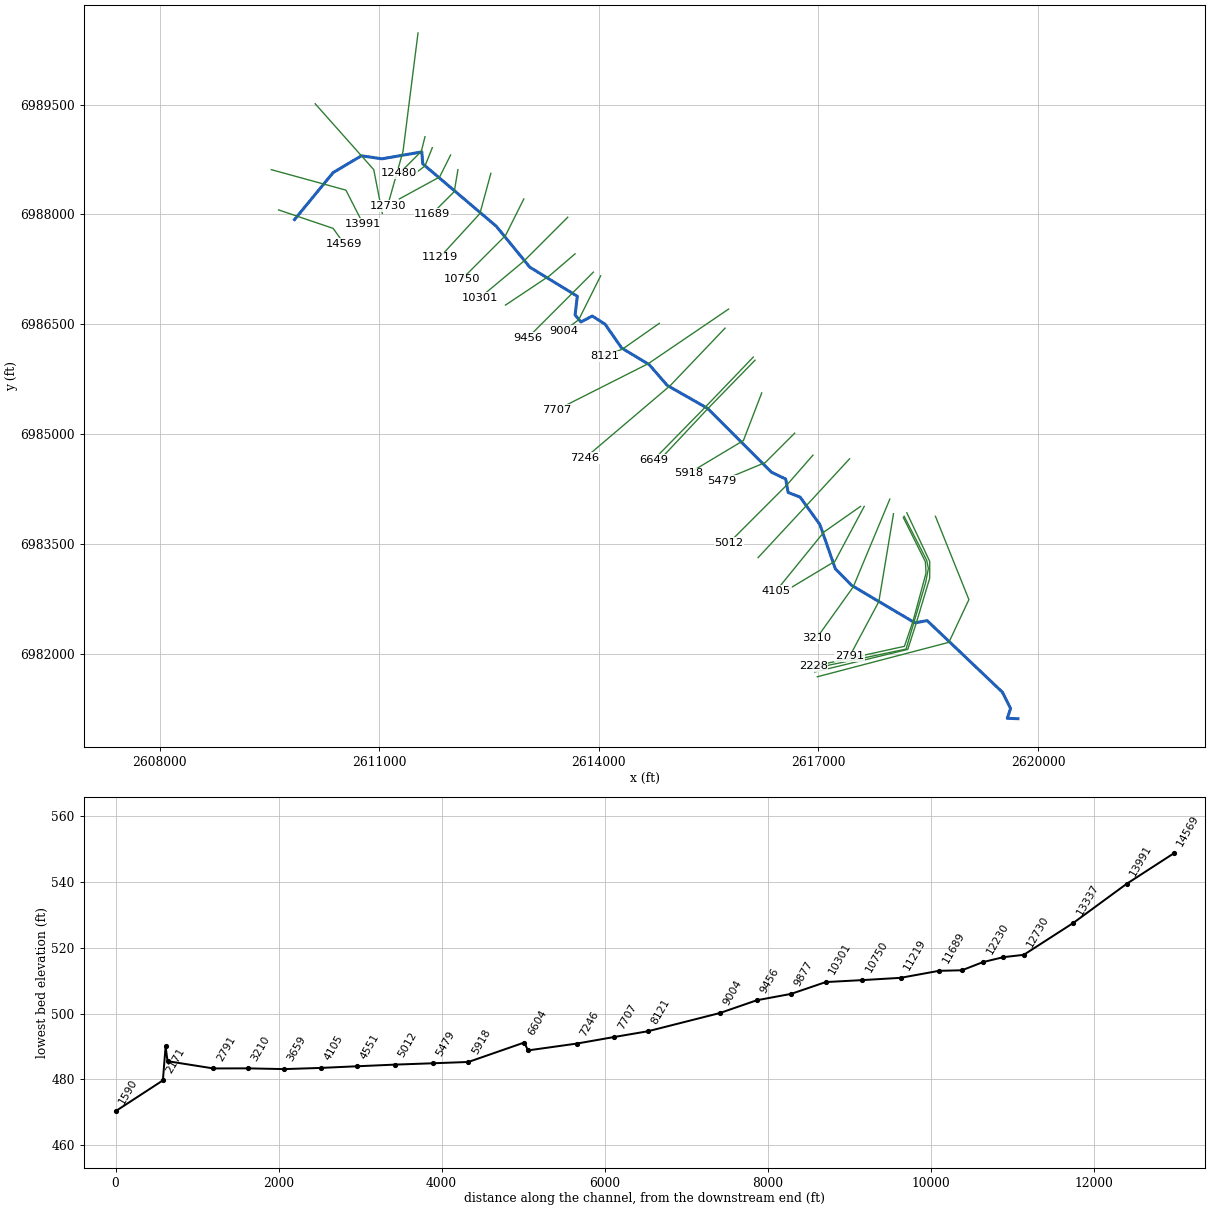
--- Brushy Creek Trib 2.prj (project) ---

Proj Title=Brushy Creek Trib 2 Base Level Engineering
Current Plan=p01
Default Exp/Contr=0.3,0.1
English Units
Geom File=g01
Flow File=f01
Plan File=p01
BEGIN DESCRIPTION:
Brushy Creek Trib 2
END DESCRIPTION:

--- Brushy Creek Trib 2.p01 (plan) ---

Plan Title=Multiple Run
Short Identifier=Multiple
Geom File=g01
Flow File=f01
Subcritical Flow
K Sum by GR= 0
Std Step Tol= 0.01
Critical Tol= 0.01
Num of Std Step Trials= 20
Max Error Tol= 0.3
Flow Tol Ratio= 0.001
Split Flow NTrial= 30
Split Flow Tol= 0.02
Split Flow Ratio= 0.02
Log Output Level= 0
Friction Slope Method= 1
Unsteady Friction Slope Method= 2
Unsteady Bridges Friction Slope Method= 1
Parabolic Critical Depth
Global Vel Dist=  1 , 1 , 1
Global Log Level= 0
CheckData=True
Encroach Param= -1, 0, 0, 0
BEGIN DESCRIPTION:
Multiple Run
END DESCRIPTION:

--- Brushy Creek Trib 2.f01 (steady flow) ---

Flow Title=Multiple
Number of Profiles=7
Profile Names=10-year,25-year,50-year,1pct_min,100-year,1pct_plu,500-year
River Rch & RM= Brushy Creek Tri,Reach-1,14569
     442     582     694     411     820    1637    1144
River Rch & RM= Brushy Creek Tri,Reach-1,10750
     710     962    1168     703    1403    2800    2023
River Rch & RM= Brushy Creek Tri,Reach-1,5918
     794    1077    1308     787    1570    3133    2262
River Rch & RM= Brushy Creek Tri,Reach-1,2204
     939    1289    1579     958    1911    3813    2800
Boundary for River Rch & Prof#=Brushy Creek Tri,Reach-1,1
Up Type=0
Dn Type=3
Dn Slope=0.005
Boundary for River Rch & Prof#=Brushy Creek Tri,Reach-1,2
Up Type=0
Dn Type=3
Dn Slope=0.005
Boundary for River Rch & Prof#=Brushy Creek Tri,Reach-1,3
Up Type=0
Dn Type=3
Dn Slope=0.005
Boundary for River Rch & Prof#=Brushy Creek Tri,Reach-1,4
Up Type=0
Dn Type=3
Dn Slope=0.005
Boundary for River Rch & Prof#=Brushy Creek Tri,Reach-1,5
Up Type=0
Dn Type=3
Dn Slope=0.005
Boundary for River Rch & Prof#=Brushy Creek Tri,Reach-1,6
Up Type=0
Dn Type=3
Dn Slope=0.005
Boundary for River Rch & Prof#=Brushy Creek Tri,Reach-1,7
Up Type=0
Dn Type=3
Dn Slope=0.005

--- Brushy Creek Trib 2.g01 (geometry) ---

Geom Title=Existing Conditions

River Reach=Brushy Creek Tri,Reach-1
Reach XY= 30
      2609843.76      6987928.85      2610370.79      6988570.51
      2610757.58      6988800.47      2611038.01      6988758.93
      2611582.84      6988853.20      2611595.27      6988690.53
      2612599.47      6987837.98      2613059.25      6987277.46
      2613706.77      6986881.57      2613676.37      6986626.15
      2613755.95      6986530.19      2613910.64      6986611.10
      2614085.70      6986500.23      2614312.44      6986174.49
      2614689.24      6985947.39      2614934.49      6985664.54
      2615485.68      6985350.22      2616359.29      6984477.63
      2616553.30      6984384.90      2616586.33      6984200.83
      2616749.86      6984138.17      2617020.16      6983763.29
      2617231.52      6983158.57      2617455.91      6982930.79
      2618319.26      6982420.13      2618485.79      6982450.56
      2619512.38      6981474.21      2619625.24      6981250.31
      2619580.52      6981116.12      2619726.00      6981111.00

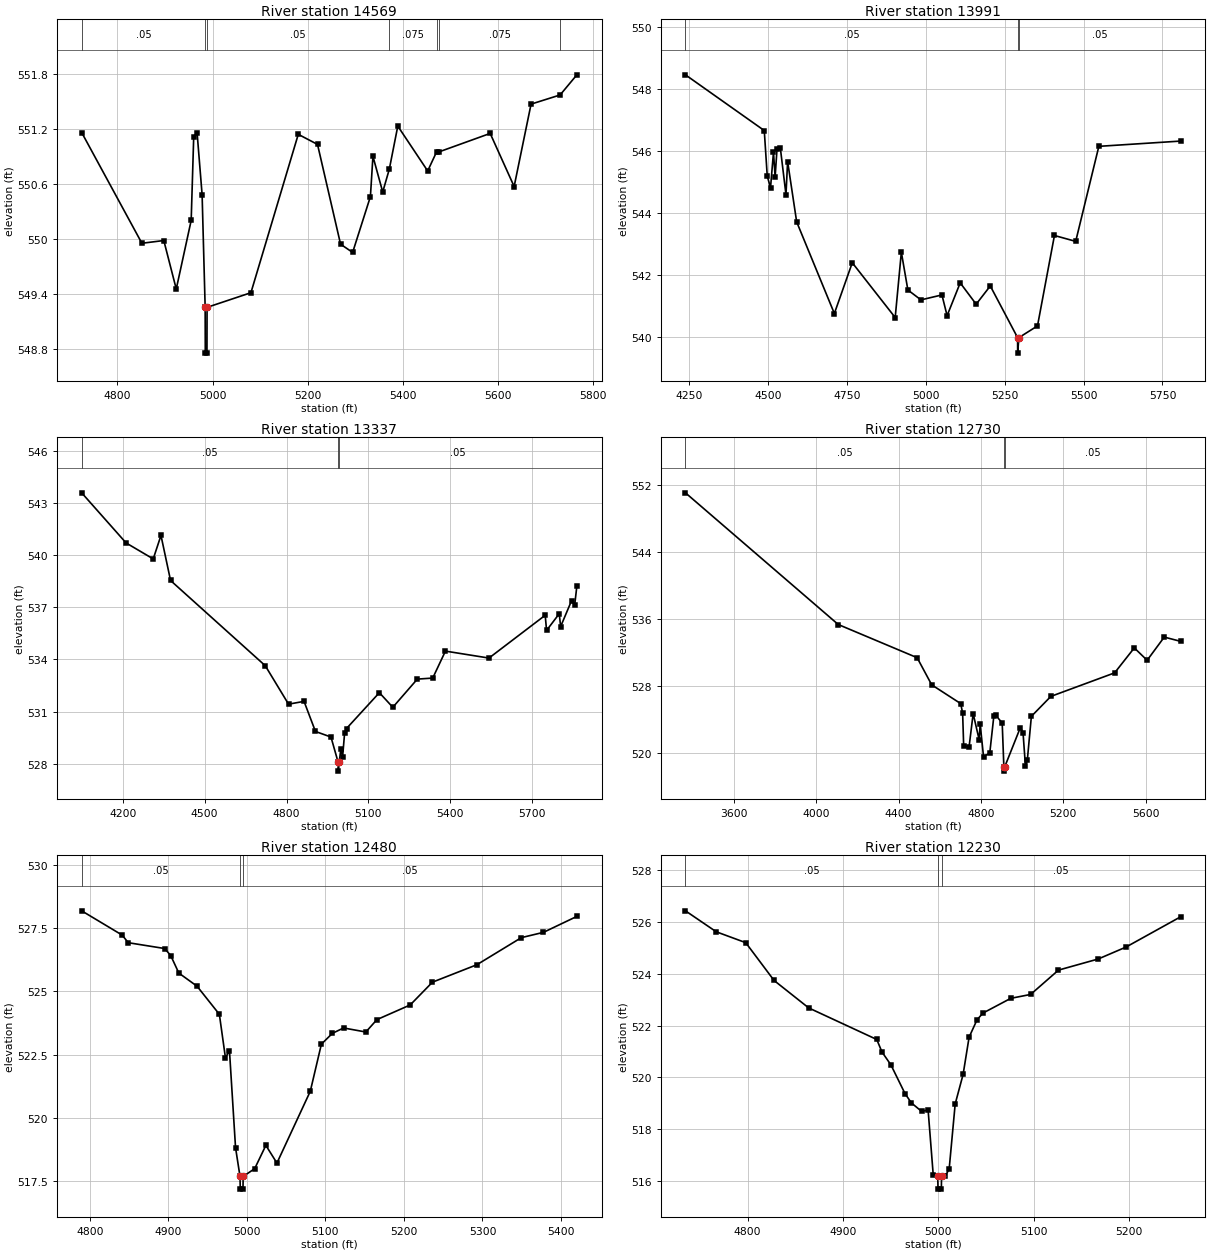
Type RM Length L Ch R = 1,14569,578,578,578
BEGIN DESCRIPTION:
Brushy Creek Trib 2 30.0
END DESCRIPTION:
XS GIS Cut Line= 3
      2609626.02      6988060.99      2610371.36      6987808.65
      2610519.45      6987601.05
#Sta/Elev= 30
  4724.7  551.16  4851.4  549.95  4897.5  549.98  4923.7  549.45  4955.1  550.20
  4960.4  551.11  4967.5  551.16  4978.1  550.48  4984.5  549.25  4984.8  548.75
  4988.3  548.75  4988.5  549.25  5080.8  549.41  5180.4  551.14  5220.9  551.03
  5269.4  549.94  5294.8  549.85  5332.2  550.46  5337.5  550.90  5358.1  550.51
  5372.0  550.76  5389.8  551.23  5452.7  550.74  5471.6  550.95  5477.4  550.95
  5584.2  551.15  5634.6  550.57  5670.2  551.47  5731.3  551.57  5766.6  551.79
#Mann=7,-1,0
  4724.7    0.05       0  4984.5   0.035       0  4988.5    0.05       0
  5372.0   0.075       0  5471.6    0.05       0  5477.4   0.075       0
  5731.3    0.05       0
Bank Sta=4984.5,4988.5
Exp/Cntr=0.3,0.1

Type RM Length L Ch R = 1,13991,654,654,654
BEGIN DESCRIPTION:
Brushy Creek Trib 2 29.0
END DESCRIPTION:
XS GIS Cut Line= 3
      2609525.96      6988611.01      2610545.79      6988331.09
      2610778.63      6987874.48
#Sta/Elev= 30
  4237.5  548.46  4487.4  546.66  4496.8  545.19  4507.2  544.81  4516.6  545.96
  4521.8  545.16  4527.9  546.08  4538.3  546.10  4556.2  544.59  4561.4  545.66
  4590.1  543.71  4709.6  540.75  4766.4  542.39  4902.5  540.62  4922.0  542.73
  4942.7  541.51  4984.2  541.19  5050.7  541.35  5067.1  540.68  5108.6  541.74
  5159.2  541.05  5204.0  541.64  5290.6  539.97  5290.8  539.47  5294.6  539.97
  5353.7  540.35  5407.4  543.27  5474.8  543.08  5548.2  546.15  5807.6  546.32
#Mann=3,-1,0
  4237.5    0.05       0  5290.6   0.035       0  5294.6    0.05       0
Bank Sta=5290.6,5294.6
Exp/Cntr=0.3,0.1

Type RM Length L Ch R = 1,13337,607,607,607
BEGIN DESCRIPTION:
Brushy Creek Trib 2 28.0
END DESCRIPTION:
XS GIS Cut Line= 3
      2610125.97      6989511.03      2610926.00      6988611.00
      2611043.28      6988011.87
#Sta/Elev= 30
  4049.3  543.58  4212.0  540.70  4311.5  539.78  4339.9  541.13  4375.0  538.54
  4722.1  533.64  4807.4  531.43  4864.2  531.59  4906.0  529.86  4962.9  529.54
  4989.3  528.08  4989.6  527.58  4993.3  528.08  4998.9  528.86  5005.6  528.42
  5012.7  529.75  5019.8  530.03  5140.2  532.09  5189.5  531.25  5279.3  532.87
  5335.8  532.93  5382.3  534.48  5541.9  534.08  5747.9  536.54  5753.0  535.67
  5799.4  536.63  5804.5  535.89  5844.5  537.38  5856.0  537.13  5864.0  538.23
#Mann=3,-1,0
  4049.3    0.05       0  4989.3    0.05       0  4993.3    0.05       0
Bank Sta=4989.3,4993.3
Exp/Cntr=0.3,0.1

Type RM Length L Ch R = 1,12730,250,250,250
BEGIN DESCRIPTION:
Brushy Creek Trib 2 27.0
END DESCRIPTION:
XS GIS Cut Line= 3
      2611530.62      6990477.36      2611326.00      6988861.00
      2611114.41      6988114.36
#Sta/Elev= 30
  3365.2  551.11  4107.4  535.39  4490.5  531.43  4561.3  528.19  4702.1  525.95
  4711.5  524.82  4716.5  520.94  4742.5  520.72  4762.6  524.75  4791.6  521.66
  4796.7  523.50  4813.0  519.62  4843.3  520.05  4863.4  524.53  4871.7  524.57
  4903.7  523.64  4911.8  518.39  4912.1  517.89  4915.8  518.39  4991.9  523.09
  5004.9  522.47  5016.6  518.51  5025.6  519.17  5045.4  524.43  5140.0  526.81
  5449.8  529.62  5545.3  532.60  5607.7  531.12  5690.8  533.89  5770.5  533.38
#Mann=3,-1,0
  3365.2    0.05       0  4911.8    0.03       0  4915.8    0.05       0
Bank Sta=4911.8,4915.8
Exp/Cntr=0.3,0.1

Type RM Length L Ch R = 1,12480,250,250,250
BEGIN DESCRIPTION:
Brushy Creek Trib 2 26.0
END DESCRIPTION:
XS GIS Cut Line= 3
      2611626.01      6989061.05      2611576.00      6988861.00
      2611275.98      6988560.98
#Sta/Elev= 30
  4789.7  528.18  4841.3  527.22  4849.0  526.92  4895.4  526.69  4903.1  526.41
  4913.4  525.72  4936.6  525.20  4965.0  524.09  4972.7  522.38  4977.9  522.64
  4985.6  518.82  4991.3  517.68  4991.6  517.18  4995.1  517.18  4995.3  517.68
  5010.0  517.99  5024.2  518.91  5038.3  518.21  5080.8  521.05  5094.9  522.91
  5109.0  523.34  5123.2  523.55  5151.5  523.39  5165.6  523.88  5208.0  524.46
  5236.3  525.36  5292.9  526.05  5349.5  527.12  5377.7  527.33  5420.2  527.96
#Mann=3,-1,0
  4789.7    0.05       0  4991.3    0.03       0  4995.3    0.05       0
Bank Sta=4991.3,4995.3
Exp/Cntr=0.3,0.1

Type RM Length L Ch R = 1,12230,258,258,258
BEGIN DESCRIPTION:
Brushy Creek Trib 2 25.0
END DESCRIPTION:
XS GIS Cut Line= 3
      2611725.99      6988910.97      2611626.00      6988661.00
      2611426.02      6988511.02
#Sta/Elev= 30
  4734.9  526.43  4767.2  525.62  4798.1  525.20  4827.8  523.74  4864.1  522.68
  4935.5  521.46  4940.9  520.98  4950.3  520.48  4965.1  519.37  4971.8  519.01
  4982.6  518.68  4989.3  518.74  4994.7  516.22  4999.4  516.18  4999.7  515.68
  5003.2  515.68  5003.4  516.18  5007.3  516.18  5011.4  516.46  5017.7  518.97
  5026.0  520.11  5032.3  521.55  5040.6  522.22  5046.8  522.48  5076.0  523.05
  5096.8  523.20  5126.0  524.14  5167.7  524.57  5196.8  525.03  5254.1  526.20
#Mann=3,-1,0
  4734.9    0.05       0  4999.4    0.03       0  5003.4    0.05       0
Bank Sta=4999.4,5003.4
Exp/Cntr=0.3,0.1

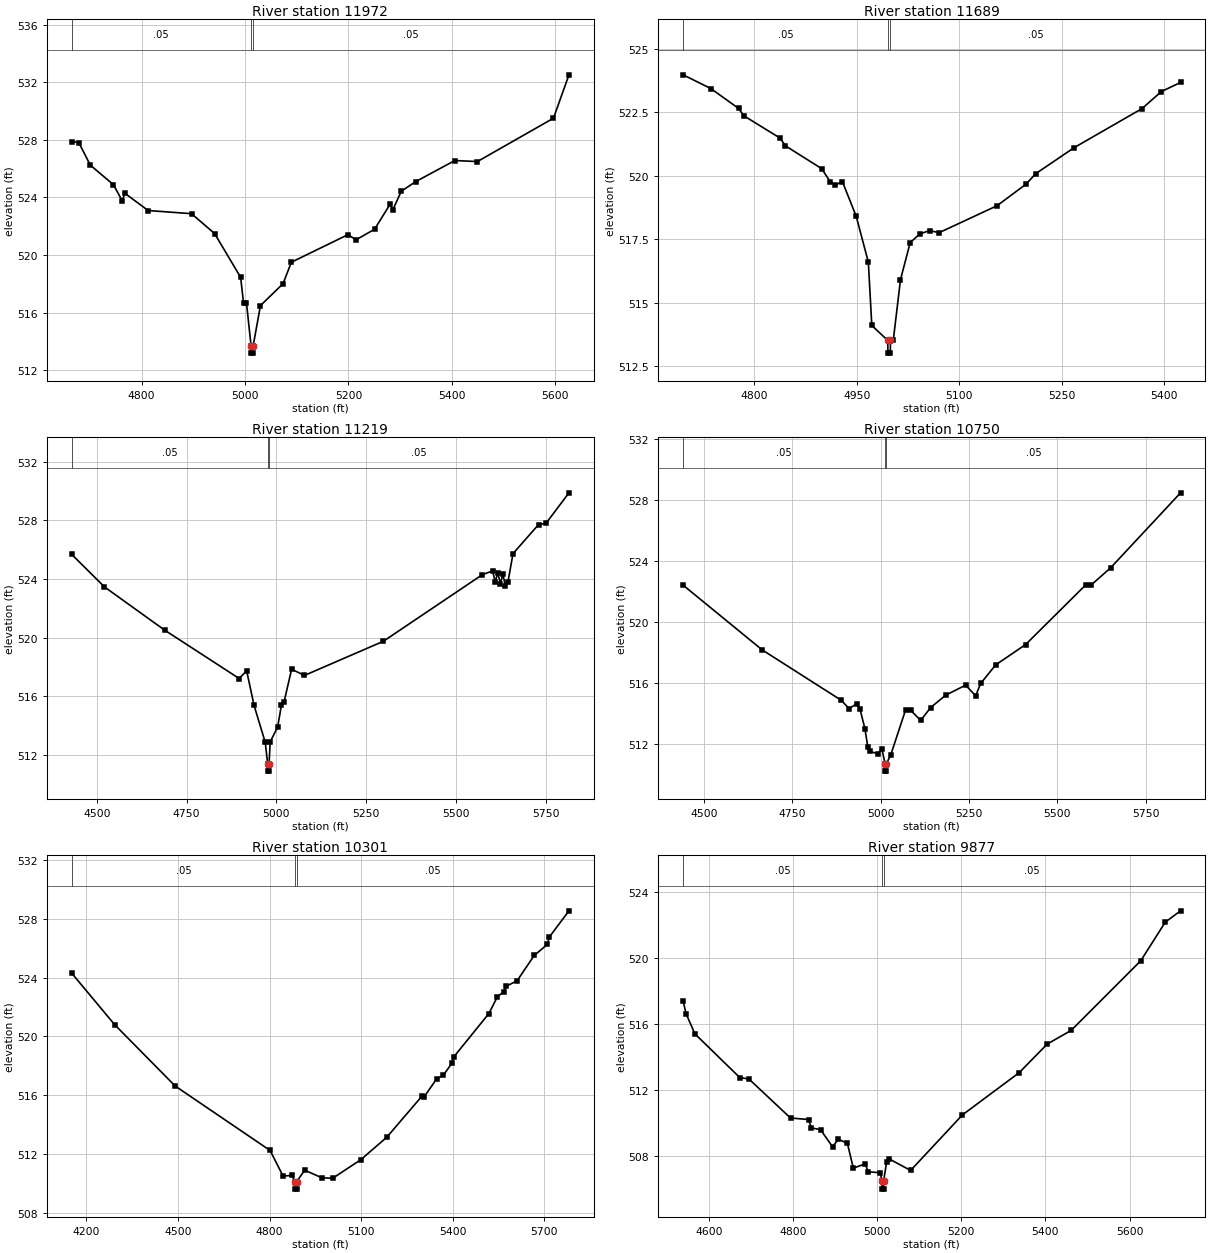
Type RM Length L Ch R = 1,11972,283,283,283
BEGIN DESCRIPTION:
Brushy Creek Trib 2 24.0
END DESCRIPTION:
XS GIS Cut Line= 3
      2611976.00      6988811.00      2611826.00      6988511.00
      2611276.01      6988211.01
#Sta/Elev= 30
  4664.6  527.88  4678.6  527.81  4700.9  526.24  4745.7  524.88  4762.4  523.78
  4768.0  524.28  4812.7  523.09  4896.6  522.87  4941.3  521.49  4991.6  518.45
  4997.2  516.68  5002.9  516.68  5011.8  513.69  5012.0  513.19  5015.5  513.19
  5015.8  513.69  5029.9  516.49  5073.6  518.01  5089.7  519.50  5198.9  521.41
  5215.0  521.06  5250.6  521.79  5280.5  523.52  5286.2  523.16  5302.3  524.43
  5330.3  525.10  5405.8  526.56  5449.5  526.49  5596.6  529.50  5626.5  532.51
#Mann=3,-1,0
  4664.6    0.05       0  5011.8    0.03       0  5015.8    0.05       0
Bank Sta=5011.8,5015.8
Exp/Cntr=0.3,0.1

Type RM Length L Ch R = 1,11689,470,470,470
BEGIN DESCRIPTION:
Brushy Creek Trib 2 23.0
END DESCRIPTION:
XS GIS Cut Line= 3
      2612076.01      6988611.04      2612026.00      6988311.00
      2611726.03      6988011.03
#Sta/Elev= 30
  4695.8  523.97  4736.4  523.43  4776.9  522.65  4784.6  522.36  4837.8  521.48
  4845.4  521.18  4898.6  520.28  4911.3  519.76  4918.9  519.64  4929.0  519.77
  4949.3  518.40  4967.0  516.60  4972.1  514.11  4995.4  513.52  4995.7  513.02
  4999.2  513.02  4999.4  513.52  5003.5  513.52  5014.1  515.91  5028.3  517.37
  5042.4  517.71  5056.6  517.84  5070.7  517.76  5155.5  518.82  5198.0  519.67
  5212.1  520.08  5268.7  521.11  5367.7  522.64  5396.0  523.31  5424.2  523.67
#Mann=3,-1,0
  4695.8    0.05       0  4995.4   0.035       0  4999.4    0.05       0
Bank Sta=4995.4,4999.4
Exp/Cntr=0.3,0.1

Type RM Length L Ch R = 1,11219,469,469,469
BEGIN DESCRIPTION:
Brushy Creek Trib 2 22.0
END DESCRIPTION:
XS GIS Cut Line= 3
      2612526.00      6988561.01      2612376.00      6988011.00
      2611826.03      6987411.03
#Sta/Elev= 30
  4429.9  525.69  4521.5  523.46  4689.0  520.51  4896.3  517.21  4917.1  517.74
  4937.8  515.37  4968.9  512.85  4975.5  511.39  4975.8  510.89  4979.3  510.89
  4979.5  511.39  4982.7  512.89  5003.4  513.90  5013.9  515.40  5021.3  515.62
  5042.2  517.84  5078.0  517.42  5297.5  519.75  5573.1  524.30  5601.5  524.55
  5608.9  523.78  5615.7  524.44  5623.1  523.68  5629.9  524.34  5637.3  523.50
  5644.1  523.78  5658.2  525.73  5729.2  527.71  5750.1  527.80  5813.9  529.88
#Mann=3,-1,0
  4429.9    0.05       0  4975.5    0.03       0  4979.5    0.05       0
Bank Sta=4975.5,4979.5
Exp/Cntr=0.3,0.1

Type RM Length L Ch R = 1,10750,449,449,449
BEGIN DESCRIPTION:
Brushy Creek Trib 2 21.0
END DESCRIPTION:
XS GIS Cut Line= 3
      2612976.00      6988211.00      2612726.00      6987711.00
      2612126.03      6987111.03
#Sta/Elev= 30
  4441.0  522.42  4664.6  518.17  4888.2  514.86  4910.6  514.31  4932.9  514.64
  4941.3  514.29  4955.3  513.00  4963.7  511.77  4969.3  511.49  4991.6  511.35
  5003.6  511.66  5012.2  510.70  5012.4  510.20  5015.9  510.20  5016.2  510.70
  5028.3  511.25  5070.7  514.24  5084.9  514.20  5113.2  513.53  5141.4  514.38
  5183.9  515.19  5240.4  515.85  5268.7  515.15  5282.9  515.96  5325.3  517.18
  5410.1  518.52  5579.8  522.43  5594.0  522.40  5650.6  523.56  5848.5  528.49
#Mann=3,-1,0
  4441.0    0.05       0  5012.2   0.035       0  5016.2    0.05       0
Bank Sta=5012.2,5016.2
Exp/Cntr=0.3,0.1

Type RM Length L Ch R = 1,10301,424,424,424
BEGIN DESCRIPTION:
Brushy Creek Trib 2 20.0
END DESCRIPTION:
XS GIS Cut Line= 3
      2613576.00      6987961.00      2612976.00      6987361.00
      2612375.97      6986860.97
#Sta/Elev= 30
  4151.2  524.31  4292.6  520.79  4490.6  516.62  4801.7  512.23  4844.2  510.49
  4872.5  510.53  4884.6  510.10  4884.8  509.60  4888.3  509.60  4888.6  510.10
  4914.9  510.89  4971.5  510.37  5006.9  510.34  5099.3  511.61  5183.9  513.13
  5298.5  515.91  5305.0  515.84  5347.9  517.12  5368.8  517.34  5397.4  518.17
  5403.9  518.61  5518.5  521.55  5546.5  522.70  5567.9  523.04  5574.4  523.40
  5610.9  523.78  5666.9  525.50  5709.8  526.25  5716.3  526.75  5780.8  528.54
#Mann=3,-1,0
  4151.2    0.05       0  4884.6   0.035       0  4888.6    0.05       0
Bank Sta=4884.6,4888.6
Exp/Cntr=0.3,0.1

Type RM Length L Ch R = 1,9877,421,421,421
BEGIN DESCRIPTION:
Brushy Creek Trib 2 19.0
END DESCRIPTION:
XS GIS Cut Line= 3
      2613676.01      6987461.01      2613326.00      6987161.00
      2612726.00      6986761.00
#Sta/Elev= 30
  4539.0  517.39  4546.1  516.61  4567.0  515.40  4673.5  512.76  4695.4  512.67
  4794.2  510.31  4837.0  510.22  4843.6  509.71  4865.5  509.61  4894.1  508.57
  4907.8  509.02  4929.2  508.79  4943.5  507.28  4972.0  507.54  4978.6  507.06
  5007.5  507.00  5011.5  506.51  5011.8  506.01  5015.3  506.01  5015.5  506.51
  5022.5  507.63  5028.5  507.84  5079.6  507.14  5202.8  510.50  5338.0  513.06
  5404.1  514.78  5461.2  515.61  5626.5  519.82  5685.0  522.16  5721.1  522.84
#Mann=3,-1,0
  4539.0    0.05       0  5011.5   0.035       0  5015.5    0.05       0
Bank Sta=5011.5,5015.5
Exp/Cntr=0.3,0.1

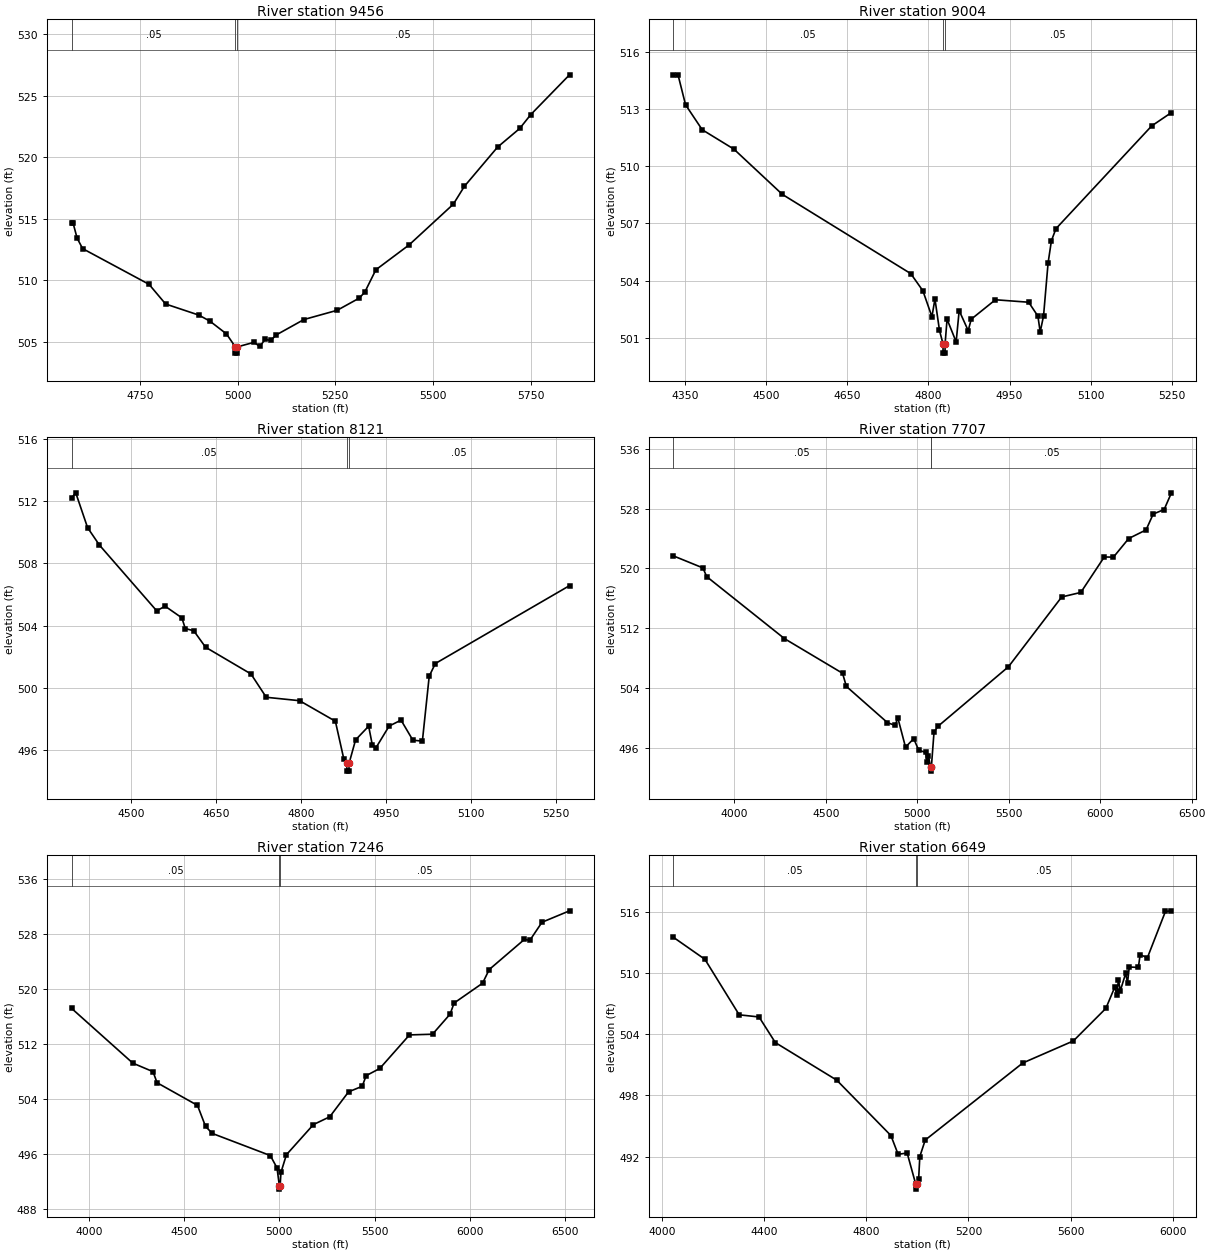
Type RM Length L Ch R = 1,9456,452,452,452
BEGIN DESCRIPTION:
Brushy Creek Trib 2 18.0
END DESCRIPTION:
XS GIS Cut Line= 3
      2613926.02      6987211.02      2613626.00      6986911.00
      2613026.02      6986311.02
#Sta/Elev= 30
  4575.7  514.67  4579.3  514.67  4589.9  513.41  4604.0  512.56  4773.7  509.66
  4816.1  508.06  4901.0  507.16  4929.3  506.67  4971.7  505.63  4994.5  504.57
  4994.7  504.07  4998.2  504.07  4998.5  504.57  5042.4  504.95  5056.6  504.61
  5070.7  505.19  5084.8  505.10  5099.0  505.55  5169.7  506.80  5254.6  507.55
  5311.1  508.54  5325.3  509.03  5353.5  510.84  5438.4  512.86  5551.5  516.17
  5579.8  517.62  5664.7  520.81  5721.2  522.32  5749.5  523.45  5848.5  526.68
#Mann=3,-1,0
  4575.7    0.05       0  4994.5    0.03       0  4998.5    0.05       0
Bank Sta=4994.5,4998.5
Exp/Cntr=0.3,0.1

Type RM Length L Ch R = 1,9004,883,883,883
BEGIN DESCRIPTION:
Brushy Creek Trib 2 17.0
END DESCRIPTION:
XS GIS Cut Line= 3
      2614025.99      6987160.98      2613726.00      6986561.00
      2613526.00      6986411.00
#Sta/Elev= 30
  4328.6  514.77  4337.0  514.79  4350.9  513.22  4381.7  511.91  4440.4  510.89
  4529.8  508.52  4767.4  504.36  4789.8  503.46  4806.5  502.10  4812.1  503.03
  4820.5  501.38  4826.9  500.69  4827.2  500.19  4830.7  500.19  4830.9  500.69
  4834.5  501.97  4851.3  500.78  4856.9  502.42  4873.6  501.37  4879.2  501.97
  4923.9  502.99  4985.4  502.86  5002.5  502.13  5006.7  501.30  5012.9  502.14
  5021.3  504.92  5027.5  506.09  5035.9  506.72  5212.9  512.11  5249.4  512.81
#Mann=3,-1,0
  4328.6    0.05       0  4826.9    0.03       0  4830.9    0.05       0
Bank Sta=4826.9,4830.9
Exp/Cntr=0.3,0.1

Type RM Length L Ch R = 1,8121,414,414,414
BEGIN DESCRIPTION:
Brushy Creek Trib 2 15.0
END DESCRIPTION:
XS GIS Cut Line= 3
      2614825.97      6986510.98      2614326.00      6986161.00
      2614075.96      6986060.98
#Sta/Elev= 30
  4394.9  512.21  4402.3  512.54  4423.2  510.30  4444.1  509.18  4545.3  504.95
  4560.1  505.25  4589.7  504.50  4595.8  503.81  4610.7  503.67  4631.6  502.61
  4711.8  500.89  4738.8  499.39  4797.7  499.17  4860.9  497.85  4875.7  495.44
  4881.1  495.14  4881.4  494.64  4884.9  494.64  4885.1  495.14  4896.6  496.65
  4919.7  497.53  4926.3  496.30  4932.4  496.13  4955.9  497.54  4976.9  497.92
  4997.8  496.63  5014.6  496.57  5026.7  500.75  5037.5  501.56  5274.5  506.57
#Mann=3,-1,0
  4394.9    0.05       0  4881.1    0.03       0  4885.1    0.05       0
Bank Sta=4881.1,4885.1
Exp/Cntr=0.3,0.1

Type RM Length L Ch R = 1,7707,461,461,461
BEGIN DESCRIPTION:
Brushy Creek Trib 2 14.0
END DESCRIPTION:
XS GIS Cut Line= 3
      2615773.67      6986706.49      2614676.00      6985961.00
      2613430.50      6985331.78
#Sta/Elev= 30
  3667.1  521.67  3827.8  520.07  3848.8  518.90  4273.9  510.61  4591.3  505.98
  4612.3  504.22  4836.7  499.38  4878.7  499.00  4893.7  500.00  4935.6  496.10
  4980.5  497.23  5007.9  495.68  5046.9  495.39  5052.5  494.06  5061.2  494.87
  5072.8  493.39  5073.1  492.89  5076.8  493.39  5091.5  498.12  5113.8  498.90
  5498.4  506.85  5789.4  516.18  5894.0  516.79  6022.2  521.53  6072.4  521.51
  6155.9  524.00  6250.7  525.15  6289.7  527.27  6349.6  527.88  6389.4  530.11
#Mann=3,-1,0
  3667.1    0.05       0  5072.8    0.03       0  5076.8    0.05       0
Bank Sta=5072.8,5076.8
Exp/Cntr=0.3,0.1

Type RM Length L Ch R = 1,7246,597,597,597
BEGIN DESCRIPTION:
Brushy Creek Trib 2 13.0
END DESCRIPTION:
XS GIS Cut Line= 3
      2615725.07      6986446.09      2614976.00      6985661.00
      2613811.86      6984671.76
#Sta/Elev= 30
  3909.3  517.15  4230.6  509.19  4336.6  507.95  4358.0  506.34  4570.0  503.05
  4612.4  499.99  4648.0  498.97  4952.1  495.76  4987.3  493.97  4999.6  491.38
  4999.8  490.88  5003.6  491.38  5008.1  493.32  5036.7  495.88  5178.4  500.26
  5264.0  501.39  5362.9  505.02  5434.3  505.82  5455.1  507.37  5526.5  508.41
  5682.5  513.29  5803.3  513.39  5895.6  516.31  5916.4  517.92  6065.8  520.80
  6100.9  522.79  6285.5  527.17  6314.0  527.03  6377.7  529.66  6522.1  531.32
#Mann=3,-1,0
  3909.3    0.05       0  4999.6    0.03       0  5003.6    0.05       0
Bank Sta=4999.6,5003.6
Exp/Cntr=0.3,0.1

Type RM Length L Ch R = 1,6649,45,45,45
BEGIN DESCRIPTION:
Mapping XS ff981275
END DESCRIPTION:
XS GIS Cut Line= 3
      2616110.48      6986050.24      2615447.28      6985359.27
      2614752.84      6984650.94
#Sta/Elev= 30
  4044.9  513.48  4167.9  511.33  4302.2  505.89  4379.9  505.68  4443.7  503.17
  4684.0  499.49  4896.2  494.06  4924.5  492.22  4959.8  492.35  4993.3  489.31
  4993.5  488.81  4997.3  489.31  5004.9  489.85  5009.4  492.00  5030.6  493.62
  5412.5  501.17  5610.5  503.33  5737.8  506.52  5773.1  508.62  5780.2  507.79
  5787.2  509.33  5794.4  508.24  5815.5  509.96  5822.6  509.02  5829.6  510.58
  5865.1  510.53  5872.1  511.79  5900.4  511.48  5971.1  516.02  5994.6  516.08
#Mann=3,-1,0
  4044.9    0.05       0  4993.3    0.03       0  4997.3    0.05       0
Bank Sta=4993.3,4997.3
Exp/Cntr=0.3,0.1

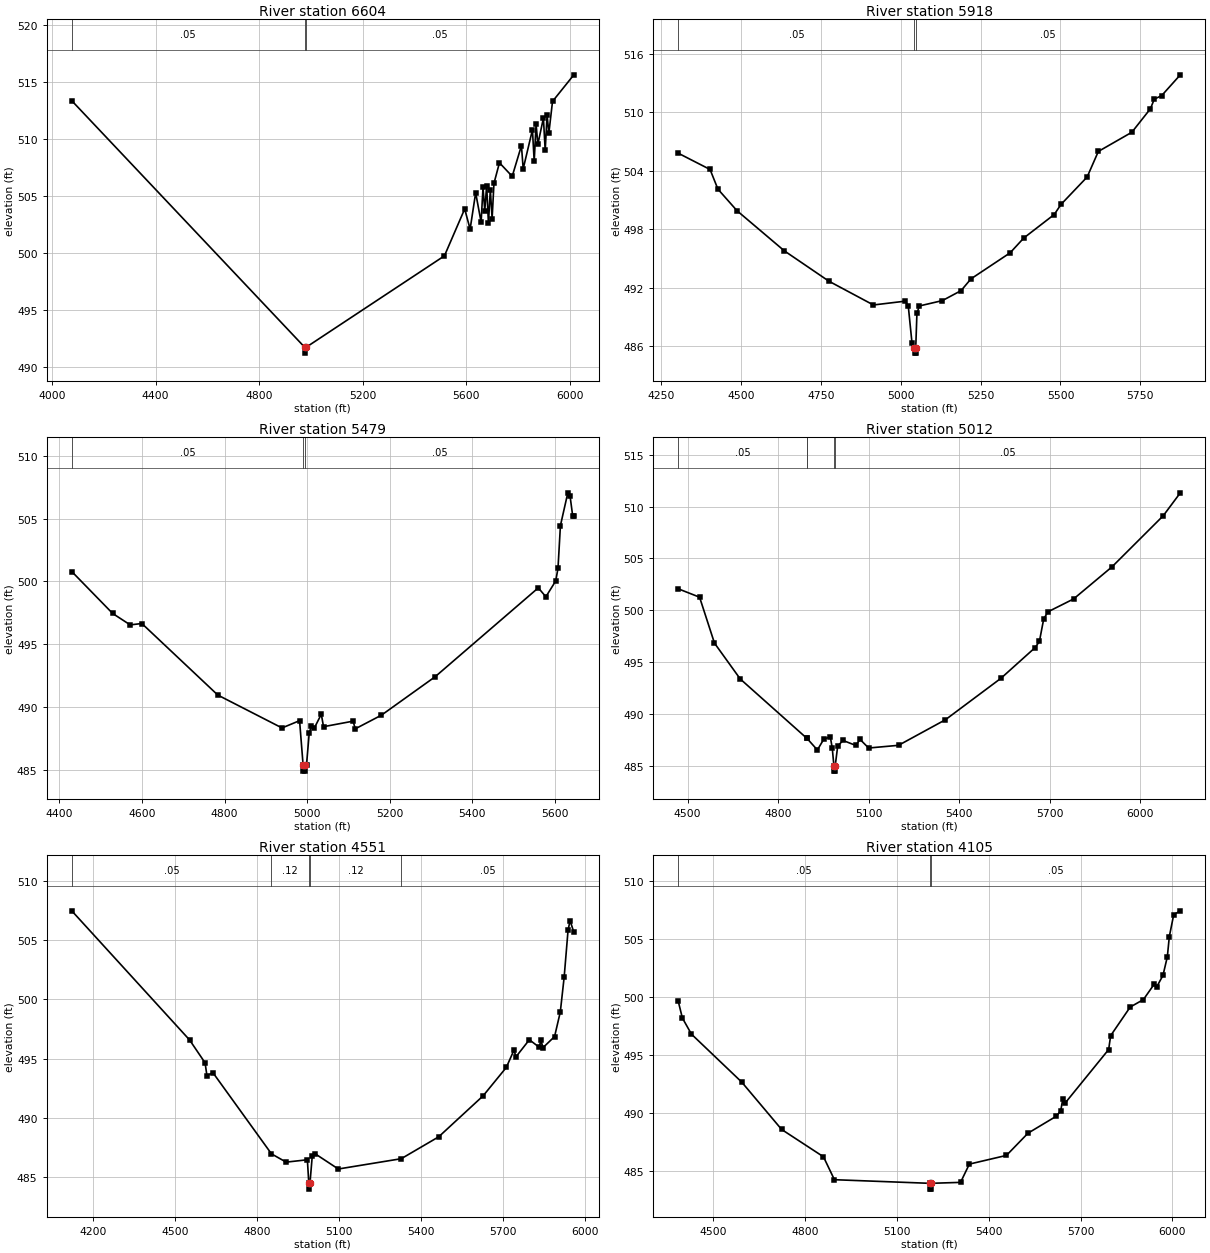
Type RM Length L Ch R = 1,6604,686,686,686
BEGIN DESCRIPTION:
Mapping XS b6ffd191
END DESCRIPTION:
XS GIS Cut Line= 3
      2616134.76      6986008.55      2615488.95      6985345.38
      2614794.63      6984605.93
#Sta/Elev= 30
  4076.0  513.34  4976.6  491.71  4976.9  491.21  4980.6  491.71  5516.0  499.74
  5594.2  503.85  5615.2  502.08  5636.6  505.27  5657.7  502.69  5665.0  505.75
  5671.8  503.70  5679.1  505.90  5686.0  502.60  5693.3  505.55  5700.2  503.01
  5707.3  506.09  5728.5  507.90  5777.8  506.71  5813.5  509.40  5820.3  507.37
  5856.0  510.79  5862.8  508.02  5870.1  511.29  5877.0  509.52  5898.4  511.82
  5905.3  508.98  5912.6  512.06  5919.5  510.51  5933.6  513.28  6016.0  515.61
#Mann=3,-1,0
  4076.0    0.05       0  4976.6    0.03       0  4980.6    0.05       0
Bank Sta=4976.6,4980.6
Exp/Cntr=0.3,0.1

Type RM Length L Ch R = 1,5918,439,439,439
BEGIN DESCRIPTION:
Brushy Creek Trib 2 10.0
END DESCRIPTION:
XS GIS Cut Line= 3
      2616225.98      6985560.96      2615976.00      6984911.00
      2615226.02      6984461.01
#Sta/Elev= 30
  4303.9  505.80  4403.5  504.13  4428.1  502.11  4488.1  499.89  4636.0  495.78
  4775.3  492.67  4914.6  490.23  5013.9  490.62  5023.6  490.15  5035.3  486.34
  5042.9  485.79  5043.2  485.29  5046.7  485.29  5047.0  485.79  5050.8  489.40
  5058.6  490.13  5130.5  490.68  5188.8  491.70  5219.9  492.91  5342.4  495.58
  5385.1  497.10  5480.4  499.51  5501.7  500.55  5583.4  503.36  5618.4  505.98
  5723.3  507.95  5781.6  510.37  5793.3  511.34  5816.6  511.71  5874.9  513.84
#Mann=3,-1,0
  4303.9    0.05       0  5042.9    0.03       0  5047.0    0.05       0
Bank Sta=5042.9,5047
Exp/Cntr=0.3,0.1

Type RM Length L Ch R = 1,5479,467,467,467
BEGIN DESCRIPTION:
Brushy Creek Trib 2 9.0
END DESCRIPTION:
XS GIS Cut Line= 3
      2616676.02      6985011.02      2616276.00      6984611.00
      2615676.01      6984361.01
#Sta/Elev= 30
  4430.1  500.79  4529.1  497.45  4571.6  496.54  4599.8  496.65  4783.7  490.95
  4939.2  488.33  4981.7  488.91  4990.2  485.39  4990.5  484.89  4994.0  484.89
  4994.3  485.39  4998.5  485.39  5005.0  487.91  5010.4  488.50  5017.5  488.33
  5034.3  489.42  5039.7  488.43  5111.2  488.87  5116.6  488.26  5180.0  489.35
  5310.0  492.41  5559.7  499.49  5578.1  498.78  5601.9  500.04  5607.4  501.04
  5613.3  504.45  5631.2  507.06  5636.6  506.81  5643.1  505.20  5645.8  505.20
#Mann=3,-1,0
  4430.1    0.05       0  4990.2    0.03       0  4994.3    0.05       0
Bank Sta=4990.2,4994.3
Exp/Cntr=0.3,0.1

Type RM Length L Ch R = 1,5012,461,461,461
BEGIN DESCRIPTION:
Brushy Creek Trib 2 8.0
END DESCRIPTION:
XS GIS Cut Line= 3
      2616925.97      6984710.97      2616576.00      6984311.00
      2615776.03      6983511.03
#Sta/Elev= 30
  4469.1  502.07  4539.8  501.26  4589.1  496.83  4674.5  493.37  4894.9  487.65
  4895.8  487.63  4929.9  486.52  4950.7  487.54  4972.6  487.81  4979.2  486.70
  4984.7  484.98  4985.0  484.48  4988.6  484.48  4988.9  484.98  4997.2  486.89
  5014.7  487.44  5057.1  486.96  5071.3  487.54  5099.6  486.71  5198.6  486.97
  5354.1  489.44  5538.0  493.44  5651.1  496.40  5665.2  496.99  5679.4  499.15
  5693.5  499.85  5778.4  501.09  5905.7  504.19  6075.4  509.12  6131.9  511.33
#Mann=5,-1,0
  4469.1    0.05       0  4894.9    0.12       0  4895.8    0.05       0
  4984.7    0.03       0  4988.9    0.05       0
Bank Sta=4984.7,4988.9
Exp/Cntr=0.3,0.1

Type RM Length L Ch R = 1,4551,446,446,446
BEGIN DESCRIPTION:
Brushy Creek Trib 2 7.0
END DESCRIPTION:
XS GIS Cut Line= 3
      2617426.03      6984661.03      2616826.00      6984011.00
      2616175.98      6983310.98
#Sta/Elev= 30
  4120.5  507.49  4552.3  496.58  4609.0  494.65  4615.9  493.55  4637.4  493.83
  4852.3  486.96  4906.2  486.26  4983.9  486.46  4989.1  484.48  4989.4  483.98
  4993.4  484.48  5001.7  486.76  5012.2  486.97  5097.2  485.68  5327.9  486.55
  5465.2  488.40  5627.9  491.86  5712.9  494.26  5741.2  495.73  5748.1  495.15
  5797.4  496.60  5833.1  495.97  5839.9  496.54  5847.3  495.93  5889.8  496.87
  5910.8  498.95  5924.9  501.89  5939.1  505.83  5946.5  506.67  5960.4  505.68
#Mann=5,-1,0
  4120.5    0.05       0  4852.3    0.12       0  4989.1    0.07       0
  4993.4    0.12       0  5327.9    0.05       0
Bank Sta=4989.1,4993.4
Exp/Cntr=0.3,0.1

Type RM Length L Ch R = 1,4105,446,446,446
BEGIN DESCRIPTION:
Brushy Creek Trib 2 6.0
END DESCRIPTION:
XS GIS Cut Line= 3
      2617576.00      6984011.00      2617076.00      6983661.00
      2616426.00      6982861.00
#Sta/Elev= 30
  4384.8  499.63  4398.3  498.19  4428.0  496.80  4592.3  492.68  4722.7  488.61
  4859.5  486.26  4895.3  484.29  5206.3  483.98  5206.7  483.48  5210.3  483.48
  5210.6  483.98  5307.6  484.06  5336.3  485.63  5457.7  486.38  5528.1  488.29
  5620.8  489.75  5635.1  490.22  5641.6  491.21  5649.5  490.88  5791.7  495.48
  5798.2  496.67  5862.1  499.13  5905.2  499.77  5940.4  501.09  5948.3  500.84
  5969.2  501.85  5983.5  503.45  5990.0  505.19  6004.3  507.07  6025.9  507.40
#Mann=3,-1,0
  4384.8    0.05       0  5206.3    0.03       0  5210.6    0.05       0
Bank Sta=5206.3,5210.6
Exp/Cntr=0.3,0.1

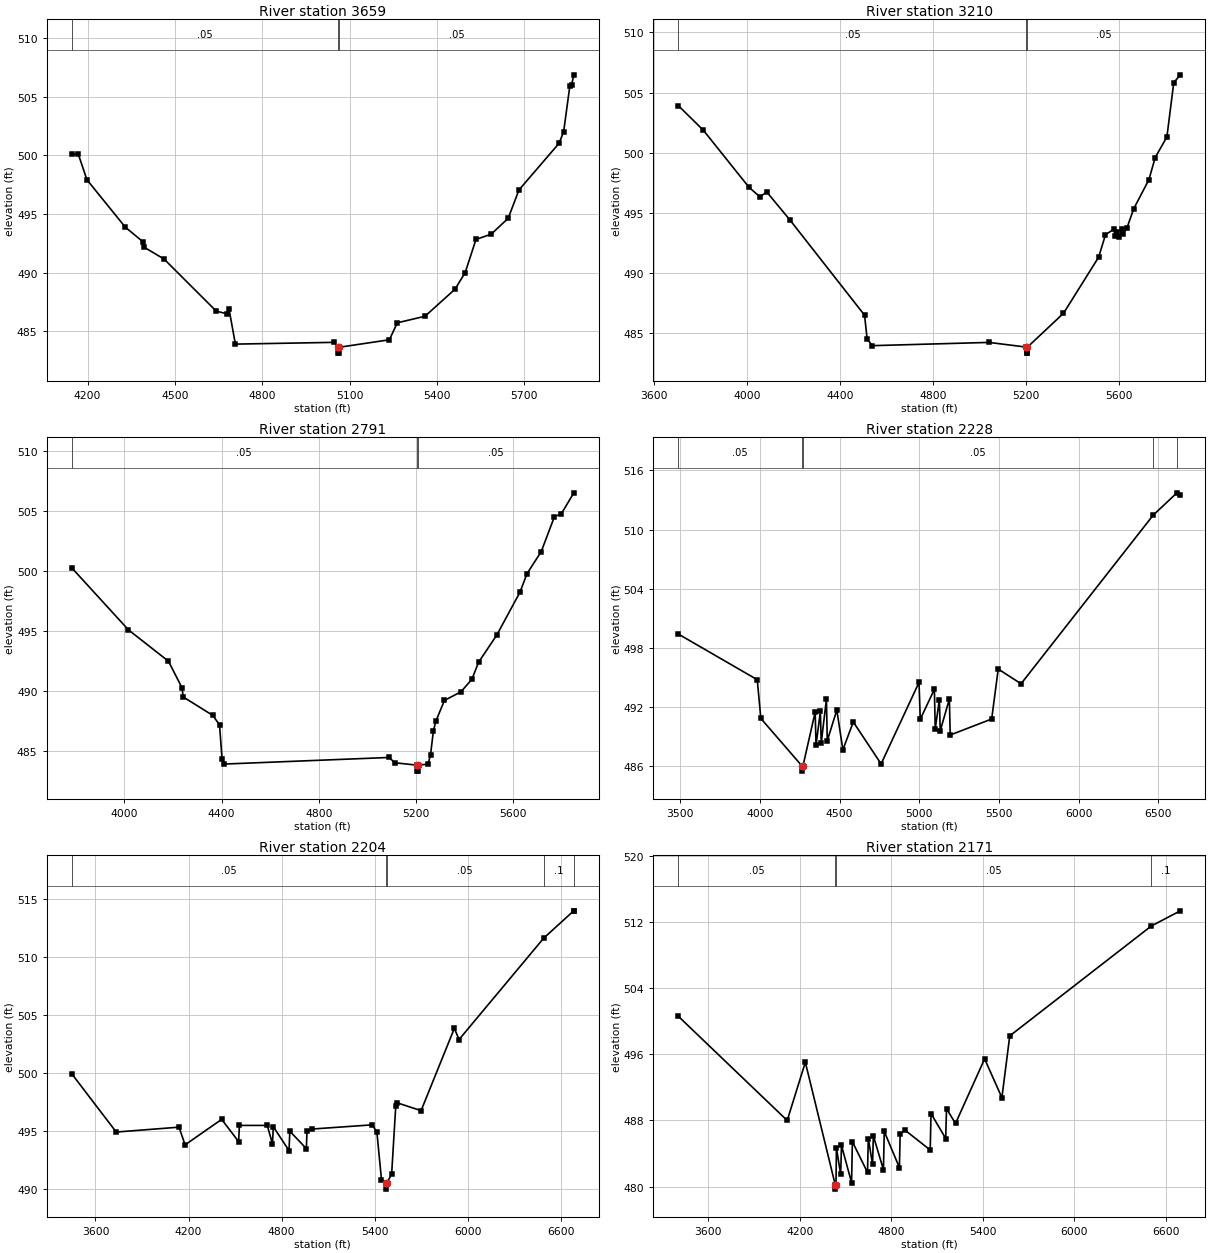
Type RM Length L Ch R = 1,3659,449,449,449
BEGIN DESCRIPTION:
Brushy Creek Trib 2 5.0
END DESCRIPTION:
XS GIS Cut Line= 3
      2617625.99      6984010.97      2617226.00      6983261.00
      2616476.01      6982811.01
#Sta/Elev= 30
  4145.8  500.12  4168.4  500.10  4197.8  497.93  4329.6  493.88  4389.8  492.64
  4395.5  492.15  4463.1  491.15  4642.0  486.71  4678.4  486.48  4685.9  486.89
  4707.8  483.89  5046.3  484.04  5059.6  483.62  5060.1  483.12  5063.7  483.12
  5064.1  483.62  5236.8  484.26  5264.0  485.71  5359.2  486.27  5462.2  488.58
  5497.2  490.00  5534.2  492.83  5586.6  493.28  5644.9  494.64  5681.9  497.06
  5819.9  501.05  5835.4  502.04  5856.8  505.97  5862.6  506.04  5870.4  506.89
#Mann=3,-1,0
  4145.8    0.05       0  5059.6    0.03       0  5064.1    0.05       0
Bank Sta=5059.6,5064.1
Exp/Cntr=0.3,0.1

Type RM Length L Ch R = 1,3210,419,419,419
BEGIN DESCRIPTION:
Brushy Creek Trib 2 4.0
END DESCRIPTION:
XS GIS Cut Line= 3
      2617976.00      6984111.00      2617476.00      6982911.00
      2616976.02      6982211.03
#Sta/Elev= 30
  3704.3  503.92  3812.6  501.86  4008.2  497.14  4055.8  496.33  4085.1  496.74
  4185.8  494.39  4506.0  486.50  4516.8  484.56  4538.5  483.97  5041.2  484.24
  5202.3  483.85  5202.8  483.35  5206.4  483.35  5206.9  483.85  5361.9  486.66
  5513.1  491.32  5542.6  493.19  5578.2  493.64  5584.3  493.06  5592.9  493.41
  5599.1  492.96  5613.8  493.64  5620.0  493.28  5634.7  493.74  5664.2  495.35
  5729.4  497.76  5756.4  499.60  5806.8  501.31  5836.3  505.82  5864.5  506.47
#Mann=3,-1,0
  3704.3    0.05       0  5202.3    0.03       0  5206.9    0.05       0
Bank Sta=5202.3,5206.9
Exp/Cntr=0.3,0.1

Type RM Length L Ch R = 1,2791,563,563,563
BEGIN DESCRIPTION:
Brushy Creek Trib 2 3.0
END DESCRIPTION:
XS GIS Cut Line= 3
      2618025.99      6983910.97      2617826.00      6982711.00
      2617426.01      6981961.02
#Sta/Elev= 30
  3783.5  500.28  4016.6  495.11  4181.4  492.49  4237.1  490.28  4242.2  489.51
  4363.9  487.97  4391.7  487.18  4401.9  484.37  4412.0  483.91  5090.3  484.46
  5112.3  484.02  5203.5  483.82  5203.9  483.32  5207.6  483.32  5208.1  483.82
  5249.7  483.90  5260.3  484.70  5272.0  486.69  5282.3  487.50  5317.4  489.22
  5385.4  489.94  5430.3  490.98  5458.0  492.41  5532.7  494.67  5628.0  498.24
  5657.4  499.80  5715.8  501.64  5770.3  504.56  5798.0  504.78  5850.0  506.54
#Mann=3,-1,0
  3783.5    0.05       0  5203.5    0.03       0  5208.1    0.05       0
Bank Sta=5203.5,5208.1
Exp/Cntr=0.3,0.1

Type RM Length L Ch R = 1,2228,24,24,24
BEGIN DESCRIPTION:
Mapping XS c8d42f3e
END DESCRIPTION:
XS GIS Cut Line= 6
      2618159.97      6983859.67      2618461.61      6983254.23
      2618470.29      6983100.15      2618292.65      6982443.45
      2618175.15      6982099.72      2616930.25      6981826.45
#Sta/Elev= 30
  3488.2  499.42  3983.9  494.79  4006.3  490.87  4265.7  486.03  4266.2  485.53
  4270.4  486.03  4347.3  491.52  4352.5  488.16  4380.0  491.57  4385.2  488.38
  4417.8  492.83  4423.1  488.61  4483.1  491.72  4521.0  487.69  4586.3  490.51
  4760.8  486.26  4998.7  494.52  5006.5  490.78  5095.1  493.82  5100.4  489.82
  5126.4  492.78  5131.7  489.61  5189.1  492.84  5194.3  489.19  5454.5  490.81
  5495.5  495.87  5638.8  494.38  6467.2  511.45  6616.7  513.72  6637.8  513.52
#Mann=5,-1,0
  3488.2    0.05       0  4265.7    0.03       0  4270.4    0.05       0
  6467.2     0.1       0  6616.7    0.05       0
Bank Sta=4265.7,4270.4
Exp/Cntr=0.3,0.1

Type RM Length L Ch R = 1,2204,33,33,33
BEGIN DESCRIPTION:
Mapping XS 8ce36723
END DESCRIPTION:
XS GIS Cut Line= 6
      2618170.27      6983876.83      2618479.53      6983275.66
      2618502.32      6983162.82      2618464.34      6982966.42
      2618197.07      6982061.86      2616921.65      6981795.88
#Sta/Elev= 30
  3447.2  499.92  3733.9  494.91  4138.7  495.33  4178.0  493.81  4413.8  496.00
  4523.2  494.09  4528.4  495.48  4707.8  495.48  4741.6  493.89  4746.8  495.37
  4848.2  493.32  4853.4  494.98  4960.0  493.49  4964.2  495.00  4998.1  495.17
  5385.2  495.53  5414.9  494.89  5444.5  490.81  5472.8  490.50  5473.3  490.00
  5477.5  490.50  5509.9  491.28  5536.5  497.12  5546.7  497.42  5699.8  496.75
  5914.4  503.83  5944.8  502.87  6490.7  511.59  6684.2  513.94  6685.0  513.91
#Mann=5,-1,0
  3447.2    0.05       0  5472.8    0.03       0  5477.5    0.05       0
  6490.7     0.1       0  6684.2    0.05       0
Bank Sta=5472.8,5477.5
Exp/Cntr=0.3,0.1

Type RM Length L Ch R = 1,2171,581,581,581
BEGIN DESCRIPTION:
Mapping XS cfda338f
END DESCRIPTION:
XS GIS Cut Line= 6
      2618207.98      6983923.74      2618520.49      6983259.66
      2618520.49      6983029.63      2618338.20      6982421.99
      2618221.01      6982057.40      2616950.12      6981749.44
#Sta/Elev= 30
  3404.5  500.60  4118.3  487.99  4237.1  495.03  4433.3  480.19  4433.8  479.69
  4438.0  480.19  4440.8  484.65  4468.7  481.46  4473.9  484.97  4540.0  480.48
  4545.2  485.43  4644.4  481.71  4649.6  485.81  4677.5  482.67  4682.7  486.13
  4748.8  482.04  4754.0  486.67  4853.2  482.30  4858.4  486.40  4891.5  486.80
  5055.1  484.42  5060.4  488.83  5156.7  485.81  5161.9  489.41  5220.9  487.63
  5411.6  495.44  5524.7  490.75  5576.2  498.22  6503.9  511.51  6693.5  513.34
#Mann=4,-1,0
  3404.5    0.05       0  4433.3    0.04       0  4438.0    0.05       0
  6503.9     0.1       0
Bank Sta=4433.3,4438
Exp/Cntr=0.3,0.1

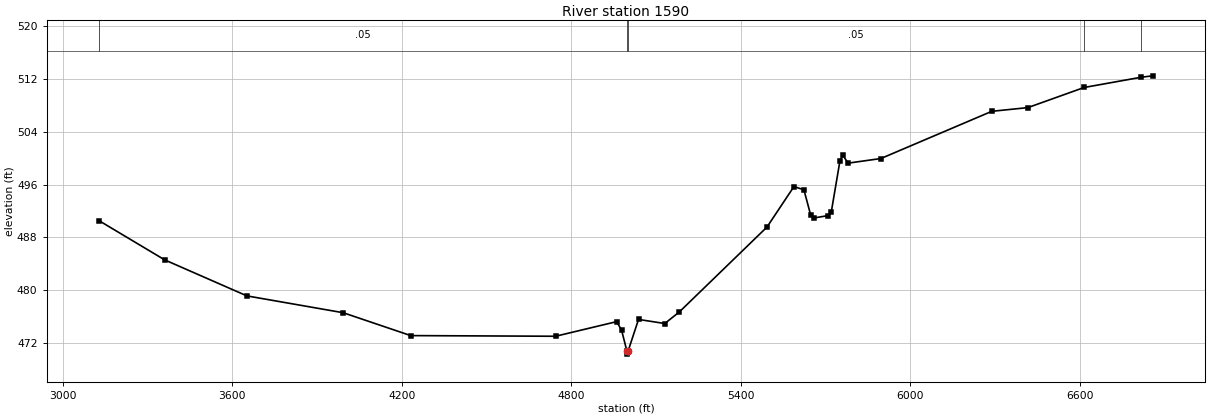
Type RM Length L Ch R = 1,1590,0,0,0
BEGIN DESCRIPTION:
Brushy Creek Trib 2 1.0
END DESCRIPTION:
XS GIS Cut Line= 4
      2618598.89      6983875.73      2619055.98      6982737.67
      2618782.68      6982154.34      2616985.01      6981683.53
#Sta/Elev= 30
  3129.4  490.51  3360.8  484.59  3651.8  479.13  3992.4  476.58  4231.7  473.11
  4744.4  473.01  4960.9  475.23  4978.2  473.91  4996.7  470.80  4997.2  470.30
  5001.4  470.80  5038.0  475.56  5131.0  474.94  5182.6  476.70  5492.8  489.57
  5588.2  495.71  5623.5  495.22  5647.8  491.33  5658.2  490.94  5709.8  491.31
  5720.2  491.81  5751.2  499.65  5761.5  500.45  5779.9  499.26  5895.9  499.96
  6288.7  507.12  6416.2  507.68  6615.2  510.73  6818.1  512.29  6858.3  512.50
#Mann=5,-1,0
  3129.4    0.05       0  4996.7    0.04       0  5001.4    0.05       0
  6615.2     0.1       0  6818.1    0.05       0
Bank Sta=4996.7,5001.4
Exp/Cntr=0.3,0.1

Chan Stop Cuts=-1