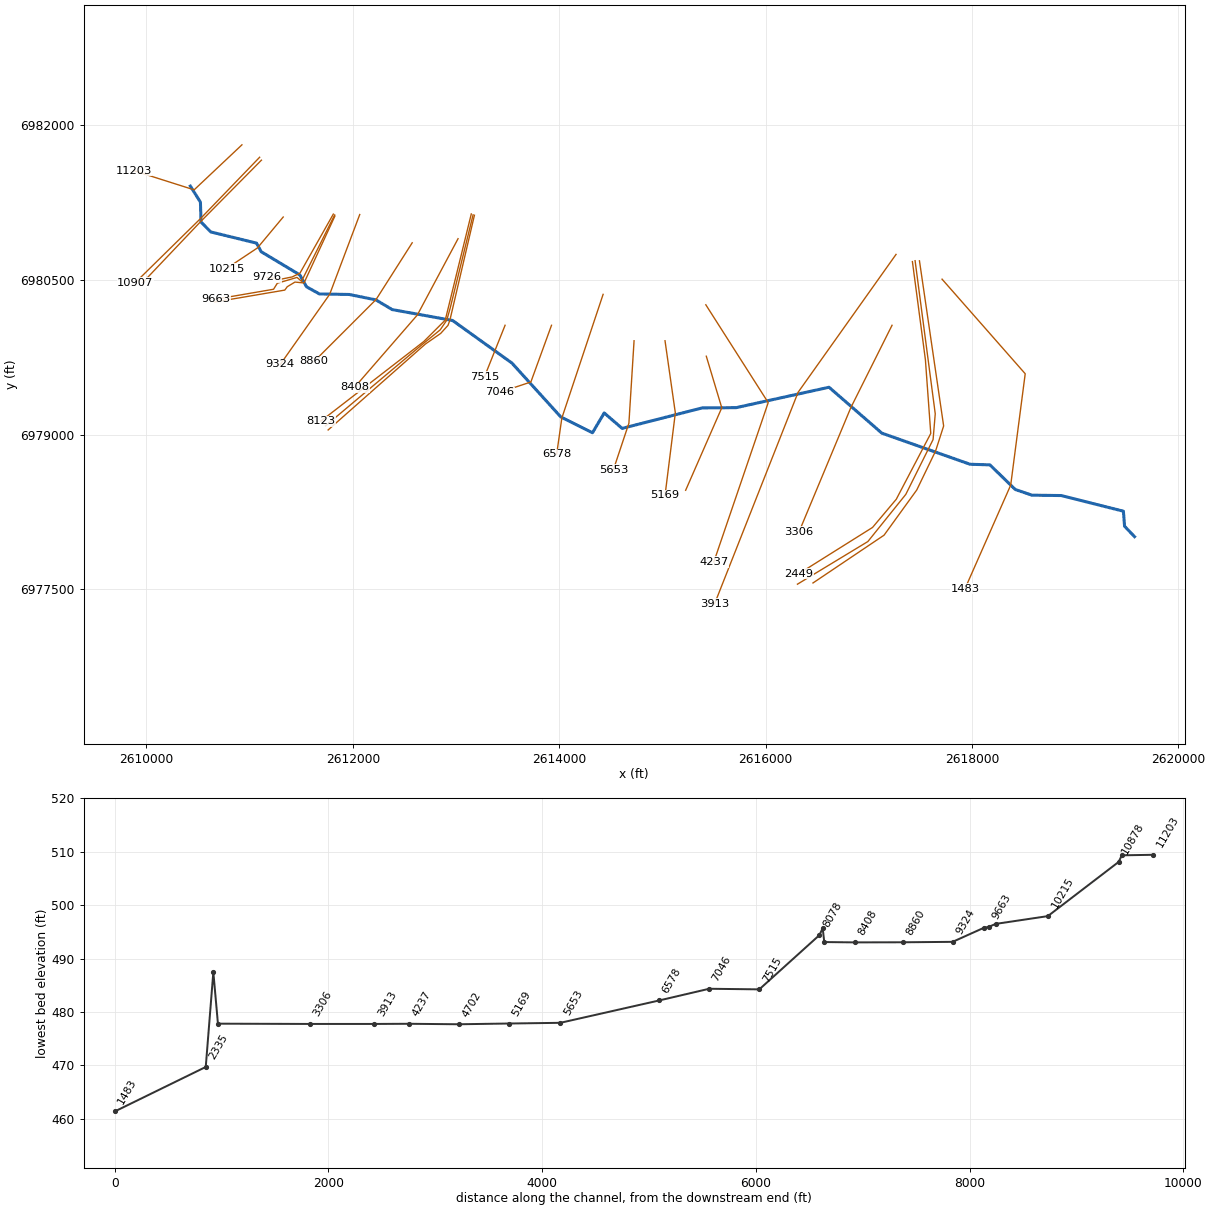
--- Brushy Creek Trib 3.prj (project) ---

Proj Title=Brushy Creek Trib 3 Base Level Engineering
Current Plan=p01
Default Exp/Contr=0.3,0.1
English Units
Geom File=g01
Flow File=f01
Plan File=p01
BEGIN DESCRIPTION:
Brushy Creek Trib 3
END DESCRIPTION:

--- Brushy Creek Trib 3.p01 (plan) ---

Plan Title=Multiple Run
Short Identifier=Multiple
Geom File=g01
Flow File=f01
Subcritical Flow
K Sum by GR= 0
Std Step Tol= 0.01
Critical Tol= 0.01
Num of Std Step Trials= 20
Max Error Tol= 0.3
Flow Tol Ratio= 0.001
Split Flow NTrial= 30
Split Flow Tol= 0.02
Split Flow Ratio= 0.02
Log Output Level= 0
Friction Slope Method= 1
Unsteady Friction Slope Method= 2
Unsteady Bridges Friction Slope Method= 1
Parabolic Critical Depth
Global Vel Dist=  1 , 1 , 1
Global Log Level= 0
CheckData=True
Encroach Param= -1, 0, 0, 0
BEGIN DESCRIPTION:
Multiple Run
END DESCRIPTION:

--- Brushy Creek Trib 3.f01 (steady flow) ---

Flow Title=Multiple
Number of Profiles=7
Profile Names=10-year,25-year,50-year,1pct_min,100-year,1pct_plu,500-year
River Rch & RM= Brushy Creek Tri,Reach-1,11203
     593     797     964     578    1154    2302    1652
River Rch & RM= Brushy Creek Tri,Reach-1,8860
     768    1047    1277     772    1541    3074    2242
River Rch & RM= Brushy Creek Tri,Reach-1,5653
     828    1130    1378     833    1662    3316    2416
River Rch & RM= Brushy Creek Tri,Reach-1,3306
    1353    1894    2350    1443    2878    5743    4319
River Rch & RM= Brushy Creek Tri,Reach-1,2335
    1496    2106    2624    1616    3225    6435    4877
Boundary for River Rch & Prof#=Brushy Creek Tri,Reach-1,1
Up Type=0
Dn Type=3
Dn Slope=0.005
Boundary for River Rch & Prof#=Brushy Creek Tri,Reach-1,2
Up Type=0
Dn Type=3
Dn Slope=0.005
Boundary for River Rch & Prof#=Brushy Creek Tri,Reach-1,3
Up Type=0
Dn Type=3
Dn Slope=0.005
Boundary for River Rch & Prof#=Brushy Creek Tri,Reach-1,4
Up Type=0
Dn Type=3
Dn Slope=0.005
Boundary for River Rch & Prof#=Brushy Creek Tri,Reach-1,5
Up Type=0
Dn Type=3
Dn Slope=0.005
Boundary for River Rch & Prof#=Brushy Creek Tri,Reach-1,6
Up Type=0
Dn Type=3
Dn Slope=0.005
Boundary for River Rch & Prof#=Brushy Creek Tri,Reach-1,7
Up Type=0
Dn Type=3
Dn Slope=0.005

--- Brushy Creek Trib 3.g01 (geometry) ---

Geom Title=Existing Conditions

River Reach=Brushy Creek Tri,Reach-1
Reach XY= 30
      2610426.00      6981411.00      2610523.77      6981255.08
      2610529.53      6981062.45      2610623.56      6980966.52
      2611067.51      6980857.47      2611112.47      6980774.55
      2611485.99      6980550.35      2611552.16      6980433.86
      2611677.55      6980364.75      2611965.50      6980359.78
      2612224.45      6980307.25      2612381.93      6980213.24
      2612967.52      6980107.51      2613542.67      6979694.35
      2614016.32      6979171.76      2614322.88      6979018.52
      2614436.85      6979210.68      2614610.58      6979061.03
      2615386.50      6979259.78      2615715.50      6979262.22
      2616615.52      6979460.07      2617127.58      6979014.83
      2617981.94      6978713.26      2618174.54      6978707.46
      2618419.83      6978468.86      2618581.94      6978413.26
      2618865.50      6978409.78      2619468.08      6978258.08
      2619479.46      6978112.27      2619576.00      6978011.00

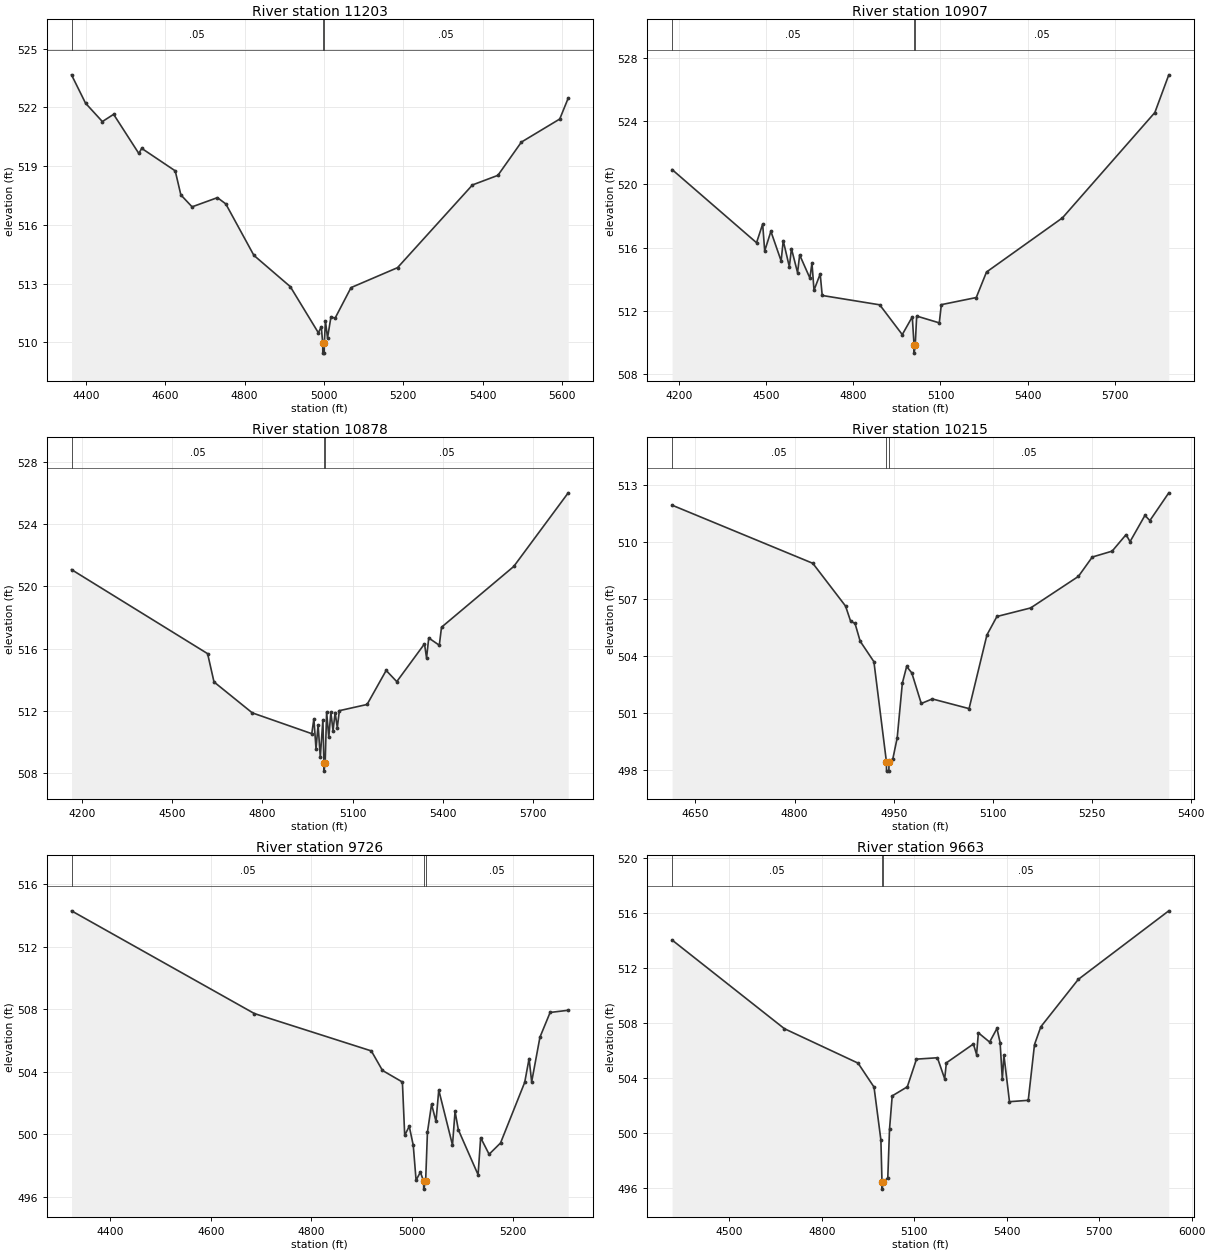
Type RM Length L Ch R = 1,11203,296,296,296
BEGIN DESCRIPTION:
Brushy Creek Trib 3 22.0
END DESCRIPTION:
XS GIS Cut Line= 3
      2610925.97      6981810.98      2610462.71      6981374.35
      2609875.98      6981561.01
#Sta/Elev= 30
  4363.4  523.67  4398.8  522.22  4441.2  521.28  4469.6  521.65  4533.1  519.65
  4540.4  519.91  4624.9  518.76  4639.1  517.53  4667.4  516.92  4731.3  517.39
  4752.4  517.07  4823.2  514.44  4915.0  512.84  4985.8  510.48  4993.1  510.79
  4996.8  509.94  4997.0  509.44  5000.5  509.44  5000.8  509.94  5003.6  511.08
  5008.9  510.22  5017.5  511.29  5028.0  511.23  5068.1  512.79  5185.4  513.81
  5374.3  518.04  5438.4  518.53  5497.6  520.23  5594.3  521.41  5615.7  522.48
#Mann=3,-1,0
  4363.4    0.05       0  4996.8    0.03       0  5000.8    0.05       0
Bank Sta=4996.8,5000.8
Exp/Cntr=0.3,0.1

Type RM Length L Ch R = 1,10907,29,29,29
BEGIN DESCRIPTION:
Mapping XS d5a9d455
END DESCRIPTION:
XS GIS Cut Line= 3
      2611097.56      6981690.62      2610522.49      6981093.85
      2609893.46      6980475.67
#Sta/Elev= 30
  4175.6  520.93  4466.5  516.31  4487.6  517.49  4494.6  515.79  4515.9  517.03
  4551.2  515.16  4558.4  516.44  4579.5  514.79  4586.7  515.94  4607.8  514.42
  4615.0  515.54  4650.2  514.08  4657.4  515.03  4664.4  513.31  4685.7  514.34
  4692.7  512.98  4890.7  512.39  4968.4  510.51  5002.9  511.63  5009.0  509.84
  5009.3  509.34  5013.0  509.84  5018.0  511.68  5095.9  511.25  5102.9  512.40
  5223.2  512.85  5258.5  514.46  5520.1  517.88  5838.3  524.53  5886.3  526.91
#Mann=3,-1,0
  4175.6    0.05       0  5009.0    0.03       0  5013.0    0.05       0
Bank Sta=5009,5013
Exp/Cntr=0.3,0.1

Type RM Length L Ch R = 1,10878,663,663,663
BEGIN DESCRIPTION:
Mapping XS fc287310
END DESCRIPTION:
XS GIS Cut Line= 3
      2611114.97      6981662.46      2610526.83      6981067.81
      2609965.06      6980475.67
#Sta/Elev= 30
  4164.8  521.08  4617.6  515.67  4638.9  513.85  4766.2  511.86  4964.2  510.52
  4971.2  511.48  4978.3  509.55  4985.3  511.09  4992.5  509.01  5001.2  511.42
  5004.7  508.61  5004.9  508.11  5008.7  508.61  5013.6  511.92  5020.8  510.29
  5027.7  511.89  5035.0  510.72  5041.9  511.88  5049.1  510.91  5056.0  512.00
  5148.2  512.40  5211.7  514.59  5247.0  513.87  5339.2  516.30  5346.1  515.39
  5353.3  516.68  5388.5  516.21  5395.8  517.37  5636.1  521.28  5817.4  526.02
#Mann=3,-1,0
  4164.8    0.05       0  5004.7    0.05       0  5008.7    0.05       0
Bank Sta=5004.7,5008.7
Exp/Cntr=0.3,0.1

Type RM Length L Ch R = 1,10215,489,489,489
BEGIN DESCRIPTION:
Brushy Creek Trib 3 20.0
END DESCRIPTION:
XS GIS Cut Line= 3
      2611326.00      6981111.00      2611076.00      6980811.00
      2610775.97      6980610.98
#Sta/Elev= 30
  4614.7  511.95  4827.5  508.89  4877.0  506.64  4884.8  505.83  4891.3  505.73
  4899.1  504.79  4919.9  503.71  4938.8  498.45  4939.0  497.95  4942.5  497.95
  4942.8  498.45  4948.6  498.61  4955.1  499.70  4962.9  502.58  4969.4  503.46
  4977.2  503.12  4991.5  501.51  5008.2  501.75  5063.8  501.24  5090.8  505.12
  5105.9  506.09  5156.9  506.54  5229.1  508.20  5250.1  509.22  5280.1  509.53
  5301.2  510.40  5307.2  510.03  5329.7  511.41  5337.2  511.14  5365.8  512.60
#Mann=3,-1,0
  4614.7    0.05       0  4938.8    0.03       0  4942.8    0.05       0
Bank Sta=4938.8,4942.8
Exp/Cntr=0.3,0.1

Type RM Length L Ch R = 1,9726,63,63,63
BEGIN DESCRIPTION:
Mapping XS 0be519be
END DESCRIPTION:
XS GIS Cut Line= 5
      2611811.57      6981139.45      2611488.20      6980566.51
      2611412.19      6980529.72      2611303.74      6980507.92
      2611170.31      6980525.90
#Sta/Elev= 30
  4323.1  514.29  4686.7  507.72  4919.2  505.33  4941.4  504.08  4981.0  503.34
  4985.6  499.93  4994.6  500.51  5002.6  499.29  5008.2  497.06  5016.8  497.58
  5023.2  496.99  5023.4  496.49  5027.2  496.99  5030.8  500.13  5039.0  501.92
  5047.8  500.82  5053.3  502.83  5080.6  499.31  5085.7  501.46  5092.2  500.29
  5131.5  497.41  5136.6  499.78  5153.4  498.72  5176.1  499.44  5224.2  503.32
  5232.9  504.84  5238.0  503.35  5254.5  506.21  5274.7  507.79  5310.7  507.93
#Mann=3,-1,0
  4323.1    0.05       0  5023.2    0.03       0  5027.2    0.05       0
Bank Sta=5023.2,5027.2
Exp/Cntr=0.3,0.1

Type RM Length L Ch R = 1,9663,47,47,47
BEGIN DESCRIPTION:
Mapping XS d81d4e3c
END DESCRIPTION:
XS GIS Cut Line= 6
      2611824.57      6981130.74      2611503.16      6980487.71
      2611459.76      6980525.21      2611269.02      6980468.85
      2611232.40      6980410.42      2610676.59      6980314.78
#Sta/Elev= 30
  4314.2  514.03  4678.7  507.59  4917.6  505.09  4969.4  503.35  4991.7  499.51
  4995.3  496.44  4995.6  495.94  4999.3  496.44  5014.1  496.77  5019.7  500.29
  5028.4  502.71  5077.4  503.37  5107.2  505.38  5175.1  505.48  5198.7  503.95
  5204.1  505.11  5291.9  506.48  5302.1  505.71  5308.0  507.29  5344.5  506.62
  5368.3  507.61  5378.5  506.58  5385.7  503.91  5390.8  505.68  5408.9  502.29
  5469.8  502.39  5490.1  506.44  5510.6  507.73  5632.1  511.17  5925.8  516.15
#Mann=3,-1,0
  4314.2    0.05       0  4995.3    0.03       0  4999.3    0.05       0
Bank Sta=4995.3,4999.3
Exp/Cntr=0.3,0.1

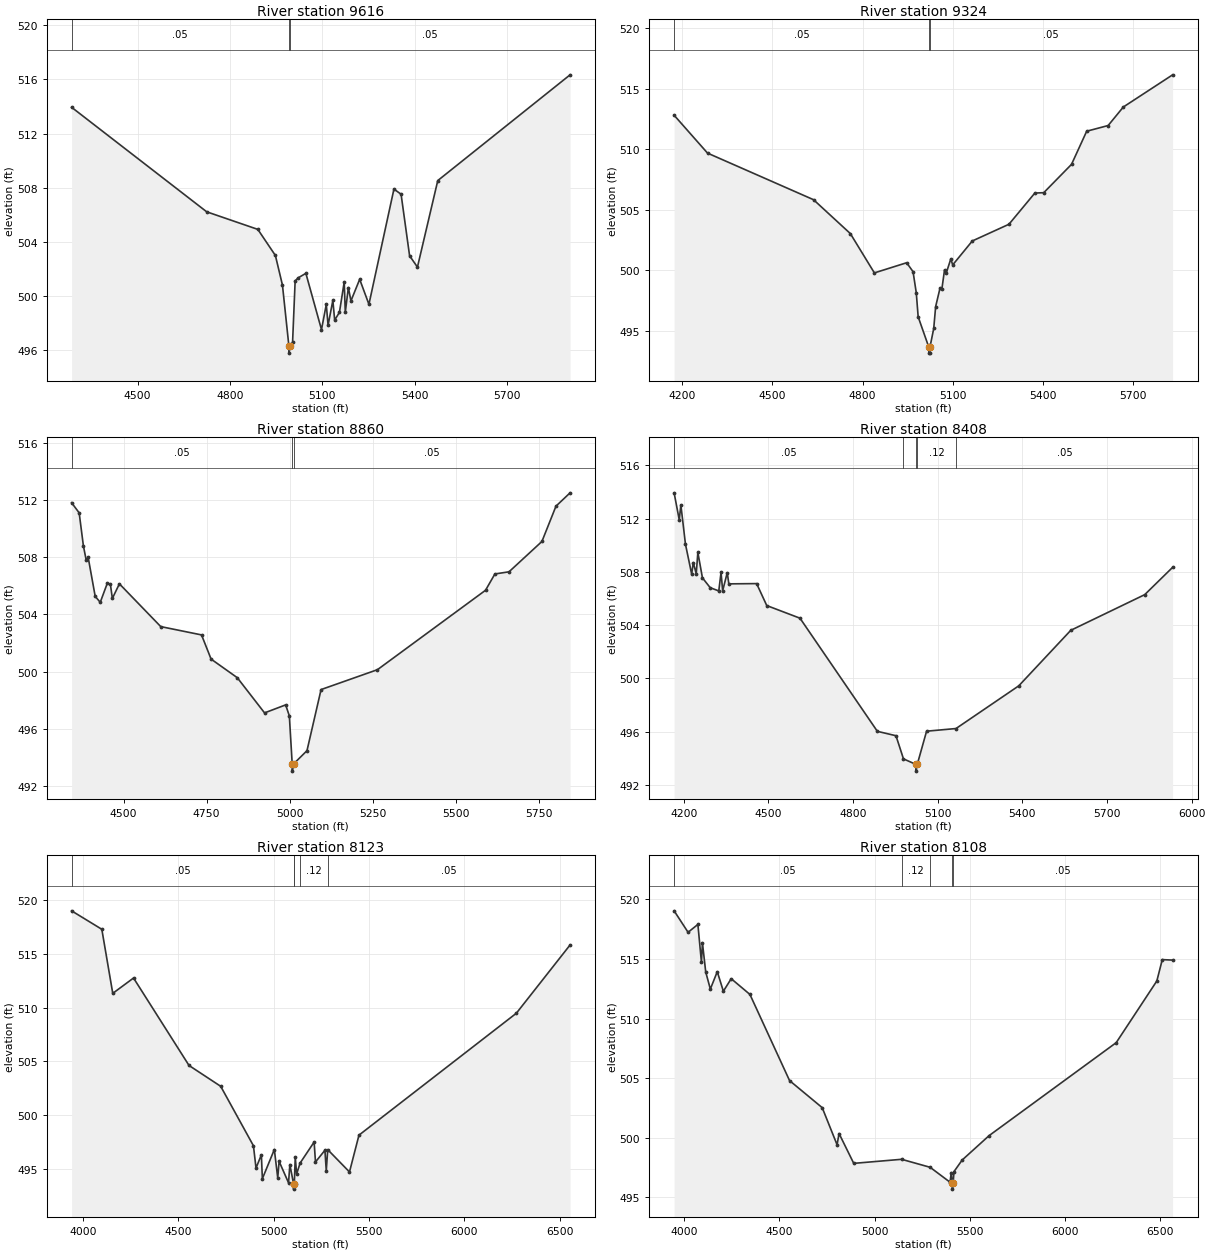
Type RM Length L Ch R = 1,9616,292,292,292
BEGIN DESCRIPTION:
Mapping XS f3debd4c
END DESCRIPTION:
XS GIS Cut Line= 6
      2611826.75      6981119.91      2611527.50      6980471.53
      2611439.97      6980480.07      2611364.97      6980434.93
      2611341.36      6980402.29      2610663.56      6980286.56
#Sta/Elev= 30
  4285.9  513.94  4724.5  506.21  4890.5  504.91  4947.5  502.98  4970.4  500.79
  4991.4  496.26  4991.6  495.76  4995.4  496.26  5003.3  496.58  5011.6  501.10
  5021.6  501.33  5046.4  501.66  5097.1  497.50  5112.7  499.36  5118.5  497.82
  5134.0  499.66  5139.9  498.20  5155.4  498.78  5170.9  501.02  5174.4  498.79
  5184.4  500.61  5192.7  499.62  5221.1  501.22  5251.1  499.37  5332.3  507.89
  5355.5  507.51  5383.1  502.96  5408.6  502.12  5474.6  508.52  5904.1  516.34
#Mann=3,-1,0
  4285.9    0.05       0  4991.4    0.03       0  4995.4    0.05       0
Bank Sta=4991.4,4995.4
Exp/Cntr=0.3,0.1

Type RM Length L Ch R = 1,9324,464,464,464
BEGIN DESCRIPTION:
Brushy Creek Trib 3 18.0
END DESCRIPTION:
XS GIS Cut Line= 3
      2612067.63      6981135.09      2611776.00      6980361.00
      2611297.21      6979681.07
#Sta/Elev= 30
  4172.7  512.79  4283.9  509.66  4636.6  505.81  4759.1  503.01  4839.1  499.76
  4946.5  500.60  4967.8  499.86  4978.5  498.12  4984.8  496.13  5020.1  493.63
  5020.4  493.13  5023.9  493.13  5024.1  493.63  5036.6  495.17  5043.0  496.98
  5057.8  498.53  5063.9  498.46  5072.6  500.02  5078.7  499.78  5093.5  500.92
  5099.7  500.42  5165.0  502.40  5286.9  503.78  5373.1  506.36  5402.7  506.39
  5495.1  508.73  5545.6  511.47  5617.0  511.94  5667.5  513.47  5831.5  516.13
#Mann=3,-1,0
  4172.7    0.05       0  5020.1    0.03       0  5024.1    0.05       0
Bank Sta=5020.1,5024.1
Exp/Cntr=0.3,0.1

Type RM Length L Ch R = 1,8860,452,452,452
BEGIN DESCRIPTION:
Brushy Creek Trib 3 17.0
END DESCRIPTION:
XS GIS Cut Line= 3
      2612575.99      6980860.98      2612226.00      6980311.00
      2611626.02      6979711.02
#Sta/Elev= 30
  4343.6  511.81  4366.4  511.10  4379.1  508.80  4387.6  507.79  4393.5  507.99
  4414.7  505.26  4429.9  504.85  4451.1  506.18  4460.4  506.11  4466.3  505.12
  4487.5  506.14  4612.0  503.15  4734.7  502.57  4763.5  500.88  4842.3  499.58
  4924.4  497.12  4987.9  497.68  4999.0  496.91  5007.6  493.55  5007.9  493.05
  5011.6  493.55  5052.1  494.48  5094.5  498.75  5264.2  500.14  5589.5  505.69
  5617.7  506.83  5660.2  506.98  5759.2  509.10  5801.6  511.57  5844.0  512.50
#Mann=3,-1,0
  4343.6    0.05       0  5007.6    0.03       0  5011.6    0.05       0
Bank Sta=5007.6,5011.6
Exp/Cntr=0.3,0.1

Type RM Length L Ch R = 1,8408,285,285,285
BEGIN DESCRIPTION:
Brushy Creek Trib 3 16.0
END DESCRIPTION:
XS GIS Cut Line= 3
      2613020.32      6980900.70      2612626.00      6980161.00
      2612017.69      6979459.70
#Sta/Elev= 30
  4165.9  513.94  4184.1  511.91  4189.8  513.03  4206.1  510.08  4228.1  507.83
  4233.7  508.70  4244.3  507.87  4250.0  509.46  4266.3  507.55  4293.9  506.81
  4324.2  506.57  4332.2  507.96  4337.9  506.58  4354.2  507.94  4359.8  507.10
  4458.3  507.12  4494.2  505.47  4612.0  504.52  4886.2  496.02  4952.1  495.69
  4978.7  493.95  5023.5  493.53  5023.8  493.03  5027.5  493.53  5060.6  496.03
  5164.9  496.23  5387.4  499.44  5571.6  503.61  5833.7  506.29  5932.5  508.34
#Mann=5,-1,0
  4165.9    0.05       0  4978.7    0.12       0  5023.5    0.07       0
  5027.5    0.12       0  5164.9    0.05       0
Bank Sta=5023.5,5027.5
Exp/Cntr=0.3,0.1

Type RM Length L Ch R = 1,8123,15,15,15
BEGIN DESCRIPTION:
Mapping XS d27a0390
END DESCRIPTION:
XS GIS Cut Line= 4
      2613148.57      6981140.83      2612896.25      6980111.29
      2612687.64      6979903.03      2611690.61      6979131.60
#Sta/Elev= 30
  3940.0  519.02  4098.6  517.30  4156.0  511.33  4265.0  512.76  4556.2  504.61
  4722.3  502.67  4894.1  497.13  4907.6  495.05  4935.7  496.29  4940.9  494.06
  5003.7  496.78  5021.6  494.14  5028.7  495.68  5078.2  493.68  5085.2  495.38
  5104.5  493.59  5104.7  493.09  5108.5  493.59  5113.5  496.08  5120.6  494.50
  5139.0  495.52  5212.5  497.48  5219.6  495.62  5269.1  496.71  5276.2  494.80
  5283.8  496.77  5398.0  494.69  5447.8  498.12  6273.6  509.48  6555.4  515.84
#Mann=5,-1,0
  3940.0    0.05       0  5104.5    0.03       0  5108.5    0.05       0
  5139.0    0.12       0  5283.8    0.05       0
Bank Sta=5104.5,5108.5
Exp/Cntr=0.3,0.1

Type RM Length L Ch R = 1,8108,30,30,30
BEGIN DESCRIPTION:
Mapping XS fc7ca9a4
END DESCRIPTION:
XS GIS Cut Line= 6
      2613165.93      6981132.18      2612944.58      6980229.41
      2612911.18      6980110.93      2612847.36      6980016.74
      2612665.07      6979868.30      2611735.09      6979084.80
#Sta/Elev= 30
  3947.4  519.03  4020.7  517.23  4072.2  517.89  4090.9  514.71  4096.0  516.36
  4113.4  513.90  4137.6  512.47  4174.0  513.93  4206.0  512.29  4247.2  513.34
  4345.5  512.02  4553.5  504.80  4725.0  502.53  4803.0  499.42  4813.5  500.36
  4890.5  497.86  5141.9  498.20  5291.7  497.53  5396.2  496.28  5402.7  497.09
  5408.5  496.20  5408.8  495.70  5412.5  496.20  5417.0  497.17  5459.9  498.14
  5601.7  500.19  6268.8  507.98  6482.1  513.15  6510.7  514.94  6564.9  514.90
#Mann=5,-1,0
  3947.4    0.05       0  5141.9    0.12       0  5291.7    0.05       0
  5408.5    0.03       0  5412.5    0.05       0
Bank Sta=5408.5,5412.5
Exp/Cntr=0.3,0.1

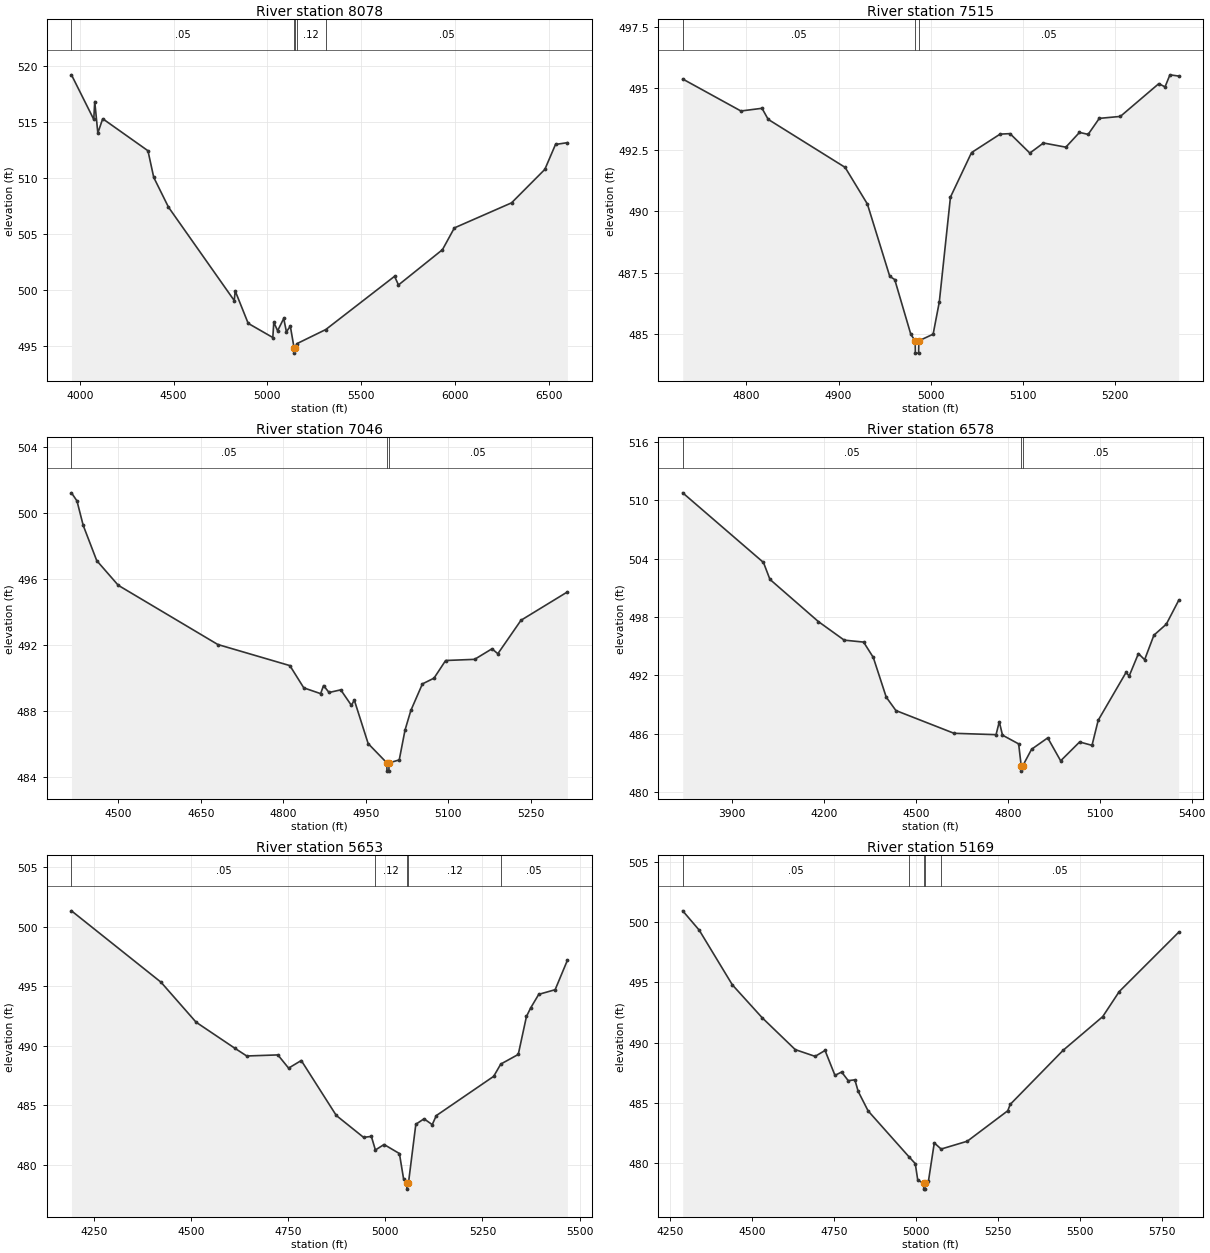
Type RM Length L Ch R = 1,8078,563,563,563
BEGIN DESCRIPTION:
Mapping XS 1c5abcaa
END DESCRIPTION:
XS GIS Cut Line= 6
      2613178.95      6981127.84      2612941.38      6980111.23
      2612922.88      6980060.14      2612851.70      6979982.02
      2612703.26      6979878.72      2611761.20      6979045.85
#Sta/Elev= 30
  3956.0  519.18  4074.8  515.21  4080.0  516.80  4096.5  514.00  4122.5  515.27
  4363.5  512.42  4394.3  510.05  4472.8  507.40  4823.2  499.08  4828.3  499.94
  4897.5  497.05  5028.7  495.79  5034.0  497.15  5054.3  496.39  5086.9  497.49
  5101.1  496.30  5122.0  496.80  5141.7  494.90  5141.9  494.40  5145.7  494.90
  5156.7  495.24  5310.9  496.50  5677.3  501.24  5698.2  500.47  5932.5  503.61
  5996.0  505.55  6300.5  507.78  6477.9  510.76  6534.8  512.98  6598.3  513.14
#Mann=5,-1,0
  3956.0    0.05       0  5141.7    0.03       0  5145.7    0.05       0
  5156.7    0.12       0  5310.9    0.05       0
Bank Sta=5141.7,5145.7
Exp/Cntr=0.3,0.1

Type RM Length L Ch R = 1,7515,469,469,469
BEGIN DESCRIPTION:
Brushy Creek Trib 3 14.0
END DESCRIPTION:
XS GIS Cut Line= 3
      2613475.98      6980060.95      2613376.00      6979811.00
      2613275.99      6979560.97
#Sta/Elev= 30
  4730.8  495.37  4794.0  494.07  4816.9  494.18  4823.6  493.73  4907.1  491.78
  4931.3  490.29  4955.6  487.35  4961.0  487.22  4978.5  484.99  4983.2  484.73
  4983.4  484.23  4986.9  484.23  4987.2  484.73  5002.7  485.00  5009.4  486.31
  5021.5  490.57  5044.4  492.38  5075.4  493.13  5086.2  493.15  5107.7  492.36
  5122.5  492.77  5146.8  492.60  5161.6  493.20  5171.0  493.12  5183.1  493.77
  5206.0  493.85  5247.7  495.18  5254.5  495.05  5259.8  495.54  5269.3  495.49
#Mann=3,-1,0
  4730.8    0.05       0  4983.2    0.03       0  4987.2    0.05       0
Bank Sta=4983.2,4987.2
Exp/Cntr=0.3,0.1

Type RM Length L Ch R = 1,7046,468,468,468
BEGIN DESCRIPTION:
Brushy Creek Trib 3 13.0
END DESCRIPTION:
XS GIS Cut Line= 3
      2613926.00      6980061.00      2613726.00      6979511.00
      2613425.97      6979410.99
#Sta/Elev= 30
  4414.8  501.22  4424.8  500.73  4436.1  499.25  4460.7  497.11  4499.9  495.61
  4680.8  492.02  4811.8  490.74  4837.1  489.39  4867.7  489.04  4873.0  489.53
  4883.0  489.11  4904.3  489.27  4923.6  488.33  4928.9  488.65  4954.1  486.01
  4988.1  484.84  4988.3  484.34  4991.8  484.34  4992.1  484.84  5010.6  485.02
  5021.1  486.83  5031.7  488.02  5052.7  489.63  5073.8  489.98  5094.9  491.05
  5147.6  491.12  5179.2  491.76  5189.8  491.46  5231.9  493.49  5316.3  495.21
#Mann=3,-1,0
  4414.8    0.05       0  4988.1    0.03       0  4992.1    0.05       0
Bank Sta=4988.1,4992.1
Exp/Cntr=0.3,0.1

Type RM Length L Ch R = 1,6578,925,925,925
BEGIN DESCRIPTION:
Brushy Creek Trib 3 12.0
END DESCRIPTION:
XS GIS Cut Line= 3
      2614426.00      6980360.99      2614026.00      6979161.00
      2613976.01      6978811.05
#Sta/Elev= 30
  3739.4  510.77  4002.9  503.61  4024.0  501.87  4182.1  497.53  4266.4  495.62
  4329.7  495.42  4361.3  493.84  4403.5  489.76  4435.1  488.38  4624.8  486.04
  4761.9  485.90  4772.4  487.23  4782.9  485.85  4835.6  484.95  4844.1  482.65
  4844.4  482.15  4848.2  482.65  4877.8  484.40  4930.5  485.57  4972.7  483.21
  5034.6  485.15  5075.0  484.80  5095.2  487.38  5186.1  492.30  5196.2  491.93
  5226.5  494.24  5246.7  493.61  5277.0  496.13  5317.4  497.26  5357.8  499.71
#Mann=3,-1,0
  3739.4    0.05       0  4844.1    0.03       0  4848.2    0.05       0
Bank Sta=4844.1,4848.2
Exp/Cntr=0.3,0.1

Type RM Length L Ch R = 1,5653,484,484,484
BEGIN DESCRIPTION:
Brushy Creek Trib 3 10.0
END DESCRIPTION:
XS GIS Cut Line= 3
      2614726.00      6979911.00      2614676.00      6979111.00
      2614526.00      6978661.00
#Sta/Elev= 30
  4192.6  501.35  4423.0  495.35  4513.2  491.99  4613.4  489.79  4643.5  489.15
  4723.6  489.24  4751.2  488.13  4783.8  488.77  4873.9  484.15  4944.1  482.31
  4964.1  482.39  4974.5  481.25  4996.8  481.71  5036.3  480.95  5046.9  478.84
  5055.3  478.46  5055.6  477.96  5059.5  478.46  5078.5  483.41  5099.6  483.87
  5120.7  483.38  5131.2  484.14  5278.8  487.44  5297.0  488.47  5342.0  489.28
  5363.1  492.47  5373.6  493.17  5394.7  494.33  5436.9  494.72  5468.5  497.20
#Mann=5,-1,0
  4192.6    0.05       0  4974.5    0.12       0  5055.3    0.07       0
  5059.5    0.12       0  5297.0    0.05       0
Bank Sta=5055.3,5059.5
Exp/Cntr=0.3,0.1

Type RM Length L Ch R = 1,5169,467,467,467
BEGIN DESCRIPTION:
Brushy Creek Trib 3 9.0
END DESCRIPTION:
XS GIS Cut Line= 3
      2615026.00      6979910.98      2615126.00      6979211.00
      2615026.00      6978411.01
#Sta/Elev= 30
  4288.0  500.95  4338.5  499.34  4439.5  494.80  4530.4  492.07  4631.4  489.42
  4692.0  488.86  4722.3  489.35  4752.6  487.28  4772.9  487.56  4793.1  486.84
  4813.3  486.91  4823.4  485.95  4853.7  484.33  4977.6  480.54  4997.6  479.95
  5005.2  478.57  5023.2  478.33  5023.5  477.83  5027.1  477.83  5027.5  478.33
  5037.9  478.51  5055.6  481.67  5076.5  481.16  5156.3  481.81  5279.8  484.34
  5287.3  484.87  5448.6  489.36  5569.5  492.16  5619.9  494.24  5801.3  499.17
#Mann=5,-1,0
  4288.0    0.05       0  4977.6     0.1       0  5023.2    0.07       0
  5027.5     0.1       0  5076.5    0.05       0
Bank Sta=5023.2,5027.5
Exp/Cntr=0.3,0.1

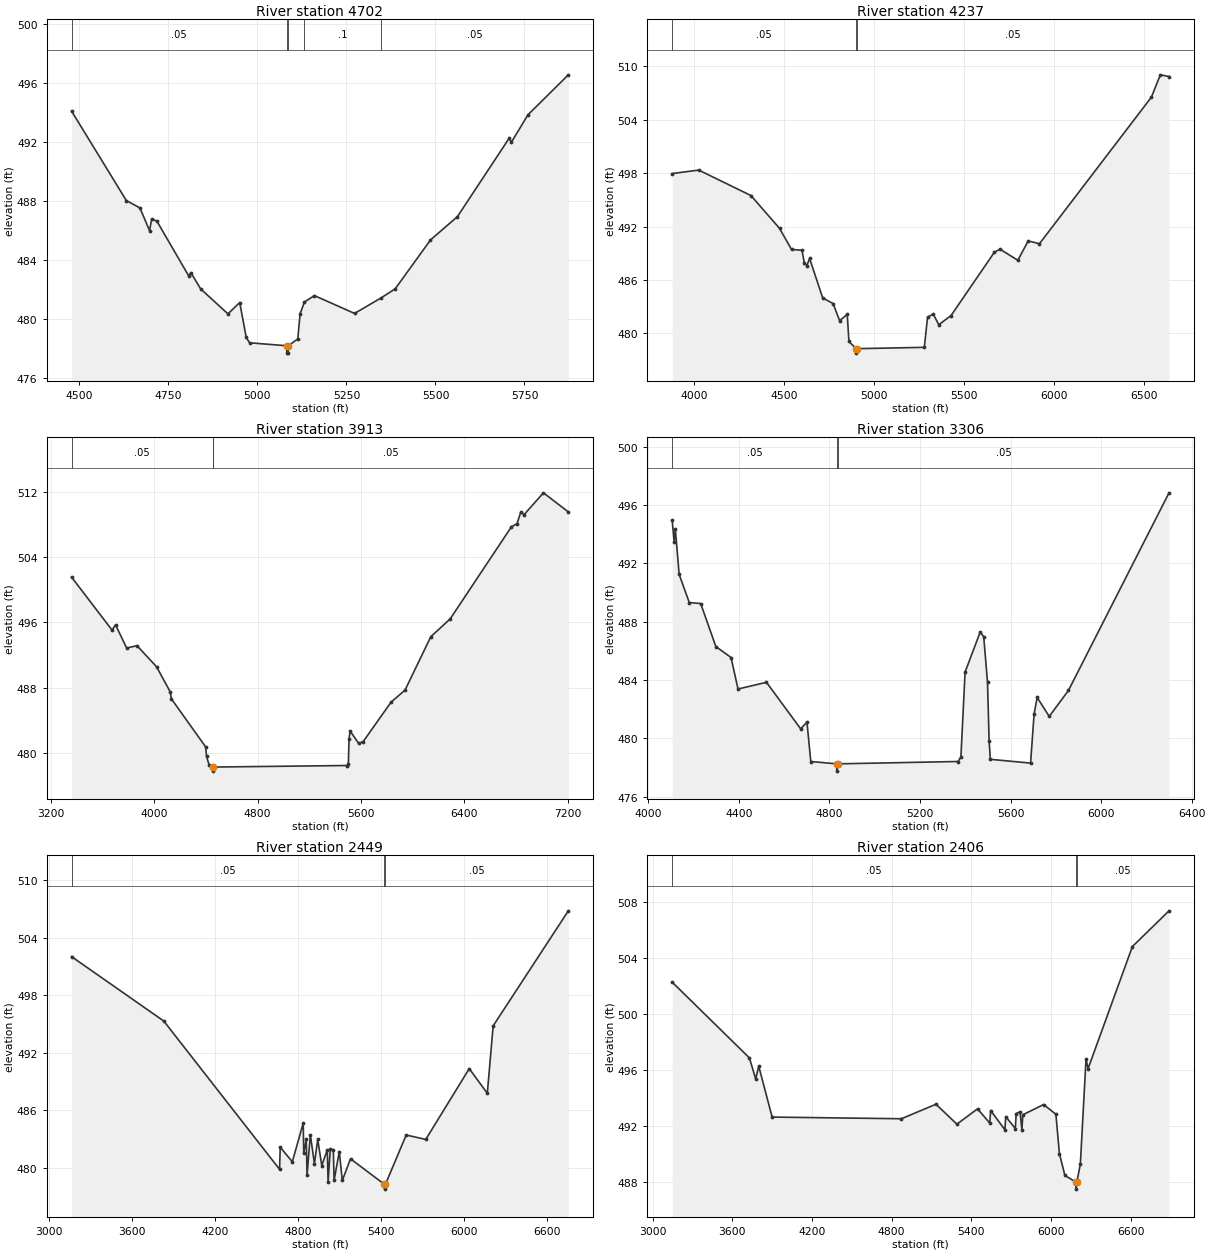
Type RM Length L Ch R = 1,4702,465,465,465
BEGIN DESCRIPTION:
Brushy Creek Trib 3 8.0
END DESCRIPTION:
XS GIS Cut Line= 3
      2615426.01      6979760.97      2615576.00      6979261.00
      2615226.00      6978460.99
#Sta/Elev= 30
  4478.0  494.10  4632.0  488.03  4670.2  487.53  4697.2  485.99  4703.3  486.79
  4718.1  486.62  4807.7  482.90  4812.9  483.15  4840.8  482.04  4917.3  480.35
  4950.4  481.12  4968.7  478.75  4978.2  478.39  5082.4  478.19  5082.8  477.69
  5086.4  477.69  5086.8  478.19  5113.4  478.65  5120.0  480.36  5132.0  481.15
  5160.2  481.59  5272.9  480.38  5347.9  481.44  5387.1  482.05  5486.1  485.36
  5561.7  486.94  5707.5  492.27  5713.0  491.97  5759.8  493.84  5873.2  496.55
#Mann=5,-1,0
  4478.0    0.05       0  5082.4    0.03       0  5086.8    0.05       0
  5132.0     0.1       0  5347.9    0.05       0
Bank Sta=5082.4,5086.8
Exp/Cntr=0.3,0.1

Type RM Length L Ch R = 1,4237,324,324,324
BEGIN DESCRIPTION:
Brushy Creek Trib 3 7.0
END DESCRIPTION:
XS GIS Cut Line= 3
      2615421.42      6980259.74      2616026.00      6979311.00
      2615498.79      6977765.34
#Sta/Elev= 30
  3879.2  497.95  4026.6  498.34  4316.4  495.48  4475.2  491.79  4541.7  489.42
  4599.6  489.34  4612.9  487.90  4626.7  487.61  4641.9  488.42  4714.7  483.98
  4772.3  483.35  4808.7  481.43  4851.0  482.13  4860.3  479.09  4900.4  478.28
  4900.8  477.78  4904.9  478.28  5278.9  478.43  5296.6  481.80  5328.0  482.17
  5359.3  480.97  5427.2  482.00  5667.4  489.10  5698.7  489.46  5798.0  488.21
  5855.4  490.38  5918.1  490.07  6539.5  506.53  6589.1  509.04  6637.3  508.85
#Mann=3,-1,0
  3879.2    0.05       0  4900.4    0.03       0  4904.9    0.05       0
Bank Sta=4900.4,4904.9
Exp/Cntr=0.3,0.1

Type RM Length L Ch R = 1,3913,607,607,607
BEGIN DESCRIPTION:
Brushy Creek Trib 3 6.0
END DESCRIPTION:
XS GIS Cut Line= 3
      2617264.77      6980748.40      2616315.82      6979411.45
      2615507.17      6977361.80
#Sta/Elev= 30
  3360.5  501.56  3674.0  495.05  3701.0  495.70  3787.2  492.85  3867.1  493.14
  4018.5  490.55  4125.5  487.43  4131.6  486.65  4398.6  480.71  4404.7  479.58
  4425.6  478.47  4452.9  478.25  4453.4  477.75  4457.5  478.25  5495.0  478.44
  5502.0  478.65  5507.3  481.75  5516.5  482.65  5580.5  481.18  5615.6  481.35
  5832.1  486.21  5940.3  487.69  6140.0  494.25  6289.4  496.42  6763.5  507.73
  6806.3  508.10  6836.1  509.54  6860.3  509.20  7010.8  511.89  7203.4  509.55
#Mann=3,-1,0
  3360.5    0.05       0  4452.9    0.03       0  4457.5    0.05       0
Bank Sta=4452.9,4457.5
Exp/Cntr=0.3,0.1

Type RM Length L Ch R = 1,3306,857,857,857
BEGIN DESCRIPTION:
Brushy Creek Trib 3 5.0
END DESCRIPTION:
XS GIS Cut Line= 3
      2617225.99      6980060.98      2616826.00      6979261.00
      2616326.00      6978061.00
#Sta/Elev= 30
  4105.6  494.94  4114.0  493.48  4119.5  494.34  4136.3  491.24  4181.0  489.31
  4231.4  489.24  4298.4  486.29  4365.5  485.54  4396.3  483.38  4522.0  483.84
  4673.0  480.65  4700.9  481.11  4717.7  478.41  4831.5  478.25  4832.6  477.75
  4838.7  478.25  5368.3  478.41  5380.8  478.72  5399.2  484.54  5465.8  487.28
  5481.5  486.97  5498.3  483.84  5505.4  479.83  5510.8  478.56  5688.5  478.30
  5704.2  481.69  5717.7  482.80  5770.8  481.50  5855.8  483.28  6300.0  496.83
#Mann=3,-1,0
  4105.6    0.05       0  4831.5    0.03       0  4838.7    0.05       0
Bank Sta=4831.5,4838.7
Exp/Cntr=0.3,0.1

Type RM Length L Ch R = 1,2449,43,43,43
BEGIN DESCRIPTION:
Mapping XS 6ba9e0b3
END DESCRIPTION:
XS GIS Cut Line= 6
      2617423.37      6980678.63      2617549.23      6979728.12
      2617601.32      6979011.98      2617267.12      6978373.96
      2617037.08      6978100.52      2616325.27      6977653.47
#Sta/Elev= 30
  3160.2  502.04  3828.2  495.32  4666.4  479.86  4671.0  482.17  4758.6  480.65
  4837.6  484.68  4841.3  481.52  4859.8  483.00  4865.2  479.25  4889.1  483.47
  4918.5  480.46  4942.4  482.98  4971.8  480.26  5011.8  481.89  5017.5  478.53
  5033.5  481.98  5055.3  481.91  5061.0  478.71  5098.7  481.72  5120.4  478.70
  5179.8  480.96  5425.3  478.30  5426.4  477.80  5432.6  478.30  5583.0  483.44
  5724.7  482.98  6039.3  490.36  6170.1  487.79  6212.5  494.82  6756.6  506.81
#Mann=3,-1,0
  3160.2    0.05       0  5425.3    0.03       0  5432.6    0.05       0
Bank Sta=5425.3,5432.6
Exp/Cntr=0.3,0.1

Type RM Length L Ch R = 1,2406,71,71,71
BEGIN DESCRIPTION:
Mapping XS cb66571b
END DESCRIPTION:
XS GIS Cut Line= 6
      2617449.41      6980687.28      2617644.72      6979202.95
      2617623.87      6978953.03      2617359.54      6978421.35
      2616991.92      6977963.88      2616309.45      6977550.24
#Sta/Elev= 30
  3147.9  502.28  3729.1  496.86  3776.6  495.35  3799.7  496.26  3900.5  492.62
  4873.9  492.50  5134.3  493.54  5292.0  492.11  5447.2  493.21  5539.6  492.19
  5545.9  493.09  5653.5  491.71  5659.9  492.65  5732.0  491.80  5738.4  492.87
  5767.2  493.00  5781.6  491.71  5788.0  492.78  5945.0  493.52  6037.4  492.82
  6063.9  490.01  6105.3  488.44  6188.2  487.96  6189.3  487.46  6195.5  487.96
  6221.7  489.27  6264.4  496.77  6279.9  496.09  6613.4  504.83  6889.4  507.39
#Mann=3,-1,0
  3147.9    0.05       0  6188.2    0.03       0  6195.5    0.05       0
Bank Sta=6188.2,6195.5
Exp/Cntr=0.3,0.1

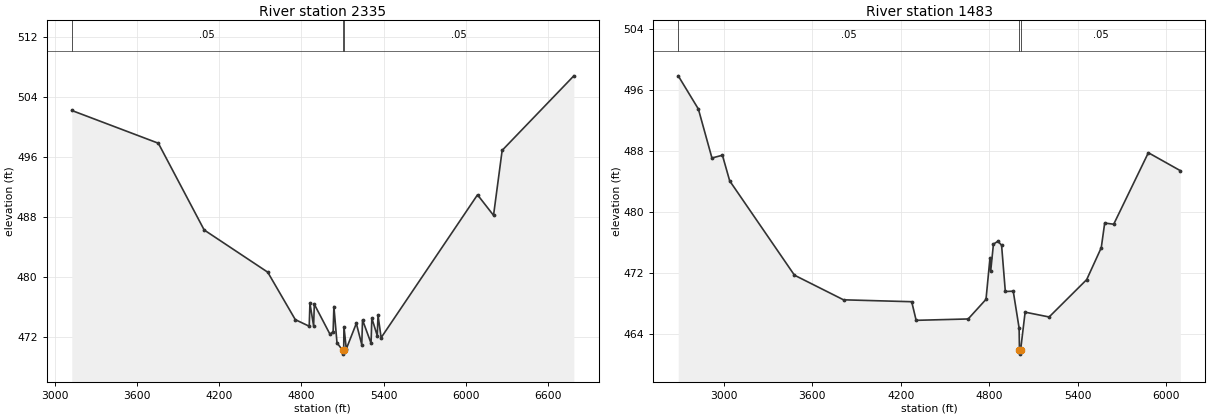
Type RM Length L Ch R = 1,2335,852,852,852
BEGIN DESCRIPTION:
Mapping XS ab29d9ba
END DESCRIPTION:
XS GIS Cut Line= 6
      2617491.72      6980686.25      2617726.10      6979084.68
      2617647.98      6978841.62      2617465.68      6978464.02
      2617148.84      6978025.65      2616459.85      6977561.99
#Sta/Elev= 30
  3124.0  502.19  3755.9  497.82  4090.4  486.25  4554.3  480.62  4755.5  474.29
  4857.1  473.41  4862.3  476.48  4889.2  473.46  4894.4  476.34  5009.1  472.33
  5031.7  472.70  5037.2  476.04  5059.8  471.20  5101.4  470.19  5102.5  469.69
  5108.7  470.19  5110.6  473.35  5127.7  470.38  5201.0  473.79  5240.7  470.95
  5246.2  474.25  5308.5  471.14  5314.1  474.49  5353.7  472.15  5359.3  474.88
  5381.9  471.88  6085.5  490.94  6202.4  488.20  6265.4  496.87  6788.6  506.81
#Mann=3,-1,0
  3124.0    0.05       0  5101.4    0.04       0  5108.7    0.05       0
Bank Sta=5101.4,5108.7
Exp/Cntr=0.3,0.1

Type RM Length L Ch R = 1,1483,0,0,0
BEGIN DESCRIPTION:
Brushy Creek Trib 3 1.0
END DESCRIPTION:
XS GIS Cut Line= 4
      2617710.62      6980508.38      2618516.57      6979590.97
      2618376.00      6978511.00      2617933.56      6977507.54
#Sta/Elev= 30
  2689.5  497.83  2826.1  493.48  2918.2  487.06  2989.3  487.42  3038.7  484.06
  3478.0  471.70  3811.0  468.47  4273.7  468.22  4303.9  465.78  4656.9  465.96
  4777.9  468.53  4804.6  473.89  4809.6  472.21  4828.3  475.77  4858.6  476.14
  4883.6  475.63  4909.0  469.56  4962.7  469.60  5002.5  464.78  5005.0  461.85
  5006.1  461.35  5012.4  461.85  5043.4  466.85  5206.2  466.22  5461.2  471.12
  5560.0  475.30  5583.3  478.53  5644.5  478.38  5879.6  487.75  6096.4  485.40
#Mann=3,-1,0
  2689.5    0.05       0  5005.0    0.03       0  5012.4    0.05       0
Bank Sta=5005,5012.4
Exp/Cntr=0.3,0.1

Chan Stop Cuts=-1