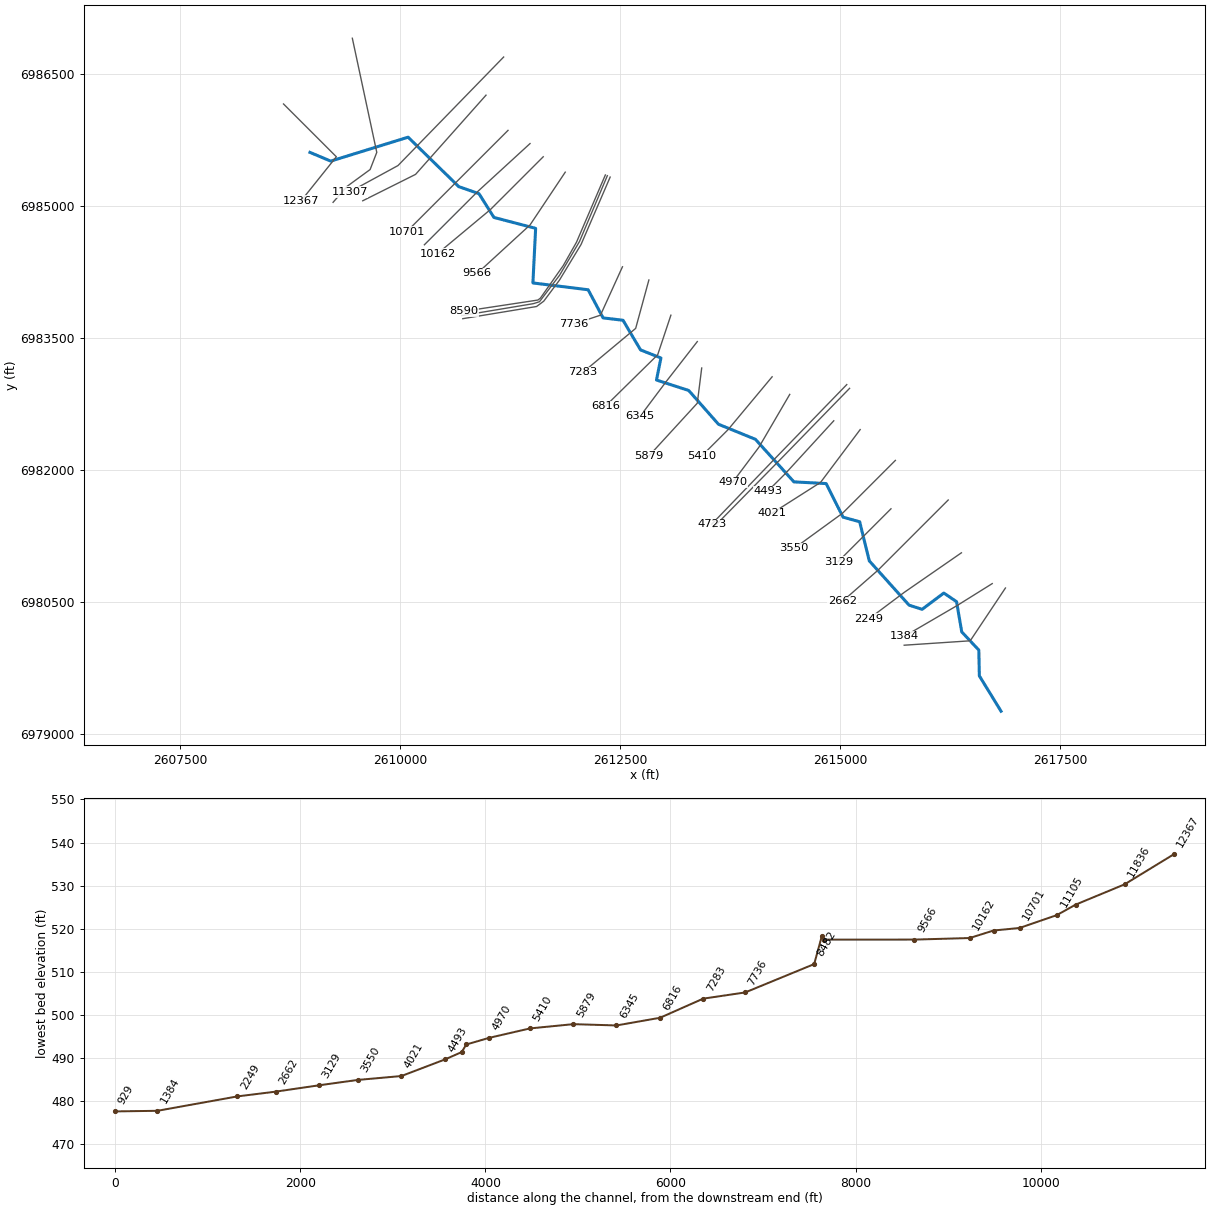
--- Brushy Creek Trib 3_1.prj (project) ---

Proj Title=Brushy Creek Trib 3_1 Base Level Engineering
Current Plan=p01
Default Exp/Contr=0.3,0.1
English Units
Geom File=g01
Flow File=f01
Plan File=p01
BEGIN DESCRIPTION:
Brushy Creek Trib 3_1
END DESCRIPTION:

--- Brushy Creek Trib 3_1.p01 (plan) ---

Plan Title=Multiple Run
Short Identifier=Multiple
Geom File=g01
Flow File=f01
Subcritical Flow
K Sum by GR= 0
Std Step Tol= 0.01
Critical Tol= 0.01
Num of Std Step Trials= 20
Max Error Tol= 0.3
Flow Tol Ratio= 0.001
Split Flow NTrial= 30
Split Flow Tol= 0.02
Split Flow Ratio= 0.02
Log Output Level= 0
Friction Slope Method= 1
Unsteady Friction Slope Method= 2
Unsteady Bridges Friction Slope Method= 1
Parabolic Critical Depth
Global Vel Dist=  1 , 1 , 1
Global Log Level= 0
CheckData=True
Encroach Param= -1, 0, 0, 0
BEGIN DESCRIPTION:
Multiple Run
END DESCRIPTION:

--- Brushy Creek Trib 3_1.f01 (steady flow) ---

Flow Title=Multiple
Number of Profiles=7
Profile Names=10-year,25-year,50-year,1pct_min,100-year,1pct_plu,500-year
River Rch & RM= Brushy Creek Tri,Reach-1,12367
     420     550     653     386     770    1536    1066
River Rch & RM= Brushy Creek Tri,Reach-1,7736
     685     925    1120     673    1342    2679    1926
River Rch & RM= Brushy Creek Tri,Reach-1,2662
     739    1000    1212     728    1453    2899    2087
Boundary for River Rch & Prof#=Brushy Creek Tri,Reach-1,1
Up Type=0
Dn Type=3
Dn Slope=0.005
Boundary for River Rch & Prof#=Brushy Creek Tri,Reach-1,2
Up Type=0
Dn Type=3
Dn Slope=0.005
Boundary for River Rch & Prof#=Brushy Creek Tri,Reach-1,3
Up Type=0
Dn Type=3
Dn Slope=0.005
Boundary for River Rch & Prof#=Brushy Creek Tri,Reach-1,4
Up Type=0
Dn Type=3
Dn Slope=0.005
Boundary for River Rch & Prof#=Brushy Creek Tri,Reach-1,5
Up Type=0
Dn Type=3
Dn Slope=0.005
Boundary for River Rch & Prof#=Brushy Creek Tri,Reach-1,6
Up Type=0
Dn Type=3
Dn Slope=0.005
Boundary for River Rch & Prof#=Brushy Creek Tri,Reach-1,7
Up Type=0
Dn Type=3
Dn Slope=0.005

--- Brushy Creek Trib 3_1.g01 (geometry) ---

Geom Title=Existing Conditions

River Reach=Brushy Creek Tri,Reach-1
Reach XY= 30
      2608976.00      6985611.00      2609212.08      6985511.65
      2610091.18      6985783.45      2610666.32      6985221.76
      2610896.20      6985141.39      2611066.00      6984871.65
      2611539.71      6984747.53      2611508.69      6984127.28
      2612136.08      6984049.90      2612305.45      6983730.44
      2612532.19      6983703.17      2612731.25      6983366.44
      2612962.76      6983274.75      2612912.25      6983024.20
      2613278.55      6982905.27      2613616.32      6982521.76
      2614036.10      6982350.61      2614473.70      6981866.83
      2614839.34      6981847.64      2615031.41      6981466.18
      2615220.29      6981413.59      2615329.41      6980969.44
      2615781.44      6980466.24      2615929.42      6980418.79
      2616176.08      6980603.70      2616320.81      6980505.56
      2616379.54      6980162.47      2616573.83      6979955.56
      2616579.75      6979662.55      2616826.00      6979261.00

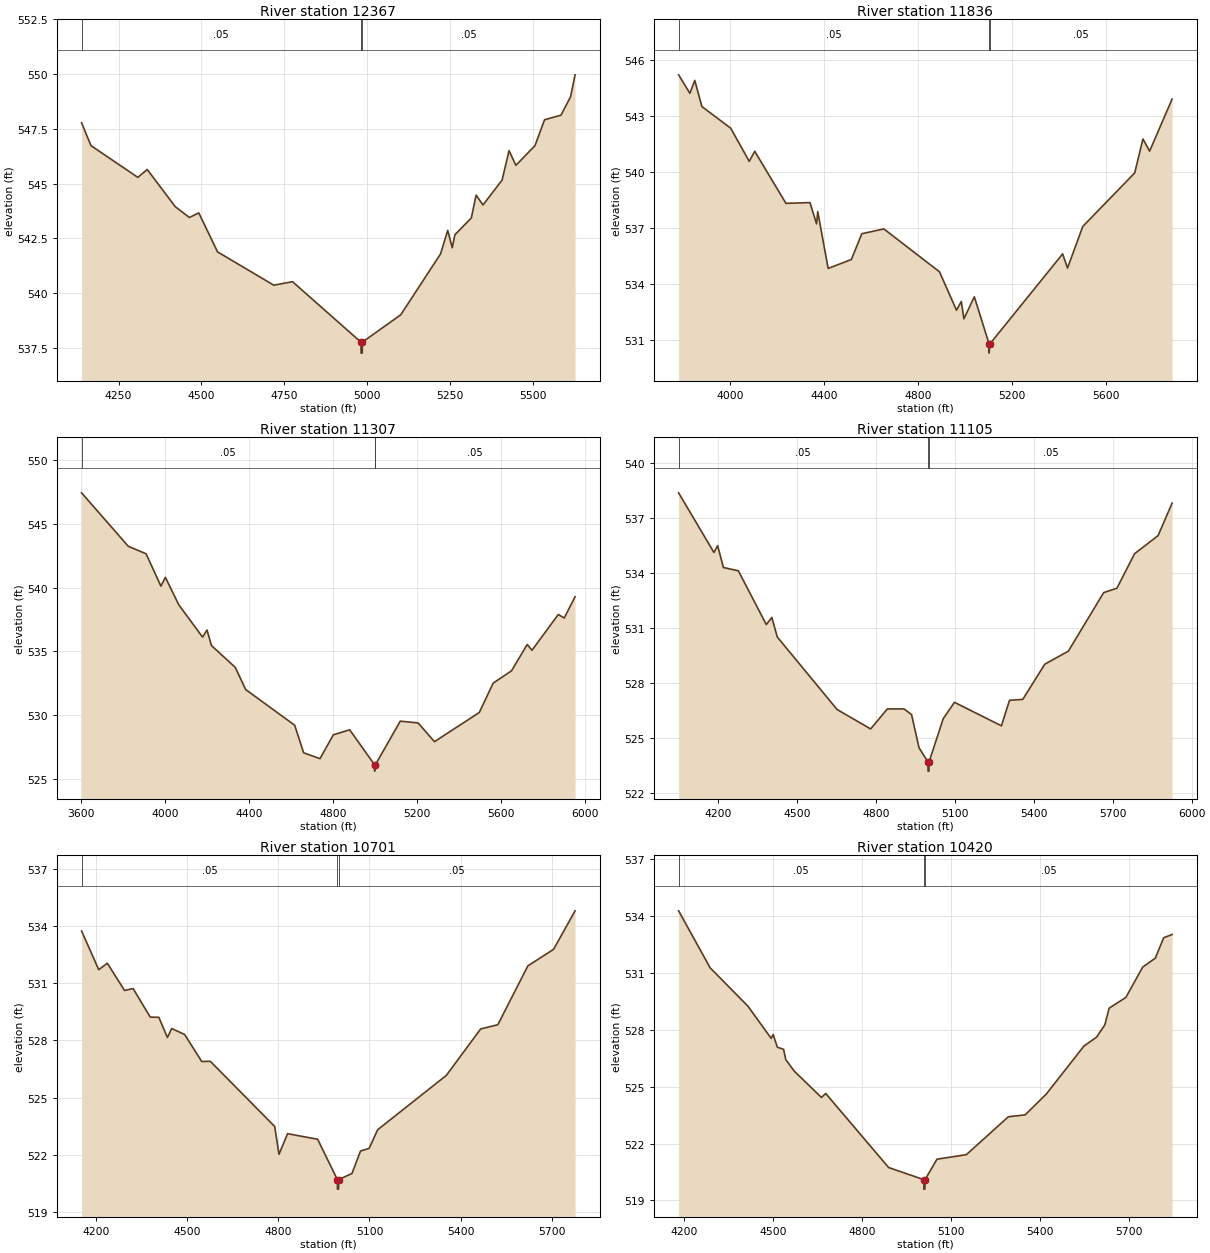
Type RM Length L Ch R = 1,12367,531,531,531
BEGIN DESCRIPTION:
Brushy Creek Trib 3_1 29.0
END DESCRIPTION:
XS GIS Cut Line= 3
      2608675.98      6986161.02      2609276.00      6985561.00
      2608875.98      6985060.98
#Sta/Elev= 30
  4138.6  547.77  4166.9  546.73  4308.3  545.28  4336.6  545.64  4421.5  543.94
  4463.9  543.45  4492.2  543.66  4548.8  541.88  4718.5  540.36  4775.0  540.52
  4981.6  537.76  4981.9  537.26  4985.4  537.26  4985.6  537.76  5101.6  539.01
  5221.7  541.79  5243.3  542.86  5256.9  542.07  5264.9  542.66  5314.5  543.43
  5328.9  544.47  5349.7  544.02  5407.4  545.16  5428.2  546.50  5449.0  545.83
  5506.6  546.73  5535.4  547.91  5585.1  548.12  5613.9  548.96  5627.5  549.96
#Mann=3,-1,0
  4138.6    0.05       0  4981.6   0.035       0  4985.6    0.05       0
Bank Sta=4981.6,4985.6
Exp/Cntr=0.3,0.1

Type RM Length L Ch R = 1,11836,529,529,529
BEGIN DESCRIPTION:
Brushy Creek Trib 3_1 28.0
END DESCRIPTION:
XS GIS Cut Line= 5
      2609457.53      6986907.90      2609735.22      6985611.11
      2609659.59      6985415.92      2609396.48      6985223.69
      2609238.75      6985043.29
#Sta/Elev= 30
  3780.7  545.22  3828.7  544.23  3849.6  544.92  3879.8  543.52  4002.5  542.36
  4081.5  540.58  4104.8  541.12  4237.7  538.33  4340.0  538.37  4368.0  537.23
  4373.1  537.89  4417.4  534.84  4516.3  535.32  4560.6  536.70  4654.4  536.96
  4891.4  534.66  4963.8  532.60  4984.3  533.07  4995.4  532.14  5039.8  533.32
  5102.4  530.80  5102.6  530.30  5106.4  530.80  5415.7  535.62  5436.5  534.86
  5501.4  537.09  5722.5  539.96  5757.6  541.78  5786.1  541.13  5881.7  543.92
#Mann=3,-1,0
  3780.7    0.05       0  5102.4    0.03       0  5106.4    0.05       0
Bank Sta=5102.4,5106.4
Exp/Cntr=0.3,0.1

Type RM Length L Ch R = 1,11307,202,202,202
BEGIN DESCRIPTION:
Brushy Creek Trib 3_1 27.0
END DESCRIPTION:
XS GIS Cut Line= 3
      2611176.29      6986694.37      2609976.00      6985461.00
      2609426.01      6985161.01
#Sta/Elev= 30
  3604.5  547.43  3826.3  543.24  3911.2  542.65  3981.9  540.11  4003.0  540.80
  4066.8  538.65  4180.0  536.11  4201.1  536.67  4222.4  535.45  4335.4  533.74
  4385.0  532.00  4618.3  529.20  4660.7  527.04  4738.6  526.58  4802.2  528.45
  4879.9  528.84  4998.2  526.10  4998.5  525.60  5002.2  526.10  5120.4  529.52
  5205.3  529.38  5283.2  527.91  5496.4  530.20  5562.3  532.50  5649.7  533.47
  5724.2  535.53  5747.0  535.08  5872.3  537.89  5900.3  537.61  5952.0  539.28
#Mann=3,-1,0
  3604.5    0.05       0  4998.2    0.03       0  5002.2    0.05       0
Bank Sta=4998.2,5002.2
Exp/Cntr=0.3,0.1

Type RM Length L Ch R = 1,11105,404,404,404
BEGIN DESCRIPTION:
Brushy Creek Trib 3_1 26.0
END DESCRIPTION:
XS GIS Cut Line= 3
      2610975.99      6986260.99      2610176.00      6985361.00
      2609575.97      6985060.99
#Sta/Elev= 30
  4050.7  538.35  4184.9  535.10  4199.1  535.47  4220.9  534.28  4277.7  534.10
  4383.9  531.17  4404.8  531.56  4425.7  530.49  4652.8  526.54  4780.3  525.48
  4843.8  526.57  4907.4  526.57  4935.8  526.26  4964.3  524.45  4998.2  523.68
  4998.5  523.18  5002.0  523.18  5002.2  523.68  5056.2  526.04  5098.9  526.93
  5277.2  525.65  5308.0  527.04  5358.3  527.09  5442.1  529.01  5531.6  529.72
  5665.7  532.91  5716.0  533.15  5783.1  535.03  5872.6  536.02  5925.7  537.79
#Mann=3,-1,0
  4050.7    0.05       0  4998.2   0.035       0  5002.2    0.05       0
Bank Sta=4998.2,5002.2
Exp/Cntr=0.3,0.1

Type RM Length L Ch R = 1,10701,281,281,281
BEGIN DESCRIPTION:
Brushy Creek Trib 3_1 24.0
END DESCRIPTION:
XS GIS Cut Line= 3
      2611226.03      6985861.03      2610626.00      6985261.00
      2610075.99      6984710.99
#Sta/Elev= 30
  4151.2  533.74  4207.8  531.71  4236.1  532.05  4292.7  530.62  4321.0  530.72
  4377.5  529.22  4405.8  529.21  4434.1  528.15  4448.2  528.62  4490.7  528.31
  4547.2  526.89  4575.5  526.90  4787.6  523.48  4801.8  522.02  4830.1  523.10
  4929.1  522.81  4994.2  520.69  4994.5  520.19  4998.0  520.19  4998.2  520.69
  5042.2  521.01  5070.5  522.19  5098.8  522.33  5127.1  523.31  5353.3  526.16
  5466.5  528.60  5523.0  528.82  5622.0  531.91  5706.9  532.78  5777.6  534.80
#Mann=3,-1,0
  4151.2    0.05       0  4994.2    0.03       0  4998.2    0.05       0
Bank Sta=4994.2,4998.2
Exp/Cntr=0.3,0.1

Type RM Length L Ch R = 1,10420,258,258,258
BEGIN DESCRIPTION:
Brushy Creek Trib 3_1 23.0
END DESCRIPTION:
XS GIS Cut Line= 3
      2611476.00      6985711.00      2610876.00      6985161.00
      2610275.98      6984560.98
#Sta/Elev= 30
  4181.7  534.29  4288.1  531.28  4415.1  529.26  4493.4  527.56  4500.2  527.76
  4514.4  527.09  4535.3  526.98  4542.7  526.44  4571.1  525.83  4663.0  524.44
  4677.2  524.65  4889.3  520.74  5007.8  520.10  5008.0  519.60  5011.5  519.60
  5011.8  520.10  5052.2  521.18  5151.2  521.42  5292.6  523.42  5349.2  523.52
  5419.9  524.61  5547.2  527.15  5589.6  527.62  5617.9  528.28  5632.0  529.15
  5688.6  529.72  5745.2  531.32  5787.6  531.79  5815.9  532.87  5844.2  533.04
#Mann=3,-1,0
  4181.7    0.05       0  5007.8    0.03       0  5011.8    0.05       0
Bank Sta=5007.8,5011.8
Exp/Cntr=0.3,0.1

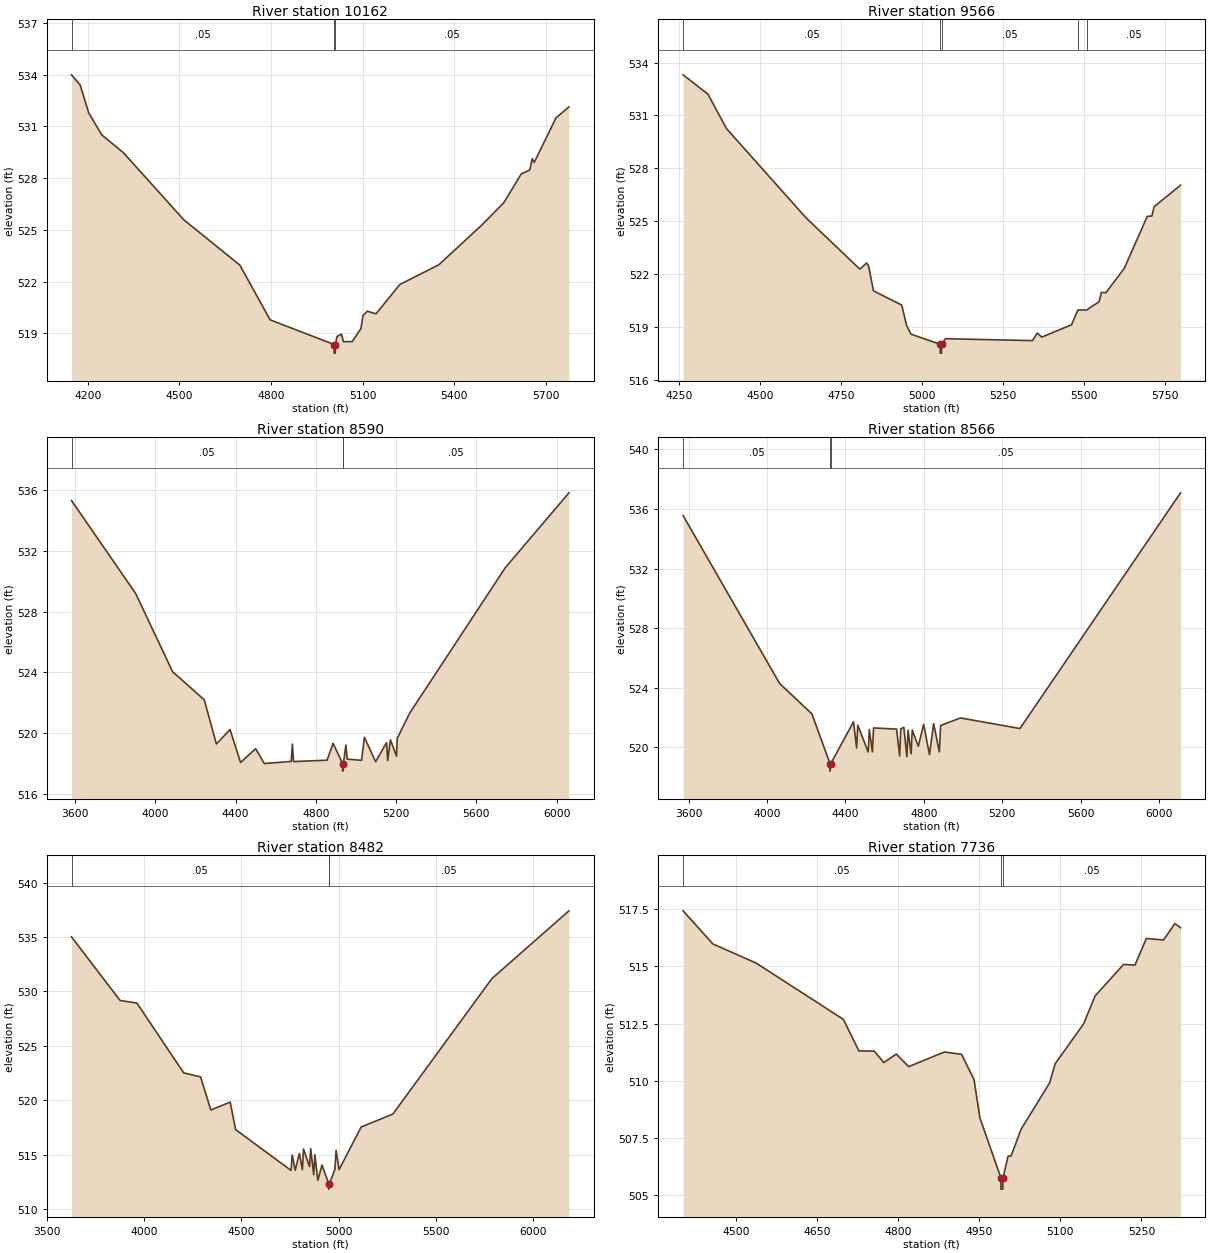
Type RM Length L Ch R = 1,10162,596,596,596
BEGIN DESCRIPTION:
Brushy Creek Trib 3_1 22.0
END DESCRIPTION:
XS GIS Cut Line= 3
      2611626.00      6985561.00      2611026.00      6984961.00
      2610425.97      6984460.97
#Sta/Elev= 30
  4146.6  533.99  4174.9  533.40  4203.2  531.77  4245.6  530.51  4316.3  529.48
  4514.3  525.59  4698.1  522.96  4797.1  519.79  5006.8  518.36  5007.0  517.86
  5010.5  517.86  5010.8  518.36  5016.6  518.83  5030.9  518.96  5037.4  518.52
  5066.1  518.53  5094.7  519.28  5101.2  520.03  5115.5  520.29  5144.2  520.14
  5222.3  521.84  5349.8  522.98  5491.7  525.30  5563.3  526.59  5620.0  528.25
  5647.9  528.47  5655.7  529.13  5662.3  528.91  5733.9  531.50  5776.2  532.13
#Mann=3,-1,0
  4146.6    0.05       0  5006.8    0.03       0  5010.8    0.05       0
Bank Sta=5006.8,5010.8
Exp/Cntr=0.3,0.1

Type RM Length L Ch R = 1,9566,976,976,976
BEGIN DESCRIPTION:
Brushy Creek Trib 3_1 20.0
END DESCRIPTION:
XS GIS Cut Line= 3
      2611876.02      6985386.03      2611476.00      6984786.00
      2610875.99      6984235.99
#Sta/Elev= 30
  4261.9  533.31  4338.6  532.21  4395.6  530.26  4640.5  525.20  4807.3  522.27
  4828.3  522.62  4834.3  522.45  4849.3  521.04  4936.5  520.23  4951.5  519.08
  4965.0  518.58  5055.3  518.00  5055.6  517.50  5059.1  517.50  5059.3  518.00
  5071.5  518.32  5340.4  518.21  5354.6  518.64  5368.7  518.41  5460.6  519.11
  5480.1  519.95  5507.1  519.95  5545.7  520.42  5552.8  520.95  5566.7  520.93
  5623.4  522.32  5694.3  525.27  5708.5  525.29  5715.6  525.82  5797.0  527.04
#Mann=5,-1,0
  4261.9    0.05       0  5055.3    0.03       0  5059.3    0.05       0
  5480.1    0.12       0  5507.1    0.05       0
Bank Sta=5055.3,5059.3
Exp/Cntr=0.3,0.1

Type RM Length L Ch R = 1,8590,24,24,24
BEGIN DESCRIPTION:
Mapping XS 56b238b8
END DESCRIPTION:
XS GIS Cut Line= 6
      2612331.67      6985354.58      2612003.97      6984590.67
      2611854.23      6984325.92      2611593.82      6983954.82
      2611565.60      6983933.12      2610721.42      6983805.08
#Sta/Elev= 30
  3581.9  535.32  3901.4  529.20  4085.9  524.04  4243.6  522.19  4304.0  519.28
  4372.3  520.23  4424.6  518.06  4499.7  518.97  4543.0  517.99  4677.0  518.13
  4683.0  519.27  4688.7  518.12  4855.7  518.21  4885.9  519.32  4933.3  517.99
  4933.6  517.49  4937.3  517.99  4949.6  519.20  4956.2  518.28  5027.7  518.20
  5042.0  519.72  5097.9  518.11  5152.5  519.37  5158.1  518.19  5171.6  519.55
  5202.1  518.48  5205.5  519.65  5268.1  521.32  5743.5  530.88  6061.7  535.83
#Mann=3,-1,0
  3581.9    0.05       0  4933.3    0.03       0  4937.3    0.05       0
Bank Sta=4933.3,4937.3
Exp/Cntr=0.3,0.1

Type RM Length L Ch R = 1,8566,84,84,84
BEGIN DESCRIPTION:
Mapping XS 359dfb30
END DESCRIPTION:
XS GIS Cut Line= 6
      2612354.24      6985346.07      2612037.39      6984597.36
      2611811.69      6984215.10      2611583.05      6983913.80
      2611514.39      6983892.06      2610698.25      6983755.68
#Sta/Elev= 30
  3572.2  535.56  4064.5  524.29  4229.2  522.25  4321.1  518.91  4321.3  518.41
  4325.1  518.91  4441.3  521.72  4457.1  519.96  4462.9  521.49  4516.1  519.70
  4521.8  521.20  4537.6  519.70  4543.4  521.31  4660.9  521.23  4676.5  519.43
  4682.3  521.25  4697.9  521.35  4713.5  519.38  4719.3  521.16  4734.9  519.57
  4740.7  521.17  4771.7  520.08  4798.8  521.55  4828.6  519.52  4850.0  521.60
  4879.1  519.70  4885.4  521.47  4986.4  521.98  5290.1  521.27  6109.1  537.09
#Mann=3,-1,0
  3572.2    0.05       0  4321.1    0.03       0  4325.1    0.05       0
Bank Sta=4321.1,4325.1
Exp/Cntr=0.3,0.1

Type RM Length L Ch R = 1,8482,746,746,746
BEGIN DESCRIPTION:
Mapping XS 0e5a96c1
END DESCRIPTION:
XS GIS Cut Line= 6
      2612386.22      6985330.29      2612055.22      6984563.53
      2611810.10      6984159.18      2611632.01      6983920.34
      2611550.31      6983859.58      2610712.27      6983721.31
#Sta/Elev= 30
  3626.7  535.00  3876.4  529.16  3963.0  528.92  4203.2  522.51  4290.3  522.13
  4342.8  519.09  4442.3  519.82  4470.3  517.29  4755.3  513.54  4761.2  514.95
  4776.7  513.55  4798.0  515.10  4813.5  513.60  4819.3  515.50  4850.3  513.89
  4856.2  515.53  4871.7  513.14  4877.5  514.99  4893.0  512.63  4914.3  514.03
  4948.8  512.32  4949.0  511.82  4952.8  512.32  4980.7  513.64  4986.8  515.38
  5002.1  513.61  5115.8  517.53  5278.7  518.72  5788.2  531.18  6183.9  537.40
#Mann=3,-1,0
  3626.7    0.05       0  4948.8    0.03       0  4952.8    0.05       0
Bank Sta=4948.8,4952.8
Exp/Cntr=0.3,0.1

Type RM Length L Ch R = 1,7736,453,453,453
BEGIN DESCRIPTION:
Brushy Creek Trib 3_1 16.0
END DESCRIPTION:
XS GIS Cut Line= 3
      2612526.00      6984311.01      2612276.00      6983761.00
      2611975.99      6983661.00
#Sta/Elev= 30
  4401.9  517.44  4456.8  515.99  4537.0  515.15  4698.5  512.68  4727.1  511.30
  4755.6  511.29  4773.2  510.79  4796.3  511.16  4819.3  510.61  4885.2  511.25
  4917.1  511.15  4940.2  510.04  4951.1  508.36  4989.8  505.74  4990.0  505.24
  4993.5  505.24  4993.8  505.74  5003.3  506.69  5008.7  506.69  5027.1  507.86
  5079.9  509.89  5090.4  510.74  5143.1  512.49  5164.2  513.71  5216.9  515.09
  5238.0  515.06  5259.0  516.23  5290.7  516.16  5311.8  516.88  5322.3  516.70
#Mann=3,-1,0
  4401.9    0.05       0  4989.8    0.04       0  4993.8    0.05       0
Bank Sta=4989.8,4993.8
Exp/Cntr=0.3,0.1

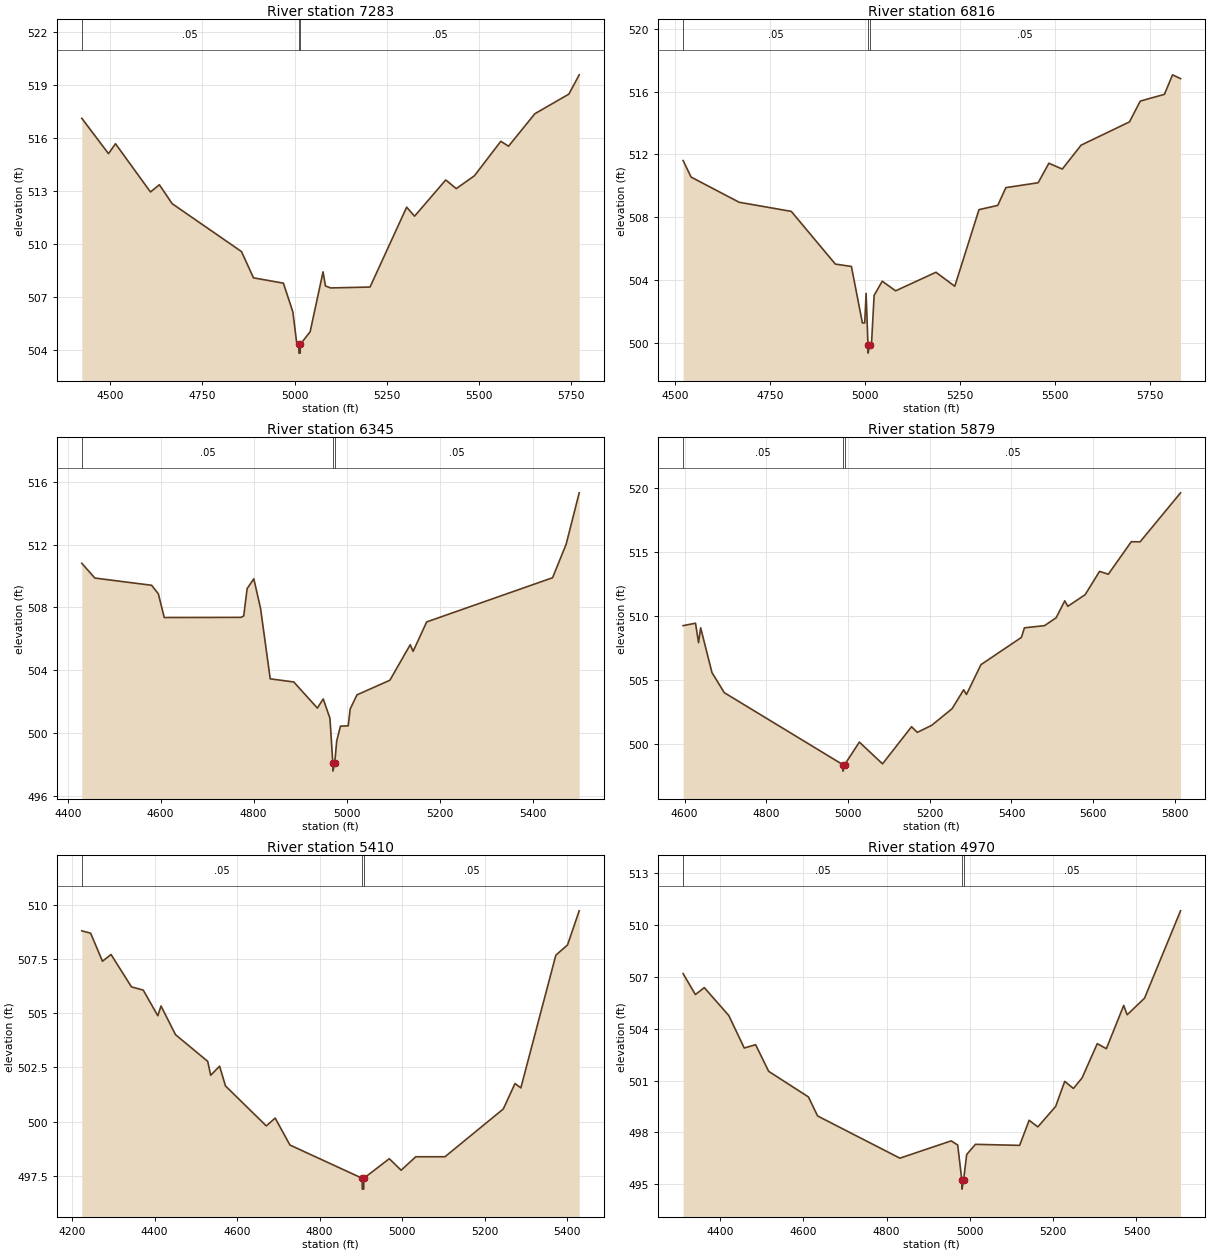
Type RM Length L Ch R = 1,7283,467,467,467
BEGIN DESCRIPTION:
Brushy Creek Trib 3_1 15.0
END DESCRIPTION:
XS GIS Cut Line= 3
      2612826.01      6984161.05      2612676.00      6983611.00
      2612075.97      6983110.98
#Sta/Elev= 30
  4422.1  517.10  4494.7  515.10  4513.7  515.66  4608.7  512.93  4632.9  513.34
  4667.5  512.27  4855.8  509.56  4888.6  508.07  4969.8  507.77  4995.5  506.14
  5005.9  504.39  5011.7  504.31  5012.0  503.81  5015.5  503.81  5015.7  504.31
  5042.4  505.02  5077.5  508.41  5084.0  507.61  5098.3  507.50  5205.1  507.55
  5304.6  512.07  5326.1  511.56  5410.7  513.61  5439.4  513.12  5488.8  513.85
  5560.4  515.80  5581.3  515.52  5652.9  517.36  5745.3  518.47  5773.3  519.56
#Mann=3,-1,0
  4422.1    0.05       0  5011.7    0.04       0  5015.7    0.05       0
Bank Sta=5011.7,5015.7
Exp/Cntr=0.3,0.1

Type RM Length L Ch R = 1,6816,471,471,471
BEGIN DESCRIPTION:
Brushy Creek Trib 3_1 14.0
END DESCRIPTION:
XS GIS Cut Line= 3
      2613075.99      6983760.96      2612926.00      6983311.00
      2612330.95      6982726.06
#Sta/Elev= 30
  4521.5  511.61  4542.5  510.56  4669.0  508.96  4806.1  508.38  4922.0  505.03
  4964.2  504.88  4993.2  501.29  4999.3  501.29  5002.9  503.17  5007.9  499.87
  5008.1  499.37  5011.9  499.87  5017.0  499.91  5024.0  503.04  5045.3  503.94
  5080.6  503.33  5186.7  504.51  5236.2  503.62  5299.9  508.49  5349.3  508.76
  5370.6  509.89  5455.5  510.20  5483.8  511.44  5519.1  511.07  5568.6  512.59
  5695.9  514.07  5724.2  515.39  5787.8  515.82  5809.1  517.06  5830.2  516.82
#Mann=3,-1,0
  4521.5    0.05       0  5007.9    0.04       0  5011.9    0.05       0
Bank Sta=5007.9,5011.9
Exp/Cntr=0.3,0.1

Type RM Length L Ch R = 1,6345,466,466,466
BEGIN DESCRIPTION:
Brushy Creek Trib 3_1 13.0
END DESCRIPTION:
XS GIS Cut Line= 3
      2613376.02      6983461.03      2613026.00      6983011.00
      2612726.01      6982611.02
#Sta/Elev= 30
  4430.3  510.81  4458.4  509.87  4580.5  509.41  4595.0  508.87  4607.7  507.36
  4772.4  507.37  4778.7  507.46  4786.0  509.20  4800.4  509.82  4814.9  507.94
  4835.7  503.46  4886.4  503.26  4937.1  501.60  4949.7  502.18  4964.2  500.95
  4970.4  498.09  4970.6  497.59  4974.4  498.09  4978.7  499.51  4986.8  500.45
  5003.5  500.47  5007.7  501.54  5022.3  502.44  5093.1  503.37  5136.9  505.63
  5143.1  505.21  5172.3  507.08  5443.1  509.89  5472.3  512.02  5500.4  515.29
#Mann=3,-1,0
  4430.3    0.05       0  4970.4    0.04       0  4974.4    0.05       0
Bank Sta=4970.4,4974.4
Exp/Cntr=0.3,0.1

Type RM Length L Ch R = 1,5879,469,469,469
BEGIN DESCRIPTION:
Brushy Creek Trib 3_1 12.0
END DESCRIPTION:
XS GIS Cut Line= 3
      2613426.01      6983161.05      2613376.00      6982761.00
      2612826.00      6982161.00
#Sta/Elev= 30
  4596.6  509.26  4626.9  509.45  4634.4  507.93  4639.5  509.09  4667.2  505.59
  4697.4  504.02  4987.7  498.39  4987.9  497.89  4991.7  498.39  5027.8  500.16
  5084.5  498.46  5155.5  501.36  5169.6  500.92  5204.8  501.47  5254.7  502.77
  5283.1  504.25  5289.9  503.88  5325.3  506.21  5424.3  508.34  5431.7  509.09
  5481.0  509.26  5509.4  509.88  5530.4  511.20  5537.8  510.77  5580.3  511.68
  5615.5  513.50  5637.0  513.28  5693.2  515.82  5714.7  515.81  5813.7  519.64
#Mann=3,-1,0
  4596.6    0.05       0  4987.7    0.04       0  4991.7    0.05       0
Bank Sta=4987.7,4991.7
Exp/Cntr=0.3,0.1

Type RM Length L Ch R = 1,5410,440,440,440
BEGIN DESCRIPTION:
Brushy Creek Trib 3_1 11.0
END DESCRIPTION:
XS GIS Cut Line= 3
      2614225.99      6983060.99      2613726.00      6982461.00
      2613425.98      6982160.98
#Sta/Elev= 30
  4223.8  508.79  4245.3  508.68  4273.9  507.39  4294.7  507.70  4344.2  506.21
  4372.8  506.06  4408.0  504.88  4415.8  505.33  4450.9  504.01  4529.0  502.78
  4536.2  502.14  4557.7  502.56  4572.0  501.65  4670.9  499.81  4692.4  500.17
  4728.2  498.93  4903.2  497.40  4903.5  496.90  4907.0  496.90  4907.2  497.40
  4969.0  498.30  4997.6  497.77  5033.1  498.39  5103.8  498.39  5245.2  500.59
  5273.5  501.76  5287.7  501.56  5372.5  507.67  5400.8  508.14  5429.1  509.71
#Mann=3,-1,0
  4223.8    0.05       0  4903.2    0.03       0  4907.2    0.05       0
Bank Sta=4903.2,4907.2
Exp/Cntr=0.3,0.1

Type RM Length L Ch R = 1,4970,247,247,247
BEGIN DESCRIPTION:
Brushy Creek Trib 3_1 10.0
END DESCRIPTION:
XS GIS Cut Line= 3
      2614426.02      6982861.04      2614076.00      6982261.00
      2613775.98      6981860.97
#Sta/Elev= 30
  4311.1  507.18  4340.5  505.97  4362.0  506.37  4420.7  504.76  4457.9  502.88
  4485.2  503.07  4516.6  501.53  4612.1  500.05  4634.1  498.95  4831.7  496.51
  4954.9  497.51  4970.6  497.27  4980.6  495.22  4980.9  494.72  4984.6  495.22
  4992.1  496.72  5013.1  497.31  5119.3  497.25  5142.2  498.70  5163.1  498.32
  5205.8  499.50  5227.6  500.95  5248.5  500.54  5269.3  501.15  5305.8  503.13
  5327.6  502.84  5369.3  505.34  5377.6  504.80  5419.3  505.76  5505.8  510.81
#Mann=3,-1,0
  4311.1    0.05       0  4980.6    0.03       0  4984.6    0.05       0
Bank Sta=4980.6,4984.6
Exp/Cntr=0.3,0.1

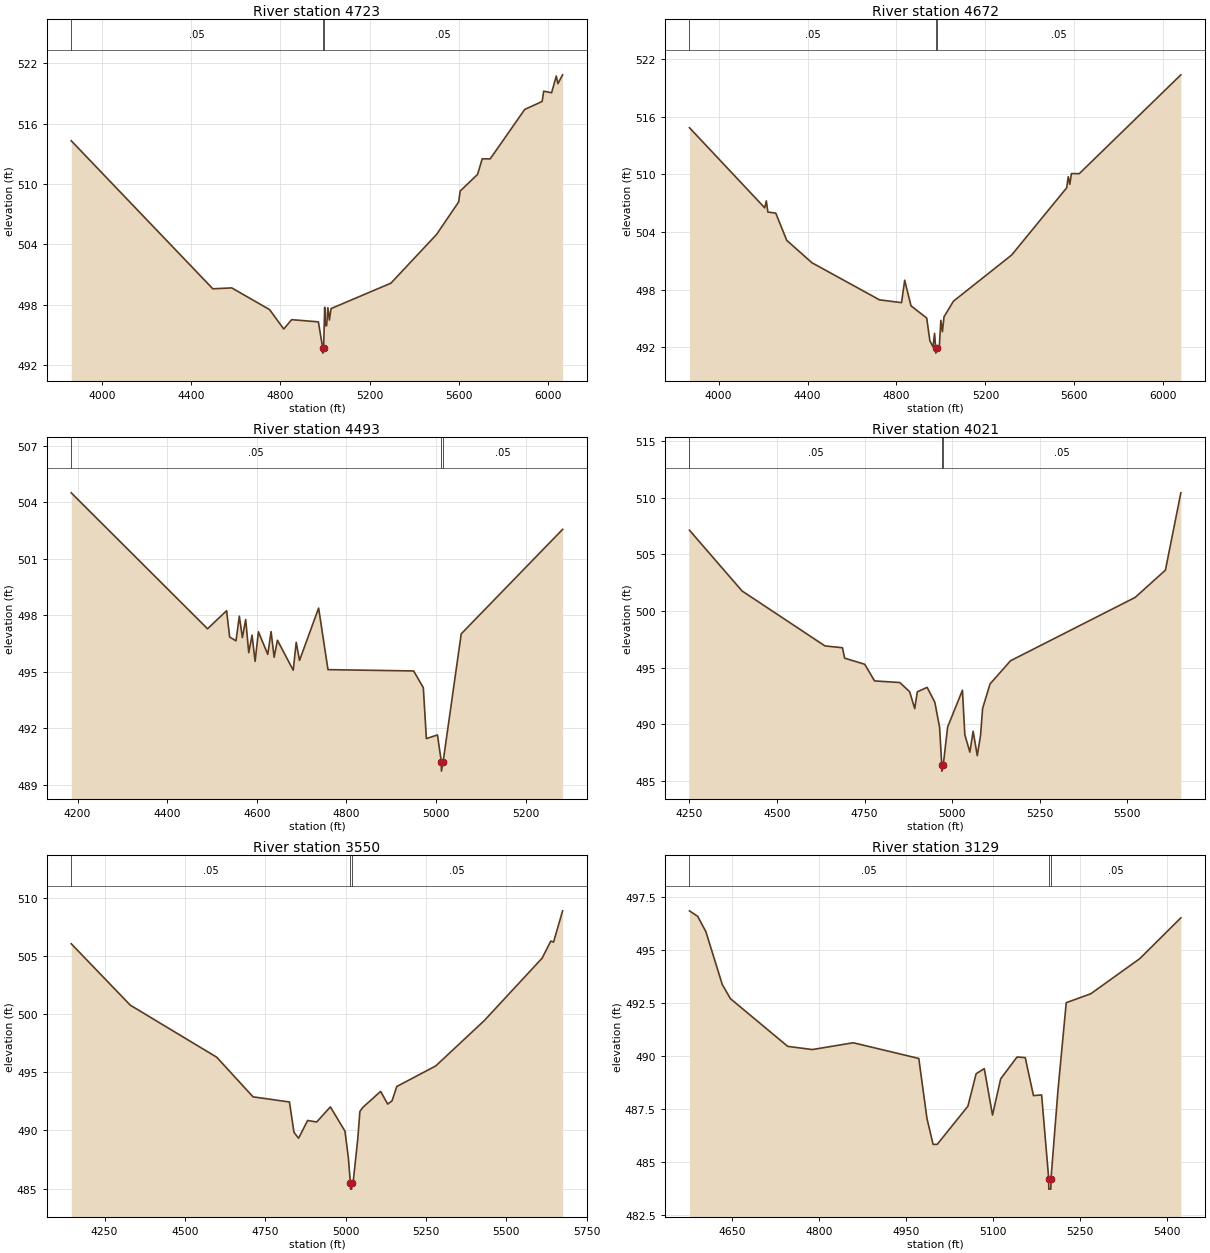
Type RM Length L Ch R = 1,4723,51,51,51
BEGIN DESCRIPTION:
Mapping XS f8528834
END DESCRIPTION:
XS GIS Cut Line= 3
      2615073.68      6982972.27      2614278.54      6982152.82
      2613540.25      6981386.80
#Sta/Elev= 30
  3860.7  514.31  4496.4  499.58  4581.3  499.67  4751.1  497.51  4814.6  495.58
  4850.1  496.51  4970.2  496.29  4989.4  493.68  4989.6  493.18  4993.4  493.68
  4998.5  497.74  5000.7  495.91  5007.2  495.91  5012.7  497.70  5019.6  496.47
  5026.8  497.61  5295.7  500.14  5500.7  504.99  5599.7  508.22  5606.7  509.31
  5684.6  510.96  5705.7  512.52  5741.1  512.50  5896.6  517.43  5974.6  518.22
  5981.5  519.24  6017.0  519.09  6038.1  520.75  6045.3  519.99  6066.4  520.87
#Mann=3,-1,0
  3860.7    0.05       0  4989.4    0.03       0  4993.4    0.05       0
Bank Sta=4989.4,4993.4
Exp/Cntr=0.3,0.1

Type RM Length L Ch R = 1,4672,179,179,179
BEGIN DESCRIPTION:
Mapping XS b60fe75e
END DESCRIPTION:
XS GIS Cut Line= 3
      2615105.81      6982929.75      2614328.02      6982131.12
      2613560.85      6981350.07
#Sta/Elev= 30
  3869.1  514.85  4207.5  506.52  4214.7  507.24  4221.6  506.08  4257.1  505.97
  4306.5  503.14  4419.7  500.81  4723.7  496.95  4822.8  496.66  4836.9  498.99
  4865.2  496.33  4935.9  495.06  4950.1  492.70  4964.2  492.06  4971.2  493.47
  4976.4  491.91  4976.6  491.41  4980.4  491.91  4992.5  492.00  4999.5  494.82
  5006.6  493.64  5013.6  495.18  5056.1  496.81  5317.8  501.61  5565.3  508.60
  5572.4  509.75  5579.4  508.96  5586.5  510.08  5621.8  510.07  6078.7  520.35
#Mann=3,-1,0
  3869.1    0.05       0  4976.4    0.03       0  4980.4    0.05       0
Bank Sta=4976.4,4980.4
Exp/Cntr=0.3,0.1

Type RM Length L Ch R = 1,4493,472,472,472
BEGIN DESCRIPTION:
Brushy Creek Trib 3_1 9.0
END DESCRIPTION:
XS GIS Cut Line= 3
      2614926.00      6982561.00      2614376.00      6981961.00
      2614175.99      6981760.99
#Sta/Elev= 30
  4185.8  504.50  4490.1  497.28  4532.6  498.24  4539.4  496.84  4553.6  496.64
  4561.0  497.95  4567.8  496.81  4575.2  497.77  4582.0  496.01  4589.4  496.94
  4596.2  495.55  4603.6  497.12  4624.5  495.92  4631.9  497.13  4638.7  495.77
  4646.1  496.67  4681.3  495.08  4688.0  496.56  4695.4  495.60  4738.0  498.38
  4758.9  495.11  4950.1  495.04  4971.7  494.15  4978.5  491.45  5003.3  491.64
  5011.9  490.22  5012.1  489.72  5015.9  490.22  5056.3  497.01  5282.6  502.56
#Mann=3,-1,0
  4185.8    0.05       0  5011.9    0.03       0  5015.9    0.05       0
Bank Sta=5011.9,5015.9
Exp/Cntr=0.3,0.1

Type RM Length L Ch R = 1,4021,471,471,471
BEGIN DESCRIPTION:
Brushy Creek Trib 3_1 8.0
END DESCRIPTION:
XS GIS Cut Line= 3
      2615226.01      6982461.01      2614776.00      6981861.00
      2614226.03      6981511.02
#Sta/Elev= 30
  4250.6  507.12  4400.6  501.76  4637.1  496.91  4687.1  496.75  4693.3  495.83
  4750.6  495.29  4778.7  493.82  4850.6  493.68  4878.7  492.87  4893.3  491.38
  4900.6  492.86  4928.7  493.25  4950.6  491.94  4964.2  489.73  4970.5  486.36
  4970.7  485.86  4974.5  486.36  4987.1  489.75  5029.4  493.00  5036.2  489.07
  5050.6  487.54  5059.9  489.38  5071.7  487.23  5081.0  489.00  5087.0  491.40
  5108.1  493.55  5166.6  495.60  5522.2  501.19  5608.5  503.60  5652.5  510.42
#Mann=3,-1,0
  4250.6    0.05       0  4970.5    0.03       0  4974.5    0.05       0
Bank Sta=4970.5,4974.5
Exp/Cntr=0.3,0.1

Type RM Length L Ch R = 1,3550,421,421,421
BEGIN DESCRIPTION:
Brushy Creek Trib 3_1 7.0
END DESCRIPTION:
XS GIS Cut Line= 3
      2615625.98      6982110.98      2615026.00      6981511.00
      2614475.97      6981110.98
#Sta/Elev= 30
  4146.4  506.05  4330.2  500.77  4598.9  496.30  4712.1  492.89  4825.2  492.45
  4839.3  489.85  4853.5  489.33  4881.8  490.86  4910.0  490.73  4952.5  492.03
  4998.0  489.94  5008.4  487.68  5014.9  485.46  5015.2  484.96  5018.7  484.96
  5018.9  485.46  5023.1  485.49  5037.8  489.28  5044.4  491.63  5052.5  491.96
  5108.9  493.36  5130.9  492.27  5144.4  492.55  5159.1  493.78  5280.4  495.55
  5431.1  499.44  5611.2  504.81  5638.3  506.28  5646.8  506.19  5675.0  508.88
#Mann=3,-1,0
  4146.4    0.05       0  5014.9    0.03       0  5018.9    0.05       0
Bank Sta=5014.9,5018.9
Exp/Cntr=0.3,0.1

Type RM Length L Ch R = 1,3129,467,467,467
BEGIN DESCRIPTION:
Brushy Creek Trib 3_1 6.0
END DESCRIPTION:
XS GIS Cut Line= 3
      2615576.01      6981561.01      2615276.00      6981261.00
      2614976.03      6980961.03
#Sta/Elev= 30
  4576.2  496.83  4590.4  496.57  4604.5  495.85  4632.8  493.36  4646.9  492.69
  4745.9  490.44  4788.3  490.29  4859.1  490.61  4972.2  489.87  4986.3  487.04
  4996.9  485.82  5004.0  485.82  5057.0  487.62  5071.2  489.15  5085.3  489.39
  5099.5  487.20  5113.6  488.91  5141.9  489.94  5156.0  489.91  5170.2  488.12
  5184.3  488.15  5196.5  484.21  5196.7  483.71  5200.2  483.71  5200.5  484.21
  5212.6  488.39  5226.8  492.50  5269.2  492.92  5354.0  494.58  5424.7  496.50
#Mann=3,-1,0
  4576.2    0.05       0  5196.5    0.03       0  5200.5    0.05       0
Bank Sta=5196.5,5200.5
Exp/Cntr=0.3,0.1

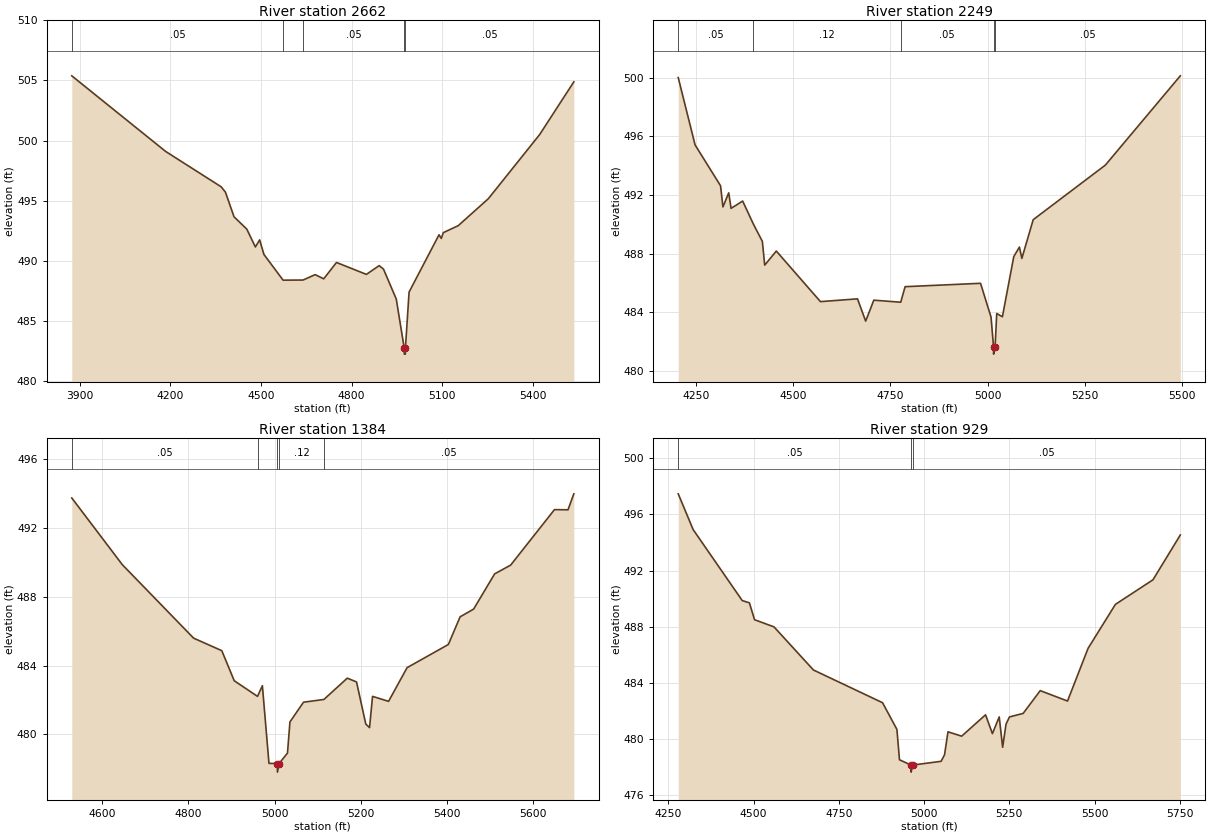
Type RM Length L Ch R = 1,2662,413,413,413
BEGIN DESCRIPTION:
Brushy Creek Trib 3_1 5.0
END DESCRIPTION:
XS GIS Cut Line= 3
      2616226.00      6981661.00      2615426.00      6980861.00
      2615025.98      6980510.98
#Sta/Elev= 30
  3873.3  505.38  4184.4  499.09  4368.3  496.15  4382.4  495.70  4410.7  493.66
  4453.1  492.63  4481.4  491.15  4495.6  491.74  4509.7  490.53  4573.2  488.39
  4639.3  488.40  4679.4  488.85  4707.7  488.50  4750.1  489.86  4849.1  488.87
  4891.5  489.60  4905.7  489.31  4948.1  486.82  4974.4  482.74  4974.6  482.24
  4978.1  482.24  4978.4  482.74  4990.5  487.40  5089.6  492.16  5097.2  491.86
  5103.9  492.34  5153.2  492.92  5252.9  495.16  5422.8  500.49  5536.2  504.88
#Mann=5,-1,0
  3873.3    0.05       0  4573.2    0.12       0  4639.3    0.05       0
  4974.4    0.03       0  4978.4    0.05       0
Bank Sta=4974.4,4978.4
Exp/Cntr=0.3,0.1

Type RM Length L Ch R = 1,2249,865,865,865
BEGIN DESCRIPTION:
Brushy Creek Trib 3_1 4.0
END DESCRIPTION:
XS GIS Cut Line= 3
      2616376.02      6981061.01      2615726.00      6980611.00
      2615325.99      6980310.99
#Sta/Elev= 30
  4204.9  500.00  4248.2  495.41  4313.7  492.62  4319.8  491.18  4334.7  492.14
  4340.7  491.08  4370.5  491.58  4397.7  490.03  4421.1  488.83  4427.2  487.21
  4457.0  488.17  4570.5  484.72  4665.7  484.91  4686.7  483.39  4707.6  484.82
  4776.8  484.68  4788.1  485.74  4982.0  485.97  5009.0  483.66  5015.4  481.64
  5015.6  481.14  5019.4  481.64  5023.6  483.91  5038.2  483.69  5067.4  487.79
  5081.9  488.44  5088.2  487.67  5117.4  490.31  5302.8  494.03  5495.5  500.12
#Mann=5,-1,0
  4204.9    0.05       0  4397.7    0.12       0  4776.8    0.05       0
  5015.4    0.03       0  5019.4    0.05       0
Bank Sta=5015.4,5019.4
Exp/Cntr=0.3,0.1

Type RM Length L Ch R = 1,1384,455,455,455
BEGIN DESCRIPTION:
Brushy Creek Trib 3_1 3.0
END DESCRIPTION:
XS GIS Cut Line= 3
      2616726.00      6980711.00      2616326.00      6980461.00
      2615726.02      6980111.01
#Sta/Elev= 30
  4528.9  493.76  4646.2  489.88  4811.9  485.60  4877.4  484.87  4906.3  483.12
  4960.4  482.21  4971.7  482.83  4987.0  478.31  5006.4  478.30  5006.7  477.80
  5010.6  478.30  5030.0  478.91  5035.7  480.72  5067.2  481.87  5114.6  482.03
  5168.9  483.27  5190.4  483.05  5211.9  480.60  5220.6  480.39  5227.6  482.21
  5264.8  481.92  5307.8  483.88  5403.7  485.23  5431.0  486.84  5462.4  487.29
  5511.2  489.34  5548.4  489.85  5650.2  493.08  5681.6  493.07  5695.2  494.00
#Mann=5,-1,0
  4528.9    0.05       0  4960.4    0.12       0  5006.4    0.07       0
  5010.6    0.12       0  5114.6    0.05       0
Bank Sta=5006.4,5010.6
Exp/Cntr=0.3,0.1

Type RM Length L Ch R = 1,929,0,0,0
BEGIN DESCRIPTION:
Brushy Creek Trib 3_1 2.0
END DESCRIPTION:
XS GIS Cut Line= 3
      2616876.00      6980661.00      2616476.00      6980061.00
      2615725.97      6980011.00
#Sta/Elev= 30
  4278.9  497.47  4322.5  494.93  4466.7  489.87  4487.7  489.71  4502.7  488.51
  4559.8  488.00  4675.5  484.93  4878.3  482.60  4920.4  480.70  4927.9  478.54
  4961.8  478.16  4962.2  477.66  4966.1  478.16  5050.1  478.43  5060.1  478.90
  5070.2  480.53  5110.3  480.22  5180.4  481.74  5200.5  480.40  5220.5  481.59
  5230.5  479.43  5240.5  481.08  5250.6  481.59  5290.7  481.84  5340.8  483.46
  5420.9  482.72  5481.1  486.47  5561.3  489.60  5671.5  491.35  5751.7  494.54
#Mann=3,-1,0
  4278.9    0.05       0  4961.8    0.03       0  4966.1    0.05       0
Bank Sta=4961.8,4966.1
Exp/Cntr=0.3,0.1

Chan Stop Cuts=-1