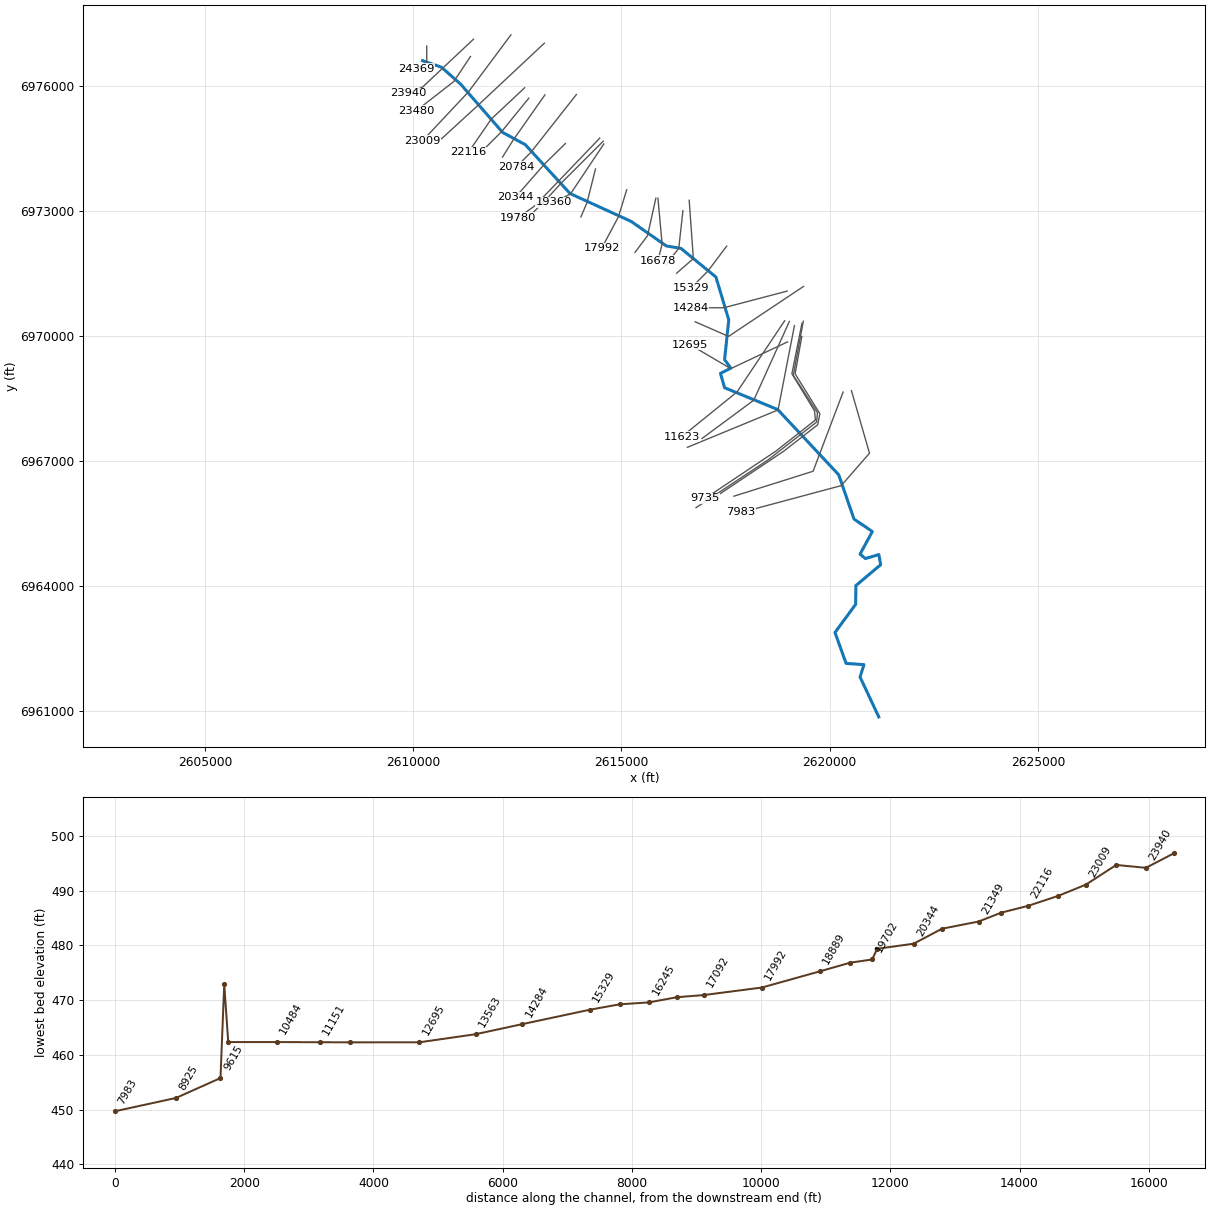
--- Brushy Creek Trib 4.prj (project) ---

Proj Title=Brushy Creek Trib 4 Base Level Engineering
Current Plan=p01
Default Exp/Contr=0.3,0.1
English Units
Geom File=g01
Flow File=f01
Plan File=p01
BEGIN DESCRIPTION:
Brushy Creek Trib 4
END DESCRIPTION:

--- Brushy Creek Trib 4.p01 (plan) ---

Plan Title=Multiple Run
Short Identifier=Multiple
Geom File=g01
Flow File=f01
Subcritical Flow
K Sum by GR= 0
Std Step Tol= 0.01
Critical Tol= 0.01
Num of Std Step Trials= 20
Max Error Tol= 0.3
Flow Tol Ratio= 0.001
Split Flow NTrial= 30
Split Flow Tol= 0.02
Split Flow Ratio= 0.02
Log Output Level= 0
Friction Slope Method= 1
Unsteady Friction Slope Method= 2
Unsteady Bridges Friction Slope Method= 1
Parabolic Critical Depth
Global Vel Dist=  1 , 1 , 1
Global Log Level= 0
CheckData=True
Encroach Param= -1, 0, 0, 0
BEGIN DESCRIPTION:
Multiple Run
END DESCRIPTION:

--- Brushy Creek Trib 4.f01 (steady flow) ---

Flow Title=Multiple
Number of Profiles=7
Profile Names=10-year,25-year,50-year,1pct_min,100-year,1pct_plu,500-year
River Rch & RM= Brushy Creek Tri,Reach-1,24369
     578     777     938     563    1123    2241    1607
River Rch & RM= Brushy Creek Tri,Reach-1,23940
     769    1050    1282     776    1548    3089    2258
River Rch & RM= Brushy Creek Tri,Reach-1,22116
    1051    1446    1773    1076    2146    4282    3147
River Rch & RM= Brushy Creek Tri,Reach-1,11623
    1800    2541    3168    1952    3894    7770    5888
River Rch & RM= Brushy Creek Tri,Reach-1,9735
    2146    3055    3832    2374    4736    9449    7240
Boundary for River Rch & Prof#=Brushy Creek Tri,Reach-1,1
Up Type=0
Dn Type=3
Dn Slope=0.005
Boundary for River Rch & Prof#=Brushy Creek Tri,Reach-1,2
Up Type=0
Dn Type=3
Dn Slope=0.005
Boundary for River Rch & Prof#=Brushy Creek Tri,Reach-1,3
Up Type=0
Dn Type=3
Dn Slope=0.005
Boundary for River Rch & Prof#=Brushy Creek Tri,Reach-1,4
Up Type=0
Dn Type=3
Dn Slope=0.005
Boundary for River Rch & Prof#=Brushy Creek Tri,Reach-1,5
Up Type=0
Dn Type=3
Dn Slope=0.005
Boundary for River Rch & Prof#=Brushy Creek Tri,Reach-1,6
Up Type=0
Dn Type=3
Dn Slope=0.005
Boundary for River Rch & Prof#=Brushy Creek Tri,Reach-1,7
Up Type=0
Dn Type=3
Dn Slope=0.005

--- Brushy Creek Trib 4.g01 (geometry) ---

Geom Title=Existing Conditions

River Reach=Brushy Creek Tri,Reach-1
Reach XY= 30
      2610226.00      6976611.00      2610678.45      6976455.53
      2611143.13      6976044.70      2612145.84      6974890.61
      2612692.79      6974594.56      2613766.32      6973421.76
      2615228.66      6972755.54      2616077.55      6972164.75
      2616428.43      6972105.48      2617268.15      6971417.19
      2617575.93      6970390.97      2617475.70      6969435.88
      2617626.49      6969231.12      2617377.95      6969105.11
      2617476.00      6968761.00      2618749.47      6968237.99
      2620215.37      6966671.00      2620581.73      6965608.45
      2621022.48      6965309.47      2620727.61      6964767.03
      2620855.83      6964660.53      2621178.58      6964756.03
      2621222.47      6964512.46      2620626.00      6964011.00
      2620622.45      6963562.47      2620125.68      6962885.89
      2620392.45      6962143.85      2620820.55      6962113.48
      2620727.58      6961817.05      2621176.00      6960861.00

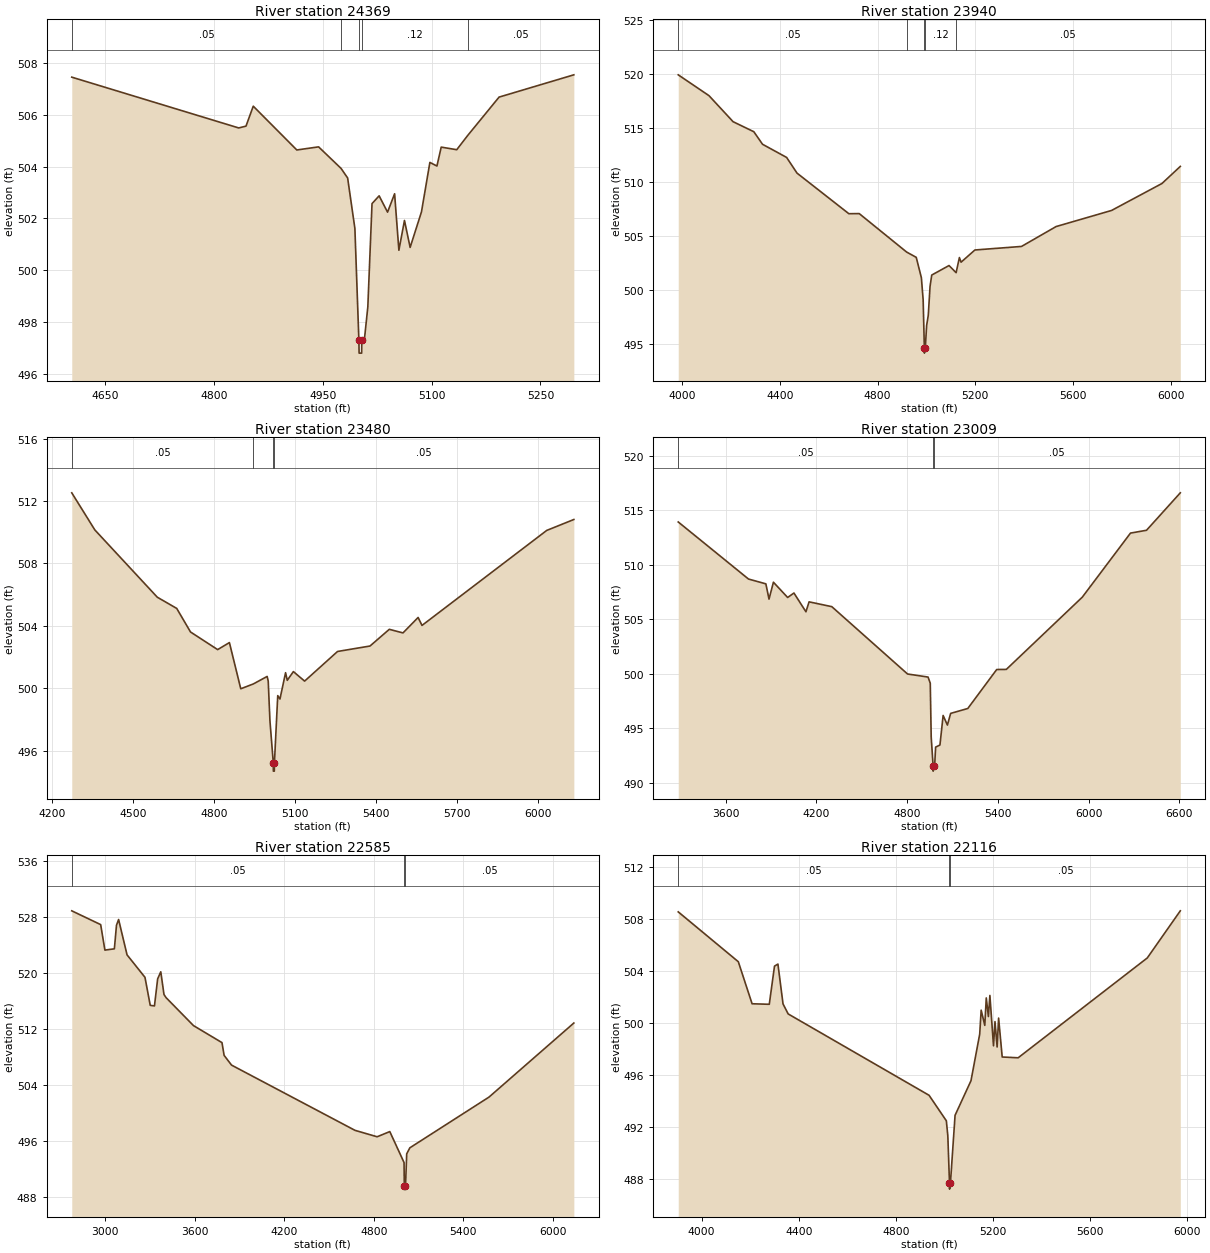
Type RM Length L Ch R = 1,24369,429,429,429
BEGIN DESCRIPTION:
Brushy Creek Trib 4 34.0
END DESCRIPTION:
XS GIS Cut Line= 3
      2610326.00      6976961.04      2610326.00      6976561.00
      2610075.99      6976410.99
#Sta/Elev= 30
  4604.4  507.45  4834.4  505.49  4844.4  505.56  4854.4  506.33  4914.4  504.64
  4944.4  504.76  4975.3  503.93  4984.4  503.56  4994.4  501.61  4999.9  497.30
  5000.2  496.80  5003.7  496.80  5003.9  497.30  5007.4  497.30  5012.2  498.58
  5018.0  502.57  5027.8  502.87  5039.4  502.24  5049.1  502.95  5055.0  500.77
  5062.7  501.92  5070.5  500.88  5086.1  502.25  5097.7  504.16  5107.4  504.02
  5113.3  504.75  5134.7  504.65  5149.8  505.20  5193.0  506.68  5296.0  507.54
#Mann=5,-1,0
  4604.4    0.05       0  4975.3    0.12       0  4999.9    0.07       0
  5003.9    0.12       0  5149.8    0.05       0
Bank Sta=4999.9,5003.9
Exp/Cntr=0.3,0.1

Type RM Length L Ch R = 1,23940,460,460,460
BEGIN DESCRIPTION:
Brushy Creek Trib 4 33.0
END DESCRIPTION:
XS GIS Cut Line= 3
      2611448.21      6977126.61      2610227.05      6975978.89
      2609877.09      6975828.91
#Sta/Elev= 30
  3983.3  519.94  4109.3  518.01  4208.0  515.60  4293.0  514.67  4328.6  513.51
  4427.3  512.29  4469.8  510.84  4682.2  507.08  4724.7  507.09  4918.8  503.53
  4958.2  503.04  4979.2  501.16  4986.5  499.12  4991.4  494.67  4991.6  494.17
  4995.4  494.67  5000.7  496.72  5007.5  497.67  5014.8  500.35  5021.7  501.40
  5092.5  502.28  5121.6  501.62  5135.0  503.02  5141.8  502.59  5198.5  503.72
  5389.5  504.05  5531.1  505.89  5758.2  507.38  5964.9  509.88  6039.9  511.46
#Mann=5,-1,0
  3983.3    0.05       0  4918.8    0.12       0  4991.4    0.07       0
  4995.4    0.12       0  5121.6    0.05       0
Bank Sta=4991.4,4995.4
Exp/Cntr=0.3,0.1

Type RM Length L Ch R = 1,23480,471,471,471
BEGIN DESCRIPTION:
Brushy Creek Trib 4 32.0
END DESCRIPTION:
XS GIS Cut Line= 3
      2611376.00      6976711.00      2610976.00      6976111.00
      2610075.99      6975410.99
#Sta/Elev= 30
  4273.4  512.53  4359.0  510.15  4590.4  505.84  4662.5  505.12  4713.6  503.61
  4814.2  502.48  4857.8  502.93  4899.9  499.97  4946.7  500.28  4997.7  500.76
  5001.7  500.46  5008.1  497.91  5020.6  495.19  5020.8  494.69  5024.3  494.69
  5024.6  495.19  5037.0  499.53  5045.2  499.31  5066.0  501.00  5072.3  500.51
  5095.0  501.07  5136.6  500.46  5258.7  502.36  5379.1  502.71  5450.6  503.78
  5501.3  503.55  5557.4  504.54  5571.8  504.03  6034.2  510.12  6134.7  510.82
#Mann=4,-1,0
  4273.4    0.05       0  4946.7    0.12       0  5020.6    0.07       0
  5024.6    0.05       0
Bank Sta=5020.6,5024.6
Exp/Cntr=0.3,0.1

Type RM Length L Ch R = 1,23009,424,424,424
BEGIN DESCRIPTION:
Brushy Creek Trib 4 31.0
END DESCRIPTION:
XS GIS Cut Line= 3
      2612346.65      6977230.78      2611326.00      6975861.00
      2610224.29      6974687.42
#Sta/Elev= 30
  3287.5  513.92  3751.9  508.69  3866.6  508.25  3887.4  506.85  3916.6  508.40
  4010.5  507.00  4052.1  507.41  4131.4  505.69  4152.2  506.60  4302.4  506.16
  4802.8  499.99  4938.4  499.71  4953.0  499.14  4959.2  494.21  4971.8  491.59
  4972.1  491.09  4975.8  491.59  4982.2  491.65  4988.4  493.29  5017.0  493.48
  5038.0  496.19  5066.3  495.31  5087.8  496.38  5201.1  496.83  5392.1  500.40
  5455.6  500.41  5957.7  507.03  6276.2  512.90  6382.2  513.16  6605.4  516.59
#Mann=3,-1,0
  3287.5    0.05       0  4971.8    0.03       0  4975.8    0.05       0
Bank Sta=4971.8,4975.8
Exp/Cntr=0.3,0.1

Type RM Length L Ch R = 1,22585,469,469,469
BEGIN DESCRIPTION:
Brushy Creek Trib 4 30.0
END DESCRIPTION:
XS GIS Cut Line= 3
      2613149.61      6977031.14      2611526.00      6975511.00
      2610684.37      6974739.51
#Sta/Elev= 30
  2775.6  528.82  2969.4  526.85  2997.7  523.21  3061.2  523.39  3075.4  526.76
  3089.6  527.58  3146.2  522.53  3266.4  519.32  3301.6  515.32  3329.9  515.23
  3351.4  519.10  3372.4  520.11  3393.9  516.86  3408.1  516.41  3591.7  512.42
  3782.7  509.99  3796.9  508.17  3846.7  506.78  4674.2  497.46  4822.7  496.54
  4907.7  497.28  5003.2  492.86  5004.9  489.56  5005.1  489.06  5008.9  489.56
  5013.6  489.83  5021.0  494.10  5042.0  494.96  5572.9  502.21  6141.5  512.79
#Mann=3,-1,0
  2775.6    0.05       0  5004.9    0.03       0  5008.9    0.05       0
Bank Sta=5004.9,5008.9
Exp/Cntr=0.3,0.1

Type RM Length L Ch R = 1,22116,414,414,414
BEGIN DESCRIPTION:
Brushy Creek Trib 4 29.0
END DESCRIPTION:
XS GIS Cut Line= 3
      2612675.99      6975960.99      2611876.00      6975211.00
      2611326.00      6974411.00
#Sta/Elev= 30
  3903.6  508.52  4151.0  504.69  4207.7  501.46  4278.5  501.42  4300.0  504.35
  4314.1  504.51  4335.1  501.45  4356.2  500.68  4936.4  494.43  5007.6  492.47
  5013.7  491.32  5020.5  487.72  5020.8  487.22  5024.6  487.72  5043.5  492.89
  5109.1  495.55  5145.0  499.13  5151.0  500.97  5165.9  499.80  5172.0  501.91
  5180.8  500.48  5186.9  502.10  5201.8  498.23  5207.9  500.09  5216.7  498.14
  5222.8  500.36  5237.6  497.37  5303.3  497.31  5835.0  504.98  5971.0  508.60
#Mann=3,-1,0
  3903.6    0.05       0  5020.5    0.03       0  5024.6    0.05       0
Bank Sta=5020.5,5024.6
Exp/Cntr=0.3,0.1

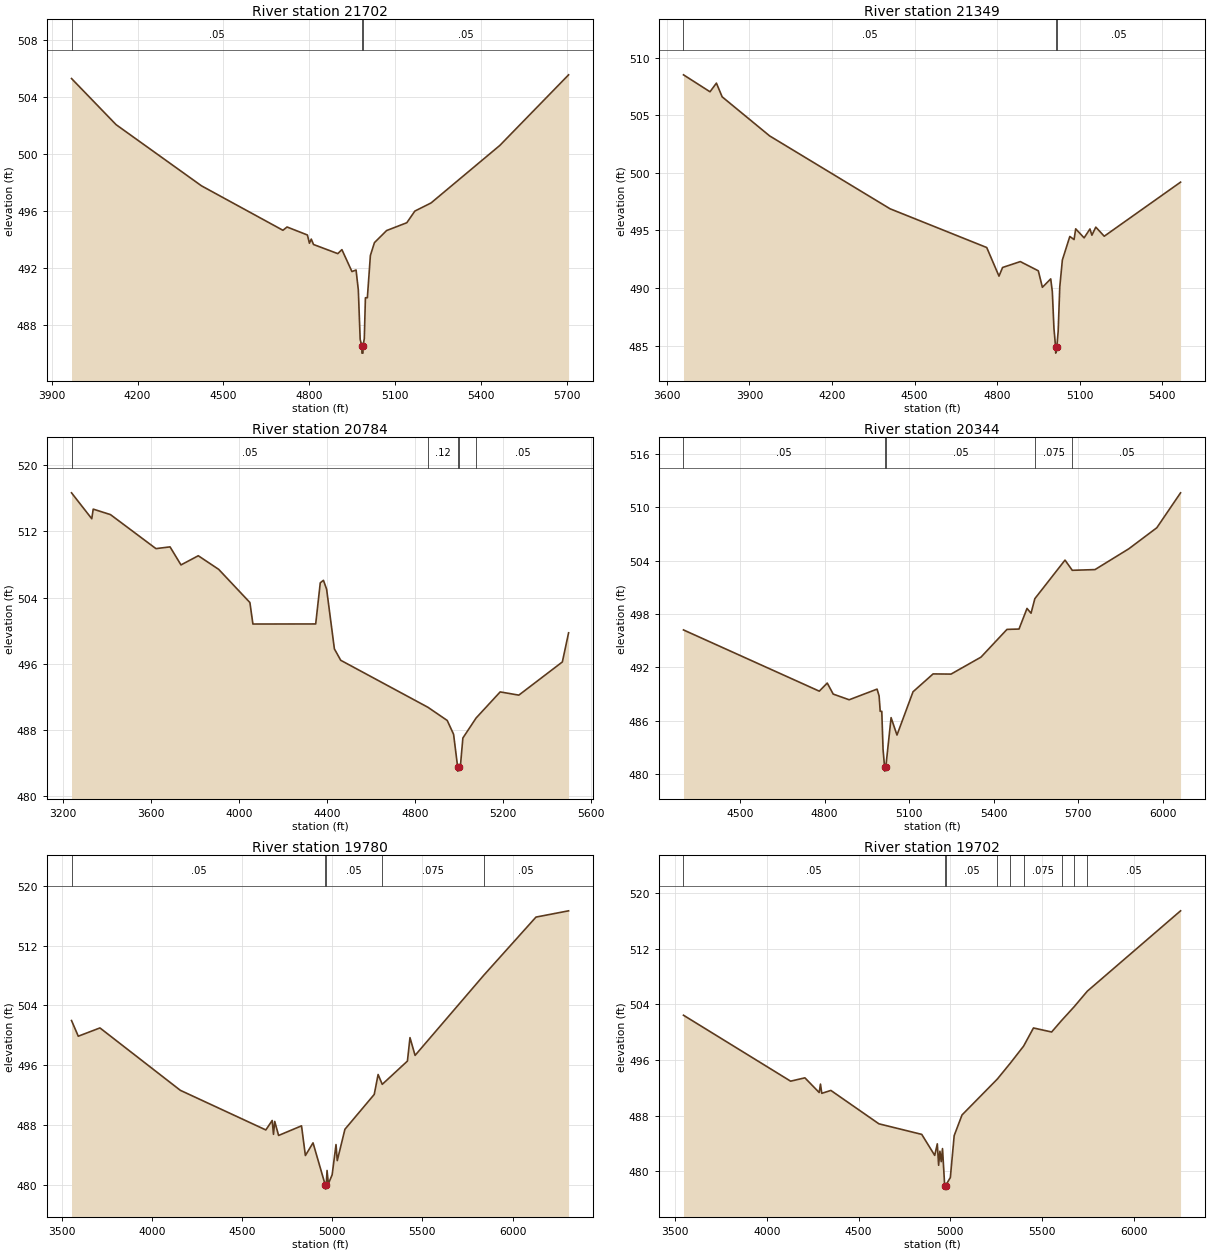
Type RM Length L Ch R = 1,21702,353,353,353
BEGIN DESCRIPTION:
Brushy Creek Trib 4 28.0
END DESCRIPTION:
XS GIS Cut Line= 3
      2612775.98      6975710.97      2612126.00      6974911.00
      2611626.03      6974411.03
#Sta/Elev= 30
  3969.0  505.28  4124.8  502.04  4423.6  497.74  4708.1  494.62  4722.5  494.85
  4793.6  494.29  4800.8  493.71  4807.2  494.00  4815.1  493.62  4899.9  492.98
  4914.3  493.26  4949.4  491.72  4963.8  491.83  4971.7  490.43  4978.2  486.95
  4984.0  486.49  4984.4  485.99  4987.9  485.99  4988.2  486.49  4992.6  487.01
  4996.5  489.88  5003.3  489.88  5013.9  492.85  5028.0  493.75  5070.5  494.60
  5141.2  495.15  5169.4  495.97  5226.0  496.54  5466.4  500.58  5706.8  505.54
#Mann=3,-1,0
  3969.0    0.05       0  4984.0    0.03       0  4988.2    0.05       0
Bank Sta=4984,4988.2
Exp/Cntr=0.3,0.1

Type RM Length L Ch R = 1,21349,565,565,565
BEGIN DESCRIPTION:
Brushy Creek Trib 4 27.0
END DESCRIPTION:
XS GIS Cut Line= 3
      2613162.61      6975789.79      2612395.95      6974697.86
      2612145.94      6974297.86
#Sta/Elev= 30
  3660.4  508.50  3756.7  507.03  3780.0  507.78  3800.9  506.59  3973.5  503.20
  4410.9  496.88  4762.1  493.52  4806.6  491.04  4819.7  491.79  4884.1  492.30
  4949.5  491.50  4964.3  490.07  4994.6  490.80  5000.4  489.70  5006.3  486.51
  5012.4  484.86  5012.7  484.36  5016.6  484.86  5021.6  486.24  5027.5  490.11
  5036.9  492.44  5064.0  494.48  5079.4  494.21  5085.3  495.14  5115.9  494.36
  5137.1  495.13  5144.2  494.59  5158.4  495.29  5189.0  494.50  5466.3  499.19
#Mann=3,-1,0
  3660.4    0.05       0  5012.4    0.03       0  5016.6    0.05       0
Bank Sta=5012.4,5016.6
Exp/Cntr=0.3,0.1

Type RM Length L Ch R = 1,20784,440,440,440
BEGIN DESCRIPTION:
Brushy Creek Trib 4 26.0
END DESCRIPTION:
XS GIS Cut Line= 3
      2613917.86      6975798.53      2612826.00      6974411.00
      2612475.99      6974060.99
#Sta/Elev= 30
  3238.8  516.67  3330.9  513.54  3337.5  514.70  3415.9  514.04  3622.8  509.93
  3686.9  510.14  3736.7  507.96  3815.3  509.07  3908.3  507.42  4050.0  503.42
  4063.8  500.82  4349.3  500.83  4370.1  505.80  4384.6  506.10  4399.0  505.02
  4434.3  497.82  4463.2  496.44  4859.9  490.76  4947.5  489.17  4976.4  487.50
  4994.9  483.55  4995.4  483.05  4999.4  483.55  5008.0  483.84  5018.6  487.05
  5078.9  489.47  5188.3  492.62  5273.1  492.23  5471.1  496.24  5499.4  499.76
#Mann=5,-1,0
  3238.8    0.05       0  4859.9    0.12       0  4994.9    0.07       0
  4999.4    0.12       0  5078.9    0.05       0
Bank Sta=4994.9,4999.4
Exp/Cntr=0.3,0.1

Type RM Length L Ch R = 1,20344,564,564,564
BEGIN DESCRIPTION:
Brushy Creek Trib 4 25.0
END DESCRIPTION:
XS GIS Cut Line= 3
      2613654.81      6974623.25      2613155.35      6974132.86
      2612455.33      6973332.85
#Sta/Elev= 30
  4299.4  496.20  4781.0  489.31  4809.3  490.22  4830.4  488.98  4887.0  488.34
  4986.0  489.54  4993.2  488.77  4997.1  487.04  5002.7  487.04  5007.2  482.77
  5012.5  480.81  5013.0  480.31  5017.1  480.81  5035.7  486.33  5056.6  484.37
  5113.5  489.24  5184.7  491.25  5248.3  491.23  5354.6  493.14  5446.7  496.26
  5489.4  496.30  5517.8  498.62  5532.1  498.08  5545.6  499.72  5652.6  504.06
  5678.3  502.91  5758.9  502.99  5878.8  505.33  5978.2  507.70  6062.4  511.63
#Mann=5,-1,0
  4299.4    0.05       0  5012.5    0.03       0  5017.1    0.05       0
  5545.6   0.075       0  5678.3    0.05       0
Bank Sta=5012.5,5017.1
Exp/Cntr=0.3,0.1

Type RM Length L Ch R = 1,19780,78,78,78
BEGIN DESCRIPTION:
Mapping XS de0ac03d
END DESCRIPTION:
XS GIS Cut Line= 4
      2614478.43      6974751.46      2613484.51      6973714.14
      2612915.94      6973123.86      2612509.44      6972834.12
#Sta/Elev= 30
  3554.9  501.97  3592.4  499.87  3712.5  500.98  4158.1  492.62  4632.1  487.31
  4667.3  488.58  4674.5  486.72  4681.4  488.45  4702.8  486.57  4829.9  487.86
  4851.3  483.88  4893.7  485.58  4962.1  479.88  4962.6  479.38  4966.8  479.88
  4971.4  481.88  4978.6  480.08  4999.7  481.31  5021.1  485.35  5028.0  483.20
  5070.5  487.40  5233.0  492.07  5254.4  494.74  5277.4  493.42  5417.0  496.54
  5431.1  499.68  5459.4  497.30  5839.6  508.02  6129.5  515.83  6310.3  516.67
#Mann=5,-1,0
  3554.9    0.05       0  4962.1    0.03       0  4966.8    0.05       0
  5277.4   0.075       0  5839.6    0.05       0
Bank Sta=4962.1,4966.8
Exp/Cntr=0.3,0.1

Type RM Length L Ch R = 1,19702,342,342,342
BEGIN DESCRIPTION:
Mapping XS 12d200ea
END DESCRIPTION:
XS GIS Cut Line= 4
      2614563.48      6974678.74      2613539.16      6973658.75
      2613270.06      6973363.61      2612666.76      6972747.29
#Sta/Elev= 30
  3546.7  502.43  4130.2  492.95  4208.0  493.43  4285.8  491.32  4292.8  492.53
  4299.9  491.20  4349.4  491.62  4611.1  486.82  4844.4  485.30  4915.1  482.28
  4929.2  483.94  4936.3  480.86  4943.4  482.88  4950.5  481.38  4957.5  483.26
  4969.3  477.93  4969.8  477.43  4974.0  477.93  5000.2  479.10  5021.1  485.12
  5063.7  488.09  5256.3  493.26  5327.4  495.56  5399.2  497.99  5452.9  500.60
  5551.9  500.02  5605.6  501.66  5675.5  503.68  5745.9  505.88  6254.1  517.44
#Mann=9,-1,0
  3546.7    0.05       0  4969.3    0.03       0  4974.0    0.05       0
  5256.3   0.075       0  5327.4    0.05       0  5399.2   0.075       0
  5605.6    0.05       0  5675.5   0.075       0  5745.9    0.05       0
Bank Sta=4969.3,4974
Exp/Cntr=0.3,0.1

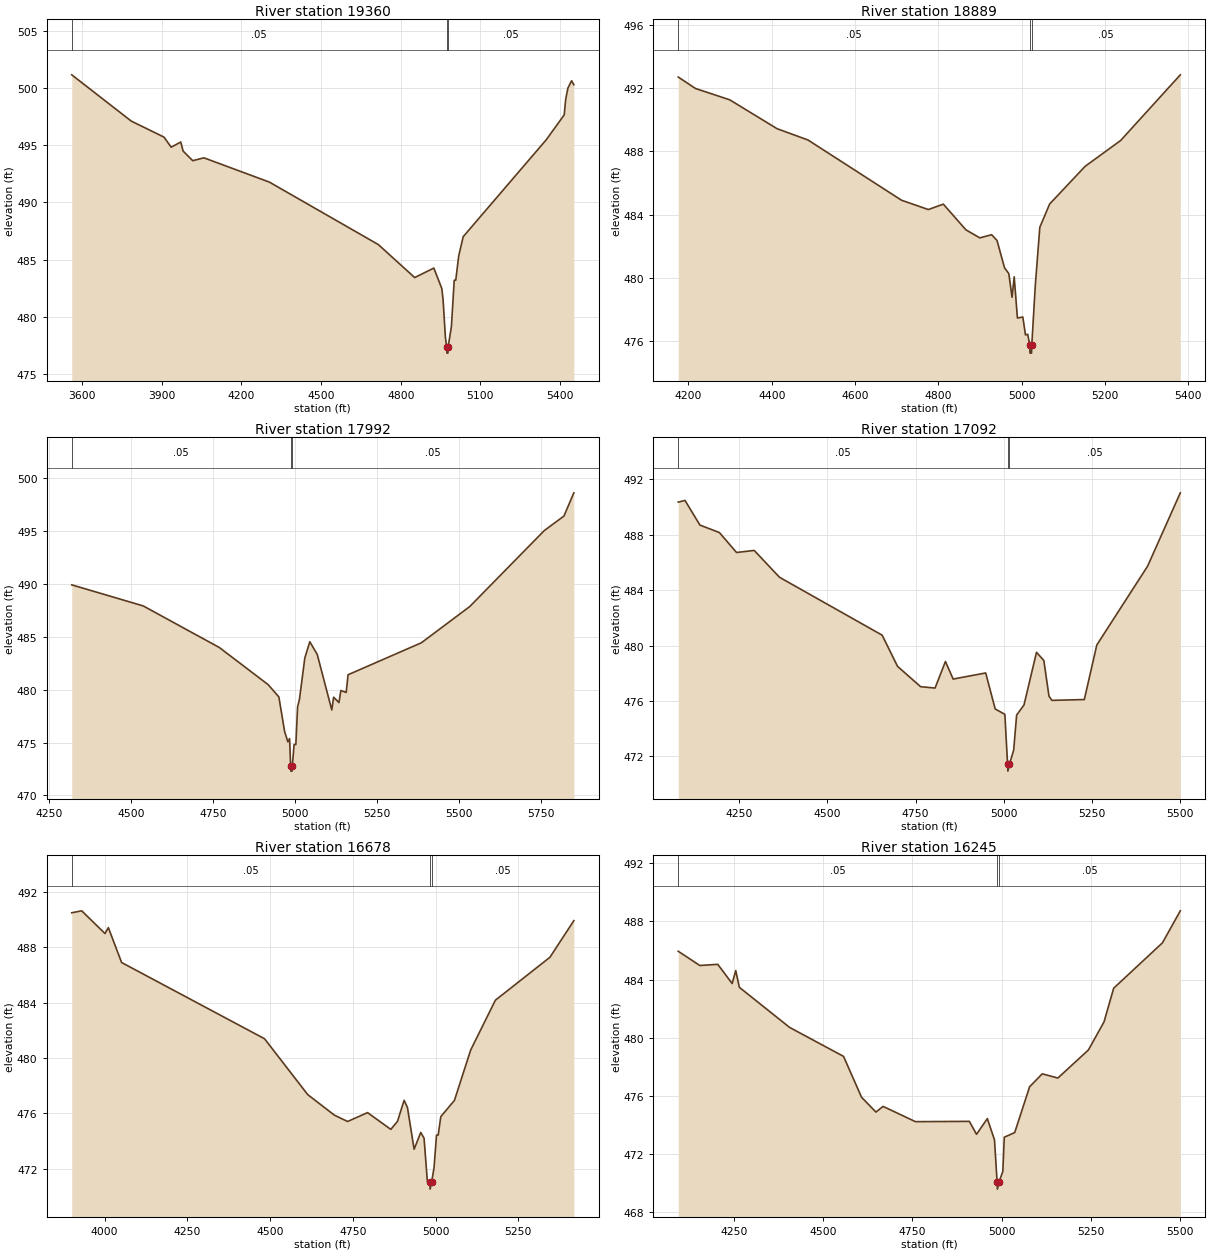
Type RM Length L Ch R = 1,19360,471,471,471
BEGIN DESCRIPTION:
Brushy Creek Trib 4 23.0
END DESCRIPTION:
XS GIS Cut Line= 3
      2614576.00      6974611.00      2613776.00      6973411.00
      2613376.03      6973211.02
#Sta/Elev= 30
  3562.2  501.15  3786.0  497.11  3909.2  495.71  3936.3  494.83  3972.3  495.28
  3981.3  494.49  4017.4  493.65  4059.5  493.90  4305.8  491.78  4716.0  486.32
  4852.7  483.44  4924.8  484.27  4954.8  482.48  4959.4  481.55  4968.4  478.18
  4973.5  477.34  4974.0  476.84  4977.7  476.84  4978.3  477.34  4990.9  479.17
  5001.4  483.21  5007.2  483.21  5018.4  485.34  5035.2  487.01  5348.2  495.49
  5415.3  497.65  5420.9  499.00  5429.3  500.00  5443.2  500.63  5451.6  500.28
#Mann=3,-1,0
  3562.2    0.05       0  4973.5    0.03       0  4978.3    0.05       0
Bank Sta=4973.5,4978.3
Exp/Cntr=0.3,0.1

Type RM Length L Ch R = 1,18889,897,897,897
BEGIN DESCRIPTION:
Brushy Creek Trib 4 22.0
END DESCRIPTION:
XS GIS Cut Line= 3
      2614375.99      6974010.98      2614176.00      6973211.00
      2614026.00      6972860.99
#Sta/Elev= 30
  4175.4  492.69  4216.6  491.97  4299.1  491.25  4412.5  489.43  4487.2  488.71
  4711.4  484.91  4775.8  484.32  4811.9  484.66  4866.0  483.04  4899.5  482.53
  4927.8  482.73  4940.7  482.37  4958.8  480.64  4969.1  480.27  4976.8  478.78
  4982.0  480.07  4989.7  477.47  5002.7  477.53  5009.1  476.40  5014.5  476.44
  5019.3  475.75  5019.9  475.25  5023.6  475.25  5024.2  475.75  5032.6  479.51
  5043.5  483.20  5067.1  484.67  5152.3  487.05  5237.5  488.68  5380.8  492.83
#Mann=3,-1,0
  4175.4    0.05       0  5019.3    0.03       0  5024.2    0.05       0
Bank Sta=5019.3,5024.2
Exp/Cntr=0.3,0.1

Type RM Length L Ch R = 1,17992,900,900,900
BEGIN DESCRIPTION:
Brushy Creek Trib 4 20.0
END DESCRIPTION:
XS GIS Cut Line= 3
      2615126.01      6973511.03      2614926.00      6972861.00
      2614526.00      6972111.00
#Sta/Elev= 30
  4319.9  489.89  4537.7  487.90  4769.8  483.97  4918.3  480.47  4951.0  479.31
  4968.6  476.04  4978.4  475.07  4983.7  475.37  4986.9  472.80  4987.6  472.30
  4991.4  472.30  4992.1  472.80  4997.4  474.81  5002.8  474.81  5008.1  478.37
  5013.8  479.08  5030.1  482.98  5045.3  484.52  5068.0  483.32  5112.3  478.08
  5117.9  479.28  5134.2  478.77  5139.9  479.91  5156.2  479.73  5161.9  481.40
  5385.3  484.42  5532.7  487.84  5759.7  495.01  5819.9  496.39  5850.0  498.58
#Mann=3,-1,0
  4319.9    0.05       0  4986.9    0.03       0  4992.1    0.05       0
Bank Sta=4986.9,4992.1
Exp/Cntr=0.3,0.1

Type RM Length L Ch R = 1,17092,414,414,414
BEGIN DESCRIPTION:
Brushy Creek Trib 4 18.0
END DESCRIPTION:
XS GIS Cut Line= 3
      2615826.01      6973311.03      2615626.00      6972411.00
      2615325.99      6972010.99
#Sta/Elev= 30
  4077.8  490.36  4097.0  490.48  4139.3  488.70  4194.4  488.16  4243.0  486.72
  4293.0  486.87  4364.7  484.93  4655.3  480.75  4698.9  478.50  4764.2  477.03
  4805.2  476.93  4834.6  478.85  4856.4  477.58  4948.6  478.02  4975.5  475.42
  5002.9  475.03  5010.6  471.43  5011.4  470.93  5016.0  471.43  5027.9  472.46
  5036.2  474.98  5057.1  475.71  5092.5  479.51  5113.3  478.92  5127.9  476.34
  5136.2  476.04  5227.9  476.10  5263.3  480.04  5407.1  485.73  5499.8  491.03
#Mann=3,-1,0
  4077.8    0.05       0  5010.6    0.03       0  5016.0    0.05       0
Bank Sta=5010.6,5016
Exp/Cntr=0.3,0.1

Type RM Length L Ch R = 1,16678,433,433,433
BEGIN DESCRIPTION:
Brushy Creek Trib 4 17.0
END DESCRIPTION:
XS GIS Cut Line= 3
      2615876.00      6973311.02      2615976.00      6972211.00
      2615875.99      6971810.97
#Sta/Elev= 30
  3900.7  490.48  3930.8  490.62  4001.1  488.98  4011.2  489.41  4051.3  486.89
  4483.1  481.39  4613.6  477.36  4694.0  475.88  4734.1  475.42  4794.4  476.06
  4864.7  474.85  4884.8  475.43  4904.8  476.95  4914.9  476.43  4935.0  473.42
  4955.1  474.63  4965.1  474.21  4975.1  471.08  4982.5  471.04  4983.3  470.54
  4987.9  471.04  4995.2  472.09  5002.7  474.44  5007.8  474.44  5015.6  475.77
  5056.8  476.94  5105.8  480.57  5180.5  484.17  5345.4  487.27  5417.6  489.91
#Mann=3,-1,0
  3900.7    0.05       0  4982.5    0.03       0  4987.9    0.05       0
Bank Sta=4982.5,4987.9
Exp/Cntr=0.3,0.1

Type RM Length L Ch R = 1,16245,447,447,447
BEGIN DESCRIPTION:
Brushy Creek Trib 4 16.0
END DESCRIPTION:
XS GIS Cut Line= 3
      2616476.00      6973011.01      2616376.00      6972111.00
      2616075.97      6971710.96
#Sta/Elev= 30
  4094.5  485.95  4154.9  484.97  4205.2  485.05  4245.4  483.73  4255.5  484.62
  4265.6  483.47  4406.4  480.71  4557.3  478.72  4607.7  475.91  4647.9  474.89
  4668.0  475.28  4758.6  474.23  4909.5  474.25  4929.6  473.36  4959.8  474.44
  4979.9  472.98  4987.2  470.09  4988.0  469.59  4992.7  470.09  5003.2  470.81
  5007.3  473.16  5036.5  473.48  5078.2  476.63  5113.6  477.52  5157.3  477.23
  5242.8  479.16  5286.5  481.09  5313.6  483.41  5450.1  486.53  5500.1  488.73
#Mann=3,-1,0
  4094.5    0.05       0  4987.2    0.03       0  4992.7    0.05       0
Bank Sta=4987.2,4992.7
Exp/Cntr=0.3,0.1

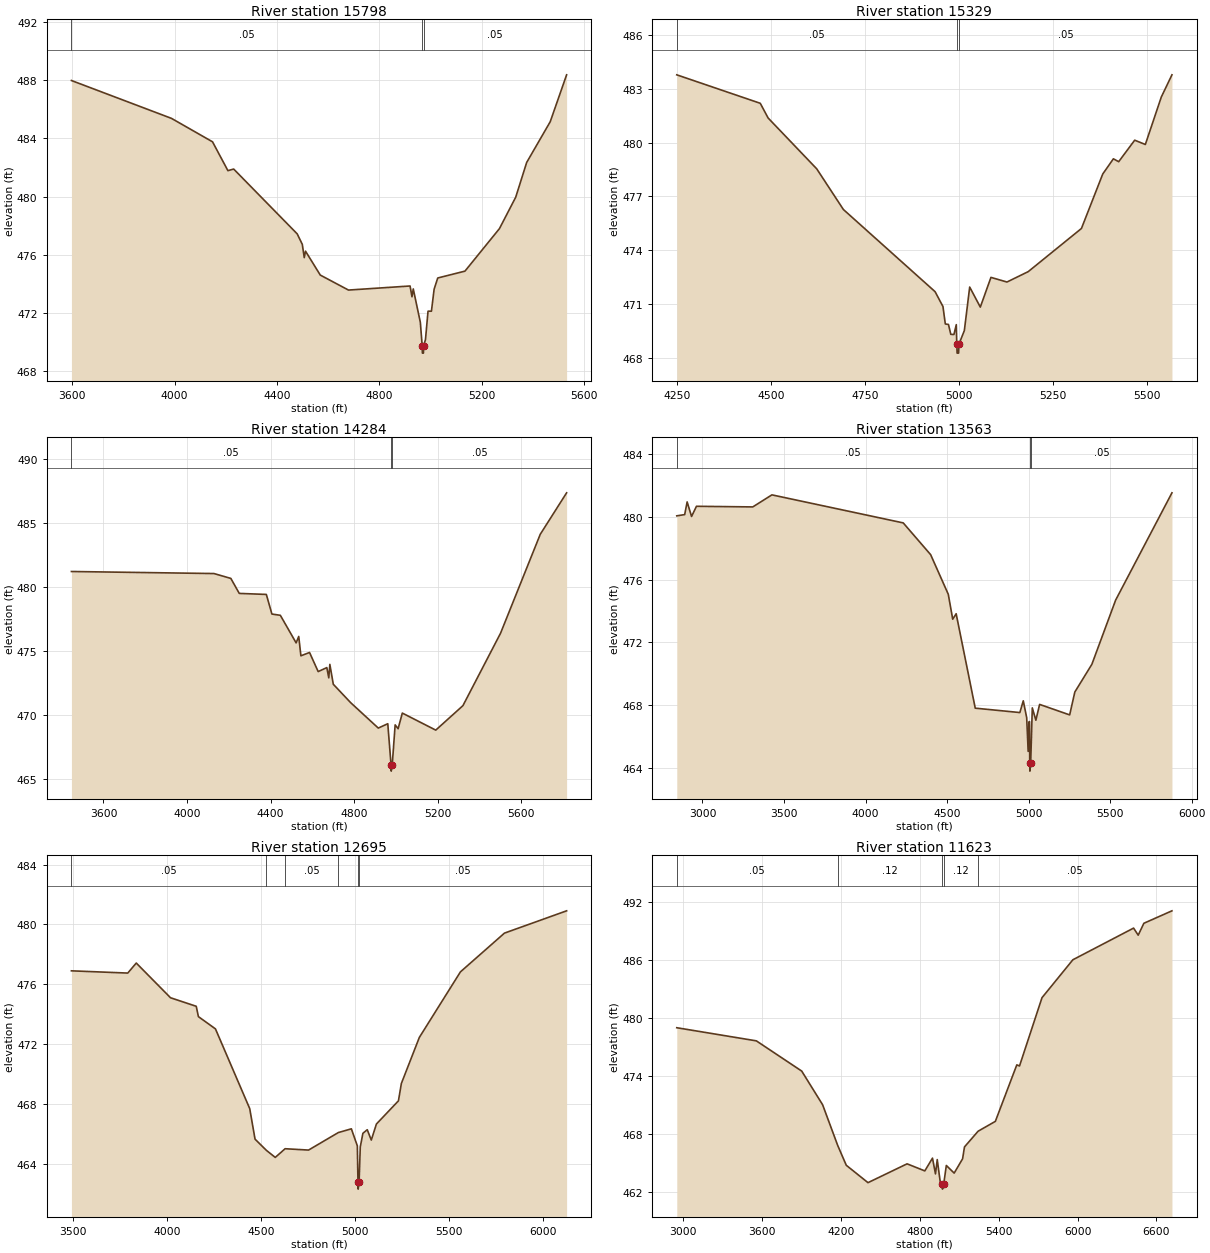
Type RM Length L Ch R = 1,15798,469,469,469
BEGIN DESCRIPTION:
Brushy Creek Trib 4 15.0
END DESCRIPTION:
XS GIS Cut Line= 3
      2616626.00      6973260.96      2616726.00      6971861.00
      2616326.02      6971511.02
#Sta/Elev= 30
  3596.8  487.97  3987.7  485.37  4148.2  483.76  4208.3  481.78  4230.9  481.89
  4479.0  477.44  4499.0  476.72  4506.6  475.81  4511.6  476.25  4569.2  474.61
  4679.5  473.58  4920.1  473.86  4927.6  473.12  4932.6  473.66  4960.2  471.37
  4967.5  469.75  4968.3  469.25  4972.2  469.25  4973.0  469.75  4980.3  470.18
  4990.3  472.13  5003.6  472.13  5014.1  473.64  5028.3  474.41  5134.6  474.88
  5269.4  477.80  5333.0  479.96  5375.7  482.34  5467.8  485.14  5531.8  488.36
#Mann=3,-1,0
  3596.8    0.05       0  4967.5    0.03       0  4973.0    0.05       0
Bank Sta=4967.5,4973
Exp/Cntr=0.3,0.1

Type RM Length L Ch R = 1,15329,1045,1045,1045
BEGIN DESCRIPTION:
Brushy Creek Trib 4 14.0
END DESCRIPTION:
XS GIS Cut Line= 3
      2617525.99      6972160.98      2617076.00      6971561.00
      2616675.97      6971160.97
#Sta/Elev= 30
  4249.8  483.79  4471.7  482.20  4492.5  481.38  4621.7  478.54  4692.5  476.27
  4936.2  471.68  4957.1  470.85  4963.3  469.88  4971.7  469.85  4977.9  469.30
  4986.2  469.29  4992.5  469.84  4993.8  468.75  4994.7  468.25  4998.6  468.25
  4999.5  468.75  5013.9  469.51  5028.1  471.94  5056.3  470.82  5084.6  472.48
  5127.1  472.22  5183.6  472.80  5325.0  475.21  5381.6  478.25  5409.9  479.10
  5424.0  478.94  5466.5  480.14  5494.8  479.90  5537.2  482.55  5565.5  483.79
#Mann=3,-1,0
  4249.8    0.05       0  4993.8    0.03       0  4999.5    0.05       0
Bank Sta=4993.8,4999.5
Exp/Cntr=0.3,0.1

Type RM Length L Ch R = 1,14284,721,721,721
BEGIN DESCRIPTION:
Brushy Creek Trib 4 12.0
END DESCRIPTION:
XS GIS Cut Line= 3
      2618978.15      6971080.12      2617458.64      6970680.79
      2616659.84      6970680.79
#Sta/Elev= 30
  3446.7  481.20  4129.0  481.04  4209.7  480.66  4250.0  479.49  4379.5  479.41
  4406.2  477.88  4446.6  477.78  4522.1  475.63  4534.6  476.13  4544.9  474.62
  4586.3  474.88  4627.6  473.39  4669.0  473.70  4678.4  472.90  4683.5  473.95
  4700.0  472.40  4782.7  470.97  4915.3  468.98  4960.8  469.32  4976.3  466.12
  4977.2  465.62  4982.1  466.12  4996.0  469.23  5010.2  468.93  5030.4  470.15
  5190.4  468.82  5320.4  470.73  5500.4  476.38  5690.4  484.10  5816.6  487.34
#Mann=3,-1,0
  3446.7    0.05       0  4976.3    0.03       0  4982.1    0.05       0
Bank Sta=4976.3,4982.1
Exp/Cntr=0.3,0.1

Type RM Length L Ch R = 1,13563,868,868,868
BEGIN DESCRIPTION:
Brushy Creek Trib 4 11.0
END DESCRIPTION:
XS GIS Cut Line= 3
      2619371.39      6971192.98      2617571.41      6969992.99
      2616771.43      6970342.99
#Sta/Elev= 30
  2842.7  480.08  2891.3  480.16  2906.3  480.97  2933.4  480.04  2963.4  480.69
  3308.9  480.65  3426.1  481.42  4231.4  479.63  4399.6  477.60  4507.7  475.07
  4534.8  473.48  4555.9  473.83  4673.0  467.80  4946.5  467.52  4967.5  468.27
  4988.5  467.19  4997.5  465.04  5003.3  466.94  5006.0  466.94  5007.0  464.28
  5008.0  463.78  5012.9  464.28  5022.8  467.82  5044.7  467.03  5067.7  468.04
  5252.0  467.37  5283.6  468.83  5388.1  470.60  5533.9  474.70  5879.2  481.55
#Mann=3,-1,0
  2842.7    0.05       0  5007.0    0.03       0  5012.9    0.05       0
Bank Sta=5007,5012.9
Exp/Cntr=0.3,0.1

Type RM Length L Ch R = 1,12695,1072,1072,1072
BEGIN DESCRIPTION:
Brushy Creek Trib 4 10.0
END DESCRIPTION:
XS GIS Cut Line= 3
      2618987.26      6969860.99      2617623.57      6969219.11
      2616652.20      6969791.57
#Sta/Elev= 30
  3492.8  476.90  3792.6  476.75  3837.8  477.42  4020.1  475.10  4156.9  474.53
  4168.4  473.84  4259.1  473.02  4441.5  467.69  4469.8  465.65  4530.3  464.90
  4577.3  464.43  4629.8  465.01  4754.4  464.92  4912.9  466.09  4982.3  466.34
  5014.1  465.20  5017.4  462.81  5018.4  462.31  5023.4  462.81  5029.7  465.13
  5043.6  466.04  5066.8  466.28  5088.3  465.59  5115.5  466.66  5232.7  468.21
  5248.3  469.37  5344.0  472.45  5562.6  476.83  5796.8  479.42  6127.5  480.91
#Mann=6,-1,0
  3492.8    0.05       0  4530.3    0.12       0  4629.8    0.05       0
  4912.9    0.12       0  5017.4    0.07       0  5023.4    0.05       0
Bank Sta=5017.4,5023.4
Exp/Cntr=0.3,0.1

Type RM Length L Ch R = 1,11623,472,472,472
BEGIN DESCRIPTION:
Brushy Creek Trib 4 9.0
END DESCRIPTION:
XS GIS Cut Line= 3
      2618917.85      6970368.83      2617776.00      6968661.00
      2616443.92      6967582.39
#Sta/Elev= 30
  2950.3  479.02  3555.8  477.66  3901.1  474.53  4060.3  471.04  4175.5  466.81
  4240.4  464.77  4405.6  462.97  4702.9  464.92  4838.0  464.19  4896.4  465.51
  4919.1  463.88  4932.5  465.36  4955.1  463.07  4970.9  462.80  4972.3  462.30
  4981.5  462.80  5001.7  464.75  5061.4  463.96  5125.4  465.44  5139.8  466.67
  5243.5  468.30  5374.8  469.32  5537.9  475.17  5558.7  475.06  5729.7  482.13
  5964.7  486.06  6426.7  489.34  6461.9  488.61  6505.0  489.84  6718.7  491.13
#Mann=5,-1,0
  2950.3    0.05       0  4175.5    0.12       0  4970.9    0.07       0
  4981.5    0.12       0  5243.5    0.05       0
Bank Sta=4970.9,4981.5
Exp/Cntr=0.3,0.1

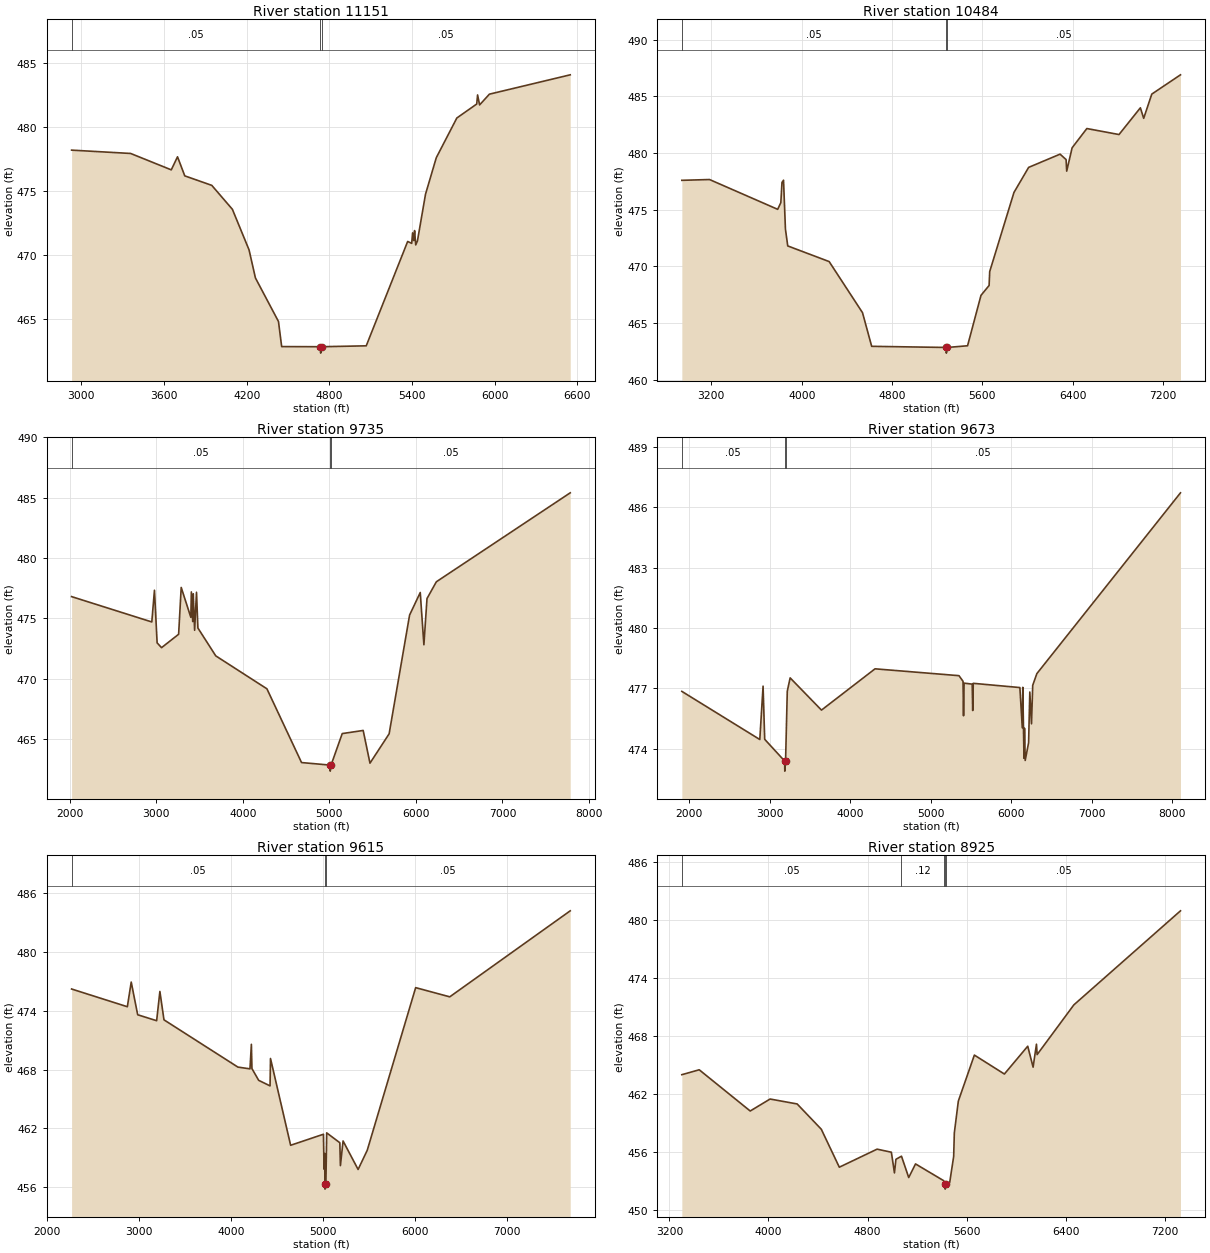
Type RM Length L Ch R = 1,11151,667,667,667
BEGIN DESCRIPTION:
Brushy Creek Trib 4 8.0
END DESCRIPTION:
XS GIS Cut Line= 3
      2619030.70      6970351.47      2618176.00      6968461.00
      2616934.33      6967543.29
#Sta/Elev= 30
  2929.4  478.17  3357.9  477.91  3652.8  476.63  3698.1  477.65  3750.8  476.16
  3946.6  475.42  4096.3  473.55  4217.3  470.38  4263.5  468.19  4430.8  464.79
  4453.9  462.83  4735.4  462.82  4736.9  462.32  4746.0  462.82  5067.7  462.89
  5368.4  471.04  5397.6  470.89  5403.9  471.71  5412.3  471.11  5418.5  471.89
  5426.9  470.77  5439.3  471.08  5497.9  474.73  5576.1  477.58  5725.3  480.68
  5869.4  481.77  5875.7  482.48  5890.3  481.70  5961.6  482.54  6548.1  484.05
#Mann=3,-1,0
  2929.4    0.05       0  4735.4    0.03       0  4746.0    0.05       0
Bank Sta=4735.4,4746
Exp/Cntr=0.3,0.1

Type RM Length L Ch R = 1,10484,749,749,749
BEGIN DESCRIPTION:
Brushy Creek Trib 4 6.0
END DESCRIPTION:
XS GIS Cut Line= 3
      2619152.21      6970251.58      2618759.49      6968228.04
      2616582.73      6967330.61
#Sta/Elev= 30
  2938.7  477.60  3183.8  477.67  3787.4  475.04  3815.3  475.63  3825.5  477.41
  3839.1  477.61  3856.1  473.29  3876.5  471.81  4243.2  470.43  4538.6  465.92
  4619.8  462.95  5279.6  462.85  5281.1  462.35  5290.5  462.85  5468.9  463.00
  5587.9  467.45  5659.7  468.32  5665.1  469.55  5879.9  476.53  6009.7  478.74
  6288.2  479.91  6341.5  479.43  6346.9  478.41  6394.8  480.47  6525.3  482.17
  6810.1  481.64  6999.4  484.00  7028.7  483.07  7100.5  485.21  7354.5  486.91
#Mann=3,-1,0
  2938.7    0.05       0  5279.6    0.03       0  5290.5    0.05       0
Bank Sta=5279.6,5290.5
Exp/Cntr=0.3,0.1

Type RM Length L Ch R = 1,9735,62,62,62
BEGIN DESCRIPTION:
Mapping XS 1c8b2336
END DESCRIPTION:
XS GIS Cut Line= 6
      2619333.25      6970309.74      2619091.46      6969097.12
      2619633.99      6968207.36      2619655.69      6967986.01
      2618713.85      6967243.82      2617009.59      6966103.31
#Sta/Elev= 30
  2023.0  476.81  2949.6  474.71  2980.2  477.34  3011.0  472.98  3062.1  472.58
  3259.5  473.69  3289.3  477.57  3400.7  475.09  3406.4  477.20  3422.5  474.74
  3428.2  477.04  3444.2  474.02  3466.0  477.17  3482.1  474.21  3688.5  471.90
  4279.6  469.17  4679.5  463.06  5009.3  462.85  5010.8  462.35  5020.5  462.85
  5149.5  465.46  5391.5  465.72  5470.1  463.01  5691.3  465.44  5927.7  475.28
  6050.8  477.15  6092.9  472.82  6128.9  476.65  6237.0  478.04  7783.5  485.41
#Mann=3,-1,0
  2023.0    0.05       0  5009.3    0.03       0  5020.5    0.05       0
Bank Sta=5009.3,5020.5
Exp/Cntr=0.3,0.1

Type RM Length L Ch R = 1,9673,58,58,58
BEGIN DESCRIPTION:
Mapping XS 87572fdd
END DESCRIPTION:
XS GIS Cut Line= 6
      2619365.37      6970355.75      2619124.19      6969058.77
      2619706.14      6968162.24      2619683.13      6967935.16
      2618521.68      6967030.21      2616791.09      6965882.70
#Sta/Elev= 30
  1909.0  476.85  2876.9  474.46  2917.5  477.11  2937.7  474.47  3185.6  473.39
  3187.1  472.89  3196.8  473.39  3218.1  476.86  3253.7  477.52  3642.7  475.92
  4307.6  477.97  5350.0  477.63  5400.1  477.35  5406.4  475.64  5413.3  477.26
  5514.1  477.21  5520.4  475.90  5527.3  477.25  6105.9  477.04  6136.0  475.04
  6142.0  477.05  6157.1  473.53  6163.1  475.02  6172.1  473.42  6214.2  474.30
  6229.3  476.82  6250.3  475.24  6265.4  477.15  6316.5  477.73  8100.0  486.71
#Mann=3,-1,0
  1909.0    0.05       0  3185.6    0.03       0  3196.8    0.05       0
Bank Sta=3185.6,3196.8
Exp/Cntr=0.3,0.1

Type RM Length L Ch R = 1,9615,690,690,690
BEGIN DESCRIPTION:
Mapping XS d3253c6d
END DESCRIPTION:
XS GIS Cut Line= 6
      2619328.87      6969989.47      2619168.28      6969095.38
      2619762.90      6968136.18      2619710.81      6967871.42
      2618890.17      6967233.34      2617163.07      6966078.89
#Sta/Elev= 30
  2263.8  476.23  2870.4  474.42  2912.5  476.94  2982.8  473.60  3189.1  472.99
  3224.4  475.98  3268.9  473.08  4073.3  468.25  4204.5  468.07  4219.9  470.58
  4225.8  468.10  4299.0  466.90  4422.9  466.33  4427.9  469.13  4646.9  460.26
  5004.0  461.39  5010.4  457.82  5018.5  459.42  5019.2  456.28  5020.7  455.78
  5030.4  456.28  5039.3  461.53  5182.1  460.52  5188.5  458.18  5217.4  460.70
  5381.0  457.79  5480.4  459.75  6007.2  476.37  6378.1  475.43  7688.9  484.22
#Mann=3,-1,0
  2263.8    0.05       0  5019.2    0.03       0  5030.4    0.05       0
Bank Sta=5019.2,5030.4
Exp/Cntr=0.3,0.1

Type RM Length L Ch R = 1,8925,942,942,942
BEGIN DESCRIPTION:
Brushy Creek Trib 4 3.0
END DESCRIPTION:
XS GIS Cut Line= 3
      2620320.63      6968657.03      2619600.14      6966755.97
      2617700.03      6966157.31
#Sta/Elev= 30
  3300.6  463.99  3440.7  464.50  3852.5  460.23  4012.9  461.47  4231.4  460.96
  4426.4  458.34  4571.8  454.41  4876.7  456.28  4992.0  455.96  5016.8  453.82
  5028.8  455.23  5073.7  455.55  5132.0  453.34  5187.0  454.75  5414.7  453.01
  5424.6  452.64  5426.1  452.14  5435.8  452.64  5462.6  452.81  5494.9  455.52
  5500.2  457.96  5532.6  461.26  5662.0  466.02  5904.3  464.06  6092.8  466.94
  6136.1  464.77  6163.2  467.15  6168.5  466.07  6465.0  471.22  7325.8  480.96
#Mann=5,-1,0
  3300.6    0.05       0  5073.7    0.12       0  5414.7    0.05       0
  5424.6    0.03       0  5435.8    0.05       0
Bank Sta=5424.6,5435.8
Exp/Cntr=0.3,0.1

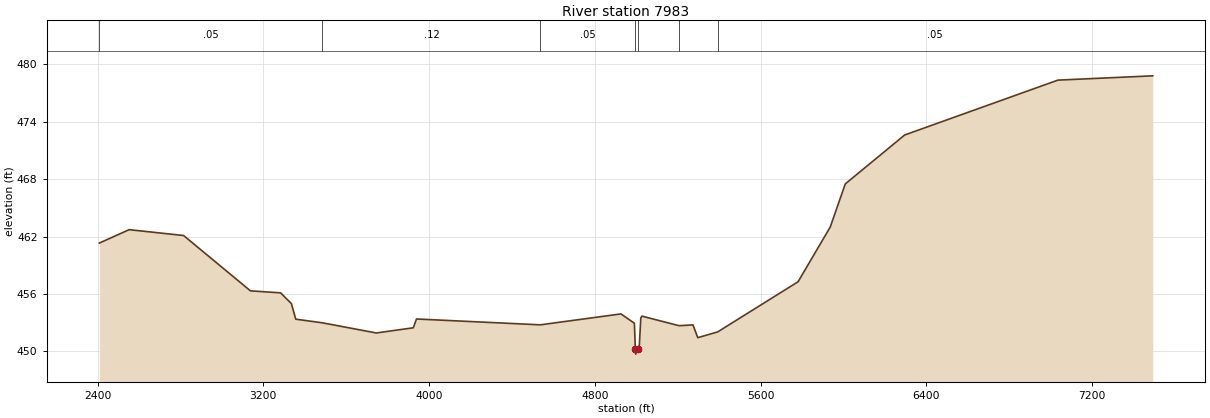
Type RM Length L Ch R = 1,7983,0,0,0
BEGIN DESCRIPTION:
Brushy Creek Trib 4 1.0
END DESCRIPTION:
XS GIS Cut Line= 4
      2620520.28      6968691.73      2620954.30      6967190.00
      2620276.00      6966411.00      2617872.67      6965766.38
#Sta/Elev= 30
  2408.6  461.32  2552.6  462.72  2815.3  462.11  3138.0  456.33  3283.7  456.12
  3335.8  454.99  3356.6  453.37  3485.5  452.99  3745.4  451.93  3923.9  452.47
  3939.5  453.39  4537.1  452.78  4926.4  453.92  4991.0  452.95  4995.8  450.22
  4997.3  449.72  5007.1  450.22  5015.1  450.67  5022.1  453.50  5027.3  453.69
  5206.7  452.69  5273.9  452.77  5297.0  451.44  5393.1  452.04  5781.2  457.28
  5936.5  463.00  6009.0  467.50  6295.8  472.61  7035.2  478.34  7493.0  478.79
#Mann=7,-1,0
  2408.6    0.05       0  3485.5    0.12       0  4537.1    0.05       0
  4995.8    0.03       0  5007.1    0.05       0  5206.7    0.12       0
  5393.1    0.05       0
Bank Sta=4995.8,5007.1
Exp/Cntr=0.3,0.1

Chan Stop Cuts=-1