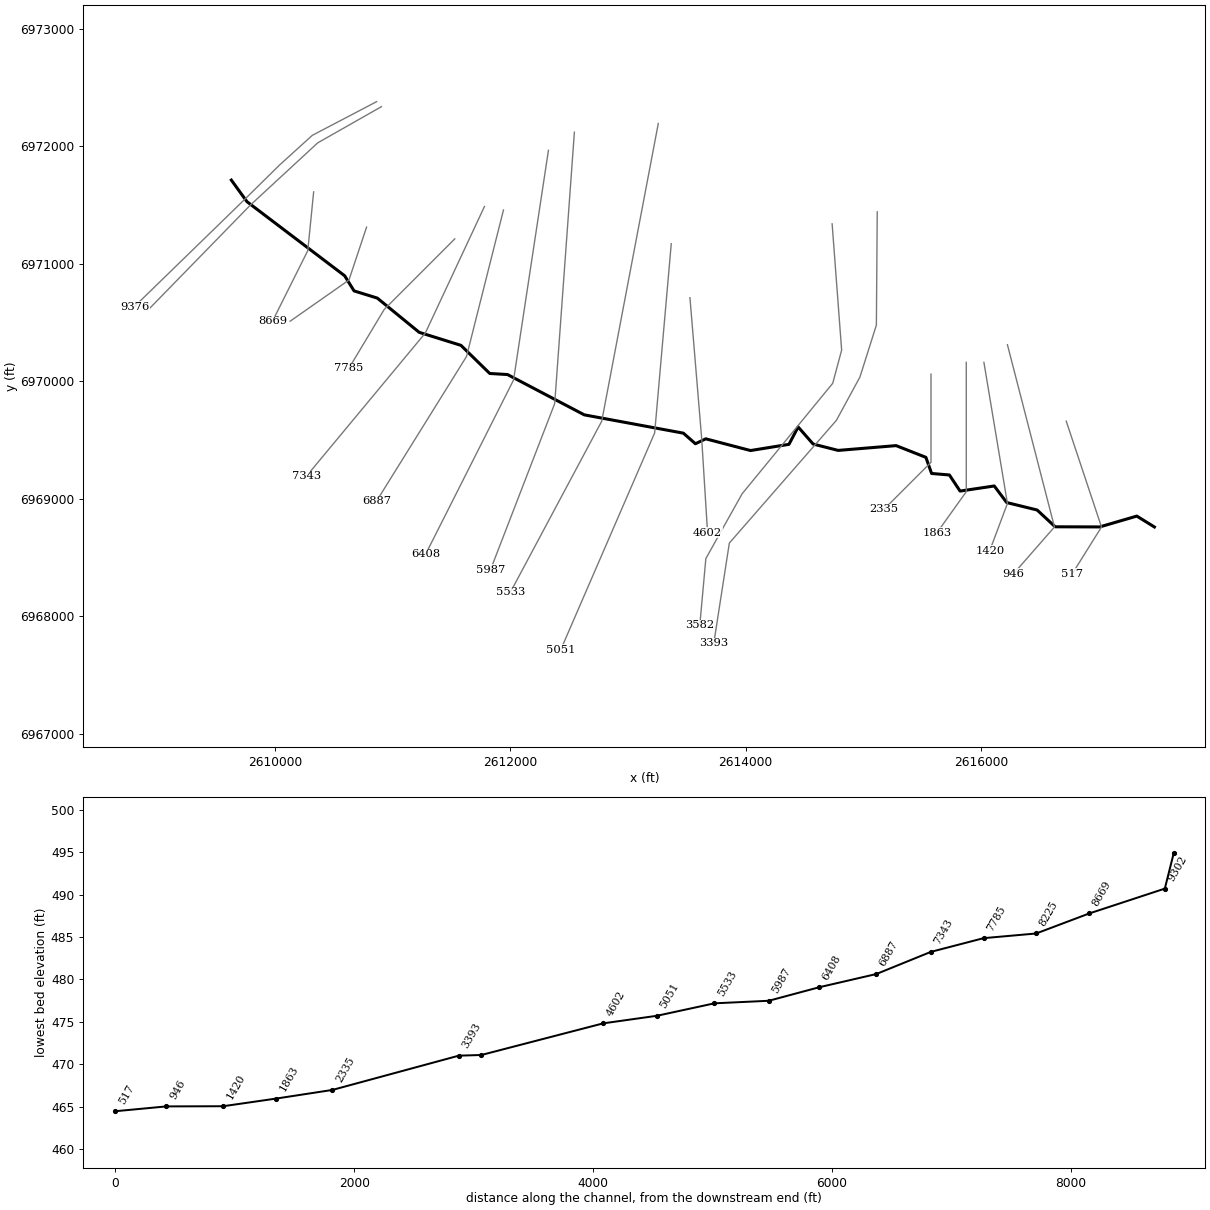
--- Brushy Creek Trib 4_1.prj (project) ---

Proj Title=Brushy Creek Trib 4_1 Base Level Engineering
Current Plan=p01
Default Exp/Contr=0.3,0.1
English Units
Geom File=g01
Flow File=f01
Plan File=p01
Y Axis Title=Elevation
X Axis Title(PF)=Main Channel Distance
X Axis Title(XS)=Station
BEGIN DESCRIPTION:
Brushy Creek Trib 4_1
END DESCRIPTION:
DSS Export Rating Curves= 0
DSS Export Rating Curve Sorted= 0
DSS Export Volume Flow Curves= 0
DXF OffsetX= 0
DXF OffsetY= 0
DXF ScaleX= 1
DXF ScaleY= 10

--- Brushy Creek Trib 4_1.p01 (plan) ---

Plan Title=Multiple Run
Short Identifier=Multiple
Geom File=g01
Flow File=f01
Subcritical Flow
K Sum by GR= 0
Std Step Tol= 0.01
Critical Tol= 0.01
Num of Std Step Trials= 20
Max Error Tol= 0.3
Flow Tol Ratio= 0.001
Split Flow NTrial= 30
Split Flow Tol= 0.02
Split Flow Ratio= 0.02
Log Output Level= 0
Friction Slope Method= 1
Unsteady Friction Slope Method= 2
Unsteady Bridges Friction Slope Method= 1
Parabolic Critical Depth
Global Vel Dist=  1 , 1 , 1
Global Log Level= 0
CheckData=True
Encroach Param= -1, 0, 0, 0
BEGIN DESCRIPTION:
Multiple Run
END DESCRIPTION:

--- Brushy Creek Trib 4_1.f01 (steady flow) ---

Flow Title=Multiple
Number of Profiles=7
Profile Names=10-year,25-year,50-year,1pct_min,100-year,1pct_plu,500-year
River Rch & RM= Brushy Creek Tri,Reach-1,9376
     515     684     819     487     972    1940    1368
River Rch & RM= Brushy Creek Tri,Reach-1,8669
     701     948    1150     692    1380    2754    1987
River Rch & RM= Brushy Creek Tri,Reach-1,6887
     973    1334    1631     988    1971    3932    2877
Boundary for River Rch & Prof#=Brushy Creek Tri,Reach-1,1
Up Type=0
Dn Type=3
Dn Slope=0.005
Boundary for River Rch & Prof#=Brushy Creek Tri,Reach-1,2
Up Type=0
Dn Type=3
Dn Slope=0.005
Boundary for River Rch & Prof#=Brushy Creek Tri,Reach-1,3
Up Type=0
Dn Type=3
Dn Slope=0.005
Boundary for River Rch & Prof#=Brushy Creek Tri,Reach-1,4
Up Type=0
Dn Type=3
Dn Slope=0.005
Boundary for River Rch & Prof#=Brushy Creek Tri,Reach-1,5
Up Type=0
Dn Type=3
Dn Slope=0.005
Boundary for River Rch & Prof#=Brushy Creek Tri,Reach-1,6
Up Type=0
Dn Type=3
Dn Slope=0.005
Boundary for River Rch & Prof#=Brushy Creek Tri,Reach-1,7
Up Type=0
Dn Type=3
Dn Slope=0.005

--- Brushy Creek Trib 4_1.g01 (geometry) ---

Geom Title=Existing Conditions
Program Version=4.10

River Reach=Brushy Creek Tri,Reach-1
Reach XY= 30
        2609626.        6971711.      2609758.95       6971527.5
      2610589.56      6970897.51      2610669.55      6970768.75
      2610867.51      6970707.47      2611223.34      6970416.46
      2611578.69      6970305.63      2611823.56      6970066.48
      2611974.53      6970057.44       2612627.5      6969714.62
      2613470.15      6969558.93       2613572.6      6969468.83
      2613660.58      6969510.85      2614041.39      6969411.09
      2614368.03      6969463.94       2614446.3      6969611.63
      2614573.54      6969466.46       2614786.5      6969412.22
      2615279.32      6969452.96       2615532.5      6969353.27
      2615581.08      6969216.04      2615732.47       6969203.3
       2615823.3      6969066.36      2616113.99      6969109.83
      2616219.81      6968968.86      2616478.43      6968905.48
      2616632.05      6968762.66      2617010.78      6968761.52
       2617326.1      6968853.69        2617476.        6968761.

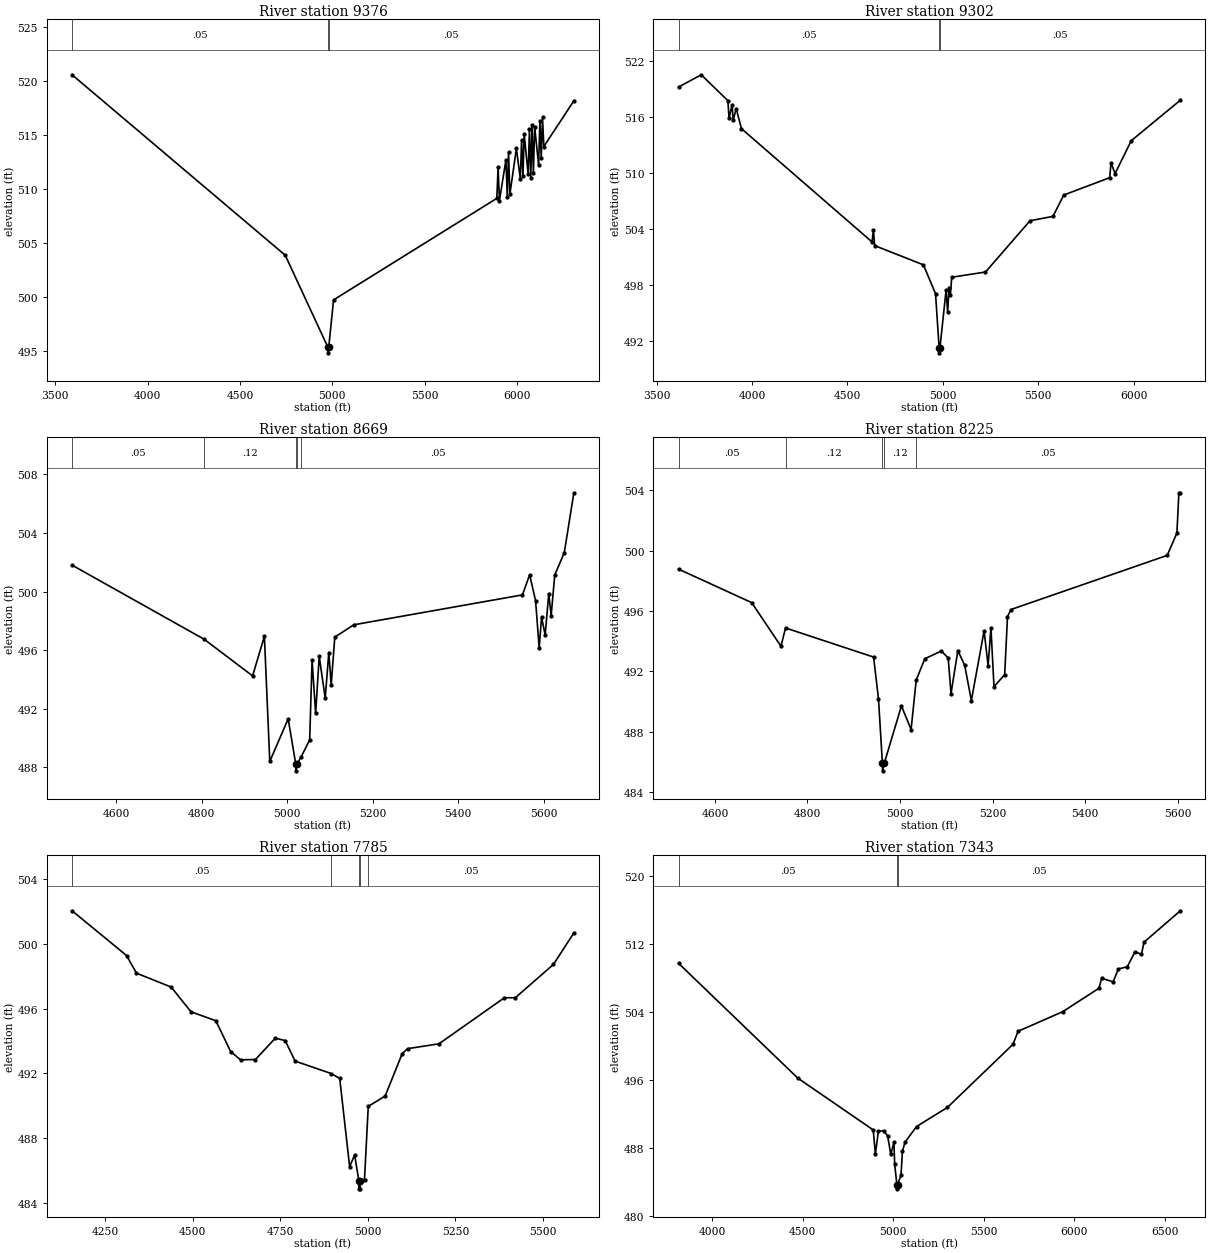
Type RM Length L Ch R = 1 ,9376    ,74,74,74
BEGIN DESCRIPTION:
Mapping XS 9b23d874
END DESCRIPTION:
XS GIS Cut Line= 5
      2610861.24      6972378.03      2610314.37      6972091.57
      2610036.59      6971839.84      2609741.45      6971549.04
      2608801.72      6970635.29
#Sta/Elev= 30
  3590.9  520.59  4745.4  503.88  4976.7  495.35  4976.9  494.85  4980.7  495.35
  5006.9  499.75    5891  509.15  5897.9  512.04  5905.1  508.94  5940.4  512.71
  5947.6  509.27  5954.5  513.44  5961.7  509.52    5997  513.77  6018.3  510.95
  6025.3  514.51  6032.4  511.19  6039.4  515.07  6060.7  511.36  6067.7  515.57
  6074.9  511.07  6081.8  515.94    6089   511.5    6096  515.76  6117.3  512.22
  6124.3  516.33  6131.5  512.92  6138.4  516.66  6145.6  513.95  6308.2  518.18
#Mann= 3 ,-1 , 0
  3590.9     .05       0  4976.7     .03       0  4980.7     .05       0
Bank Sta=4976.7,4980.7
XS Rating Curve= 0 ,0
Exp/Cntr=0.3,0.1

Type RM Length L Ch R = 1 ,9302    ,633,633,633
BEGIN DESCRIPTION:
Mapping XS 4407dbba
END DESCRIPTION:
XS GIS Cut Line= 4
      2610902.71      6972335.66       2610360.2      6972027.51
      2609787.29        6971498.      2608932.25      6970621.26
#Sta/Elev= 30
    3615  519.21  3733.9  520.53  3873.7  517.75  3879.5  515.84  3895.4  517.32
  3901.1  515.63    3917  516.91  3944.7  514.75  4628.5   502.6  4635.8  503.87
  4642.6   502.2  4897.8  500.14  4961.3  497.05  4980.3   491.2  4980.5   490.7
  4984.3   491.2  5016.5  497.42  5024.9  495.04  5031.9  497.66  5039.1  496.88
  5046.1  498.81    5223  499.37  5456.3  504.87  5576.4  505.34    5633  507.63
  5873.5  509.49  5880.7   511.1  5901.8  509.93  5986.7  513.46  6243.7   517.8
#Mann= 3 ,-1 , 0
    3615     .05       0  4980.3     .03       0  4984.3     .05       0
Bank Sta=4980.3,4984.3
XS Rating Curve= 0 ,0
Exp/Cntr=0.3,0.1

Type RM Length L Ch R = 1 ,8669    ,444,444,444
BEGIN DESCRIPTION:
Brushy Creek Trib 4_1 18.0
END DESCRIPTION:
XS GIS Cut Line= 3
        2610326.      6971610.97        2610276.        6971111.
      2609975.99      6970510.99
#Sta/Elev= 30
  4497.3  501.81  4806.3  496.75  4919.4  494.25    4947  496.95  4959.6  488.41
  5002.6  491.32  5020.1  488.27  5020.4  487.77  5024.1  488.27  5033.2  488.74
  5052.9  489.88  5058.5  495.32  5066.8  491.69  5075.2  495.58  5089.2  492.74
  5097.6  495.84  5103.2  493.64  5111.6   496.9  5156.3  497.74  5550.4  499.78
  5567.2  501.15  5581.1  499.38  5589.5  496.16  5595.1  498.26  5603.5  497.04
  5611.9  499.87  5617.5  498.36  5625.9  501.14  5648.2  502.66  5670.6  506.75
#Mann= 5 ,-1 , 0
  4497.3     .05       0  4806.3     .12       0  5020.1     .07       0
  5024.1     .12       0  5033.2     .05       0
Bank Sta=5020.1,5024.1
XS Rating Curve= 0 ,0
Exp/Cntr=0.3,0.1

Type RM Length L Ch R = 1 ,8225    ,440,440,440
BEGIN DESCRIPTION:
Brushy Creek Trib 4_1 17.0
END DESCRIPTION:
XS GIS Cut Line= 3
        2610776.        6971311.        2610626.        6970861.
      2610125.98      6970510.98
#Sta/Elev= 30
  4521.3  498.78  4679.4  496.56  4742.7  493.67  4752.6  494.88  4942.9  492.95
  4953.5  490.19    4962  485.91  4962.3  485.41    4966  485.91  5003.1  489.71
    5024  488.15  5035.1  491.43  5053.6  492.84  5089.4  493.35  5104.2  492.89
  5110.3  490.53  5125.1  493.38  5139.9   492.4  5154.3  490.07  5181.8  494.69
  5190.5  492.38  5196.6  494.89  5203.2  490.99  5226.3  491.78  5232.4  495.63
  5239.8   496.1  5577.6  499.69  5598.6  501.17  5602.9  503.84    5606  503.84
#Mann= 5 ,-1 , 0
  4521.3     .05       0  4752.6     .12       0    4962     .07       0
    4966     .12       0  5035.1     .05       0
Bank Sta=4962,4966
XS Rating Curve= 0 ,0
Exp/Cntr=0.3,0.1

Type RM Length L Ch R = 1 ,7785    ,442,442,442
BEGIN DESCRIPTION:
Brushy Creek Trib 4_1 16.0
END DESCRIPTION:
XS GIS Cut Line= 3
      2611525.97      6971210.97        2610926.        6970611.
      2610625.99      6970110.98
#Sta/Elev= 30
  4156.2  502.06  4311.7  499.29    4340   498.2    4439  497.34  4495.6  495.81
  4566.3  495.26  4608.7  493.35    4637  492.84  4679.4  492.86    4736  494.18
  4764.3  494.03  4792.6  492.76  4895.8  491.99  4919.8  491.69  4948.1  486.23
  4962.3  486.96  4974.4  485.36  4974.6  484.86  4978.1  484.86  4978.4  485.36
  4990.5  485.43  5001.2  489.96  5049.4   490.6    5098  493.22  5113.5  493.53
  5202.9  493.83  5389.5  496.68  5420.6  496.68  5529.5  498.74  5587.8  500.69
#Mann= 5 ,-1 , 0
  4156.2     .05       0  4895.8     .12       0  4974.4     .07       0
  4978.4     .12       0  5001.2     .05       0
Bank Sta=4974.4,4978.4
XS Rating Curve= 0 ,0
Exp/Cntr=0.3,0.1

Type RM Length L Ch R = 1 ,7343    ,456,456,456
BEGIN DESCRIPTION:
Brushy Creek Trib 4_1 15.0
END DESCRIPTION:
XS GIS Cut Line= 3
       2611778.4      6971486.13        2611276.        6970411.
      2610263.21       6969191.3
#Sta/Elev= 30
  3813.2  509.74    4472  496.25  4888.8  490.16  4900.6  487.33  4917.2  489.99
  4945.6  490.07  4968.4  489.47  4985.7  487.29  5003.2   488.7  5007.1  486.17
  5019.4  483.74  5019.7  483.24  5023.4  483.74  5042.2  484.86  5050.1  487.66
  5064.4  488.72  5128.2  490.56  5298.8  492.81  5660.8  500.22  5688.8  501.75
  5936.8  504.07    6136  506.81  6150.4  507.98  6214.2  507.56  6242.8  509.07
  6292.3  509.33  6335.3  511.11  6370.4  510.78  6384.7  512.22  6585.3  515.91
#Mann= 3 ,-1 , 0
  3813.2     .05       0  5019.4     .03       0  5023.4     .05       0
Bank Sta=5019.4,5023.4
XS Rating Curve= 0 ,0
Exp/Cntr=0.3,0.1

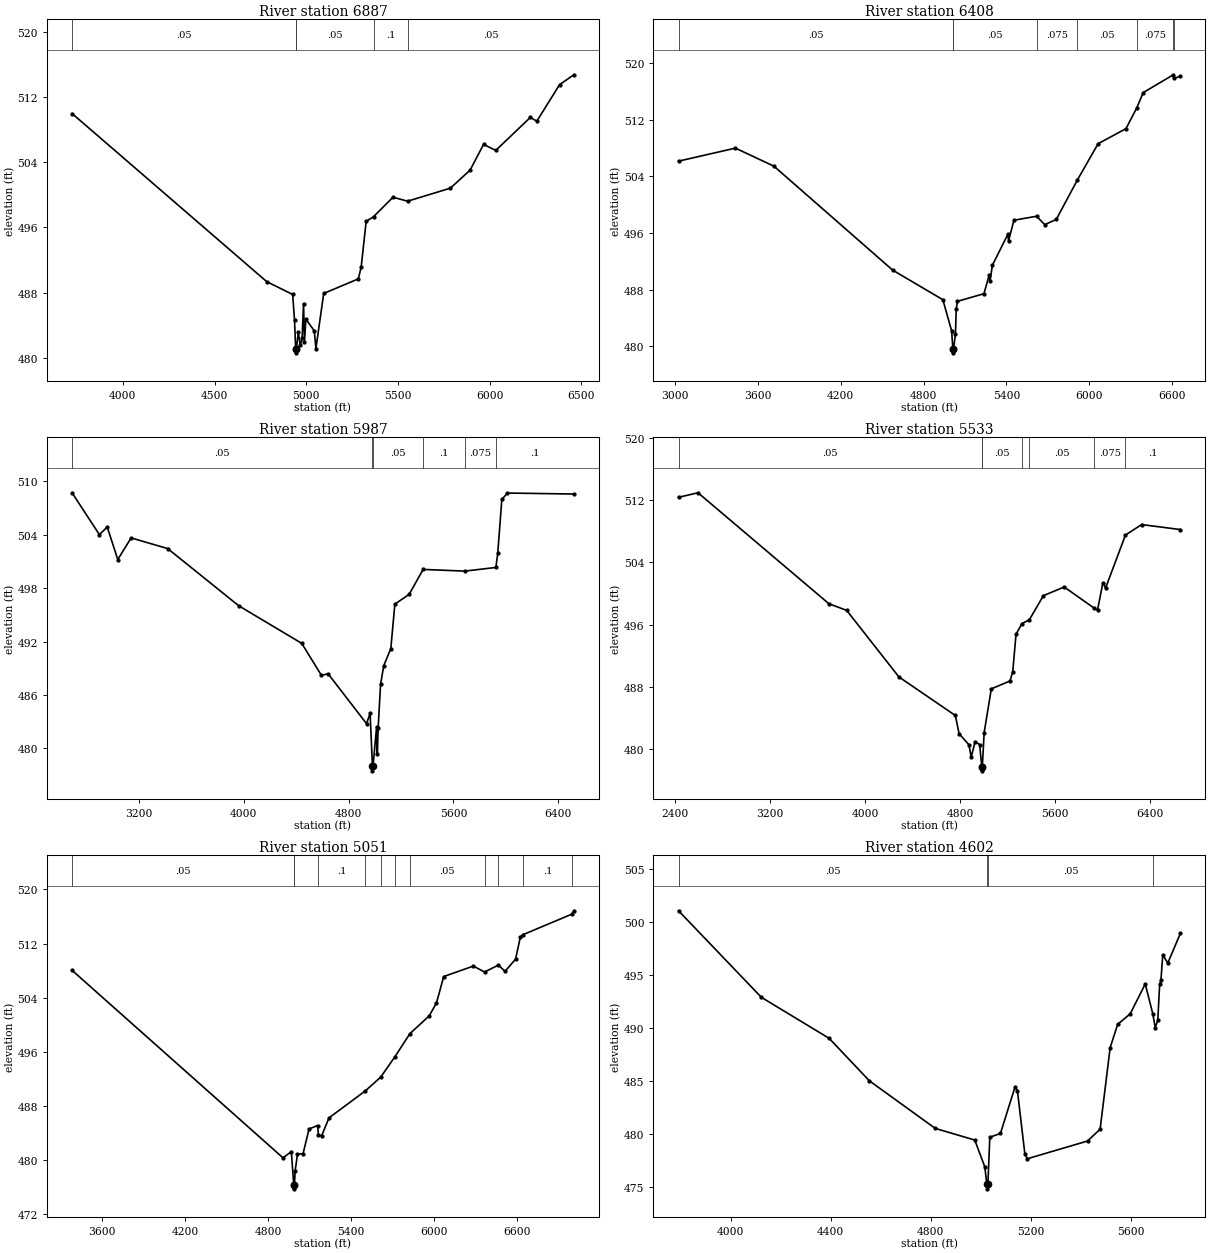
Type RM Length L Ch R = 1 ,6887    ,479,479,479
BEGIN DESCRIPTION:
Brushy Creek Trib 4_1 14.0
END DESCRIPTION:
XS GIS Cut Line= 3
       2611940.2      6971456.68        2611626.        6970211.
      2610859.99      6968979.61
#Sta/Elev= 30
  3723.6  509.97    4785  489.35  4925.8  487.79  4936.1  484.61  4942.1  481.13
  4942.4  480.63  4946.1  481.13  4956.7  483.16    4967  481.54  4977.4   482.4
  4985.2  486.66  4990.3  482.02    4998  484.75  5043.6  483.33  5052.6  481.16
  5095.1  487.91  5283.9   489.7  5299.3  491.14  5326.4  496.74  5366.6  497.32
  5472.8  499.71  5552.1  499.22  5785.6  500.82    5893  503.03  5966.2  506.18
  6032.9  505.45  6221.3  509.49  6256.7  509.03  6380.6  513.51  6458.5  514.72
#Mann= 5 ,-1 , 0
  3723.6     .05       0  4942.1     .03       0  4946.1     .05       0
  5366.6      .1       0  5552.1     .05       0
Bank Sta=4942.1,4946.1
XS Rating Curve= 0 ,0
Exp/Cntr=0.3,0.1

Type RM Length L Ch R = 1 ,6408    ,421,421,421
BEGIN DESCRIPTION:
Brushy Creek Trib 4_1 13.0
END DESCRIPTION:
XS GIS Cut Line= 3
      2612322.68      6971964.19        2612026.        6970011.
      2611278.26      6968529.38
#Sta/Elev= 30
  3024.4  506.17  3436.2  508.01  3715.4  505.46  4575.2  490.77  4939.3  486.58
  5002.8  482.18  5011.9  479.57  5012.2  479.07    5016  479.57  5030.6  481.72
  5036.2  485.27  5044.8  486.35  5236.9  487.43  5275.9  490.13  5281.5  489.26
  5298.2  491.46  5409.7  495.81  5415.3  494.91  5454.3  497.82  5618.4  498.38
  5677.3  497.19  5760.9  497.93    5913  503.48  6064.1  508.64  6265.7  510.76
  6342.9  513.65  6390.9  515.86  6608.8  518.38  6617.1  517.91  6659.6  518.15
#Mann= 8 ,-1 , 0
  3024.4     .05       0  5011.9     .03       0    5016     .05       0
  5618.4    .075       0    5913     .05       0  6342.9    .075       0
  6608.8     .05       0  6617.1    .075       0
Bank Sta=5011.9,5016
XS Rating Curve= 0 ,0
Exp/Cntr=0.3,0.1

Type RM Length L Ch R = 1 ,5987    ,454,454,454
BEGIN DESCRIPTION:
Brushy Creek Trib 4_1 12.0
END DESCRIPTION:
XS GIS Cut Line= 3
      2612543.34      6972118.73        2612376.        6969811.
      2611830.43      6968398.38
#Sta/Elev= 30
  2690.6  508.72  2898.9  504.02    2959  504.88  3039.2  501.22  3141.1  503.65
  3420.2  502.45  3961.7  496.03  4442.9   491.8  4593.3   488.2  4643.4  488.39
  4937.2  482.78  4964.3  483.94  4982.2  477.98  4982.5  477.48  4986.4  477.98
    5014  482.43  5019.4  479.37  5025.8   482.3    5044   487.2  5068.6   489.3
  5122.3  491.22  5153.1  496.21  5261.7   497.3  5368.9  500.11  5686.6  499.92
  5923.9  500.33  5938.3  501.97  5969.2  507.97  6012.1  508.69  6518.7  508.58
#Mann= 6 ,-1 , 0
  2690.6     .05       0  4982.2     .03       0  4986.4     .05       0
  5368.9      .1       0  5686.6    .075       0  5923.9      .1       0
Bank Sta=4982.2,4986.4
XS Rating Curve= 0 ,0
Exp/Cntr=0.3,0.1

Type RM Length L Ch R = 1 ,5533    ,482,482,482
BEGIN DESCRIPTION:
Brushy Creek Trib 4_1 11.0
END DESCRIPTION:
XS GIS Cut Line= 3
       2613256.8      6972192.27        2612776.        6969661.
      2611999.11      6968205.82
#Sta/Elev= 30
  2427.8  512.37    2592  512.95  3693.9  498.68  3843.9  497.82  4283.8  489.26
  4759.1   484.3  4790.6  481.96  4873.7  480.53  4892.4  478.96    4926  480.94
  4963.6  480.56  4981.9  477.68  4982.2  477.18  4986.1  477.68  5001.8   482.1
    5062  487.73  5219.7  488.74  5242.4  489.94  5270.2  494.76  5320.2  496.12
  5382.7  496.62  5500.4  499.71    5676  500.83  5924.4  498.15  5956.5  497.87
  6001.9  501.39  6024.6  500.71    6192  507.52  6328.2  508.86  6653.9  508.22
#Mann= 7 ,-1 , 0
  2427.8     .05       0  4981.9     .03       0  4986.1     .05       0
  5320.2      .1       0  5382.7     .05       0  5924.4    .075       0
    6192      .1       0
Bank Sta=4981.9,4986.1
XS Rating Curve= 0 ,0
Exp/Cntr=0.3,0.1

Type RM Length L Ch R = 1 ,5051    ,449,449,449
BEGIN DESCRIPTION:
Brushy Creek Trib 4_1 10.0
END DESCRIPTION:
XS GIS Cut Line= 3
      2613367.12       6971169.9        2613226.        6969561.
      2612426.34       6967714.5
#Sta/Elev= 30
  3384.5  508.04  4909.2   480.3  4969.5  481.21  4987.3  476.21  4987.7  475.71
  4991.8  476.21  4997.1  478.37    5014  480.85  5054.1   480.9  5097.7  484.57
  5159.7  485.08  5165.8  483.65  5189.3  483.59  5241.7  486.21  5503.7  490.19
  5615.7  492.24  5719.2  495.28    5827  498.68  5966.2   501.3  6018.6  503.21
    6071  507.12  6285.5  508.67  6365.9  507.79  6466.3  508.81  6514.3  507.89
  6590.6   509.7  6625.7  513.04    6646  513.33  6998.3  516.36  7011.8  516.85
#Mann= 12 ,-1 , 0
  3384.5     .05       0  4987.3     .03       0  4991.8     .05       0
  5159.7      .1       0  5503.7    .075       0  5615.7     .05       0
  5719.2    .075       0    5827     .05       0  6365.9      .1       0
  6466.3    .075       0    6646      .1       0  6998.3    .075       0
Bank Sta=4987.3,4991.8
XS Rating Curve= 0 ,0
Exp/Cntr=0.3,0.1

Type RM Length L Ch R = 1 ,4602    ,1020,1020,1020
BEGIN DESCRIPTION:
Brushy Creek Trib 4_1 9.0
END DESCRIPTION:
XS GIS Cut Line= 3
        2613526.      6970711.01        2613626.        6969511.
        2613676.      6968711.03
#Sta/Elev= 30
  3791.5  501.04  4122.6  492.88  4393.6  489.01  4554.1  485.01  4817.5  480.52
  4975.6  479.42  5015.7  476.89  5023.4  475.32  5023.9  474.82  5028.1  475.32
  5035.7  479.68  5078.3  480.05  5135.9  484.39    5146  484.09    5176  478.07
    5186  477.66  5426.5  479.33  5476.6  480.45  5516.7  488.13  5546.7  490.33
  5596.8  491.32    5657  494.14  5687.7  491.27    5697  490.01  5707.1  490.71
  5714.6   494.1  5719.6  494.48  5727.1  496.88  5747.1  496.11  5797.2   498.9
#Mann= 4 ,-1 , 0
  3791.5     .05       0  5023.4     .03       0  5028.1     .05       0
  5687.7    .075       0
#XS Ineff= 2 , 0
       0                  5135.9       0  484.39
Permanent Ineff=
       F       F
Bank Sta=5023.4,5028.1
XS Rating Curve= 0 ,0
Exp/Cntr=0.3,0.1

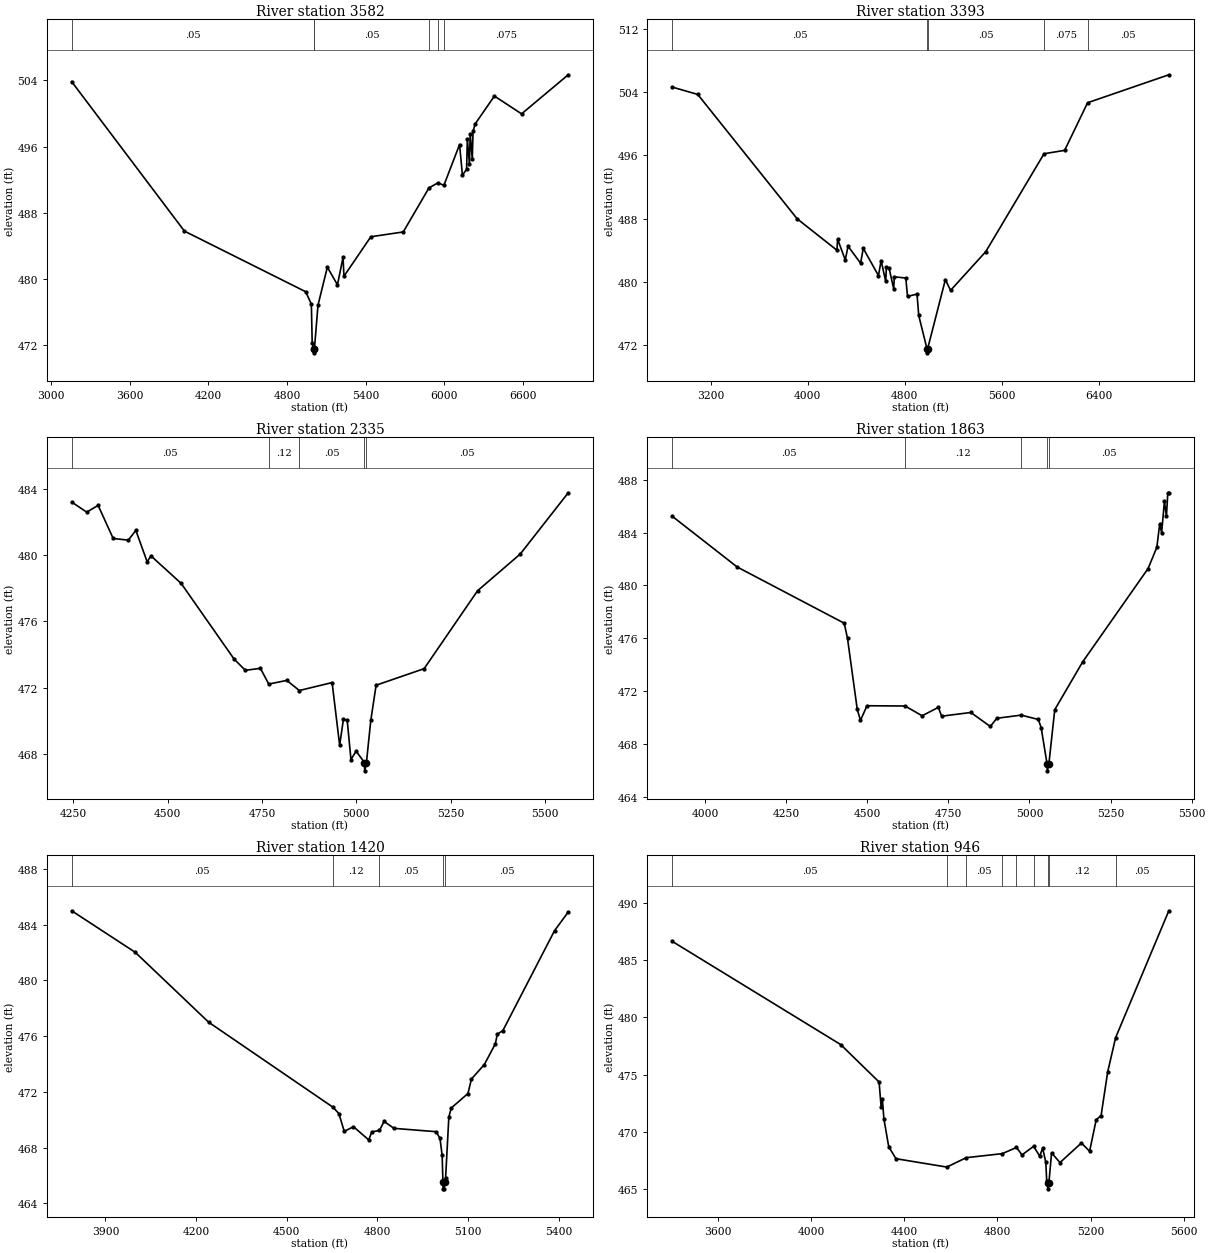
Type RM Length L Ch R = 1 ,3582    ,189,189,189
BEGIN DESCRIPTION:
Mapping XS 45397933
END DESCRIPTION:
XS GIS Cut Line= 6
      2614735.18      6971339.08      2614816.09      6970265.17
      2614740.21      6969982.87      2613970.25      6969044.21
      2613661.33      6968492.57      2613609.84      6967926.23
#Sta/Elev= 30
  3156.6  503.84  4017.1  485.79  4942.9  478.47  4986.1  476.97  4992.5  472.22
  5004.6  471.59  5005.2  471.09  5009.6  471.59  5036.7  476.85  5108.2  481.44
  5185.4   479.3  5227.8  482.63  5234.8  480.34    5440  485.11  5687.5  485.69
  5883.8  491.01  5953.2  491.63  5997.5  491.31  6117.4  496.25  6139.2  492.53
    6171  493.26  6176.7   496.9  6192.7  493.84  6198.4  497.55  6214.4  494.47
  6220.1  497.83  6236.1  498.73  6383.2   502.1  6590.6  499.95  6946.8  504.67
#Mann= 6 ,-1 , 0
  3156.6     .05       0  5004.6     .05       0  5009.6     .05       0
  5883.8    .075       0  5953.2     .05       0  5997.5    .075       0
Bank Sta=5004.6,5009.6
XS Rating Curve= 0 ,0
Exp/Cntr=0.3,0.1

Type RM Length L Ch R = 1 ,3393    ,1058,1058,1058
BEGIN DESCRIPTION:
Mapping XS 7c233eb0
END DESCRIPTION:
XS GIS Cut Line= 6
      2615118.83      6971441.31      2615111.47      6970477.78
      2614971.72      6970036.47      2614771.46      6969667.77
      2613861.09      6968624.27      2613728.69      6967771.02
#Sta/Elev= 30
  2883.9  504.66  3094.2  503.73  3913.8  487.98    4242     484  4247.2  485.41
  4310.4  482.77  4333.3  484.51  4436.8  482.36  4458.7  484.24  4584.1  480.79
    4606  482.69    4644  480.06  4649.7  481.85  4671.6  481.74  4709.6  479.13
  4715.3  480.64  4809.5  480.48  4823.8  478.15  4901.9  478.45  4916.2  475.74
  4984.3  471.51  4984.9  471.01  4989.3  471.51  5135.9  480.28  5178.6  478.92
  5468.8  483.82  5949.3  496.22  6119.3  496.65  6308.6  502.68  6978.3  506.22
#Mann= 5 ,-1 , 0
  2883.9     .05       0  4984.3     .05       0  4989.3     .05       0
  5949.3    .075       0  6308.6     .05       0
Bank Sta=4984.3,4989.3
XS Rating Curve= 0 ,0
Exp/Cntr=0.3,0.1

Type RM Length L Ch R = 1 ,2335    ,472,472,472
BEGIN DESCRIPTION:
Brushy Creek Trib 4_1 5.0
END DESCRIPTION:
XS GIS Cut Line= 3
        2615576.      6970061.05        2615576.        6969311.
      2615176.02      6968911.02
#Sta/Elev= 30
  4245.7   483.2  4285.7  482.59  4315.7     483  4355.7     481  4395.7   480.9
  4415.7  481.49  4445.7  479.59  4455.7  479.95  4535.7  478.29  4675.7  473.73
  4705.7  473.04  4745.7  473.16  4767.9  472.21  4815.7  472.43  4848.8  471.82
  4935.7   472.3  4955.7  468.52  4965.7  470.08  4975.7  470.03  4985.7  467.65
  4999.3  468.16  5021.4  467.47  5022.1  466.97  5026.7  467.47  5038.2  470.01
  5052.3  472.14  5179.6  473.14    5321  477.84  5434.2  480.06  5561.4  483.76
#Mann= 5 ,-1 , 0
  4245.7     .05       0  4767.9     .12       0  4848.8     .05       0
  5021.4     .03       0  5026.7     .05       0
Bank Sta=5021.4,5026.7
XS Rating Curve= 0 ,0
Exp/Cntr=0.3,0.1

Type RM Length L Ch R = 1 ,1863    ,443,443,443
BEGIN DESCRIPTION:
Brushy Creek Trib 4_1 4.0
END DESCRIPTION:
XS GIS Cut Line= 3
        2615876.      6970160.95        2615876.        6969061.
      2615625.98      6968710.98
#Sta/Elev= 30
  3899.5  485.23  4099.5  481.39  4429.5  477.13  4439.5  475.98  4469.5  470.61
  4479.5  469.77  4499.5  470.88  4616.9  470.86  4669.5  470.12  4719.5  470.76
  4729.5  470.09  4819.5  470.37  4879.5  469.31  4899.5  469.93  4974.6  470.17
  5027.7  469.84  5036.3  469.21  5054.6  466.45  5055.3  465.95  5059.9  466.45
  5078.1  470.58  5164.1   474.2  5365.7  481.27  5392.7  482.88  5401.3  484.61
  5407.5     484  5416.1  486.36  5422.2  485.22  5426.5  487.01  5429.6  487.01
#Mann= 5 ,-1 , 0
  3899.5     .05       0  4616.9     .12       0  4974.6     .05       0
  5054.6     .03       0  5059.9     .05       0
Bank Sta=5054.6,5059.9
XS Rating Curve= 0 ,0
Exp/Cntr=0.3,0.1

Type RM Length L Ch R = 1 ,1420    ,474,474,474
BEGIN DESCRIPTION:
Brushy Creek Trib 4_1 3.0
END DESCRIPTION:
XS GIS Cut Line= 3
        2616026.      6970161.02        2616226.        6968961.
      2616075.99      6968560.98
#Sta/Elev= 30
  3788.2     485  3998.6  482.02  4241.9     477  4652.9  470.91  4672.8  470.45
  4690.5  469.17  4720.9  469.51  4771.6  468.56  4781.7  469.14  4807.2  469.24
  4822.3  469.89  4855.2  469.39  4994.6  469.15  5007.4  468.67  5014.6  467.46
  5017.2  465.55    5018  465.05  5021.9  465.05  5022.7  465.55  5026.1  465.86
  5036.8  470.21  5044.8  470.85    5100  471.89  5111.6  472.93  5154.3  473.97
  5190.8  475.46    5197  476.14  5215.7  476.41  5386.6  483.57    5432  484.91
#Mann= 5 ,-1 , 0
  3788.2     .05       0  4652.9     .12       0  4807.2     .05       0
  5017.2     .03       0  5022.7     .05       0
Bank Sta=5017.2,5022.7
XS Rating Curve= 0 ,0
Exp/Cntr=0.3,0.1

Type RM Length L Ch R = 1 ,946     ,429,429,429
BEGIN DESCRIPTION:
Brushy Creek Trib 4_1 2.0
END DESCRIPTION:
XS GIS Cut Line= 3
      2616225.99      6970311.03        2616626.        6968761.
      2616276.01      6968361.01
#Sta/Elev= 30
  3403.9  486.62  4126.9  477.62  4292.1  474.35  4300.8  472.18    4306  472.85
  4312.8  471.12  4333.4  468.71  4364.4  467.66  4582.8  466.93  4666.5  467.75
  4820.9   468.1  4882.1  468.64  4905.6  467.99  4955.7  468.74  4981.8  467.88
  4994.4  468.58    5008  467.34  5011.8  465.72  5015.7  465.53  5016.5  465.03
  5021.2  465.53  5032.7  468.17  5068.8  467.32  5160.8  469.03    5196  468.31
  5224.4  471.06  5245.3  471.42  5273.8  475.24  5307.7  478.22  5536.2  489.29
#Mann= 9 ,-1 , 0
  3403.9     .05       0  4582.8     .12       0  4666.5     .05       0
  4820.9     .12       0  4882.1     .05       0  4955.7     .12       0
  5015.7     .07       0  5021.2     .12       0  5307.7     .05       0
Bank Sta=5015.7,5021.2
XS Rating Curve= 0 ,0
Exp/Cntr=0.3,0.1

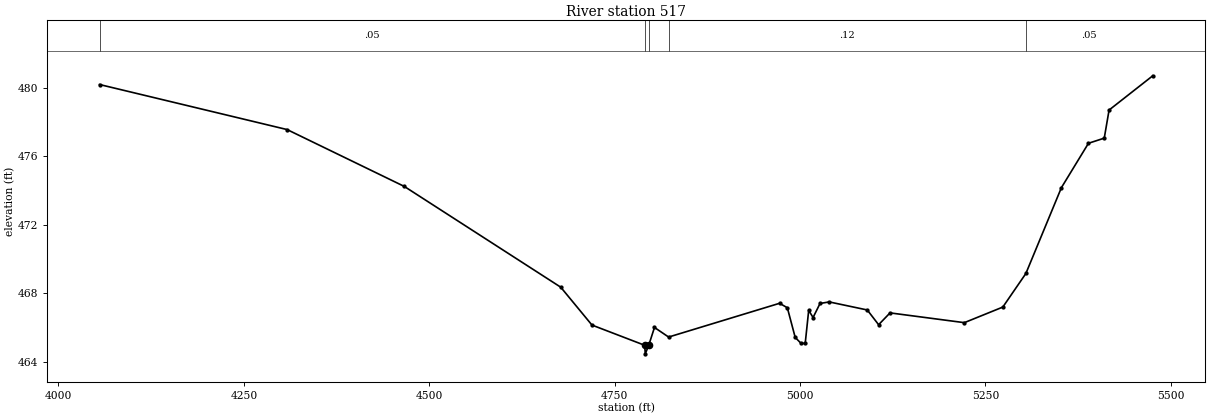
Type RM Length L Ch R = 1 ,517     ,0,0,0
BEGIN DESCRIPTION:
Brushy Creek Trib 4_1 1.0
END DESCRIPTION:
XS GIS Cut Line= 3
      2616725.99      6969661.04        2617026.        6968761.
      2616776.01      6968361.02
#Sta/Elev= 30
  4055.4  480.18  4308.4  477.55  4466.5  474.23  4677.4  468.35  4719.5  466.14
  4790.6  464.96  4791.4  464.46  4796.1  464.96  4803.8     466  4822.9  465.44
  4972.5  467.41    4983  467.15  4993.6  465.42  5001.5  465.07  5007.1  465.07
  5011.8     467  5017.7  466.58  5027.1   467.4  5039.5  467.49  5090.8  467.02
  5106.1  466.16  5121.5  466.85  5221.7  466.28  5273.6  467.19  5304.7  469.15
  5352.6  474.16  5389.1  476.75  5410.4  477.05  5416.9  478.69  5475.8  480.69
#Mann= 5 ,-1 , 0
  4055.4     .05       0  4790.6     .07       0  4796.1     .05       0
  4822.9     .12       0  5304.7     .05       0
Bank Sta=4790.6,4796.1
XS Rating Curve= 0 ,0
Exp/Cntr=0.3,0.1

Chan Stop Cuts=-1
Use User Specified Reach Order=0
Composite Channel Slope=5