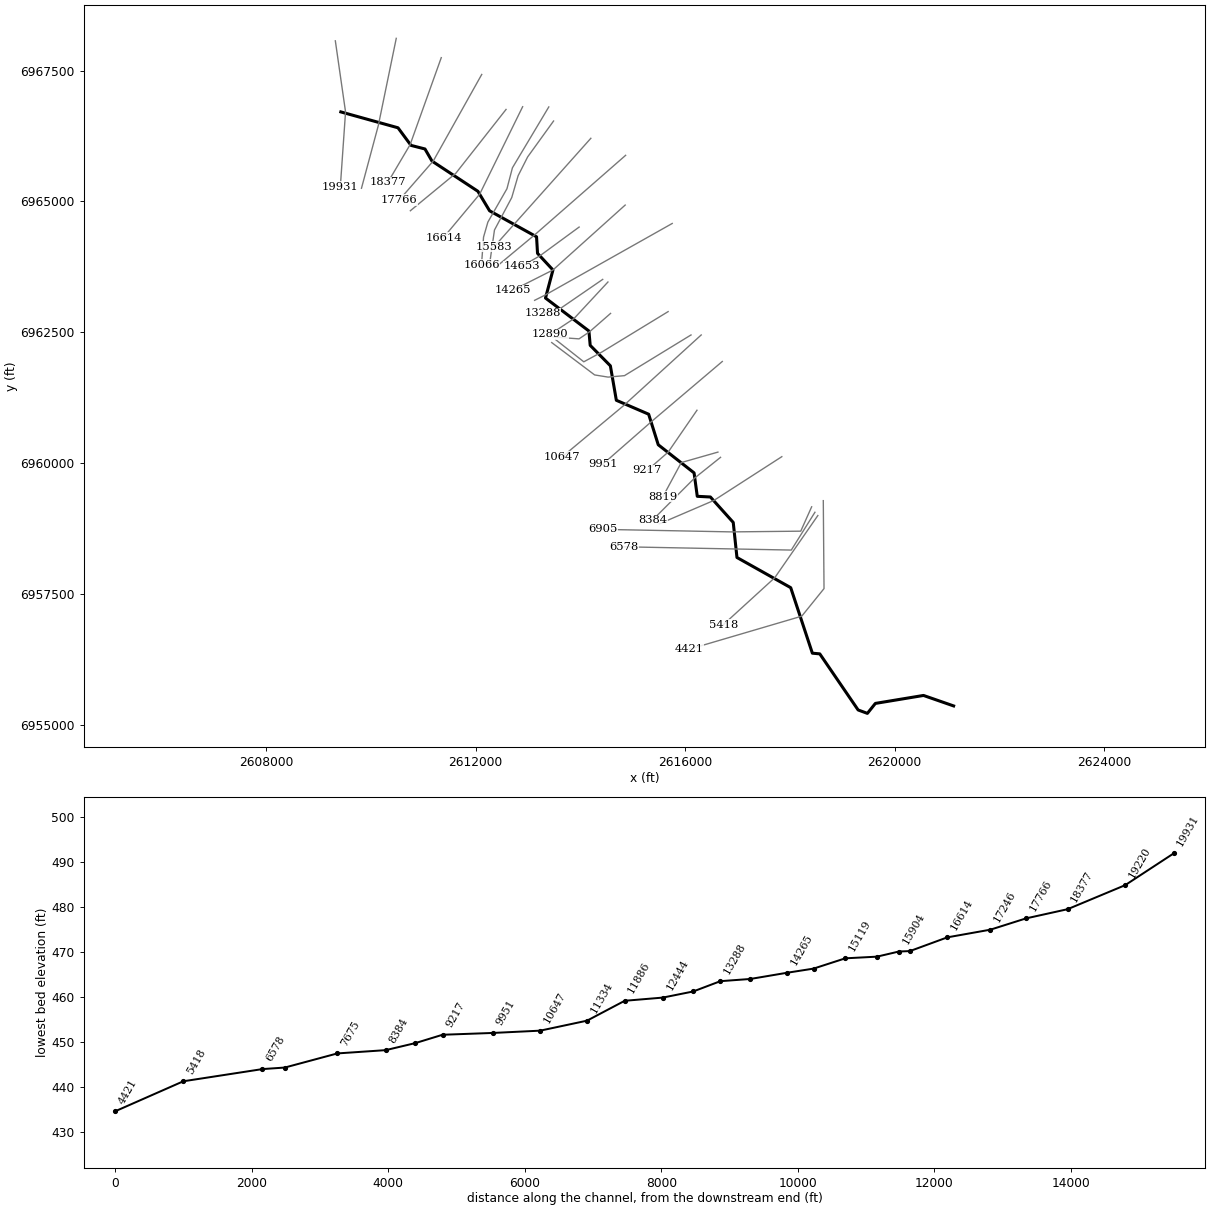
--- Brushy Creek Trib 5.prj (project) ---

Proj Title=Brushy Creek Trib 5 Base Level Engineering
Current Plan=p01
Default Exp/Contr=0.3,0.1
English Units
Geom File=g01
Flow File=f01
Plan File=p01
Y Axis Title=Elevation
X Axis Title(PF)=Main Channel Distance
X Axis Title(XS)=Station
BEGIN DESCRIPTION:
Brushy Creek Trib 5
END DESCRIPTION:
DSS Export Rating Curves= 0
DSS Export Rating Curve Sorted= 0
DSS Export Volume Flow Curves= 0
DXF OffsetX= 0
DXF OffsetY= 0
DXF ScaleX= 1
DXF ScaleY= 10

--- Brushy Creek Trib 5.p01 (plan) ---

Plan Title=Multiple Run
Short Identifier=Multiple
Geom File=g01
Flow File=f01
Subcritical Flow
K Sum by GR= 0
Std Step Tol= 0.01
Critical Tol= 0.01
Num of Std Step Trials= 20
Max Error Tol= 0.3
Flow Tol Ratio= 0.001
Split Flow NTrial= 30
Split Flow Tol= 0.02
Split Flow Ratio= 0.02
Log Output Level= 0
Friction Slope Method= 1
Unsteady Friction Slope Method= 2
Unsteady Bridges Friction Slope Method= 1
Parabolic Critical Depth
Global Vel Dist=  1 , 1 , 1
Global Log Level= 0
CheckData=True
Encroach Param= -1, 0, 0, 0
BEGIN DESCRIPTION:
Multiple Run
END DESCRIPTION:

--- Brushy Creek Trib 5.f01 (steady flow) ---

Flow Title=Multiple
Number of Profiles=7
Profile Names=10-year,25-year,50-year,1pct_min,100-year,1pct_plu,500-year
River Rch & RM= Brushy Creek Tri,Reach-1,19931
     509     677     812     484     966    1927    1364
River Rch & RM= Brushy Creek Tri,Reach-1,18377
     715     968    1175     708    1412    2818    2037
River Rch & RM= Brushy Creek Tri,Reach-1,15904
     844    1150    1401     846    1688    3367    2449
River Rch & RM= Brushy Creek Tri,Reach-1,10647
    1437    2010    2491    1527    3046    6078    4557
River Rch & RM= Brushy Creek Tri,Reach-1,5418
    1860    2636    3294    2034    4058    8096    6163
Boundary for River Rch & Prof#=Brushy Creek Tri,Reach-1,1
Up Type=0
Dn Type=3
Dn Slope=0.005
Boundary for River Rch & Prof#=Brushy Creek Tri,Reach-1,2
Up Type=0
Dn Type=3
Dn Slope=0.005
Boundary for River Rch & Prof#=Brushy Creek Tri,Reach-1,3
Up Type=0
Dn Type=3
Dn Slope=0.005
Boundary for River Rch & Prof#=Brushy Creek Tri,Reach-1,4
Up Type=0
Dn Type=3
Dn Slope=0.005
Boundary for River Rch & Prof#=Brushy Creek Tri,Reach-1,5
Up Type=0
Dn Type=3
Dn Slope=0.005
Boundary for River Rch & Prof#=Brushy Creek Tri,Reach-1,6
Up Type=0
Dn Type=3
Dn Slope=0.005
Boundary for River Rch & Prof#=Brushy Creek Tri,Reach-1,7
Up Type=0
Dn Type=3
Dn Slope=0.005

--- Brushy Creek Trib 5.g01 (geometry) ---

Geom Title=Existing Conditions
Program Version=4.10

River Reach=Brushy Creek Tri,Reach-1
Reach XY= 30
        2609426.        6966711.      2610517.56      6966407.59
      2610765.83      6966071.33      2611032.38        6966003.
      2611166.29      6965771.75      2612042.82      6965194.54
      2612266.23      6964821.53      2613162.83      6964324.72
      2613181.53      6964008.58      2613476.13      6963690.74
      2613333.67      6963154.48      2614162.77      6962524.73
      2614186.98      6962250.63      2614572.53       6961859.5
       2614686.4       6961200.9       2615303.2      6960934.97
      2615486.47      6960351.18      2616170.61      6959813.69
      2616231.41      6959366.17      2616482.19      6959353.19
      2616918.19      6958867.19      2616989.26      6958197.21
      2618015.48      6957620.79      2618428.92      6956368.92
      2618570.55      6956355.81      2619302.48      6955283.87
      2619479.43      6955218.79      2619631.71      6955409.11
       2620550.8      6955561.32        2621126.        6955361.

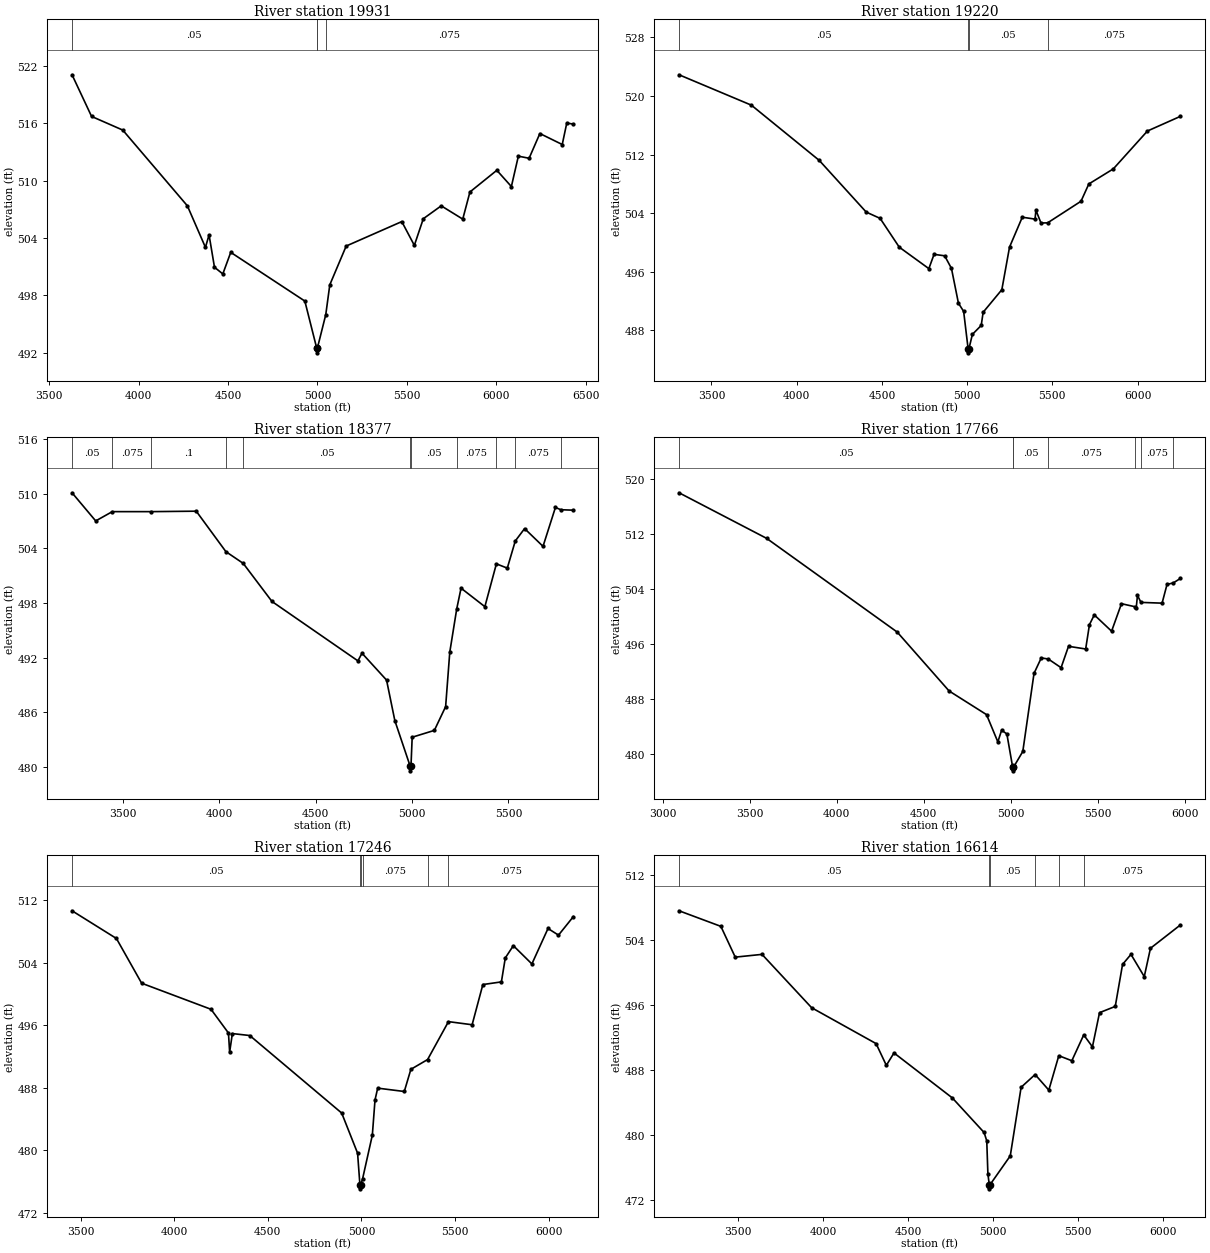
Type RM Length L Ch R = 1 ,19931   ,711,711,711
BEGIN DESCRIPTION:
Brushy Creek Trib 5 37.0
END DESCRIPTION:
XS GIS Cut Line= 3
      2609321.07      6968069.14      2609516.02      6966711.06
      2609416.67      6965284.31
#Sta/Elev= 30
    3628   521.1  3737.2  516.74  3911.5  515.31  4272.7  507.38  4373.7  503.03
  4393.9  504.34  4424.2  500.95  4470.8  500.25  4515.1  502.51  4929.3  497.41
  4995.5  492.49  4995.8  491.99  4999.5  492.49  5046.3  495.99  5068.8  499.11
  5160.4  503.17  5471.2  505.73  5541.4  503.24  5591.5  506.03  5691.7  507.38
    5812  505.99  5852.1  508.83  6002.5   511.1  6083.8   509.4  6122.8  512.58
  6182.9  512.36  6243.1  514.95  6368.1   513.8  6393.4  516.04  6430.2  515.94
#Mann= 4 ,-1 , 0
    3628     .05       0  4995.5     .03       0  4999.5     .05       0
  5046.3    .075       0
Bank Sta=4995.5,4999.5
XS Rating Curve= 0 ,0
Exp/Cntr=0.3,0.1

Type RM Length L Ch R = 1 ,19220   ,843,843,843
BEGIN DESCRIPTION:
Mapping XS f0bd4ef0
END DESCRIPTION:
XS GIS Cut Line= 3
      2610484.26      6968116.84      2610141.38      6966450.19
       2609820.2      6965252.25
#Sta/Elev= 30
  3309.6   522.9  3734.1  518.75  4132.3  511.21    4408  504.15  4489.6  503.29
  4601.9  499.36  4775.5  496.43  4806.1  498.38  4868.3  498.18  4908.2  496.46
  4949.1  491.71  4979.7  490.59  5006.2  485.43  5006.4  484.93  5010.2  485.43
    5031  487.45  5082.8  488.67  5094.1  490.47  5203.8  493.55    5249  499.37
  5323.8  503.45  5398.7  503.19  5403.8  504.41  5433.5  502.66  5472.4  502.68
  5668.4  505.63  5714.3  507.99  5858.1  510.05  6058.2  515.22  6251.4  517.22
#Mann= 4 ,-1 , 0
  3309.6     .05       0  5006.2     .05       0  5010.2     .05       0
  5472.4    .075       0
Bank Sta=5006.2,5010.2
XS Rating Curve= 0 ,0
Exp/Cntr=0.3,0.1

Type RM Length L Ch R = 1 ,18377   ,611,611,611
BEGIN DESCRIPTION:
Mapping XS 6752e93a
END DESCRIPTION:
XS GIS Cut Line= 3
      2611343.65      6967747.96      2610749.02      6966085.61
      2610323.92      6965365.53
#Sta/Elev= 30
  3235.3  510.11  3358.1  507.02  3444.2  508.04  3646.3  508.04  3879.9  508.09
  4033.7  503.65  4123.7  502.36  4272.9  498.18  4718.9  491.66  4740.2   492.5
  4867.6  489.55  4910.6   485.1  4990.3  480.09  4990.6  479.59  4994.3  480.09
  5000.6  483.28  5115.7  484.03  5174.2  486.64  5195.7  492.62  5231.8  497.37
  5254.2  499.64  5377.8  497.61  5437.6  502.31  5494.2  501.84  5535.7  504.82
    5584  506.18  5679.6  504.23    5744   508.5    5772  508.25    5837   508.2
#Mann= 11 ,-1 , 0
  3235.3     .05       0  3444.2    .075       0  3646.3      .1       0
  4033.7    .075       0  4123.7     .05       0  4990.3     .03       0
  4994.3     .05       0  5231.8    .075       0  5437.6     .05       0
  5535.7    .075       0    5772     .05       0
Bank Sta=4990.3,4994.3
XS Rating Curve= 0 ,0
Exp/Cntr=0.3,0.1

Type RM Length L Ch R = 1 ,17766   ,520,520,520
BEGIN DESCRIPTION:
Mapping XS d4c9568c
END DESCRIPTION:
XS GIS Cut Line= 3
      2612116.22      6967426.77      2611191.79      6965774.34
      2610540.86      6965027.94
#Sta/Elev= 30
  3092.1     518  3595.8  511.37  4347.1  497.73  4645.6  489.16  4860.9  485.72
    4926  481.75  4947.7  483.45  4977.9  482.91  5011.5  478.04  5011.8  477.54
  5015.5  478.04  5069.6  480.36  5134.1  491.72  5175.8  493.97  5216.3  493.81
  5289.8  492.55  5332.5  495.66  5431.2  495.27  5453.1  498.82  5480.9  500.23
  5580.3  497.86  5637.2  501.86  5713.1  501.43  5721.7  501.18  5729.3  503.07
  5749.2  502.05  5870.8  501.94  5899.2  504.66  5935.5  504.89  5975.9  505.53
#Mann= 7 ,-1 , 0
  3092.1     .05       0  5011.5    .035       0  5015.5     .05       0
  5216.3    .075       0  5713.1     .05       0  5749.2    .075       0
  5935.5     .05       0
Bank Sta=5011.5,5015.5
XS Rating Curve= 0 ,0
Exp/Cntr=0.3,0.1

Type RM Length L Ch R = 1 ,17246   ,632,632,632
BEGIN DESCRIPTION:
Mapping XS 5042b5b5
END DESCRIPTION:
XS GIS Cut Line= 3
      2612580.63      6966758.36      2611621.42      6965538.73
      2610753.35      6964822.57
#Sta/Elev= 30
  3454.3  510.66  3691.3  507.11    3826  501.38  4196.5  498.04  4289.6     495
  4295.9  492.55  4310.4  494.93  4403.4  494.68  4894.2  484.75  4979.1  479.61
  4991.6  475.54  4991.8  475.04  4995.6  475.54  5005.5  476.29  5057.9  481.92
  5072.2  486.43  5086.5  487.94  5228.5  487.51  5263.7  490.35  5352.9   491.6
  5464.4  496.46  5590.8  496.06  5648.1  501.21  5747.1  501.55  5767.9  504.62
  5810.9  506.19  5909.9  503.85    5996  508.39    6052  507.54  6131.3  509.91
#Mann= 6 ,-1 , 0
  3454.3     .05       0  4991.6    .035       0  4995.6     .05       0
  5005.5    .075       0  5352.9     .05       0  5464.4    .075       0
Bank Sta=4991.6,4995.6
XS Rating Curve= 0 ,0
Exp/Cntr=0.3,0.1

Type RM Length L Ch R = 1 ,16614   ,548,548,548
BEGIN DESCRIPTION:
Mapping XS afebeb06
END DESCRIPTION:
XS GIS Cut Line= 3
      2612897.47      6966810.46      2612077.15      6965139.43
      2611382.69      6964306.08
#Sta/Elev= 30
  3154.4  507.58  3400.2  505.66  3484.6  501.87    3642  502.21  3933.6  495.64
  4312.4  491.22  4372.7  488.54  4417.7  490.07  4760.5  484.53  4947.3  480.27
  4962.9  479.24  4969.6  475.16  4977.8  473.83  4978.1  473.33  4981.8  473.83
  5101.1  477.39  5164.8  485.84  5247.1  487.41  5327.6  485.49  5386.3  489.73
  5462.9  489.11  5532.8  492.29    5584  490.82  5625.7  495.03  5718.1   495.8
    5761  500.97  5810.5  502.21  5888.6  499.47    5925  502.96  6100.7  505.83
#Mann= 6 ,-1 , 0
  3154.4     .05       0  4977.8    .035       0  4981.8     .05       0
  5247.1    .075       0  5386.3     .05       0  5532.8    .075       0
Bank Sta=4977.8,4981.8
XS Rating Curve= 0 ,0
Exp/Cntr=0.3,0.1

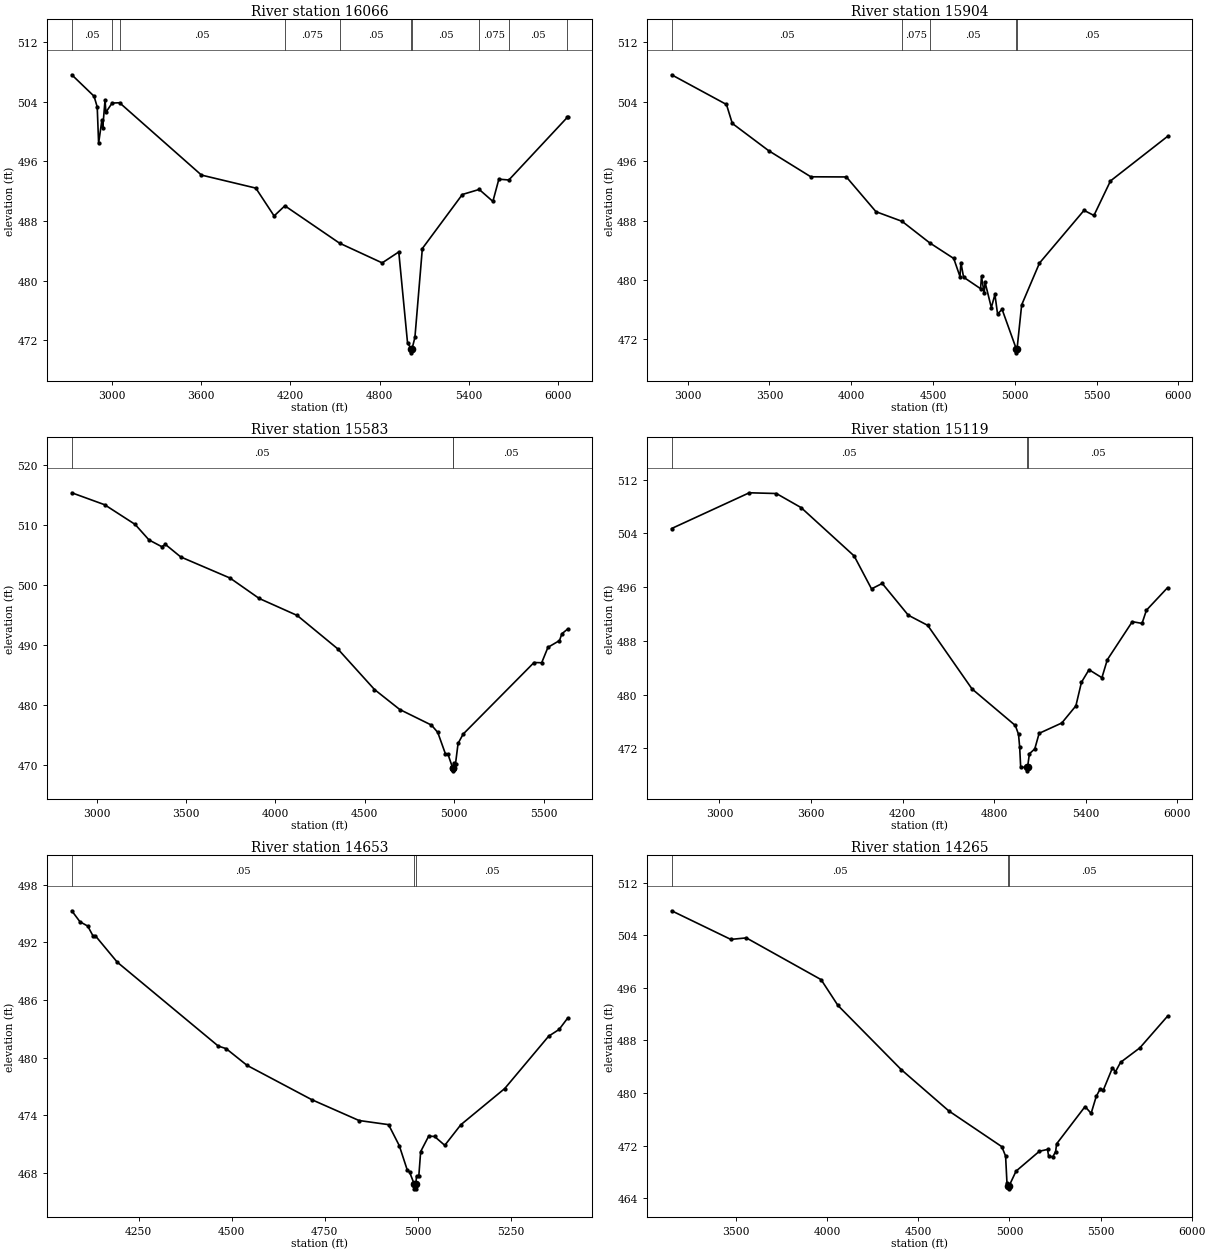
Type RM Length L Ch R = 1 ,16066   ,162,162,162
BEGIN DESCRIPTION:
Mapping XS 24d29fa0
END DESCRIPTION:
XS GIS Cut Line= 6
      2613396.61      6966806.13      2612702.15       6965642.9
      2612597.98       6965243.6       2612233.4      6964605.57
      2612150.93      6964319.12      2612111.87      6963789.59
#Sta/Elev= 30
  2729.7  507.65  2879.4  504.77  2900.8  503.33  2910.2  498.44    2932  501.53
  2937.8  500.46  2953.4  504.26  2959.2  502.61  3001.1  503.85  3051.2  503.89
  3601.7  494.17  3967.2  492.42  4090.3  488.68  4162.7  490.04  4530.3  485.02
  4817.1  482.37  4928.6  483.84  4987.5  471.63  5013.4  470.78  5013.6  470.28
  5017.4  470.78  5037.2  472.36  5087.1   484.3    5356  491.56  5469.5  492.24
  5561.5  490.63  5601.6  493.62  5668.8  493.51    6062  501.93  6064.3  501.93
#Mann= 10 ,-1 , 0
  2729.7     .05       0  3001.1    .075       0  3051.2     .05       0
  4162.7    .075       0  4530.3     .05       0  5013.4    .035       0
  5017.4     .05       0  5469.5    .075       0  5668.8     .05       0
    6062    .075       0
Bank Sta=5013.4,5017.4
XS Rating Curve= 0 ,0
Exp/Cntr=0.3,0.1

Type RM Length L Ch R = 1 ,15904   ,321,321,321
BEGIN DESCRIPTION:
Mapping XS bf3e1ef7
END DESCRIPTION:
XS GIS Cut Line= 6
      2613487.76      6966537.03      2612992.95      6965851.23
      2612810.66      6965490.99      2612689.13      6965074.32
      2612359.27      6964453.66      2612268.15      6963815.85
#Sta/Elev= 30
    2902  507.63  3237.2  503.63  3272.8  501.08  3494.9  497.41  3752.8  493.89
    3970  493.87    4151  489.19  4310.6  487.89  4478.9     485  4626.3  482.89
  4664.5  480.45  4670.2  482.33  4686.4  480.37  4790.3  478.82    4796   480.5
  4812.2  478.19  4817.9  479.68  4856.1  476.27    4878  478.04  4894.2  475.41
  4921.8  476.04  5009.1  470.68  5009.4  470.18  5013.2  470.68  5041.5  476.64
  5150.4  482.27  5422.7  489.37  5483.2  488.68  5584.2  493.33  5932.9  499.33
#Mann= 5 ,-1 , 0
    2902     .05       0  4310.6    .075       0  4478.9     .05       0
  5009.1    .035       0  5013.2     .05       0
Bank Sta=5009.1,5013.2
XS Rating Curve= 0 ,0
Exp/Cntr=0.3,0.1

Type RM Length L Ch R = 1 ,15583   ,464,464,464
BEGIN DESCRIPTION:
Brushy Creek Trib 5 28.0
END DESCRIPTION:
XS GIS Cut Line= 3
      2614199.57      6966207.17        2612776.        6964611.
      2612354.94      6964136.84
#Sta/Elev= 30
  2861.5  515.37  3045.2  513.38  3215.7   510.1  3293.4  507.51  3364.5  506.39
  3385.4  506.76  3470.7  504.68  3746.6  501.16  3909.6  497.76    4122  494.93
  4348.6  489.37  4554.2  482.59  4695.5  479.26  4872.8  476.66  4907.9  475.45
  4950.5   471.9  4964.7  471.84  4991.1  469.54  4991.4  469.04  4995.2  469.54
  4996.9  470.27  5007.4  470.24  5021.6  473.61    5050  475.16  5446.4  487.09
  5489.1  487.05  5524.2  489.62  5588.6  490.74  5602.1  491.88  5634.4  492.67
#Mann= 3 ,-1 , 0
  2861.5     .05       0  4991.1    .035       0  4995.2     .05       0
Bank Sta=4991.1,4995.2
XS Rating Curve= 0 ,0
Exp/Cntr=0.3,0.1

Type RM Length L Ch R = 1 ,15119   ,466,466,466
BEGIN DESCRIPTION:
Brushy Creek Trib 5 27.0
END DESCRIPTION:
XS GIS Cut Line= 3
      2614863.59       6965881.6        2613126.        6964361.
      2612402.69      6963759.24
#Sta/Elev= 30
  2686.6  504.73  3195.6  510.05  3373.1  509.94  3535.4  507.84  3882.8  500.65
  3996.7  495.75  4066.9  496.56  4237.7  491.83  4364.9  490.32  4655.3  480.86
  4939.1  475.42    4960  474.11  4967.6  472.21  4974.2  469.22  5014.9  469.17
  5015.3  468.67  5019.2  469.17  5031.4  471.21  5066.5  471.93  5095.2  474.25
  5243.6  475.79    5336  478.34  5372.5  481.85    5422  483.72  5506.6  482.53
  5541.9   485.2  5705.8  490.87  5769.6  490.61  5798.2  492.57  5936.5  495.92
#Mann= 3 ,-1 , 0
  2686.6     .05       0  5014.9    .035       0  5019.2     .05       0
Bank Sta=5014.9,5019.2
XS Rating Curve= 0 ,0
Exp/Cntr=0.3,0.1

Type RM Length L Ch R = 1 ,14653   ,388,388,388
BEGIN DESCRIPTION:
Brushy Creek Trib 5 26.0
END DESCRIPTION:
XS GIS Cut Line= 3
      2613976.02      6964511.01        2613226.        6963961.
      2612875.99      6963760.99
#Sta/Elev= 30
  4069.9  495.27  4091.9  494.13  4112.8  493.68  4127.4  492.63  4133.6  492.66
  4192.2  489.93  4463.9  481.21  4484.8  480.95  4541.1  479.21  4714.8  475.65
  4842.1  473.48  4921.6  473.05  4950.4  470.87  4971.8  468.34    4978  468.13
  4990.5  466.88  4990.8  466.38  4994.4  466.38  4994.8  466.88  4996.9   467.7
  5002.9   467.7  5007.9  470.25  5029.5  471.86  5045.3  471.82  5072.7   470.9
  5115.9  473.04  5233.9   476.8    5352  482.24  5380.1  482.94  5403.1  484.12
#Mann= 3 ,-1 , 0
  4069.9     .05       0  4990.5     .03       0  4994.8     .05       0
Bank Sta=4990.5,4994.8
XS Rating Curve= 0 ,0
Exp/Cntr=0.3,0.1

Type RM Length L Ch R = 1 ,14265   ,538,538,538
BEGIN DESCRIPTION:
Brushy Creek Trib 5 25.0
END DESCRIPTION:
XS GIS Cut Line= 3
      2614854.92      6964931.09      2613476.13      6963690.74
      2612702.15      6963299.15
#Sta/Elev= 30
  3145.4  507.71  3470.3  503.36  3555.5  503.59  3965.8  497.25  4058.5  493.32
  4405.3  483.59  4666.9   477.3  4957.7  471.87  4978.6  470.44  4986.1  466.39
  4994.5  465.96  4994.9  465.46  4998.9  465.96    5036  468.15  5164.1  471.17
  5208.7  471.45  5214.3  470.52  5236.6  470.27  5253.2  471.12  5258.8   472.3
  5414.8  477.96  5448.2  476.93  5476.1   479.5  5498.3  480.66    5515  480.46
  5565.2  483.84  5581.9  483.26  5609.7  484.68  5715.6  486.88  5867.4  491.69
#Mann= 3 ,-1 , 0
  3145.4     .05       0  4994.5    .035       0  4998.9     .05       0
Bank Sta=4994.5,4998.9
XS Rating Curve= 0 ,0
Exp/Cntr=0.3,0.1

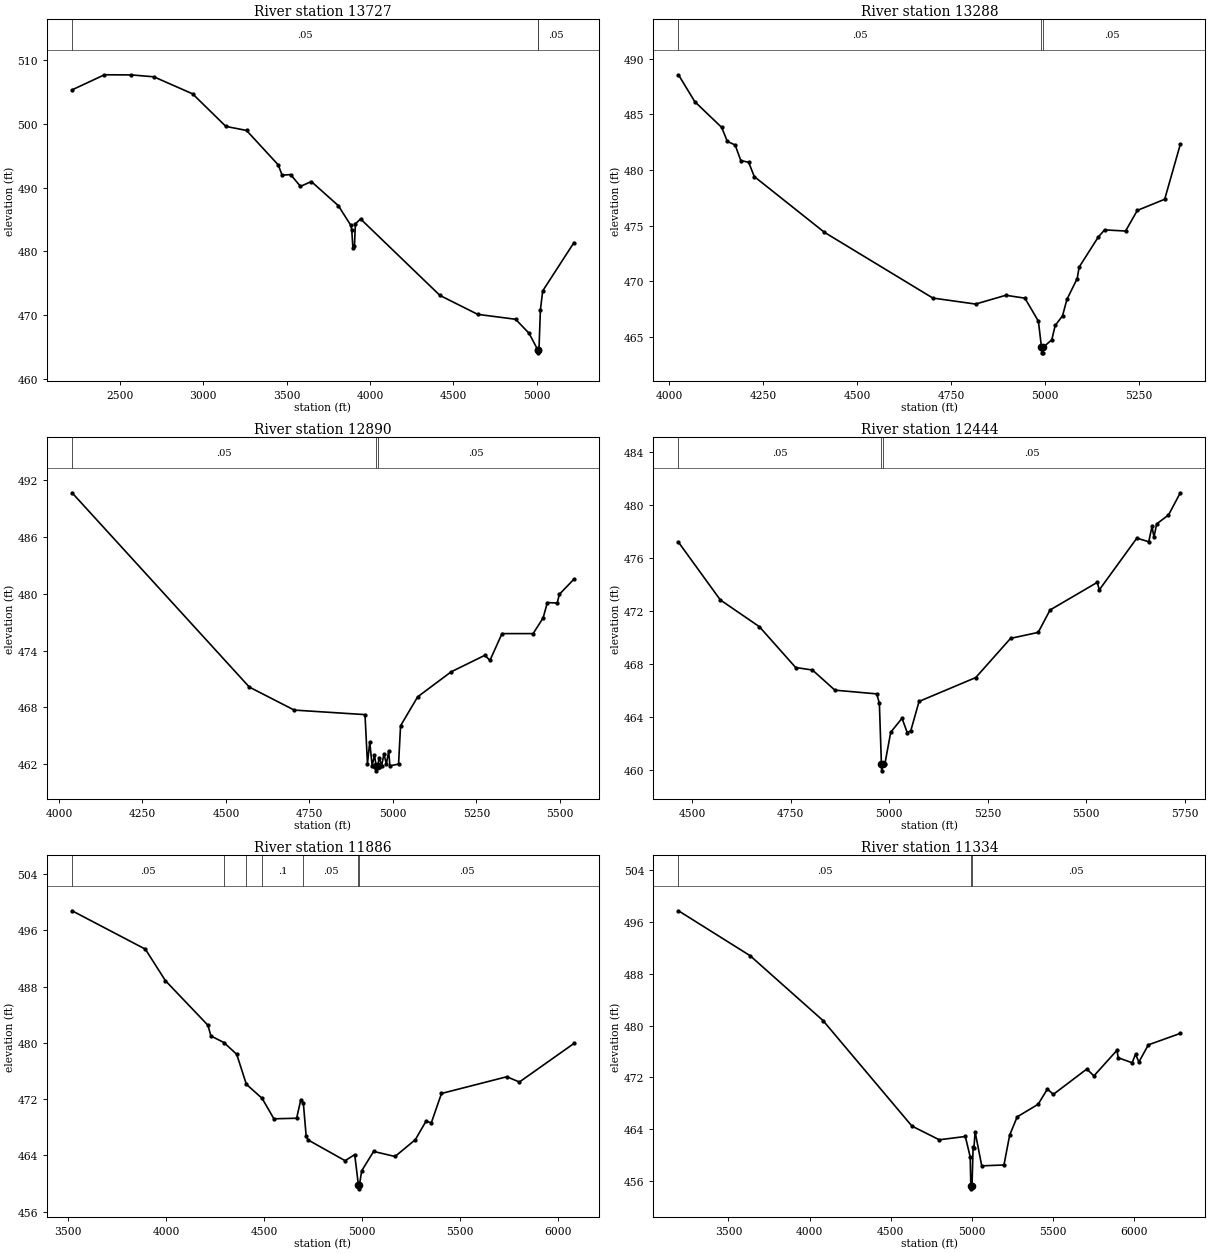
Type RM Length L Ch R = 1 ,13727   ,439,439,439
BEGIN DESCRIPTION:
Brushy Creek Trib 5 24.0
END DESCRIPTION:
XS GIS Cut Line= 3
      2615753.39      6964579.55        2613326.        6963211.
        2613126.        6963111.
#Sta/Elev= 30
  2212.9  505.36  2407.1  507.73  2568.9  507.71  2703.3  507.41  2935.8  504.74
  3135.2  499.63  3259.4  498.99  3449.7  493.58  3472.7  491.97  3523.8  492.06
    3583  490.21    3648  490.97  3809.8  487.19    3885  484.09  3890.7  483.29
  3897.4  480.55  3906.7  480.87  3912.4  484.33  3943.4   485.1  4419.5  473.09
  4646.3  470.12  4873.2  469.35    4954  467.15  5005.6  464.58  5006.1  464.08
  5010.1  464.58  5013.5  464.62  5021.9  470.77  5035.8   473.8  5223.1  481.38
#Mann= 3 ,-1 , 0
  2212.9     .05       0  5005.6    .035       0  5010.1     .05       0
Bank Sta=5005.6,5010.1
XS Rating Curve= 0 ,0
Exp/Cntr=0.3,0.1

Type RM Length L Ch R = 1 ,13288   ,398,398,398
BEGIN DESCRIPTION:
Brushy Creek Trib 5 23.0
END DESCRIPTION:
XS GIS Cut Line= 3
      2614425.98      6963510.99        2613626.        6962961.
      2613276.01        6962861.
#Sta/Elev= 30
  4024.6  488.56  4067.9  486.15  4139.6  483.83  4154.5  482.58  4175.4  482.25
  4190.3  480.86  4211.3   480.7  4226.2  479.42  4412.9  474.41  4701.1  468.51
  4814.8  467.97  4895.3  468.76    4946   468.5  4981.9  466.43  4990.1  464.09
  4990.6  463.59  4994.2  463.59  4994.6  464.09  5017.5  464.76  5026.6  466.05
  5046.1  466.91  5057.8  468.39  5085.1  470.26  5090.3  471.29    5141  473.98
  5157.9  474.63  5213.8  474.53    5245  476.38  5317.8  477.38  5359.4  482.32
#Mann= 3 ,-1 , 0
  4024.6     .05       0  4990.1    .035       0  4994.6     .05       0
Bank Sta=4990.1,4994.6
XS Rating Curve= 0 ,0
Exp/Cntr=0.3,0.1

Type RM Length L Ch R = 1 ,12890   ,446,446,446
BEGIN DESCRIPTION:
Brushy Creek Trib 5 22.0
END DESCRIPTION:
XS GIS Cut Line= 3
      2614526.01      6963461.02        2613876.        6962761.
      2613419.68      6962458.05
#Sta/Elev= 30
  4039.1  490.68    4570  470.15  4704.4  467.72  4916.4  467.24  4923.8  462.06
  4930.6  464.33  4937.9  461.82  4944.8  462.98  4949.8   461.8  4950.3   461.3
  4954.4   461.8  4958.9   462.7  4966.3  461.86  4973.1  463.06  4980.5  462.03
  4987.3  463.39    4991  461.83  5016.9  462.01  5022.9  466.06  5074.1  469.12
  5174.4  471.76  5275.5  473.51  5290.6  472.97  5326.7   475.8  5419.9   475.8
  5449.9  477.46  5462.5  479.08    5492  479.03  5498.5  479.95  5542.1  481.55
#Mann= 3 ,-1 , 0
  4039.1     .05       0  4949.8    .035       0  4954.4     .05       0
Bank Sta=4949.8,4954.4
XS Rating Curve= 0 ,0
Exp/Cntr=0.3,0.1

Type RM Length L Ch R = 1 ,12444   ,558,558,558
BEGIN DESCRIPTION:
Brushy Creek Trib 5 21.0
END DESCRIPTION:
XS GIS Cut Line= 4
      2614576.01      6962861.01        2614176.        6962511.
      2613973.85      6962374.67      2613476.02        6962411.
#Sta/Elev= 30
  4464.6   477.2  4570.9  472.84  4670.1  470.82  4762.2  467.74  4804.9  467.55
  4861.8  466.03  4968.1  465.75  4974.8  465.04    4980  460.44  4980.5  459.94
  4984.7  460.44    4989  460.49  5003.6  462.85  5032.3  463.91  5045.6  462.82
  5054.6  462.97  5075.6  465.18  5219.5  466.98    5308  469.94  5378.2  470.39
  5408.2  472.08  5528.3  474.17  5533.3   473.6  5628.8  477.51  5658.9  477.23
  5667.2  478.39  5672.2  477.58    5679  478.58    5709  479.25  5739.1  480.93
#Mann= 3 ,-1 , 0
  4464.6     .05       0    4980     .04       0  4984.7     .05       0
Bank Sta=4980,4984.7
XS Rating Curve= 0 ,0
Exp/Cntr=0.3,0.1

Type RM Length L Ch R = 1 ,11886   ,552,552,552
BEGIN DESCRIPTION:
Brushy Creek Trib 5 20.0
END DESCRIPTION:
XS GIS Cut Line= 4
      2615675.28      6962895.53      2614412.53      6962124.57
        2614065.       6961936.3      2613525.97      6962361.03
#Sta/Elev= 30
  3520.5  498.77  3894.6  493.31  3996.8  488.83  4213.6   482.5  4229.1  480.97
  4295.6  480.03  4360.7  478.36  4409.9   474.1  4490.5  472.09  4550.4  469.19
  4666.5  469.27  4687.8  471.92  4700.8  471.41    4715  466.76  4724.6  466.19
  4913.9  463.23  4962.8   464.1  4981.9  459.73  4982.4  459.23  4986.6  459.73
  4998.6   461.8  5059.3  464.55  5168.6  463.83  5272.3  466.22  5325.9  468.81
  5354.1  468.64  5405.6  472.79  5739.1  475.17  5803.2  474.42  6081.5   479.9
#Mann= 7 ,-1 , 0
  3520.5     .05       0  4295.6      .1       0  4409.9     .05       0
  4490.5      .1       0  4700.8     .05       0  4981.9     .03       0
  4986.6     .05       0
Bank Sta=4981.9,4986.6
XS Rating Curve= 0 ,0
Exp/Cntr=0.3,0.1

Type RM Length L Ch R = 1 ,11334   ,687,687,687
BEGIN DESCRIPTION:
Mapping XS 098ac647
END DESCRIPTION:
XS GIS Cut Line= 5
      2616112.19      6962449.43      2614841.34      6961671.65
      2614528.84      6961643.87      2614271.89      6961685.53
      2613452.44      6962303.59
#Sta/Elev= 30
  3192.7  497.72  3633.7  490.79  4082.8  480.78  4630.2   464.5  4798.5  462.38
  4959.1  462.89  4989.2  459.73  4992.9  455.31  4993.5  454.81  4997.7  455.31
  5000.4  455.31    5007  461.23  5012.1  461.14  5019.5   463.6  5060.1  458.36
    5197  458.49  5232.3  463.11  5278.5  465.92  5407.5  467.86  5464.5  470.21
  5501.2  469.39  5707.3   473.3    5751  472.24  5892.6  476.18  5900.9  475.03
  5986.2  474.27  6007.1  475.57  6028.1  474.39  6086.2  477.03  6283.1   478.8
#Mann= 3 ,-1 , 0
  3192.7     .05       0  4992.9     .03       0  4997.7     .05       0
Bank Sta=4992.9,4997.7
XS Rating Curve= 0 ,0
Exp/Cntr=0.3,0.1

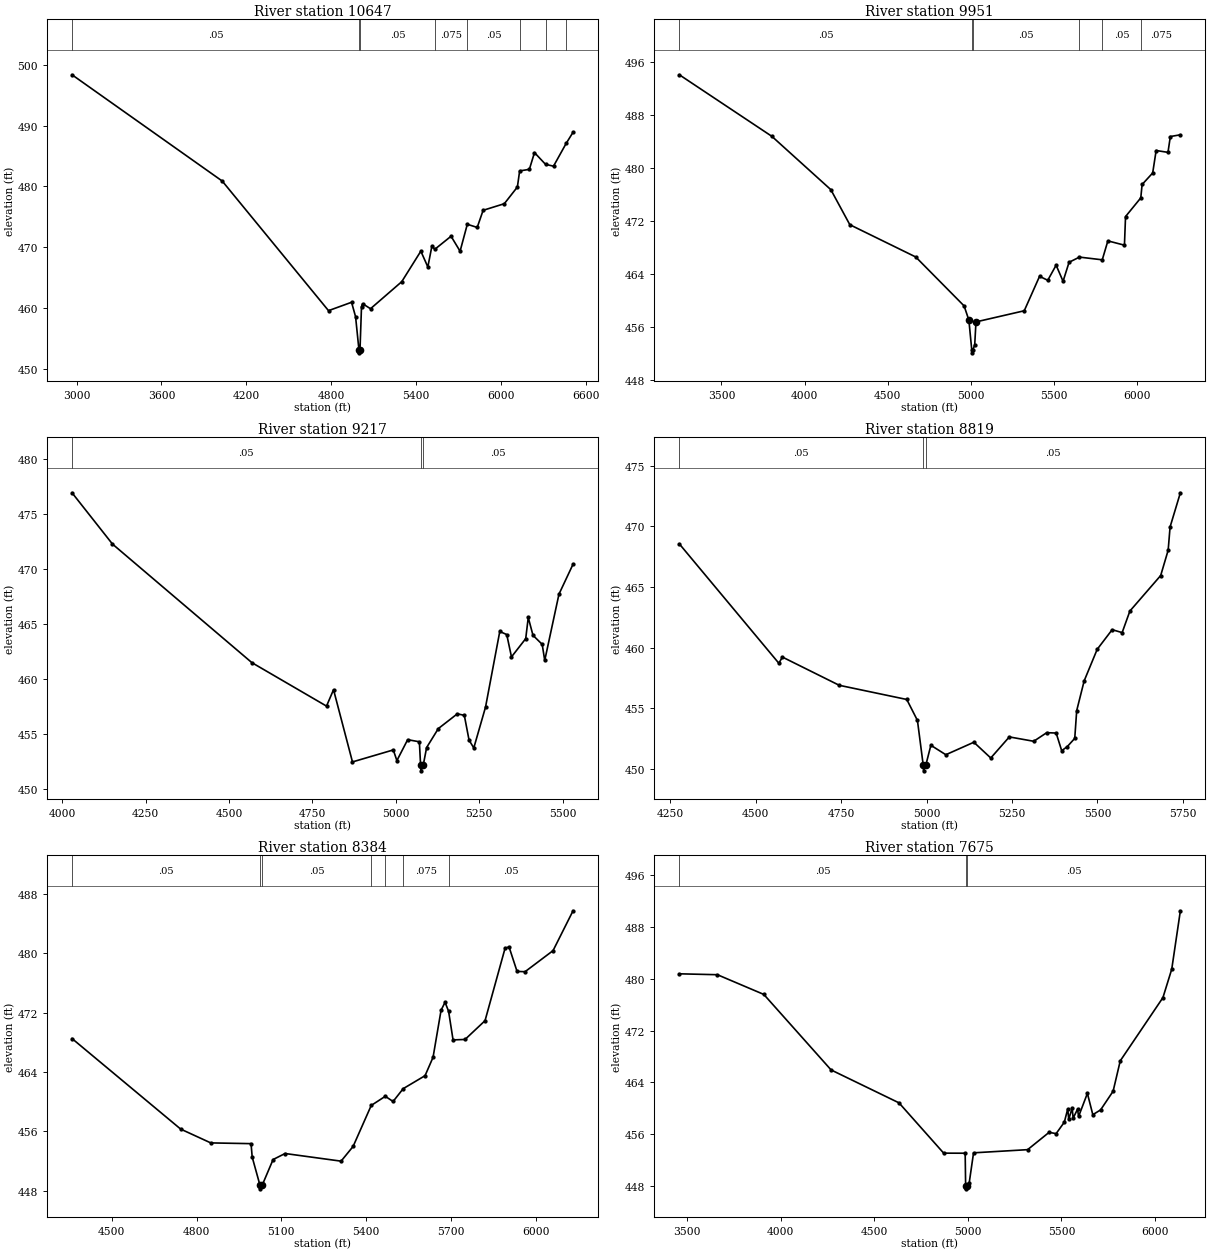
Type RM Length L Ch R = 1 ,10647   ,696,696,696
BEGIN DESCRIPTION:
Mapping XS 77473220
END DESCRIPTION:
XS GIS Cut Line= 3
      2616306.59       6962449.4       2614820.5      6961095.26
      2613646.86      6960116.06
#Sta/Elev= 30
  2968.4   498.4  4029.4  480.89  4780.1  459.54  4942.9  460.92  4971.3  458.54
  4995.1  453.09  4996.2  452.59  5002.5  453.09  5013.2  460.22    5021  460.68
  5076.9  459.86  5297.3  464.31  5432.3  469.34  5481.7  466.74  5510.4  470.17
  5531.1  469.65  5645.7   471.8  5709.5  469.33  5760.5  473.77  5830.5  473.25
  5872.2  476.07  6021.9  477.16  6114.3  479.91  6130.2  482.56  6198.9  482.82
    6235  485.58  6312.9  483.65  6369.4  483.34  6458.7  487.09  6507.4  488.93
#Mann= 8 ,-1 , 0
  2968.4     .05       0  4995.1     .03       0  5002.5     .05       0
  5531.1    .075       0  5760.5     .05       0  6130.2    .075       0
  6312.9     .05       0  6458.7    .075       0
Bank Sta=4995.1,5002.5
XS Rating Curve= 0 ,0
Exp/Cntr=0.3,0.1

Type RM Length L Ch R = 1 ,9951    ,734,734,734
BEGIN DESCRIPTION:
Mapping XS 750c3789
END DESCRIPTION:
XS GIS Cut Line= 3
       2616709.4      6961942.49      2615376.06      6960810.53
      2614424.66      6959977.19
#Sta/Elev= 30
  3246.6  494.05    3803  484.76  4157.8  476.71  4272.1  471.42  4668.5  466.55
  4959.6  459.16  4988.2  457.02  5005.3  452.58  5006.4  452.08  5012.9  452.58
  5023.3  453.28  5030.9  456.75  5321.3  458.43  5413.4  463.63  5462.7  463.03
    5513  465.31  5554.8  462.88  5590.9  465.75  5653.5  466.53  5790.6  466.12
  5824.3  468.98    5924  468.33  5930.6  472.65  6022.3  475.47  6030.3  477.49
  6093.9  479.23  6114.7  482.62  6185.9  482.34  6200.1  484.73  6260.4  484.99
#Mann= 6 ,-1 , 0
  3246.6     .05       0  5005.3     .05       0  5012.9     .05       0
  5653.5    .075       0  5790.6     .05       0  6022.3    .075       0
Bank Sta=4988.2,5030.9
XS Rating Curve= 0 ,0
Exp/Cntr=0.3,0.1

Type RM Length L Ch R = 1 ,9217    ,398,398,398
BEGIN DESCRIPTION:
Brushy Creek Trib 5 14.0
END DESCRIPTION:
XS GIS Cut Line= 3
      2616225.98      6961010.97        2615676.        6960211.
        2615276.        6959861.
#Sta/Elev= 30
  4029.1  476.94  4150.4  472.28  4568.3  461.51  4792.2  457.56  4813.2  459.05
    4870  452.49  4992.4  453.58  5003.2  452.61  5035.5  454.51  5070.6  454.32
  5074.3  452.18  5075.4  451.68  5082.1  452.18  5092.4   453.8  5127.5  455.52
  5184.5  456.86  5205.4  456.72  5219.6  454.47  5233.8  453.76    5269  457.47
  5311.7  464.34  5332.6  464.06  5346.8  462.03  5389.5  463.69  5397.1  465.61
  5411.3  463.99  5438.9  463.17  5446.5  461.71  5489.2  467.73  5531.4  470.45
#Mann= 3 ,-1 , 0
  4029.1     .05       0  5074.3     .03       0  5082.1     .05       0
Bank Sta=5074.3,5082.1
XS Rating Curve= 0 ,0
Exp/Cntr=0.3,0.1

Type RM Length L Ch R = 1 ,8819    ,435,435,435
BEGIN DESCRIPTION:
Brushy Creek Trib 5 13.0
END DESCRIPTION:
XS GIS Cut Line= 3
      2616626.01        6960211.        2615926.        6960011.
      2615575.98      6959360.97
#Sta/Elev= 30
  4276.3  468.56  4567.5  458.71  4577.9  459.22  4744.3  456.89  4941.9  455.72
  4973.1  453.99  4989.9  450.33  4991.1  449.83  4997.9  450.33  5012.4  451.94
  5056.2  451.16  5138.2  452.19  5187.7  450.89    5242  452.63  5313.4  452.27
  5351.5  452.98  5379.1  452.95  5395.3  451.49  5411.6  451.83  5433.5  452.51
  5439.2   454.8  5461.1  457.26  5499.2  459.86    5543  461.48  5572.2  461.24
  5594.9  463.02    5685  465.95  5706.9  468.04  5712.5  469.96  5742.6  472.78
#Mann= 3 ,-1 , 0
  4276.3     .05       0  4989.9     .03       0  4997.9     .05       0
Bank Sta=4989.9,4997.9
XS Rating Curve= 0 ,0
Exp/Cntr=0.3,0.1

Type RM Length L Ch R = 1 ,8384    ,709,709,709
BEGIN DESCRIPTION:
Brushy Creek Trib 5 12.0
END DESCRIPTION:
XS GIS Cut Line= 3
      2616675.99      6960110.99        2616176.        6959711.
      2615375.98      6958910.98
#Sta/Elev= 30
  4359.8  468.51    4744  456.31  4850.4  454.45  4992.9  454.35  4996.9  452.54
  5024.3  448.76  5025.5  448.26  5032.4  448.76  5070.8  452.21  5113.2  453.02
  5311.2  451.99  5353.7  453.97  5417.9   459.5  5467.6  460.73  5495.1  460.03
  5530.9  461.76  5608.2  463.51  5636.5  465.99  5664.8  472.33  5678.9   473.4
  5691.4  472.19  5707.2  468.33  5749.6  468.39  5820.3  470.92  5891.1  480.68
  5905.2  480.86  5933.5  477.56  5961.8  477.52  6060.8  480.36  6131.5  485.73
#Mann= 7 ,-1 , 0
  4359.8     .05       0  5024.3     .04       0  5032.4     .05       0
  5417.9    .075       0  5467.6     .05       0  5530.9    .075       0
  5691.4     .05       0
Bank Sta=5024.3,5032.4
XS Rating Curve= 0 ,0
Exp/Cntr=0.3,0.1

Type RM Length L Ch R = 1 ,7675    ,770,770,770
BEGIN DESCRIPTION:
Brushy Creek Trib 5 11.0
END DESCRIPTION:
XS GIS Cut Line= 3
      2617845.93      6960123.79      2616549.41      6959287.75
      2615505.66      6958839.07
#Sta/Elev= 30
  3457.3  480.79  3660.8  480.65    3909   477.6  4268.7  465.92  4631.7  460.83
  4870.6  453.05  4985.5  453.04    4988  448.03  4989.3  447.53  4996.3  448.03
  5006.8  448.39  5030.3   453.1  5319.4  453.59  5434.3  456.27  5471.8  456.07
  5515.8  457.85  5533.9   459.9  5539.3  458.29  5557.4  460.01  5562.9  458.47
  5586.4  459.85  5591.9  458.72    5639   462.3    5668     459  5709.6  459.74
  5776.5  462.63  5814.7  467.33  6042.9  477.11    6090  481.51  6136.1  490.54
#Mann= 3 ,-1 , 0
  3457.3     .05       0    4988     .04       0  4996.3     .05       0
Bank Sta=4988,4996.3
XS Rating Curve= 0 ,0
Exp/Cntr=0.3,0.1

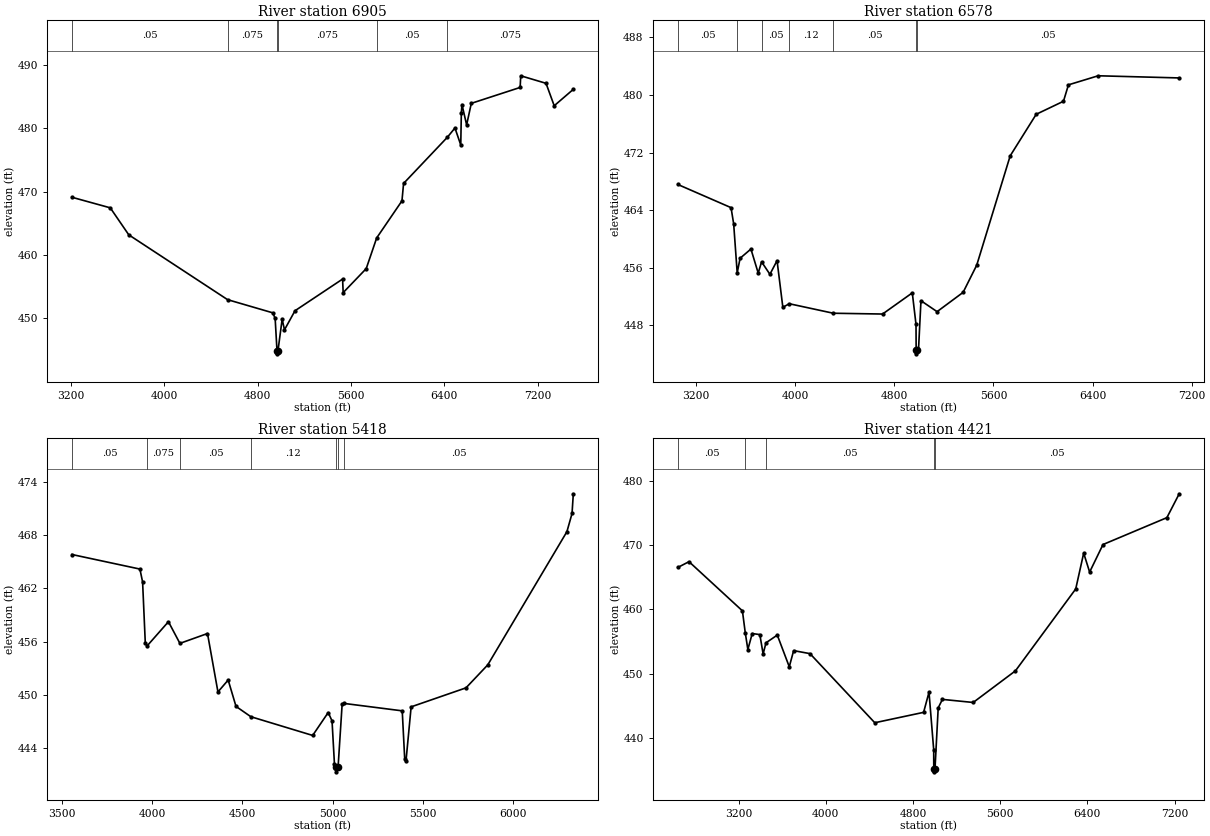
Type RM Length L Ch R = 1 ,6905    ,327,327,327
BEGIN DESCRIPTION:
Mapping XS a08de8af
END DESCRIPTION:
XS GIS Cut Line= 4
       2618415.4      6959165.46      2618207.07      6958700.19
      2616887.62       6958686.3       2614422.3      6958734.92
#Sta/Elev= 30
  3209.1   469.1  3537.6  467.43  3696.1  463.17  4542.5  452.94    4930  450.86
    4950  449.98  4965.8  444.89    4967  444.39  4974.3  444.89    5010  449.85
    5030  448.18    5120  451.19  5527.7  456.19  5532.7  454.05  5730.2  457.84
  5819.7  462.68  6036.3  468.53  6050.2  471.28  6424.8  478.56  6490.3  480.03
    6540  477.35    6545  482.43  6550.3  483.73  6590.3  480.52  6630.3  483.92
  7048.7  486.43  7053.7  488.27  7270.5  487.08  7340.5  483.54  7504.2  486.13
#Mann= 6 ,-1 , 0
  3209.1     .05       0  4542.5    .075       0  4965.8     .07       0
  4974.3    .075       0  5819.7     .05       0  6424.8    .075       0
Bank Sta=4965.8,4974.3
XS Rating Curve= 0 ,0
Exp/Cntr=0.3,0.1

Type RM Length L Ch R = 1 ,6578    ,1160,1160,1160
BEGIN DESCRIPTION:
Mapping XS 811b42f3
END DESCRIPTION:
XS GIS Cut Line= 4
      2618477.91      6959061.33      2618026.51      6958339.08
      2616950.12      6958359.91      2614832.03      6958401.58
#Sta/Elev= 30
  3052.5  467.58    3482  464.36  3503.2  462.11  3531.7   455.3  3555.1  457.33
  3642.5  458.61  3701.3  455.27  3728.5  456.83  3795.7   455.1  3853.4     457
  3900.1  450.52  3952.3  451.01  4307.4  449.69  4704.9  449.58  4944.9  452.52
  4974.9  448.14  4976.1  444.55  4977.3  444.05  4984.7  444.55  4994.9  444.57
  5014.9  451.43    5145  449.91    5355  452.59    5465  456.37  5735.1  471.56
  5945.1  477.33  6165.1  479.14  6205.2  481.42  6445.2  482.68  7099.3  482.38
#Mann= 7 ,-1 , 0
  3052.5     .05       0  3531.7    .075       0  3728.5     .05       0
  3952.3     .12       0  4307.4     .05       0  4976.1     .03       0
  4984.7     .05       0
Bank Sta=4976.1,4984.7
XS Rating Curve= 0 ,0
Exp/Cntr=0.3,0.1

Type RM Length L Ch R = 1 ,5418    ,997,997,997
BEGIN DESCRIPTION:
Brushy Creek Trib 5 6.0
END DESCRIPTION:
XS GIS Cut Line= 3
      2618533.45      6958998.79      2617710.94      6957810.85
        2616726.        6956911.
#Sta/Elev= 30
  3555.1  465.82  3931.9  464.18  3946.8  462.73  3961.7  455.88  3971.2  455.51
    4090  458.25  4153.6  455.81  4306.5  456.92  4364.4  450.34  4421.1  451.68
  4464.6  448.71  4546.8  447.55  4889.4  445.44  4975.5  448.02  4996.8  447.08
  5010.3  442.17  5018.9  441.84  5020.4  441.34  5030.2  441.84  5052.9  448.99
  5065.8  449.04  5385.9  448.21  5399.5  442.81  5406.9  442.61  5435.2  448.66
  5739.3   450.8    5860  453.39  6298.6  468.39    6327  470.44  6334.1  472.66
#Mann= 7 ,-1 , 0
  3555.1     .05       0  3971.2    .075       0  4153.6     .05       0
  4546.8     .12       0  5018.9     .07       0  5030.2     .12       0
  5065.8     .05       0
Bank Sta=5018.9,5030.2
XS Rating Curve= 0 ,0
Exp/Cntr=0.3,0.1

Type RM Length L Ch R = 1 ,4421    ,0,0,0
BEGIN DESCRIPTION:
Brushy Creek Trib 5 5.0
END DESCRIPTION:
XS GIS Cut Line= 4
      2618637.62       6959283.5      2618651.51      6957602.97
      2618226.43      6957076.18       2616075.1      6956443.24
#Sta/Elev= 30
  2642.5  466.53    2745  467.43    3235  459.77  3260.9  456.39    3285  453.74
    3325  456.23    3395  456.07    3425  453.05  3451.5  454.79    3555  455.99
    3665  451.05    3705  453.57    3855   453.1  4449.5  442.33  4897.3  443.95
  4946.9  447.09    4990  438.12  4990.7  435.18  4992.3  434.68    5002  435.18
  5031.3  444.65  5069.8  445.97  5352.3  445.49    5740  450.42    6293  463.18
    6366  468.76  6420.6  465.81  6543.2   470.1  7129.3  474.29  7242.5  478.01
#Mann= 5 ,-1 , 0
  2642.5     .05       0  3260.9    .075       0  3451.5     .05       0
  4990.7     .03       0    5002     .05       0
Bank Sta=4990.7,5002
XS Rating Curve= 0 ,0
Exp/Cntr=0.3,0.1

Chan Stop Cuts=-1
Use User Specified Reach Order=0
Composite Channel Slope=5