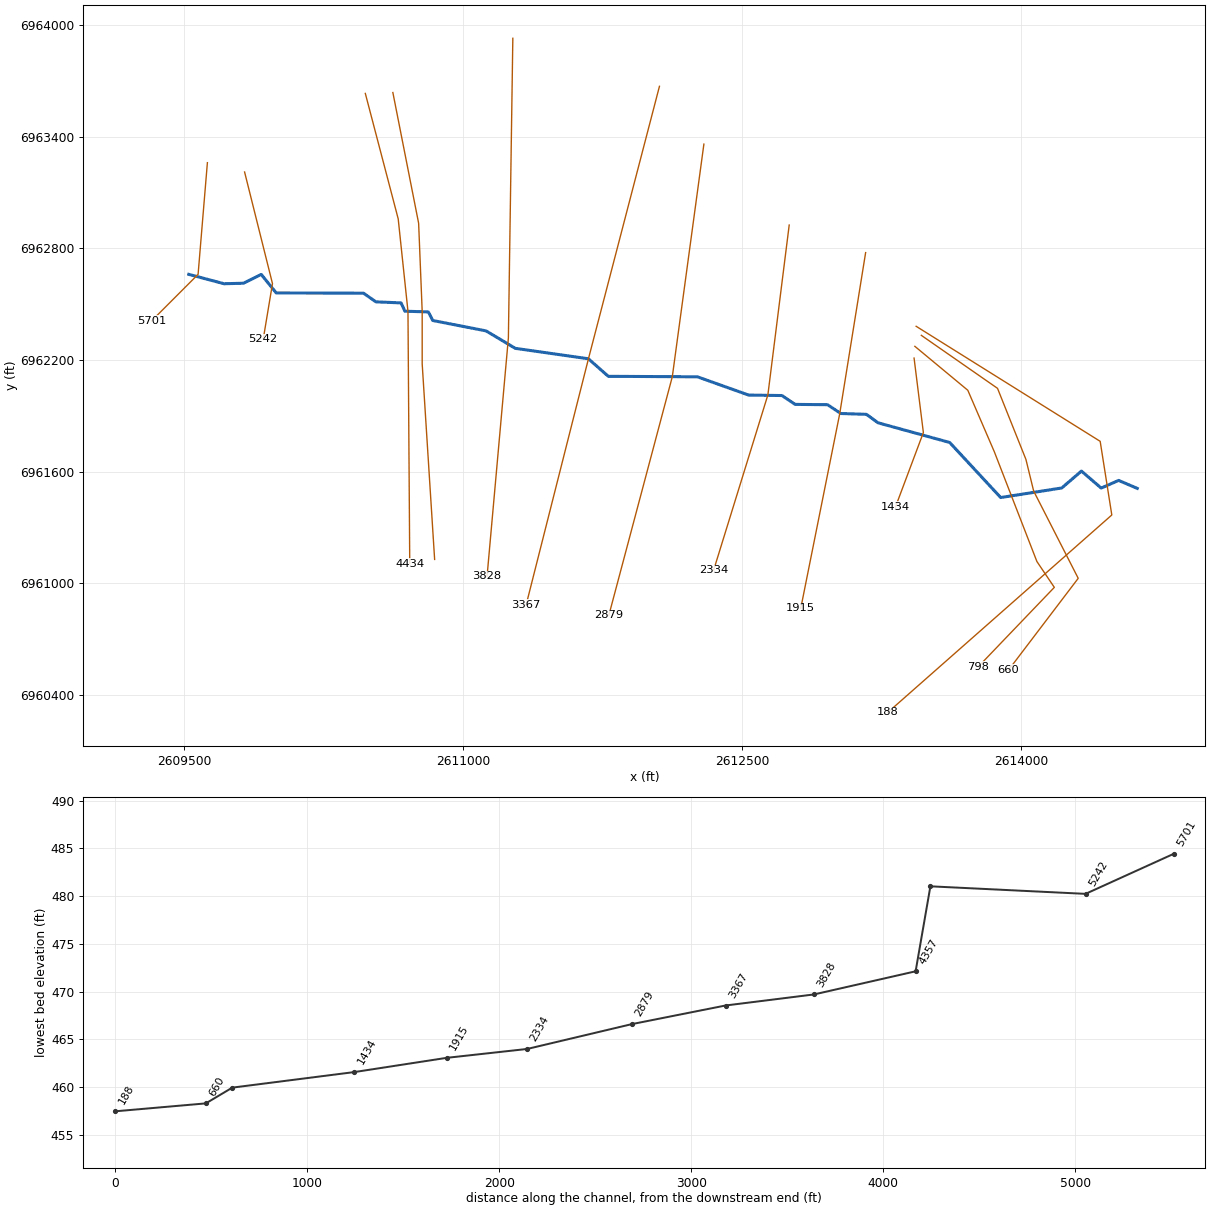
--- Brushy Creek Trib 5_1.prj (project) ---

Proj Title=Brushy Creek Trib 5_1 Base Level Engineering
Current Plan=p01
Default Exp/Contr=0.3,0.1
English Units
Geom File=g01
Flow File=f01
Plan File=p01
Y Axis Title=Elevation
X Axis Title(PF)=Main Channel Distance
X Axis Title(XS)=Station
BEGIN DESCRIPTION:
Brushy Creek Trib 5_1
END DESCRIPTION:
DSS Export Rating Curves= 0
DSS Export Rating Curve Sorted= 0
DSS Export Volume Flow Curves= 0
DXF OffsetX= 0
DXF OffsetY= 0
DXF ScaleX= 1
DXF ScaleY= 10

--- Brushy Creek Trib 5_1.p01 (plan) ---

Plan Title=Multiple Run
Short Identifier=Multiple
Geom File=g01
Flow File=f01
Subcritical Flow
K Sum by GR= 0
Std Step Tol= 0.01
Critical Tol= 0.01
Num of Std Step Trials= 20
Max Error Tol= 0.3
Flow Tol Ratio= 0.001
Split Flow NTrial= 30
Split Flow Tol= 0.02
Split Flow Ratio= 0.02
Log Output Level= 0
Friction Slope Method= 1
Unsteady Friction Slope Method= 2
Unsteady Bridges Friction Slope Method= 1
Parabolic Critical Depth
Global Vel Dist=  1 , 1 , 1
Global Log Level= 0
CheckData=True
Encroach Param= -1, 0, 0, 0
BEGIN DESCRIPTION:
Multiple Run
END DESCRIPTION:

--- Brushy Creek Trib 5_1.f01 (steady flow) ---

Flow Title=Multiple
Number of Profiles=7
Profile Names=10-year,25-year,50-year,1pct_min,100-year,1pct_plu,500-year
River Rch & RM= Brushy Creek Tri,Reach-1,5701
     621     837    1012     608    1213    2420    1740
River Rch & RM= Brushy Creek Tri,Reach-1,3828
     717     973    1182     712    1422    2836    2054
River Rch & RM= Brushy Creek Tri,Reach-1,1915
     738    1001    1217     733    1463    2919    2113
Boundary for River Rch & Prof#=Brushy Creek Tri,Reach-1,1
Up Type=0
Dn Type=3
Dn Slope=0.005
Boundary for River Rch & Prof#=Brushy Creek Tri,Reach-1,2
Up Type=0
Dn Type=3
Dn Slope=0.005
Boundary for River Rch & Prof#=Brushy Creek Tri,Reach-1,3
Up Type=0
Dn Type=3
Dn Slope=0.005
Boundary for River Rch & Prof#=Brushy Creek Tri,Reach-1,4
Up Type=0
Dn Type=3
Dn Slope=0.005
Boundary for River Rch & Prof#=Brushy Creek Tri,Reach-1,5
Up Type=0
Dn Type=3
Dn Slope=0.005
Boundary for River Rch & Prof#=Brushy Creek Tri,Reach-1,6
Up Type=0
Dn Type=3
Dn Slope=0.005
Boundary for River Rch & Prof#=Brushy Creek Tri,Reach-1,7
Up Type=0
Dn Type=3
Dn Slope=0.005

--- Brushy Creek Trib 5_1.g01 (geometry) ---

Geom Title=Existing Conditions
Program Version=4.10

River Reach=Brushy Creek Tri,Reach-1
Reach XY= 30
        2609526.        6962661.      2609715.83       6962610.5
      2609820.07      6962613.28      2609915.52      6962660.45
       2609996.2      6962561.06       2610465.5      6962559.78
      2610531.95      6962513.28      2610667.53      6962507.53
      2610687.98      6962462.98      2610814.02      6962459.02
      2610837.97      6962412.98      2611124.42      6962357.17
      2611281.93      6962263.25      2611674.53      6962207.45
      2611781.86      6962113.07      2612260.78      6962110.48
      2612536.51      6962012.22      2612715.49      6962009.78
      2612786.51      6961962.22      2612960.78      6961960.48
      2613031.94      6961913.27      2613170.06      6961908.73
      2613231.98      6961863.36      2613617.52      6961757.51
      2613891.84      6961461.65      2614220.14      6961513.09
        2614326.       6961603.9      2614432.05      6961512.67
      2614526.03      6961553.65        2614626.        6961511.

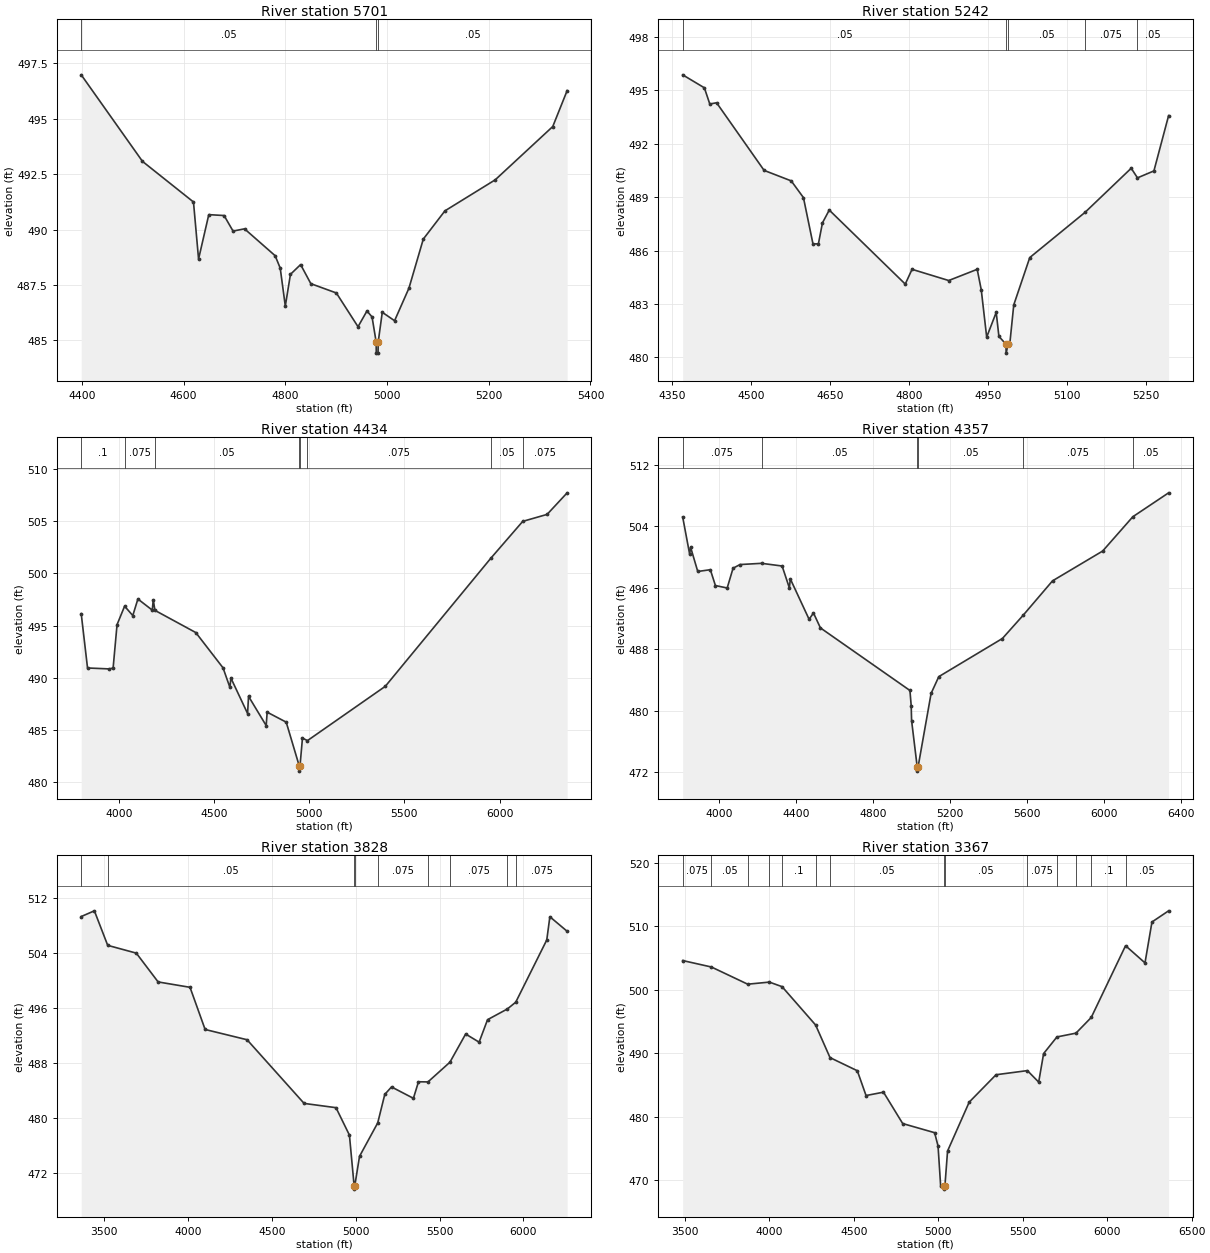
Type RM Length L Ch R = 1 ,5701    ,459,459,459
BEGIN DESCRIPTION:
Brushy Creek Trib 5_1 11.0
END DESCRIPTION:
XS GIS Cut Line= 3
        2609626.      6963261.05        2609576.        6962661.
      2609325.99      6962410.99
#Sta/Elev= 30
  4398.5  496.97    4519  493.07  4619.3  491.24  4629.3  488.67  4649.4  490.67
  4679.5  490.63  4697.1  489.93  4719.7  490.03  4779.9  488.82  4789.9  488.26
  4799.9  486.55    4810  487.98    4830  488.42  4850.1  487.56  4900.3  487.14
  4942.9  485.62  4960.5  486.33  4970.5  486.06  4978.6  484.93  4978.8  484.43
  4982.3  484.43  4982.6  484.93  4990.6  486.27  5014.8  485.89  5043.1  487.36
  5071.3  489.57  5113.8  490.84  5212.8  492.24  5325.9  494.64  5354.2  496.26
#Mann= 3 ,-1 , 0
  4398.5     .05       0  4978.6     .03       0  4982.6     .05       0
Bank Sta=4978.6,4982.6
XS Rating Curve= 0 ,0
Exp/Cntr=0.3,0.1

Type RM Length L Ch R = 1 ,5242    ,808,808,808
BEGIN DESCRIPTION:
Brushy Creek Trib 5_1 10.0
END DESCRIPTION:
XS GIS Cut Line= 3
        2609826.      6963210.99        2609976.        6962611.
        2609926.        6962311.
#Sta/Elev= 30
  4370.8  495.88    4412  495.15  4422.3  494.24  4435.2  494.31  4525.4  490.51
  4576.9  489.92  4600.1  488.98  4618.2  486.38  4628.5  486.38  4636.2  487.56
  4649.1  488.28  4793.4  484.12  4806.3  484.95  4875.9  484.32    4930  484.95
  4937.7   483.8    4948  481.14  4966.1  482.53  4971.2  481.18  4984.7  480.74
  4984.9  480.24  4988.7  480.74  4991.8  480.74  4999.4  482.95  5029.8  485.61
  5134.7  488.15  5222.4  490.63  5234.3  490.09  5265.5  490.48  5293.4  493.59
#Mann= 5 ,-1 , 0
  4370.8     .05       0  4984.7     .03       0  4988.7     .05       0
  5134.7    .075       0  5234.3     .05       0
Bank Sta=4984.7,4988.7
XS Rating Curve= 0 ,0
Exp/Cntr=0.3,0.1

Type RM Length L Ch R = 1 ,4434    ,77,77,77
BEGIN DESCRIPTION:
Mapping XS 43920baa
END DESCRIPTION:
XS GIS Cut Line= 4
      2610475.19      6963633.15        2610652.      6962959.37
      2610704.56       6962462.4      2610714.11      6961105.67
#Sta/Elev= 30
    3802  496.14  3835.2  490.93    3949  490.84  3969.6  490.92  3990.3  495.09
    4030  496.86    4073  495.96  4099.8  497.55  4175.4  496.48  4180.5  497.47
  4189.3  496.46  4403.9  494.33  4547.2  490.94  4583.3  489.06  4588.3  489.97
  4676.1  486.56  4681.1  488.21  4773.9   485.4  4778.9  486.69  4879.1  485.73
  4947.5  481.53  4947.7  481.03  4951.5  481.53  4964.5   484.2  4990.8  483.96
  5399.7  489.17  5953.5  501.45  6121.7     505  6249.8  505.67  6355.1  507.74
#Mann= 8 ,-1 , 0
    3802      .1       0    4030    .075       0  4189.3     .05       0
  4947.5     .07       0  4951.5     .05       0  4990.8    .075       0
  5953.5     .05       0  6121.7    .075       0
Bank Sta=4947.5,4951.5
XS Rating Curve= 0 ,0
Exp/Cntr=0.3,0.1

Type RM Length L Ch R = 1 ,4357    ,529,529,529
BEGIN DESCRIPTION:
Mapping XS 8bf67c17
END DESCRIPTION:
XS GIS Cut Line= 5
      2610623.33      6963637.89       2610761.9      6962935.48
      2610781.02       6962462.4      2610781.02      6962180.47
      2610847.92      6961129.15
#Sta/Elev= 30
  3809.6   505.2  3845.7  500.37  3850.8  501.25    3888   498.1  3953.4  498.33
  3979.7  496.27  4040.9  495.95  4071.4  498.52  4107.3     499  4219.3  499.16
  4326.3  498.81  4363.9  495.97    4369  497.13  4466.5  491.88  4489.3   492.7
  4525.3  490.76  4990.4  482.62    4997  480.63    4999  478.71  5028.4  472.63
  5028.7  472.13  5032.4  472.63  5100.4  482.24  5140.4  484.42  5470.8  489.38
  5578.5   492.4  5731.3  496.88  5991.9  500.76  6148.6  505.22  6334.4  508.33
#Mann= 6 ,-1 , 0
  3809.6    .075       0  4219.3     .05       0  5028.4     .05       0
  5032.4     .05       0  5578.5    .075       0  6148.6     .05       0
Bank Sta=5028.4,5032.4
XS Rating Curve= 0 ,0
Exp/Cntr=0.3,0.1

Type RM Length L Ch R = 1 ,3828    ,461,461,461
BEGIN DESCRIPTION:
Mapping XS 89f53b18
END DESCRIPTION:
XS GIS Cut Line= 3
      2611268.43      6963929.39      2611244.53      6962319.05
      2611129.85      6961038.39
#Sta/Elev= 30
  3364.4  509.27  3442.8   510.1  3522.3  505.09  3692.8  503.96  3822.8  499.78
  4012.9     499  4102.9  492.88  4352.9  491.39  4692.9  482.15    4883  481.53
    4963  477.55    4991  470.21  4991.3  469.71    4995  470.21  5023.2  474.47
  5131.6  479.32  5173.8  483.46  5213.9  484.54  5344.4  482.89  5374.6  485.29
  5431.2  485.27    5562  488.13  5655.7  492.22    5736  491.04  5786.2   494.3
  5903.9  495.85  5954.3  496.84  6139.2  505.87  6157.7  509.24  6260.7  507.13
#Mann= 9 ,-1 , 0
  3364.4    .075       0  3522.3     .05       0    4991    .035       0
    4995     .05       0  5131.6    .075       0  5431.2     .05       0
    5562    .075       0  5903.9     .05       0  5954.3    .075       0
Bank Sta=4991,4995
XS Rating Curve= 0 ,0
Exp/Cntr=0.3,0.1

Type RM Length L Ch R = 1 ,3367    ,488,488,488
BEGIN DESCRIPTION:
Brushy Creek Trib 5_1 6.0
END DESCRIPTION:
XS GIS Cut Line= 3
      2612056.88      6963671.33        2611676.        6962211.
       2611340.1      6960885.48
#Sta/Elev= 30
  3486.9   504.6  3657.1  503.58  3871.8  500.87  4000.2   501.2  4075.3  500.48
    4274  494.43  4359.2  489.29  4520.7  487.22  4572.4  483.31  4675.7  483.84
  4789.4  478.89  4978.4  477.45  4998.7  475.34    5014  469.09  5035.3  469.05
  5035.6  468.55  5039.3  469.05    5055  474.56  5183.1  482.27  5341.9  486.59
  5527.5  487.24  5594.4  485.43  5623.6  489.93  5702.4  492.55  5815.1  493.15
  5905.5  495.62  6108.7  506.94  6223.7  504.23    6265  510.68  6363.5  512.44
#Mann= 14 ,-1 , 0
  3486.9    .075       0  3657.1     .05       0  3871.8      .1       0
  4000.2    .075       0  4075.3      .1       0    4274    .075       0
  4359.2     .05       0  5035.3    .035       0  5039.3     .05       0
  5527.5    .075       0  5702.4      .1       0  5815.1    .075       0
  5905.5      .1       0  6108.7     .05       0
Bank Sta=5035.3,5039.3
XS Rating Curve= 0 ,0
Exp/Cntr=0.3,0.1

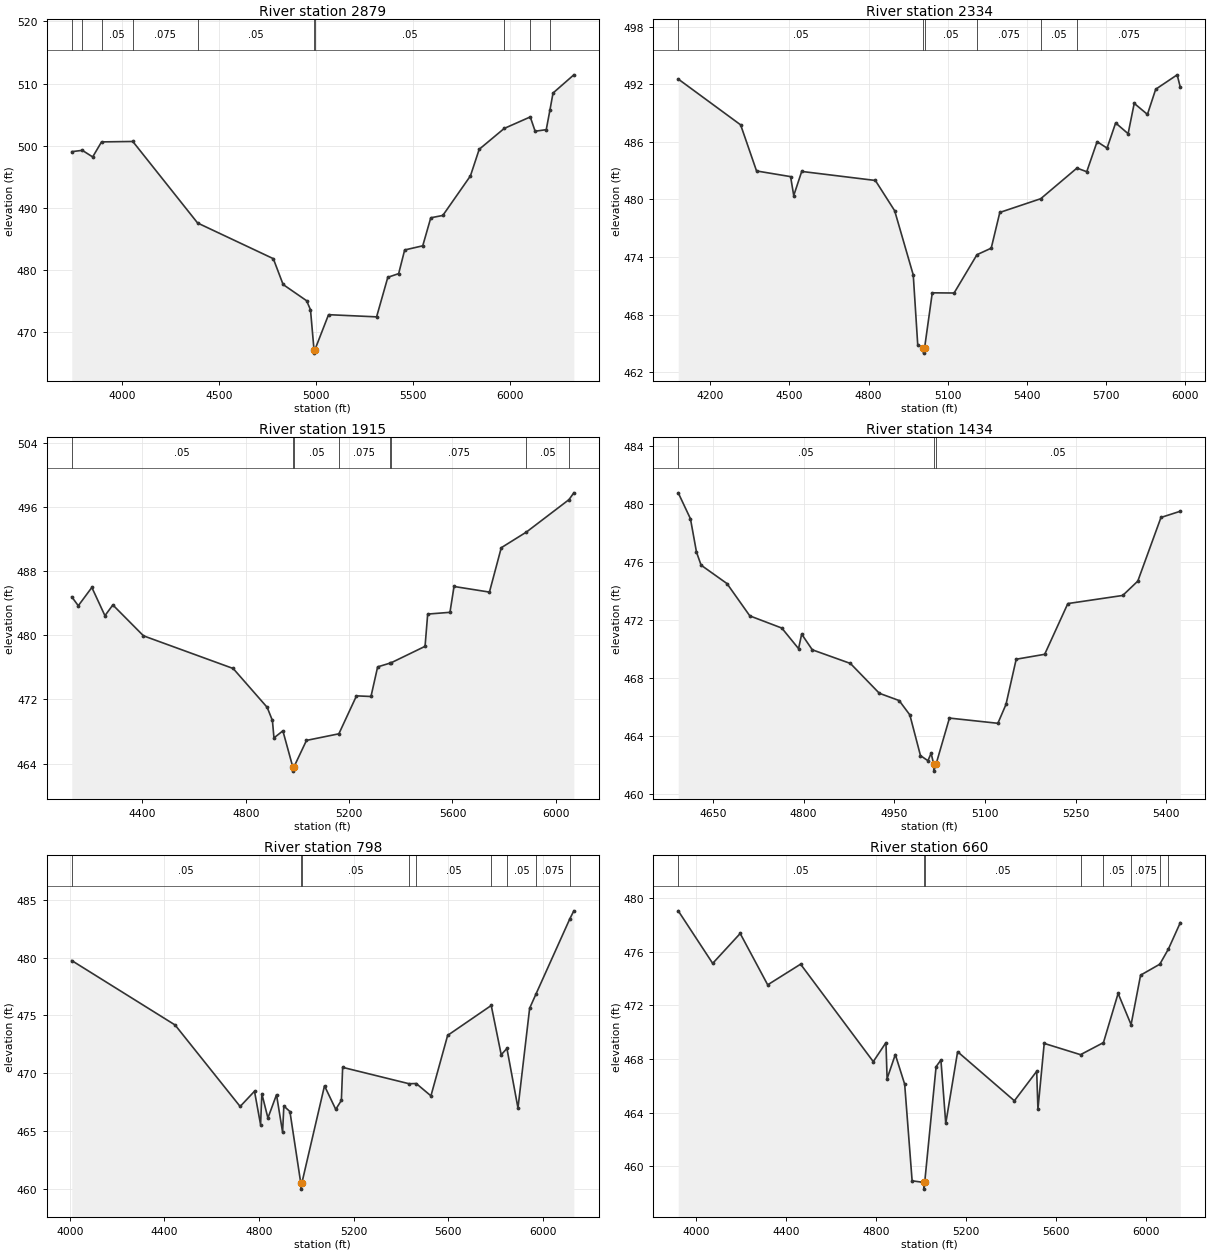
Type RM Length L Ch R = 1 ,2879    ,545,545,545
BEGIN DESCRIPTION:
Brushy Creek Trib 5_1 5.0
END DESCRIPTION:
XS GIS Cut Line= 3
      2612295.81      6963360.74        2612126.        6962111.
       2611784.5       6960828.1
#Sta/Elev= 30
  3738.8  499.04  3793.2  499.25  3846.6  498.19  3892.3  500.61  4053.5  500.68
  4387.7  487.55    4778  481.81  4828.5  477.65  4949.6  475.04  4969.7  473.58
  4987.9   467.1  4988.2   466.6  4991.9   467.1  5062.8  472.79  5310.5  472.44
  5368.4  478.81  5424.3   479.4  5455.3  483.21  5548.5  483.88  5589.9  488.39
    5652  488.77  5794.3  495.13  5839.6  499.42  5968.7  502.78  6102.9  504.63
    6128  502.33  6185.3  502.58  6204.8  505.82  6220.3  508.48  6327.6  511.41
#Mann= 10 ,-1 , 0
  3738.8      .1       0  3793.2    .075       0  3892.3     .05       0
  4053.5    .075       0  4387.7     .05       0  4987.9     .05       0
  4991.9     .05       0  5968.7    .075       0  6102.9     .05       0
  6204.8    .075       0
Bank Sta=4987.9,4991.9
XS Rating Curve= 0 ,0
Exp/Cntr=0.3,0.1

Type RM Length L Ch R = 1 ,2334    ,419,419,419
BEGIN DESCRIPTION:
Mapping XS 8ac36c39
END DESCRIPTION:
XS GIS Cut Line= 3
      2612754.55      6962925.93      2612639.87      6962013.22
      2612348.36       6961071.8
#Sta/Elev= 30
  4077.9  492.54  4314.7  487.77  4375.1  482.97  4504.3  482.38  4516.2  480.41
  4546.5  482.92    4826  481.98  4899.2  478.83  4969.8  472.14  4986.8  464.87
  5008.6   464.5  5008.8     464  5012.6   464.5    5042  470.28  5124.8  470.26
  5211.6  474.25  5265.7  474.93  5298.3  478.65  5453.6  480.08  5591.1  483.27
  5628.2  482.89  5667.5  486.02  5705.3  485.35  5737.9  487.97  5785.2  486.85
  5808.4  490.01  5858.5  488.86  5889.9  491.48  5971.4  492.98  5983.3  491.68
#Mann= 6 ,-1 , 0
  4077.9     .05       0  5008.6     .03       0  5012.6     .05       0
  5211.6    .075       0  5453.6     .05       0  5591.1    .075       0
Bank Sta=5008.6,5012.6
XS Rating Curve= 0 ,0
Exp/Cntr=0.3,0.1

Type RM Length L Ch R = 1 ,1915    ,481,481,481
BEGIN DESCRIPTION:
Brushy Creek Trib 5_1 3.0
END DESCRIPTION:
XS GIS Cut Line= 3
       2613165.5      6962777.74        2613026.        6961911.
      2612816.67      6960866.36
#Sta/Elev= 30
  4126.4  484.79  4151.6  483.68  4204.1  485.96  4254.8  482.44  4285.4  483.78
    4404  479.93  4751.1  475.86  4882.7  471.02    4903  469.38    4909  467.21
  4943.5  468.09    4982  463.57  4982.3  463.07    4986  463.57  5034.9   466.9
  5160.2  467.72  5228.4  472.45  5284.5  472.37  5310.3  476.06  5357.3  476.52
  5361.1  476.55  5493.8  478.62    5504  482.64  5590.2  482.86    5606  486.08
    5743  485.38  5788.8  490.91    5886  492.86  6050.8   496.9  6069.7  497.75
#Mann= 8 ,-1 , 0
  4126.4     .05       0    4982     .03       0    4986     .05       0
  5160.2    .075       0  5357.3     .05       0  5361.1    .075       0
    5886     .05       0  6050.8    .075       0
Bank Sta=4982,4986
XS Rating Curve= 0 ,0
Exp/Cntr=0.3,0.1

Type RM Length L Ch R = 1 ,1434    ,636,636,636
BEGIN DESCRIPTION:
Brushy Creek Trib 5_1 2.0
END DESCRIPTION:
XS GIS Cut Line= 3
        2613426.      6962211.01        2613476.        6961811.
      2613326.01      6961411.02
#Sta/Elev= 30
  4592.7  480.78  4612.9  478.99  4622.9  476.69  4630.5  475.79  4673.3  474.52
  4711.1  472.29    4764  471.45  4791.7  470.03  4796.8  471.03  4814.4  469.95
  4877.4  469.01  4925.3  466.95    4958  466.45  4975.7  465.46  4993.3  462.65
  5005.6   462.3  5010.9  462.81  5015.1  462.08  5015.4  461.58  5019.2  462.08
  5041.2  465.24  5121.3  464.88  5134.7  466.18  5151.6   469.3  5198.7  469.64
    5237  473.14  5327.8   473.7  5352.7  474.69    5391  479.08    5423  479.51
#Mann= 3 ,-1 , 0
  4592.7     .05       0  5015.1     .03       0  5019.2     .05       0
Bank Sta=5015.1,5019.2
XS Rating Curve= 0 ,0
Exp/Cntr=0.3,0.1

Type RM Length L Ch R = 1 ,798     ,138,138,138
BEGIN DESCRIPTION:
Mapping XS 84080e0b
END DESCRIPTION:
XS GIS Cut Line= 6
      2613430.23      6962274.19      2613714.96      6962038.08
      2613857.32      6961708.21      2614086.48      6961117.94
      2614180.23      6960979.05      2613770.75      6960552.22
#Sta/Elev= 30
  4008.3  479.75  4444.9  474.17  4719.8  467.11  4780.5  468.43  4806.2  465.53
  4811.5  468.22  4837.2  466.11  4873.5  468.13  4899.2  464.88  4904.5  467.15
  4930.2  466.67  4976.2  460.45  4976.5  459.95  4980.3  460.45  5076.3   468.9
  5123.8  466.86  5147.6  467.64    5153   470.5  5433.9  469.08  5463.9   469.1
  5526.1  468.03  5596.7  473.27  5780.9  475.86  5823.1  471.59  5847.2  472.14
  5893.9  466.98  5943.2  475.62  5970.6  476.88  6113.3  483.38    6130  484.06
#Mann= 9 ,-1 , 0
  4008.3     .05       0  4976.2     .03       0  4980.3     .05       0
  5433.9    .075       0  5463.9     .05       0  5780.9    .075       0
  5847.2     .05       0  5970.6    .075       0  6113.3     .05       0
Bank Sta=4976.2,4980.3
XS Rating Curve= 0 ,0
Exp/Cntr=0.3,0.1

Type RM Length L Ch R = 1 ,660     ,472,472,472
BEGIN DESCRIPTION:
Mapping XS 9aec588b
END DESCRIPTION:
XS GIS Cut Line= 6
      2613464.97      6962333.21      2613874.68      6962048.49
      2614027.46      6961666.55      2614069.12      6961496.41
      2614308.71      6961027.66      2613934.22      6960535.28
#Sta/Elev= 30
  3919.6  479.06  4072.7  475.14    4195  477.37  4317.2  473.54  4463.4  475.08
  4786.5  467.81  4842.8  469.23  4847.9  466.54  4884.4  468.34    4926  466.13
  4959.1  458.92  5010.9   458.8  5011.2   458.3    5015   458.8  5065.7  467.44
  5087.1  467.93  5108.6   463.2  5161.3  468.55  5413.6  464.89  5512.8  467.09
  5518.3  464.26  5546.2  469.17  5707.6  468.33  5809.5  469.23  5874.7   472.9
  5932.3  470.57  5974.5  474.26    6060  475.08  6098.5  476.22  6151.1  478.18
#Mann= 8 ,-1 , 0
  3919.6     .05       0  5010.9     .05       0    5015     .05       0
  5707.6    .075       0  5809.5     .05       0  5932.3    .075       0
    6060     .05       0  6098.5    .075       0
Bank Sta=5010.9,5015
XS Rating Curve= 0 ,0
Exp/Cntr=0.3,0.1

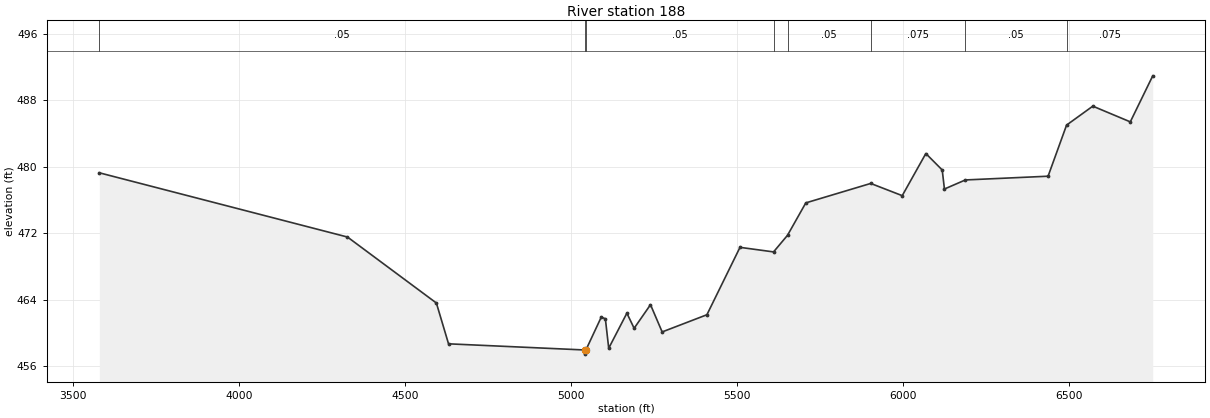
Type RM Length L Ch R = 1 ,188     ,0,0,0
BEGIN DESCRIPTION:
Brushy Creek Trib 5_1 1.0
END DESCRIPTION:
XS GIS Cut Line= 4
      2613437.16      6962381.84      2614426.76      6961763.77
      2614489.26      6961367.94      2613284.95      6960307.26
#Sta/Elev= 30
  3578.5  479.29  4325.8  471.56  4593.5  463.62  4630.1  458.71  5039.6  457.97
  5039.9  457.47  5043.8  457.97  5090.1  461.93  5102.4  461.72  5112.5  458.18
  5167.2   462.4    5189  460.58  5238.3  463.42  5273.4  460.14  5408.2  462.21
  5507.8  470.32  5608.9  469.77  5650.9  471.77    5706  475.67  5901.5  478.01
  5996.4  476.54  6067.5  481.61  6116.8  479.63  6123.5  477.34  6186.5  478.43
  6435.6  478.88  6491.3  485.03  6570.3  487.31  6683.2  485.42  6750.8  490.96
#Mann= 8 ,-1 , 0
  3578.5     .05       0  5039.6     .03       0  5043.8     .05       0
  5608.9    .075       0  5650.9     .05       0  5901.5    .075       0
  6186.5     .05       0  6491.3    .075       0
Bank Sta=5039.6,5043.8
XS Rating Curve= 0 ,0
Exp/Cntr=0.3,0.1

Chan Stop Cuts=-1
Use User Specified Reach Order=0
Composite Channel Slope=5