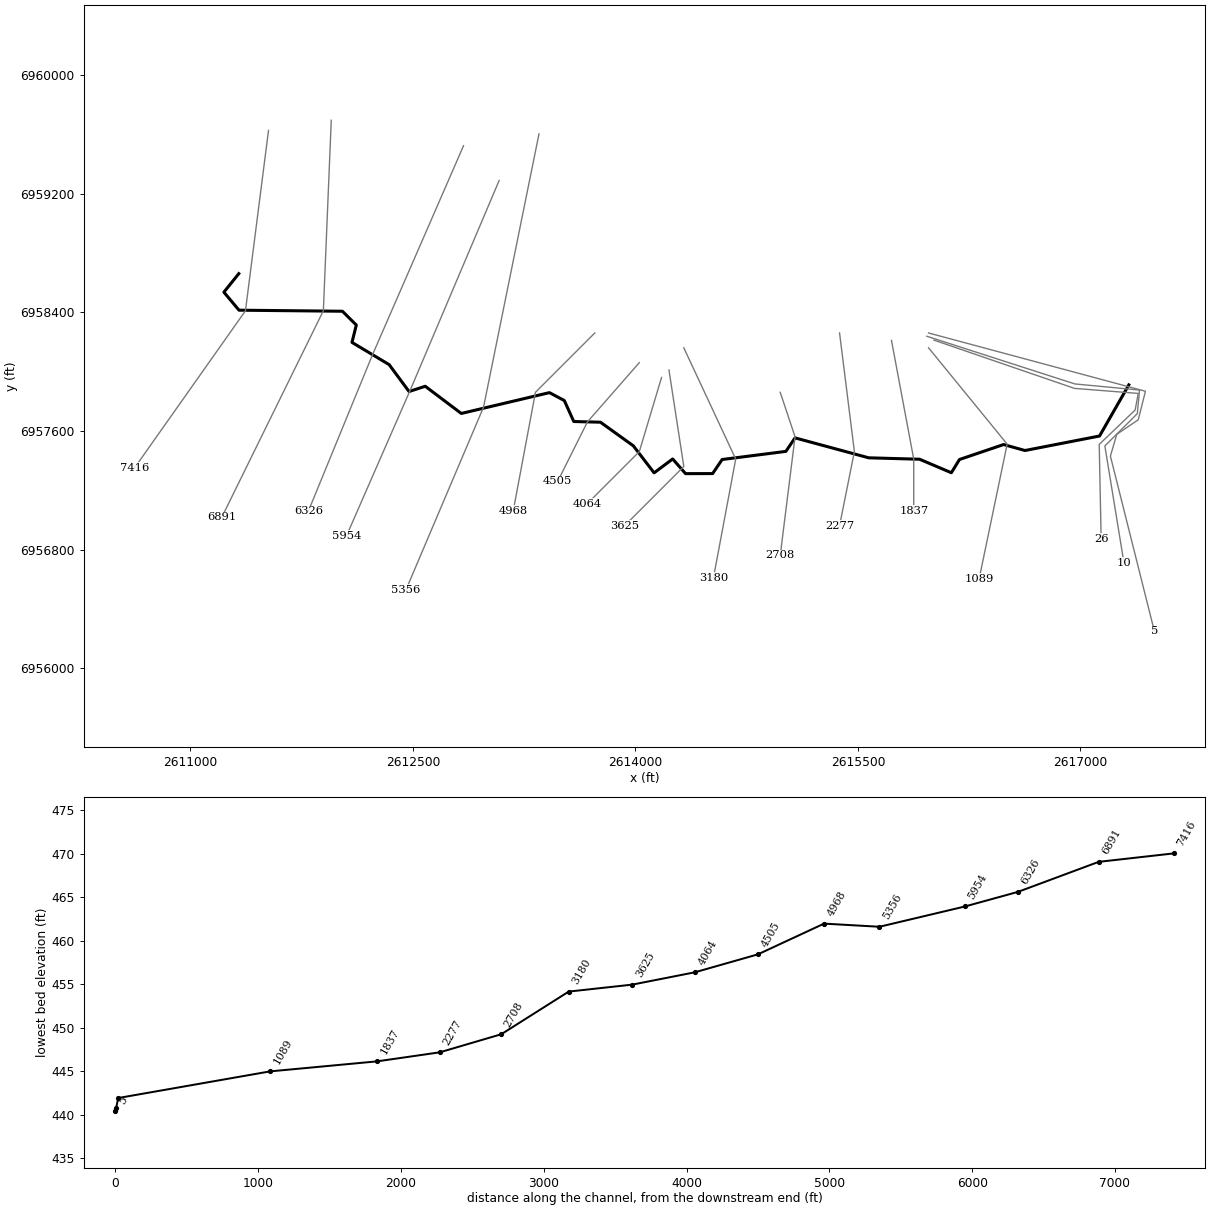
--- Brushy Creek Trib 5_2.prj (project) ---

Proj Title=Brushy Creek Trib 5_2 Base Level Engineering
Current Plan=p01
Default Exp/Contr=0.3,0.1
English Units
Geom File=g01
Flow File=f01
Plan File=p01
BEGIN DESCRIPTION:
Brushy Creek Trib 5_2
END DESCRIPTION:

--- Brushy Creek Trib 5_2.p01 (plan) ---

Plan Title=Multiple Run
Short Identifier=Multiple
Geom File=g01
Flow File=f01
Subcritical Flow
K Sum by GR= 0
Std Step Tol= 0.01
Critical Tol= 0.01
Num of Std Step Trials= 20
Max Error Tol= 0.3
Flow Tol Ratio= 0.001
Split Flow NTrial= 30
Split Flow Tol= 0.02
Split Flow Ratio= 0.02
Log Output Level= 0
Friction Slope Method= 1
Unsteady Friction Slope Method= 2
Unsteady Bridges Friction Slope Method= 1
Parabolic Critical Depth
Global Vel Dist=  1 , 1 , 1
Global Log Level= 0
CheckData=True
Encroach Param= -1, 0, 0, 0
BEGIN DESCRIPTION:
Multiple Run
END DESCRIPTION:

--- Brushy Creek Trib 5_2.f01 (steady flow) ---

Flow Title=Multiple
Number of Profiles=7
Profile Names=10-year,25-year,50-year,1pct_min,100-year,1pct_plu,500-year
River Rch & RM= Brushy Creek Tri,Reach-1,7416
     595     797     960     574    1145    2284    1626
River Rch & RM= Brushy Creek Tri,Reach-1,6326
     661     894    1083     650    1298    2590    1865
River Rch & RM= Brushy Creek Tri,Reach-1,4968
     763    1036    1259     758    1513    3019    2185
River Rch & RM= Brushy Creek Tri,Reach-1,10
    1860    2636    3294    2034    4058    8096    6163
Boundary for River Rch & Prof#=Brushy Creek Tri,Reach-1,1
Up Type=0
Dn Type=3
Dn Slope=0.005
Boundary for River Rch & Prof#=Brushy Creek Tri,Reach-1,2
Up Type=0
Dn Type=3
Dn Slope=0.005
Boundary for River Rch & Prof#=Brushy Creek Tri,Reach-1,3
Up Type=0
Dn Type=3
Dn Slope=0.005
Boundary for River Rch & Prof#=Brushy Creek Tri,Reach-1,4
Up Type=0
Dn Type=3
Dn Slope=0.005
Boundary for River Rch & Prof#=Brushy Creek Tri,Reach-1,5
Up Type=0
Dn Type=3
Dn Slope=0.005
Boundary for River Rch & Prof#=Brushy Creek Tri,Reach-1,6
Up Type=0
Dn Type=3
Dn Slope=0.005
Boundary for River Rch & Prof#=Brushy Creek Tri,Reach-1,7
Up Type=0
Dn Type=3
Dn Slope=0.005

--- Brushy Creek Trib 5_2.g01 (geometry) ---

Geom Title=Existing Conditions

River Reach=Brushy Creek Tri,Reach-1
Reach XY= 30
      2611326.00      6958661.00      2611225.38      6958535.99
      2611327.45      6958414.53      2612024.56      6958407.46
      2612118.19      6958314.42      2612088.99      6958197.44
      2612339.56      6958047.51      2612473.70      6957866.11
      2612582.72      6957901.83      2612825.90      6957718.33
      2613420.09      6957858.78      2613520.42      6957805.42
      2613584.28      6957664.06      2613764.17      6957659.36
      2613985.70      6957500.24      2614125.78      6957318.00
      2614251.08      6957411.61      2614337.83      6957312.64
      2614520.32      6957313.01      2614584.35      6957407.81
      2615014.17      6957462.66      2615075.70      6957553.74
      2615572.78      6957419.28      2615915.50      6957409.78
      2616129.65      6957318.73      2616184.31      6957407.87
      2616481.97      6957508.85      2616626.00      6957468.56
      2617128.73      6957566.35      2617326.00      6957911.00

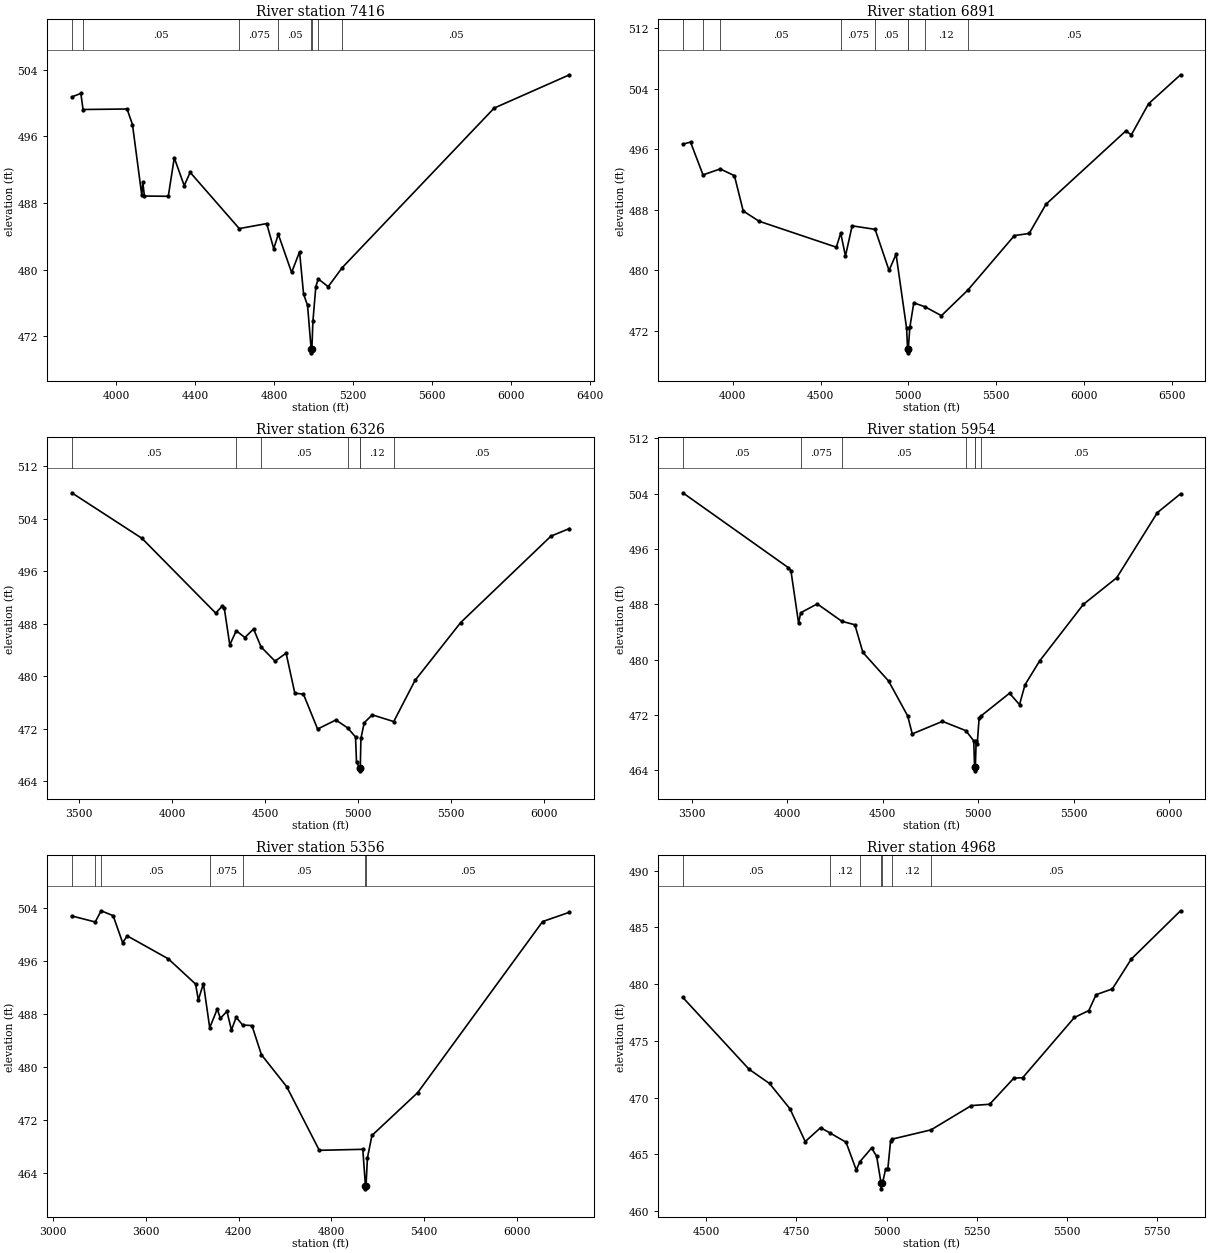
Type RM Length L Ch R = 1,7416,525,525,525
BEGIN DESCRIPTION:
Brushy Creek Trib 5_2 15.0
END DESCRIPTION:
XS GIS Cut Line= 3
      2611526.28      6959626.32      2611370.80      6958410.52
      2610623.06      6957351.13
#Sta/Elev= 30
  3774.3  500.75  3820.5  501.17  3831.6  499.24  4054.7  499.30  4082.1  497.43
  4129.4  488.92  4134.4  490.50  4142.6  488.85  4263.6  488.82  4293.9  493.44
  4344.2  490.10  4374.5  491.69  4623.3  484.94  4762.3  485.54  4797.9  482.53
  4821.2  484.25  4888.6  479.67  4928.9  482.15  4949.1  477.09  4969.3  475.72
  4987.4  470.52  4987.7  470.02  4991.4  470.52  4996.4  473.79  5011.3  477.97
  5023.6  478.89  5074.0  477.97  5145.4  480.26  5915.0  499.41  6296.7  503.41
#Mann=8,-1,0
  3774.3   0.075       0  3831.6    0.05       0  4623.3   0.075       0
  4821.2    0.05       0  4987.4    0.03       0  4991.4    0.05       0
  5023.6    0.12       0  5145.4    0.05       0
Bank Sta=4987.4,4991.4
Exp/Cntr=0.3,0.1

Type RM Length L Ch R = 1,6891,565,565,565
BEGIN DESCRIPTION:
Brushy Creek Trib 5_2 14.0
END DESCRIPTION:
XS GIS Cut Line= 3
      2611949.31      6959694.92      2611896.01      6958411.02
      2611211.88      6957019.61
#Sta/Elev= 30
  3715.0  496.67  3759.0  496.94  3830.2  492.60  3928.3  493.39  4009.2  492.49
  4059.2  487.82  4149.3  486.47  4589.7  483.03  4614.6  484.90  4641.6  481.86
  4679.7  485.86  4810.7  485.39  4889.9  479.96  4930.0  482.09  4990.0  472.29
  4995.5  469.55  4995.8  469.05  4999.5  469.55  5008.5  472.44  5030.9  475.66
  5093.6  475.16  5188.3  473.97  5338.7  477.35  5604.0  484.57  5688.3  484.85
  5783.8  488.71  6238.9  498.42  6270.4  497.90  6368.1  502.01  6550.5  505.85
#Mann=9,-1,0
  3715.0    0.05       0  3830.2   0.075       0  3928.3    0.05       0
  4614.6   0.075       0  4810.7    0.05       0  4995.5    0.03       0
  4999.5    0.05       0  5093.6    0.12       0  5338.7    0.05       0
Bank Sta=4995.5,4999.5
Exp/Cntr=0.3,0.1

Type RM Length L Ch R = 1,6326,372,372,372
BEGIN DESCRIPTION:
Brushy Creek Trib 5_2 13.0
END DESCRIPTION:
XS GIS Cut Line= 3
      2612841.11      6959523.48      2612226.00      6958111.00
      2611794.97      6957059.62
#Sta/Elev= 30
  3459.4  507.92  3836.9  500.99  4233.6  489.61  4269.2  490.69  4280.1  490.31
  4309.3  484.77  4344.3  486.92  4390.5  485.89  4437.4  487.19  4477.4  484.47
  4552.8  482.29  4612.3  483.51  4659.2  477.42  4705.5  477.27  4781.8  471.96
  4880.0  473.34  4943.5  472.13  4985.6  470.76  4991.0  466.89  5007.3  466.10
  5007.5  465.60  5011.3  466.10  5014.7  470.53  5032.4  472.92  5075.7  474.12
  5191.2  473.10  5305.6  479.36  5551.2  488.17  6036.7  501.32  6136.3  502.48
#Mann=7,-1,0
  3459.4    0.05       0  4344.3   0.075       0  4477.4    0.05       0
  4943.5    0.12       0  5007.3    0.07       0  5011.3    0.12       0
  5191.2    0.05       0
Bank Sta=5007.3,5011.3
Exp/Cntr=0.3,0.1

Type RM Length L Ch R = 1,5954,598,598,598
BEGIN DESCRIPTION:
Brushy Creek Trib 5_2 12.0
END DESCRIPTION:
XS GIS Cut Line= 3
      2613081.19      6959289.06      2612486.41      6957886.73
      2612052.66      6956894.87
#Sta/Elev= 30
  3452.6  504.11  4004.5  493.30  4018.6  492.86  4058.8  485.27  4070.0  486.77
  4156.5  488.05  4284.8  485.54  4353.5  485.03  4395.4  481.04  4530.0  476.90
  4630.1  471.85  4653.8  469.26  4812.1  471.07  4934.4  469.73  4975.9  468.25
  4980.1  464.42  4980.4  463.92  4984.1  464.42  4988.5  468.28  4993.9  467.75
  5003.9  471.55  5015.2  471.88  5163.1  475.14  5215.4  473.49  5244.2  476.36
  5320.4  479.79  5549.7  487.98  5724.3  491.83  5937.4  501.25  6058.4  503.96
#Mann=7,-1,0
  3452.6    0.05       0  4070.0   0.075       0  4284.8    0.05       0
  4934.4    0.12       0  4980.1    0.07       0  4984.1    0.12       0
  5015.2    0.05       0
Bank Sta=4980.1,4984.1
Exp/Cntr=0.3,0.1

Type RM Length L Ch R = 1,5356,388,388,388
BEGIN DESCRIPTION:
Brushy Creek Trib 5_2 11.0
END DESCRIPTION:
XS GIS Cut Line= 3
      2613349.85      6959603.42      2612975.97      6957761.07
      2612452.35      6956527.94
#Sta/Elev= 30
  3120.1  502.81  3272.0  501.90  3310.2  503.59  3387.9  502.85  3449.1  498.78
  3479.7  499.79  3745.0  496.33  3921.2  492.52  3938.9  490.12  3971.8  492.59
  4012.6  485.92  4061.3  488.74  4081.7  487.34  4123.8  488.41  4153.2  485.58
  4183.8  487.51  4225.5  486.34  4285.8  486.25  4347.0  481.85  4510.3  477.03
  4721.4  467.41  5002.8  467.56  5019.8  462.09  5020.1  461.59  5023.8  462.09
  5032.7  466.25  5061.9  469.65  5358.6  476.14  6166.0  501.96  6339.7  503.37
#Mann=7,-1,0
  3120.1    0.05       0  3272.0   0.075       0  3310.2    0.05       0
  4012.6   0.075       0  4225.5    0.05       0  5019.8    0.03       0
  5023.8    0.05       0
Bank Sta=5019.8,5023.8
Exp/Cntr=0.3,0.1

Type RM Length L Ch R = 1,4968,463,463,463
BEGIN DESCRIPTION:
Brushy Creek Trib 5_2 10.0
END DESCRIPTION:
XS GIS Cut Line= 3
      2613726.00      6958261.00      2613326.00      6957861.00
      2613176.00      6957061.02
#Sta/Elev= 30
  4435.0  478.83  4618.8  472.49  4675.4  471.24  4732.0  469.01  4774.4  466.12
  4816.8  467.34  4841.8  466.90  4887.5  466.06  4915.8  463.61  4926.0  464.35
  4958.3  465.55  4972.4  464.81  4984.5  462.45  4984.8  461.95  4988.5  462.45
  4997.1  463.68  5003.2  463.68  5010.9  466.16  5016.1  466.34  5123.0  467.15
  5234.7  469.29  5285.6  469.41  5352.5  471.71  5377.1  471.75  5520.4  477.06
  5560.3  477.67  5580.6  479.07  5625.6  479.58  5678.1  482.21  5814.6  486.47
#Mann=7,-1,0
  4435.0    0.05       0  4841.8    0.12       0  4926.0    0.05       0
  4984.5    0.03       0  4988.5    0.05       0  5016.1    0.12       0
  5123.0    0.05       0
Bank Sta=4984.5,4988.5
Exp/Cntr=0.3,0.1

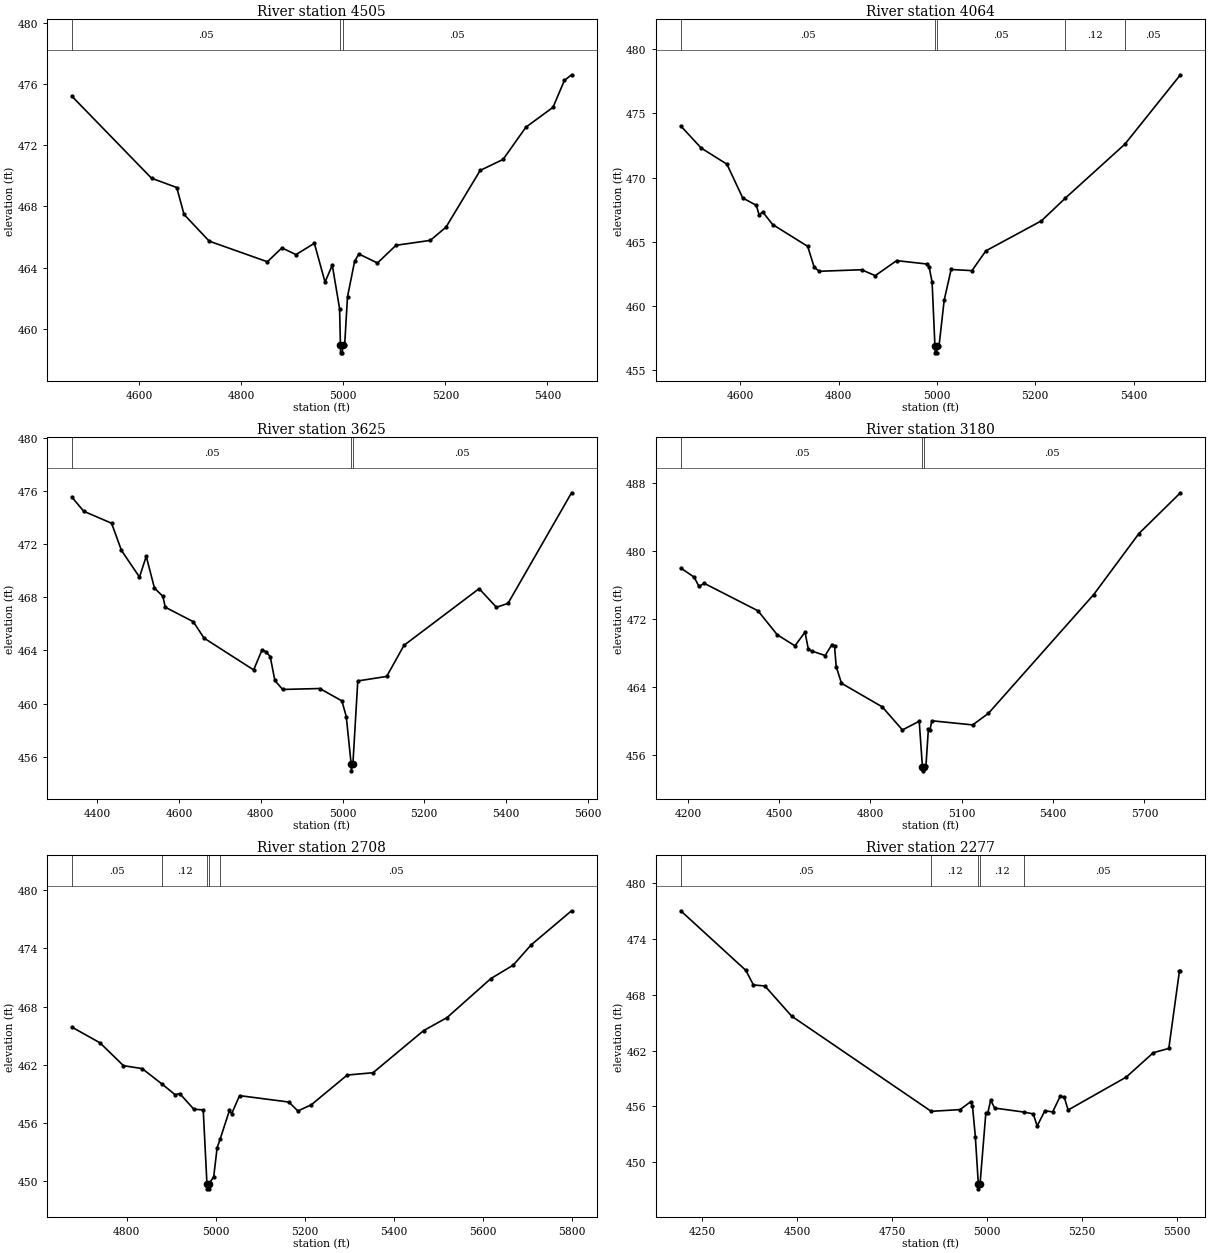
Type RM Length L Ch R = 1,4505,441,441,441
BEGIN DESCRIPTION:
Brushy Creek Trib 5_2 9.0
END DESCRIPTION:
XS GIS Cut Line= 3
      2614026.00      6958061.00      2613676.00      6957661.00
      2613476.01      6957261.01
#Sta/Elev= 30
  4468.5  475.22  4624.6  469.85  4674.0  469.24  4688.2  467.48  4737.6  465.73
  4851.5  464.38  4879.9  465.29  4907.5  464.85  4943.5  465.59  4964.4  463.05
  4978.6  464.16  4992.9  461.31  4994.6  458.92  4994.9  458.42  4998.4  458.42
  4998.7  458.92  5002.8  458.92  5008.4  462.09  5022.4  464.42  5030.7  464.89
  5067.1  464.30  5103.4  465.46  5170.5  465.78  5201.2  466.64  5268.3  470.36
  5313.1  471.08  5357.8  473.19  5410.9  474.49  5433.2  476.25  5447.2  476.62
#Mann=3,-1,0
  4468.5    0.05       0  4994.6    0.03       0  4998.7    0.05       0
Bank Sta=4994.6,4998.7
Exp/Cntr=0.3,0.1

Type RM Length L Ch R = 1,4064,439,439,439
BEGIN DESCRIPTION:
Brushy Creek Trib 5_2 8.0
END DESCRIPTION:
XS GIS Cut Line= 3
      2614176.00      6957961.01      2614026.00      6957461.00
      2613676.00      6957111.00
#Sta/Elev= 30
  4478.5  474.03  4520.3  472.30  4572.5  471.05  4604.7  468.42  4632.5  467.84
  4637.7  467.13  4645.6  467.32  4665.6  466.35  4736.9  464.65  4750.0  463.04
  4760.4  462.71  4846.5  462.83  4874.4  462.37  4917.9  463.54  4978.8  463.28
  4984.0  463.06  4990.1  461.86  4995.9  456.86  4996.2  456.36  4999.7  456.36
  5000.0  456.86  5004.1  456.86  5014.7  460.46  5028.8  462.85  5071.2  462.76
  5099.5  464.30  5212.7  466.64  5260.8  468.39  5382.5  472.61  5495.5  478.01
#Mann=5,-1,0
  4478.5    0.05       0  4995.9    0.03       0  5000.0    0.05       0
  5260.8    0.12       0  5382.5    0.05       0
Bank Sta=4995.9,5000
Exp/Cntr=0.3,0.1

Type RM Length L Ch R = 1,3625,445,445,445
BEGIN DESCRIPTION:
Brushy Creek Trib 5_2 7.0
END DESCRIPTION:
XS GIS Cut Line= 3
      2614226.01      6958010.96      2614326.00      6957361.00
      2613926.00      6956961.00
#Sta/Elev= 30
  4337.4  475.53  4366.5  474.46  4434.7  473.56  4458.8  471.52  4503.0  469.51
  4519.5  471.07  4539.7  468.68  4560.0  468.07  4566.3  467.24  4634.6  466.16
  4661.1  464.92  4782.5  462.53  4802.8  464.02  4812.9  463.90  4823.0  463.53
  4834.4  461.74  4853.4  461.06  4944.4  461.13  4998.5  460.20  5009.2  459.02
  5021.2  455.44  5021.5  454.94  5025.4  455.44  5037.4  461.70  5108.1  462.04
  5150.6  464.38  5334.4  468.64  5376.8  467.24  5405.1  467.53  5560.7  475.85
#Mann=3,-1,0
  4337.4    0.05       0  5021.2    0.03       0  5025.4    0.05       0
Bank Sta=5021.2,5025.4
Exp/Cntr=0.3,0.1

Type RM Length L Ch R = 1,3180,472,472,472
BEGIN DESCRIPTION:
Brushy Creek Trib 5_2 6.0
END DESCRIPTION:
XS GIS Cut Line= 3
      2614326.00      6958161.00      2614676.00      6957411.00
      2614526.00      6956610.99
#Sta/Elev= 30
  4176.6  477.99  4220.7  476.92  4236.5  475.83  4253.8  476.19  4430.4  472.96
  4493.5  470.15  4551.8  468.84  4584.9  470.45  4595.9  468.43  4607.0  468.23
  4651.1  467.70  4673.2  468.98  4681.9  468.78  4687.4  466.40  4704.7  464.44
  4838.7  461.66  4904.9  458.95  4960.1  459.97  4970.6  454.64  4970.9  454.14
  4974.9  454.64  4982.2  454.72  4990.1  459.01  4995.6  458.96  5001.5  460.03
  5135.7  459.54  5187.4  460.90  5533.3  474.87  5681.7  482.04  5818.2  486.84
#Mann=3,-1,0
  4176.6    0.05       0  4970.6    0.03       0  4974.9    0.05       0
Bank Sta=4970.6,4974.9
Exp/Cntr=0.3,0.1

Type RM Length L Ch R = 1,2708,431,431,431
BEGIN DESCRIPTION:
Brushy Creek Trib 5_2 5.0
END DESCRIPTION:
XS GIS Cut Line= 3
      2614976.01      6957860.97      2615076.00      6957561.00
      2614976.00      6956761.02
#Sta/Elev= 30
  4676.4  465.90  4739.6  464.28  4792.3  461.93  4834.5  461.62  4879.3  460.02
  4908.3  458.94  4918.8  459.05  4950.4  457.44  4971.5  457.37  4979.9  449.74
  4980.3  449.24  4983.9  449.24  4984.2  449.74  4995.1  450.49  5002.7  453.47
  5009.3  454.34  5030.4  457.31  5035.4  456.98  5053.1  458.84  5163.9  458.18
  5184.1  457.26  5214.3  457.90  5294.9  460.96  5352.9  461.20  5466.3  465.53
  5519.2  466.88  5617.4  470.89  5667.8  472.28  5708.1  474.37  5798.8  477.88
#Mann=5,-1,0
  4676.4    0.05       0  4879.3    0.12       0  4979.9    0.07       0
  4984.2    0.12       0  5009.3    0.05       0
Bank Sta=4979.9,4984.2
Exp/Cntr=0.3,0.1

Type RM Length L Ch R = 1,2277,440,440,440
BEGIN DESCRIPTION:
Brushy Creek Trib 5_2 4.0
END DESCRIPTION:
XS GIS Cut Line= 3
      2615376.00      6958261.04      2615476.00      6957461.00
      2615375.99      6956960.97
#Sta/Elev= 30
  4193.7  477.00  4365.1  470.61  4385.2  469.04  4415.4  468.93  4486.0  465.69
  4853.3  455.48  4929.4  455.66  4957.1  456.50  4962.2  456.05  4969.7  452.77
  4977.6  447.66  4978.0  447.16  4982.0  447.66  4997.4  455.31  5002.5  455.31
  5010.2  456.68  5020.4  455.83  5099.1  455.39  5122.3  455.20  5132.5  453.90
  5152.9  455.55  5173.3  455.41  5193.7  457.14  5203.9  456.99  5214.1  455.62
  5367.1  459.15  5438.5  461.77  5479.3  462.23  5507.3  470.54  5509.9  470.54
#Mann=5,-1,0
  4193.7    0.05       0  4853.3    0.12       0  4977.6    0.07       0
  4982.0    0.12       0  5099.1    0.05       0
Bank Sta=4977.6,4982
Exp/Cntr=0.3,0.1

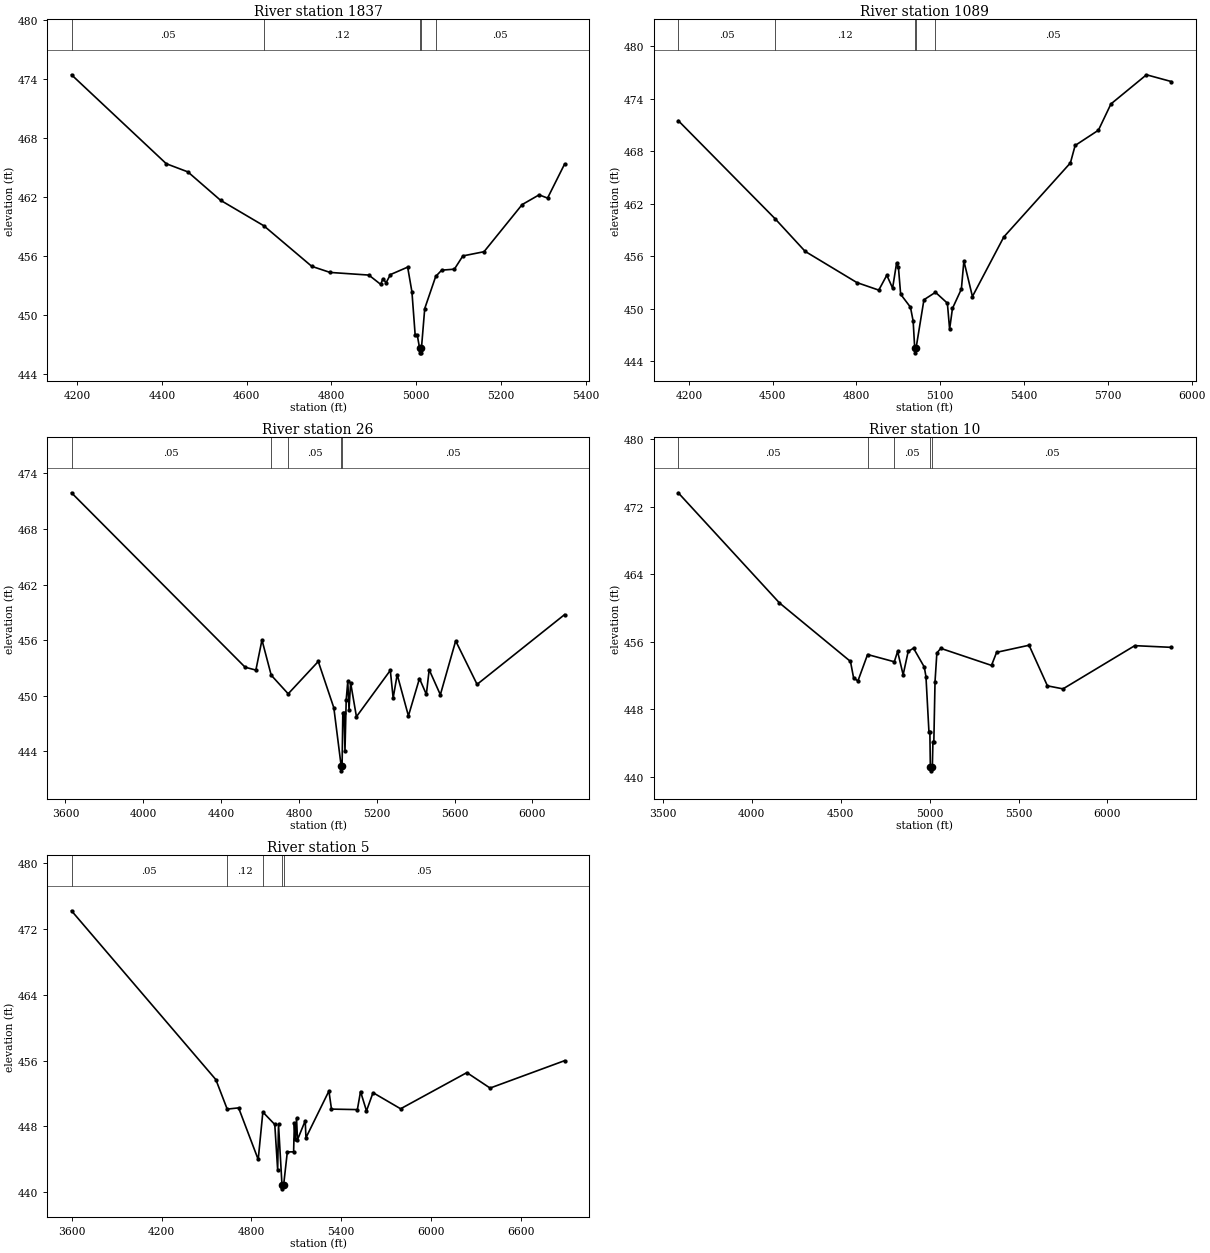
Type RM Length L Ch R = 1,1837,748,748,748
BEGIN DESCRIPTION:
Brushy Creek Trib 5_2 3.0
END DESCRIPTION:
XS GIS Cut Line= 3
      2615726.01      6958210.97      2615876.00      6957411.00
      2615876.00      6957061.01
#Sta/Elev= 30
  4186.5  474.44  4410.3  465.38  4461.2  464.55  4538.3  461.66  4640.6  459.06
  4753.7  454.93  4796.9  454.31  4888.5  454.04  4916.5  453.09  4921.6  453.67
  4929.2  453.26  4939.4  454.09  4980.1  454.85  4990.2  452.33  4997.9  447.89
  5002.9  447.89  5008.2  446.62  5008.6  446.12  5012.2  446.12  5012.7  446.62
  5020.4  450.63  5046.3  453.90  5060.4  454.54  5090.4  454.64  5110.4  455.99
  5160.4  456.42  5250.4  461.22  5290.4  462.21  5310.4  461.88  5350.4  465.33
#Mann=5,-1,0
  4186.5    0.05       0  4640.6    0.12       0  5008.2    0.07       0
  5012.7    0.12       0  5046.3    0.05       0
Bank Sta=5008.2,5012.7
Exp/Cntr=0.3,0.1

Type RM Length L Ch R = 1,1089,1063,1063,1063
BEGIN DESCRIPTION:
Brushy Creek Trib 5_2 2.0
END DESCRIPTION:
XS GIS Cut Line= 3
      2615976.00      6958161.00      2616505.95      6957511.59
      2616317.13      6956604.13
#Sta/Elev= 30
  4161.8  471.48  4507.9  460.30  4616.3  456.55  4801.5  452.99  4879.8  452.13
  4908.5  453.83  4929.3  452.36  4943.7  455.25  4950.2  454.72  4958.1  451.66
  4993.2  450.18  5002.9  448.59  5008.5  445.47  5009.0  444.97  5013.1  445.47
  5041.5  451.03  5082.8  451.88  5125.4  450.64  5133.4  447.67  5143.6  450.04
  5175.5  452.25  5184.5  455.45  5215.1  451.40  5327.5  458.20  5565.9  466.65
  5582.8  468.64  5666.1  470.38  5711.0  473.38  5838.2  476.71  5926.9  475.94
#Mann=5,-1,0
  4161.8    0.05       0  4507.9    0.12       0  5008.5    0.07       0
  5013.1    0.12       0  5082.8    0.05       0
Bank Sta=5008.5,5013.1
Exp/Cntr=0.3,0.1

Type RM Length L Ch R = 1,26,16,16,16
BEGIN DESCRIPTION:
Mapping XS 967d509b
END DESCRIPTION:
XS GIS Cut Line= 6
      2616011.98      6958212.88      2616959.93      6957887.35
      2617389.61      6957853.50      2617368.78      6957741.52
      2617126.59      6957509.75      2617139.61      6956871.72
#Sta/Elev= 30
  3631.2  471.91  4523.6  453.09  4578.9  452.78  4610.2  456.03  4657.7  452.23
  4745.0  450.22  4899.6  453.71  4979.6  448.71  5017.4  442.41  5017.9  441.91
  5022.0  442.41  5025.8  448.18  5031.9  448.18  5036.9  444.09  5043.2  449.57
  5051.3  451.57  5057.7  448.50  5065.8  451.42  5095.8  447.75  5269.9  452.75
  5284.5  449.77  5305.3  452.29  5363.0  447.84  5419.8  451.87  5455.1  450.16
  5469.7  452.82  5527.1  450.12  5605.9  455.93  5715.9  451.24  6165.3  458.76
#Mann=5,-1,0
  3631.2    0.05       0  4657.7    0.12       0  4745.0    0.05       0
  5017.4    0.03       0  5022.0    0.05       0
Bank Sta=5017.4,5022
Exp/Cntr=0.3,0.1

Type RM Length L Ch R = 1,10,5,5,5
BEGIN DESCRIPTION:
Mapping XS ef712bfc
END DESCRIPTION:
XS GIS Cut Line= 6
      2615964.10      6958238.91      2616962.79      6957917.30
      2617398.25      6957876.17      2617383.32      6957716.80
      2617164.61      6957499.33      2617293.51      6956710.31
#Sta/Elev= 30
  3586.6  473.66  4155.9  460.61  4555.1  453.68  4572.8  451.72  4597.1  451.37
  4651.3  454.50  4801.6  453.64  4820.2  454.86  4851.3  452.10  4879.6  454.86
  4909.6  455.25  4970.1  453.02  4979.6  451.89  4996.5  445.30  5001.6  445.30
  5004.3  441.22  5005.9  440.72  5015.6  441.22  5018.8  444.19  5023.9  444.16
  5030.6  451.28  5040.9  454.68  5062.9  455.23  5348.2  453.21  5376.9  454.76
  5559.4  455.60  5662.6  450.79  5750.2  450.43  6153.9  455.55  6358.9  455.35
#Mann=5,-1,0
  3586.6    0.05       0  4651.3    0.12       0  4801.6    0.05       0
  5004.3    0.03       0  5015.6    0.05       0
Bank Sta=5004.3,5015.6
Exp/Cntr=0.3,0.1

Type RM Length L Ch R = 1,5,0,0,0
BEGIN DESCRIPTION:
Brushy Creek Trib 5_2 1.0
END DESCRIPTION:
XS GIS Cut Line= 6
      2615975.95      6958261.01      2617438.16      6957867.98
      2617389.55      6957675.62      2617244.76      6957577.70
      2617202.05      6957430.83      2617498.73      6956248.81
#Sta/Elev= 30
  3598.2  474.22  4562.5  453.68  4638.3  450.09  4714.6  450.24  4845.5  443.96
  4876.5  449.73  4956.2  448.22  4975.5  442.68  4981.1  448.22  5004.3  440.89
  5005.8  440.39  5015.6  440.89  5040.0  444.88  5082.0  444.89  5087.1  448.39
  5093.4  446.40  5101.6  448.97  5107.9  446.36  5159.5  448.67  5164.6  446.61
  5317.9  452.29  5335.0  450.09  5508.0  450.03  5529.1  452.23  5568.9  449.87
  5612.5  452.09  5796.9  450.13  6239.4  454.53  6394.6  452.65  6891.8  455.98
#Mann=5,-1,0
  3598.2    0.05       0  4638.3    0.12       0  4876.5    0.05       0
  5004.3    0.03       0  5015.6    0.05       0
Bank Sta=5004.3,5015.6
Exp/Cntr=0.3,0.1

Chan Stop Cuts=-1