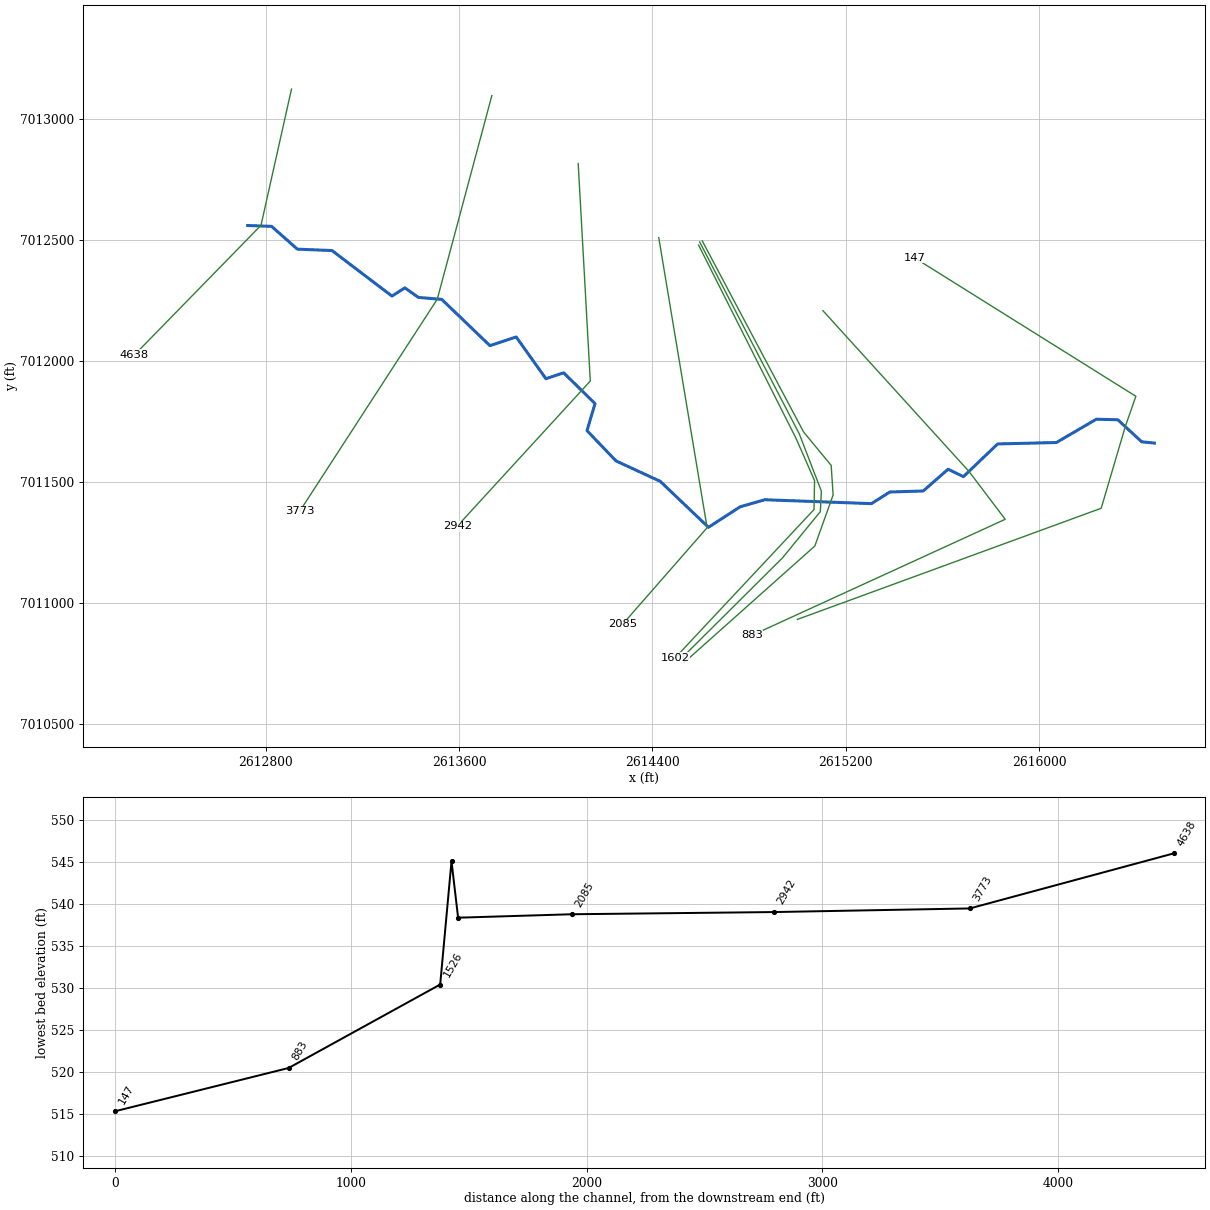
--- Brushy Creek Tributary 11.prj (project) ---

Proj Title=Brushy Creek Tributary 11 Base Level Engineering
Current Plan=p01
Default Exp/Contr=0.3,0.1
English Units
Geom File=g01
Flow File=f01
Plan File=p01
BEGIN DESCRIPTION:
Brushy Creek Tributary 11
END DESCRIPTION:

--- Brushy Creek Tributary 11.p01 (plan) ---

Plan Title=Multiple Run
Short Identifier=Multiple
Geom File=g01
Flow File=f01
Subcritical Flow
K Sum by GR= 0
Std Step Tol= 0.01
Critical Tol= 0.01
Num of Std Step Trials= 20
Max Error Tol= 0.3
Flow Tol Ratio= 0.001
Split Flow NTrial= 30
Split Flow Tol= 0.02
Split Flow Ratio= 0.02
Log Output Level= 0
Friction Slope Method= 1
Unsteady Friction Slope Method= 2
Unsteady Bridges Friction Slope Method= 1
Parabolic Critical Depth
Global Vel Dist=  1 , 1 , 1
Global Log Level= 0
CheckData=True
Encroach Param= -1, 0, 0, 0
BEGIN DESCRIPTION:
Multiple Run
END DESCRIPTION:

--- Brushy Creek Tributary 11.f01 (steady flow) ---

Flow Title=Multiple
Number of Profiles=7
Profile Names=10-year,25-year,50-year,1pct_min,100-year,1pct_plu,500-year
River Rch & RM= Brushy Creek Tri,Reach-1,4638
     380     495     585     344     686    1368     941
River Rch & RM= Brushy Creek Tri,Reach-1,1602
     410     538     639     377     753    1502    1043
River Rch & RM= Brushy Creek Tri,Reach-1,883
     417     547     650     384     766    1529    1062
Boundary for River Rch & Prof#=Brushy Creek Tri,Reach-1,1
Up Type=0
Dn Type=3
Dn Slope=0.005
Boundary for River Rch & Prof#=Brushy Creek Tri,Reach-1,2
Up Type=0
Dn Type=3
Dn Slope=0.005
Boundary for River Rch & Prof#=Brushy Creek Tri,Reach-1,3
Up Type=0
Dn Type=3
Dn Slope=0.005
Boundary for River Rch & Prof#=Brushy Creek Tri,Reach-1,4
Up Type=0
Dn Type=3
Dn Slope=0.005
Boundary for River Rch & Prof#=Brushy Creek Tri,Reach-1,5
Up Type=0
Dn Type=3
Dn Slope=0.005
Boundary for River Rch & Prof#=Brushy Creek Tri,Reach-1,6
Up Type=0
Dn Type=3
Dn Slope=0.005
Boundary for River Rch & Prof#=Brushy Creek Tri,Reach-1,7
Up Type=0
Dn Type=3
Dn Slope=0.005

--- Brushy Creek Tributary 11.g01 (geometry) ---

Geom Title=Existing Conditions

River Reach=Brushy Creek Tri,Reach-1
Reach XY= 30
      2612726.00      7012561.00      2612824.59      7012557.61
      2612931.45      7012463.19      2613074.53      7012457.45
      2613322.67      7012269.01      2613375.90      7012303.20
      2613431.89      7012263.55      2613528.43      7012255.48
      2613727.65      7012064.16      2613836.37      7012100.02
      2613959.30      7011927.38      2614032.67      7011951.70
      2614162.46      7011824.38      2614129.16      7011712.65
      2614249.18      7011587.29      2614432.06      7011502.86
      2614631.64      7011312.69      2614762.68      7011397.63
      2614864.47      7011426.72      2615305.72      7011410.61
      2615381.52      7011458.59      2615520.14      7011463.08
      2615622.67      7011552.98      2615686.00      7011522.24
      2615827.46      7011657.46      2616070.48      7011663.35
      2616235.70      7011759.76      2616324.50      7011757.54
      2616423.49      7011666.33      2616476.00      7011661.00

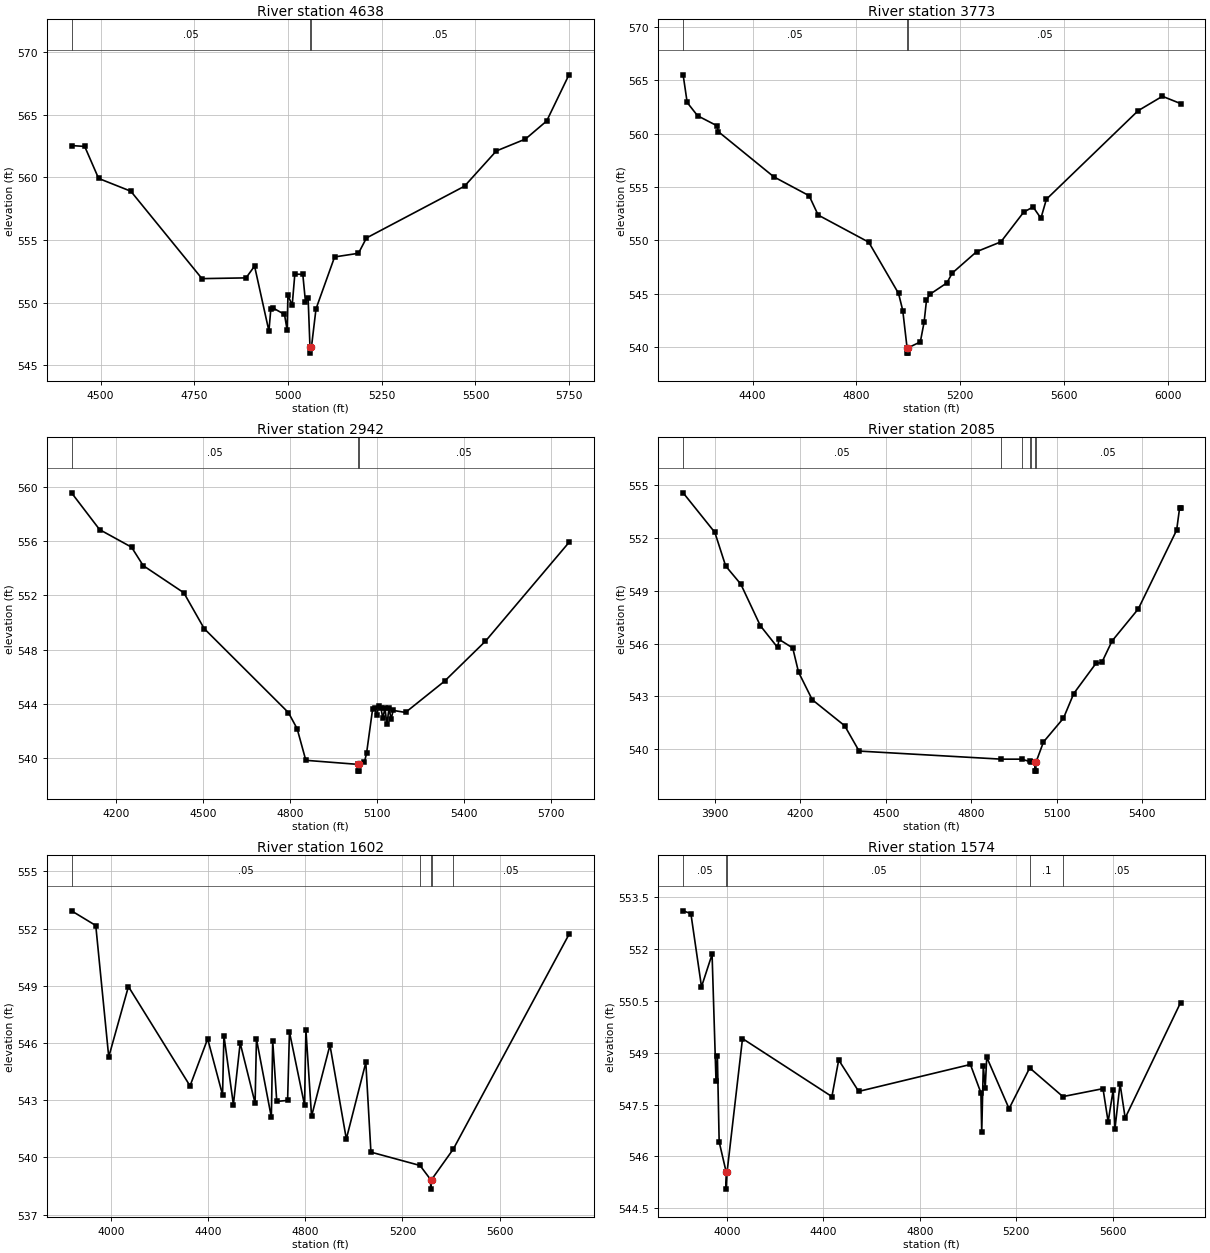
Type RM Length L Ch R = 1,4638,865,865,865
BEGIN DESCRIPTION:
Brushy Creek Tributary 11 6.0
END DESCRIPTION:
XS GIS Cut Line= 3
      2612907.03      7013125.30      2612780.86      7012561.75
      2612257.38      7012025.63
#Sta/Elev= 30
  4422.5  562.53  4457.6  562.46  4494.7  559.91  4580.6  558.89  4770.4  551.92
  4888.0  551.98  4910.7  552.92  4949.0  547.74  4954.1  549.50  4959.8  549.58
  4990.5  549.07  4997.5  547.83  4999.7  550.59  5011.1  549.80  5018.1  552.28
  5039.4  552.26  5046.4  550.09  5053.5  550.41  5058.5  546.48  5058.7  545.98
  5062.5  546.48  5074.6  549.51  5124.2  553.65  5187.8  553.94  5209.1  555.16
  5470.7  559.29  5555.6  562.10  5633.3  563.05  5689.9  564.49  5749.3  568.17
#Mann=3,-1,0
  4422.5    0.05       0  5058.5    0.03       0  5062.5    0.05       0
Bank Sta=5058.5,5062.5
Exp/Cntr=0.3,0.1

Type RM Length L Ch R = 1,3773,831,831,831
BEGIN DESCRIPTION:
Mapping XS d6b2a73e
END DESCRIPTION:
XS GIS Cut Line= 3
      2613735.73      7013098.45      2613510.04      7012256.45
      2612941.46      7011379.70
#Sta/Elev= 30
  4132.4  565.50  4148.0  562.91  4188.0  561.67  4262.9  560.73  4268.0  560.18
  4481.8  555.95  4617.9  554.18  4652.7  552.37  4847.6  549.83  4962.5  545.03
  4978.7  543.43  4995.3  539.94  4995.6  539.44  4999.1  539.44  4999.3  539.94
  5046.4  540.49  5060.9  542.33  5070.1  544.38  5082.1  544.93  5148.5  546.01
  5169.6  546.94  5263.3  548.94  5356.9  549.86  5444.6  552.64  5480.8  553.13
  5511.1  552.07  5532.2  553.85  5885.6  562.14  5979.2  563.49  6049.1  562.81
#Mann=3,-1,0
  4132.4    0.05       0  4995.3    0.03       0  4999.3    0.05       0
Bank Sta=4995.3,4999.3
Exp/Cntr=0.3,0.1

Type RM Length L Ch R = 1,2942,857,857,857
BEGIN DESCRIPTION:
Brushy Creek Tributary 11 5.0
END DESCRIPTION:
XS GIS Cut Line= 3
      2614092.85      7012817.65      2614142.85      7011917.69
      2613592.84      7011317.68
#Sta/Elev= 30
  4046.8  559.59  4143.6  556.87  4253.8  555.57  4293.8  554.21  4434.0  552.20
  4504.2  549.55  4794.6  543.34  4824.7  542.15  4854.7  539.81  5033.8  539.51
  5034.0  539.01  5037.5  539.01  5037.8  539.51  5056.7  539.68  5064.1  540.32
  5085.1  543.61  5092.5  543.70  5099.3  543.15  5106.4  543.82  5113.5  543.71
  5120.2  542.92  5127.6  543.68  5134.4  542.47  5141.8  543.70  5148.6  542.84
  5156.0  543.50  5198.5  543.35  5333.0  545.66  5474.2  548.62  5762.1  555.92
#Mann=3,-1,0
  4046.8    0.05       0  5033.8    0.03       0  5037.8    0.05       0
Bank Sta=5033.8,5037.8
Exp/Cntr=0.3,0.1

Type RM Length L Ch R = 1,2085,483,483,483
BEGIN DESCRIPTION:
Brushy Creek Tributary 11 4.0
END DESCRIPTION:
XS GIS Cut Line= 3
      2614426.00      7012510.98      2614626.00      7011311.00
      2614276.03      7010911.03
#Sta/Elev= 30
  3787.8  554.57  3899.3  552.32  3937.3  550.41  3990.5  549.38  4059.0  547.02
  4119.8  545.78  4124.9  546.24  4173.0  545.75  4193.3  544.38  4241.5  542.81
  4355.5  541.33  4406.2  539.89  4906.1  539.43  4977.1  539.43  5005.1  539.30
  5010.0  539.28  5023.7  539.25  5023.9  538.75  5027.4  538.75  5027.7  539.25
  5054.2  540.41  5124.4  541.76  5160.5  543.16  5238.3  544.87  5259.2  544.93
  5295.2  546.15  5387.3  547.97  5522.1  552.45  5532.5  553.71  5535.8  553.71
#Mann=7,-1,0
  3787.8    0.05       0  4906.1     0.1       0  4977.1    0.05       0
  5005.1     0.1       0  5010.0    0.05       0  5023.7    0.03       0
  5027.7    0.05       0
Bank Sta=5023.7,5027.7
Exp/Cntr=0.3,0.1

Type RM Length L Ch R = 1,1602,28,28,28
BEGIN DESCRIPTION:
Mapping XS cf6049cb
END DESCRIPTION:
XS GIS Cut Line= 5
      2614590.75      7012480.02      2614994.42      7011679.19
      2615070.37      7011505.58      2615068.20      7011386.22
      2614493.09      7010772.04
#Sta/Elev= 30
  3838.0  552.93  3937.7  552.16  3991.1  545.27  4072.1  548.96  4325.7  543.75
  4398.2  546.22  4459.5  543.28  4465.1  546.39  4504.1  542.77  4532.0  546.00
  4593.4  542.85  4599.0  546.21  4660.3  542.11  4665.9  546.12  4682.6  542.94
  4727.2  542.99  4734.8  546.58  4797.0  542.74  4802.5  546.70  4825.8  542.16
  4901.5  545.89  4968.9  540.97  5049.1  544.98  5070.1  540.28  5272.1  539.58
  5315.8  538.84  5316.0  538.34  5319.8  538.84  5409.2  540.44  5885.1  551.69
#Mann=5,-1,0
  3838.0    0.05       0  5272.1     0.1       0  5315.8    0.03       0
  5319.8     0.1       0  5409.2    0.05       0
Bank Sta=5315.8,5319.8
Exp/Cntr=0.3,0.1

Type RM Length L Ch R = 1,1574,48,48,48
BEGIN DESCRIPTION:
Mapping XS ab65f6bc
END DESCRIPTION:
XS GIS Cut Line= 6
      2614595.10      7012493.02      2615007.44      7011698.72
      2615098.58      7011462.18      2615094.24      7011377.54
      2614937.99      7011186.57      2614525.67      7010776.42
#Sta/Elev= 30
  3818.1  553.11  3850.3  553.03  3894.3  550.91  3938.2  551.85  3954.5  548.18
  3960.2  548.90  3967.6  546.42  3996.5  545.55  3996.7  545.05  4000.5  545.55
  4064.4  549.41  4435.3  547.73  4463.5  548.79  4546.4  547.88  5009.9  548.66
  5053.4  547.84  5056.9  546.70  5063.4  548.62  5071.3  547.98  5077.7  548.87
  5170.3  547.38  5255.9  548.56  5393.5  547.73  5560.0  547.96  5581.3  547.00
  5602.4  547.93  5609.5  546.79  5630.7  548.10  5652.0  547.11  5881.7  550.45
#Mann=5,-1,0
  3818.1    0.05       0  3996.5    0.03       0  4000.5    0.05       0
  5255.9     0.1       0  5393.5    0.05       0
Bank Sta=3996.5,4000.5
Exp/Cntr=0.3,0.1

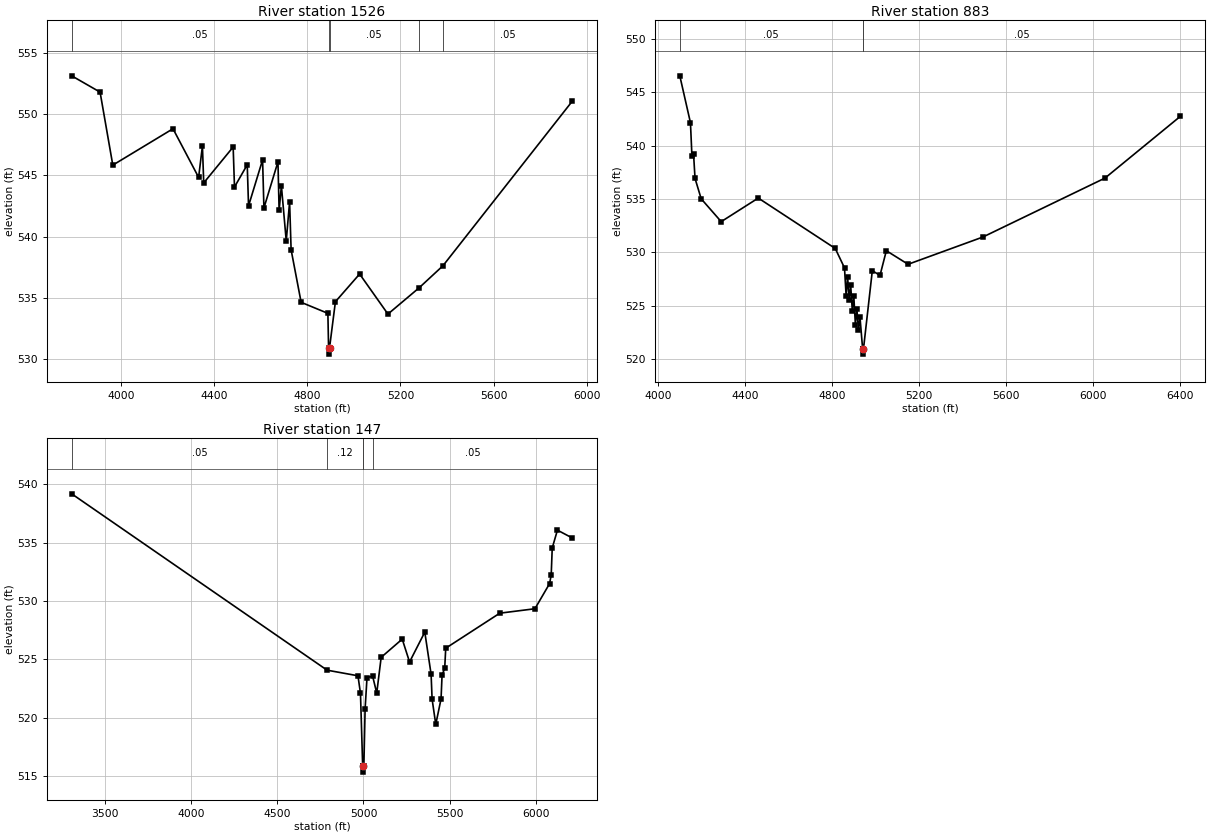
Type RM Length L Ch R = 1,1526,643,643,643
BEGIN DESCRIPTION:
Mapping XS 0c283e22
END DESCRIPTION:
XS GIS Cut Line= 6
      2614605.95      7012497.36      2615024.80      7011707.40
      2615139.21      7011568.65      2615147.02      7011446.26
      2615071.50      7011235.32      2614530.49      7010752.97
#Sta/Elev= 30
  3789.4  553.12  3911.2  551.79  3965.8  545.83  4224.1  548.80  4334.1  544.83
  4350.4  547.39  4356.0  544.38  4482.3  547.31  4488.0  544.04  4542.7  545.86
  4548.3  542.50  4608.6  546.26  4614.3  542.33  4674.6  546.10  4679.5  542.13
  4689.3  544.14  4710.1  539.64  4724.5  542.83  4731.0  538.92  4774.0  534.63
  4888.8  533.73  4891.8  530.90  4892.1  530.40  4895.8  530.90  4921.1  534.68
  5025.0  536.94  5146.5  533.67  5280.1  535.81  5382.4  537.61  5937.6  551.05
#Mann=5,-1,0
  3789.4    0.05       0  4891.8    0.03       0  4895.8    0.05       0
  5280.1     0.1       0  5382.4    0.05       0
Bank Sta=4891.8,4895.8
Exp/Cntr=0.3,0.1

Type RM Length L Ch R = 1,883,736,736,736
BEGIN DESCRIPTION:
Mapping XS b0bd09d9
END DESCRIPTION:
XS GIS Cut Line= 4
      2615104.96      7012208.75      2615709.33      7011543.48
      2615858.88      7011345.82      2614811.36      7010865.86
#Sta/Elev= 30
  4101.2  546.53  4150.1  542.14  4156.9  539.03  4164.3  539.24  4171.1  536.93
  4199.4  535.02  4291.3  532.88  4461.6  535.09  4815.1  530.37  4857.6  528.55
  4865.1  525.92  4871.8  527.70  4879.3  525.57  4886.0  526.91  4893.4  524.54
  4900.2  525.92  4907.6  523.24  4914.4  524.69  4921.8  522.71  4928.6  523.95
  4940.8  520.98  4941.0  520.48  4944.8  520.98  4985.3  528.29  5020.6  527.85
  5049.7  530.16  5149.6  528.89  5493.0  531.44  6054.0  536.96  6400.1  542.74
#Mann=3,-1,0
  4101.2    0.05       0  4940.8    0.03       0  4944.8    0.05       0
Bank Sta=4940.8,4944.8
Exp/Cntr=0.3,0.1

Type RM Length L Ch R = 1,147,0,0,0
BEGIN DESCRIPTION:
Mapping XS dd82964c
END DESCRIPTION:
XS GIS Cut Line= 5
      2614999.54      7010931.76      2616255.92      7011391.50
      2616356.19      7011731.47      2616399.21      7011854.61
      2615482.89      7012428.04
#Sta/Elev= 30
  3307.7  539.17  4789.2  524.07  4968.2  523.59  4982.8  522.09  4995.6  515.84
  4995.9  515.34  4999.6  515.84  5002.4  515.84  5009.7  520.76  5020.7  523.44
  5053.4  523.55  5077.1  522.11  5102.8  525.17  5225.0  526.73  5267.5  524.77
  5355.9  527.33  5392.4  523.73  5398.3  521.59  5419.5  519.43  5450.2  521.61
  5456.1  523.66  5471.4  524.22  5477.3  525.95  5790.9  528.95  5994.8  529.33
  6079.7  531.48  6089.2  532.23  6095.1  534.53  6125.2  536.06  6211.4  535.39
#Mann=5,-1,0
  3307.7    0.05       0  4789.2    0.12       0  4995.6    0.07       0
  4999.6    0.12       0  5053.4    0.05       0
Bank Sta=4995.6,4999.6
Exp/Cntr=0.3,0.1

Chan Stop Cuts=-1