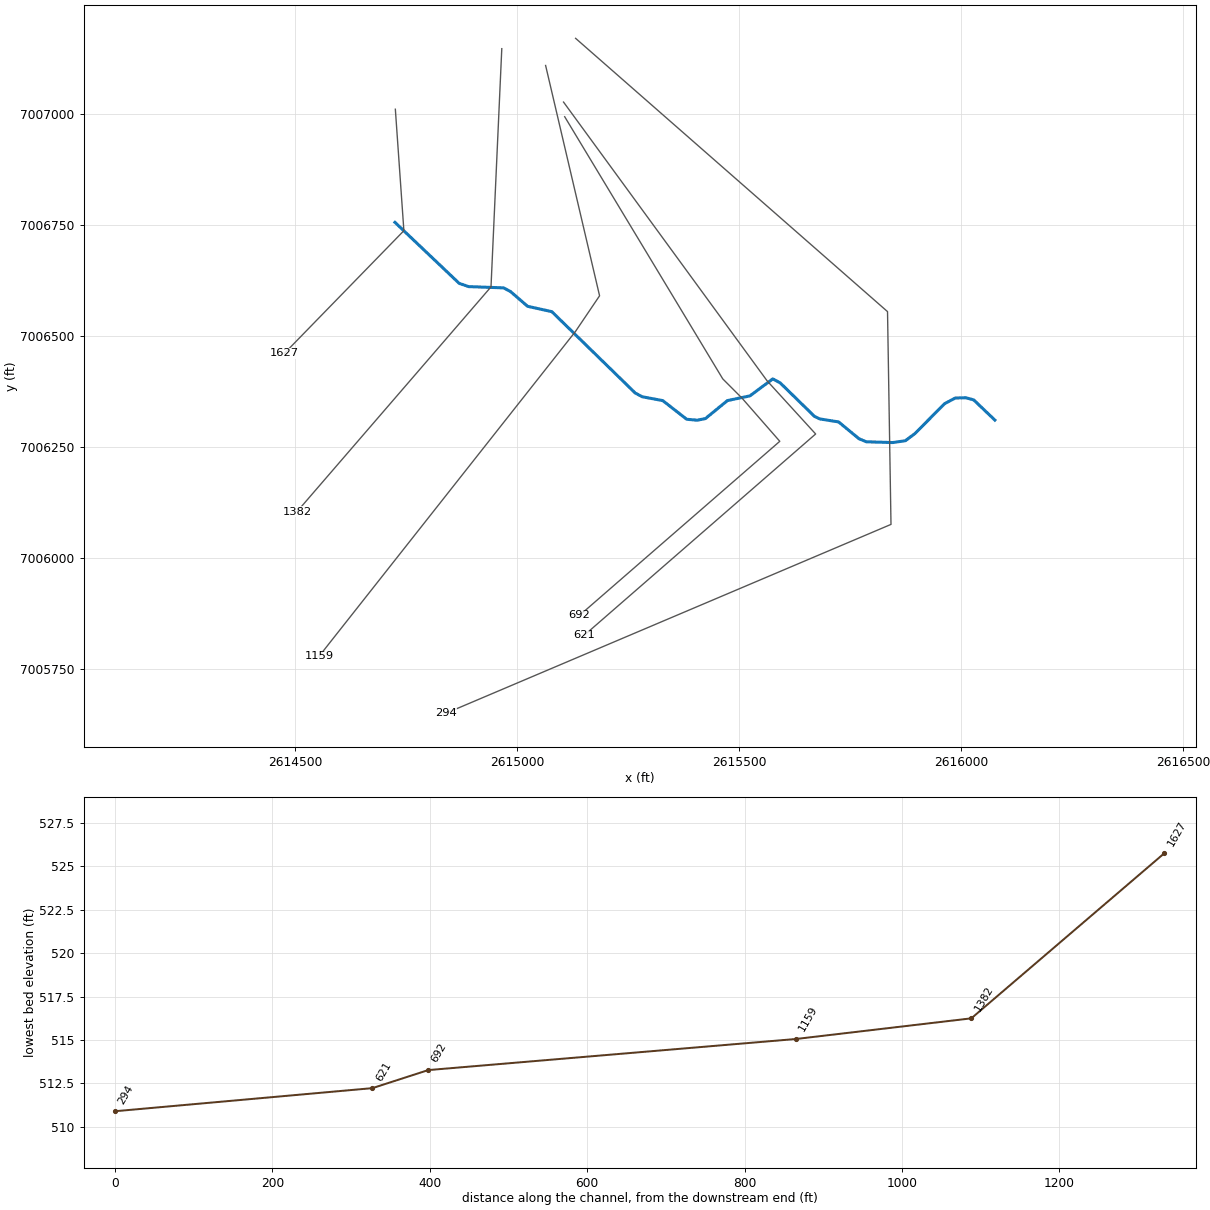
--- Brushy Creek Tributary 12.prj (project) ---

Proj Title=Brushy Creek Tributary 12 Base Level Engineering
Current Plan=p01
Default Exp/Contr=0.3,0.1
English Units
Geom File=g01
Flow File=f01
Plan File=p01
BEGIN DESCRIPTION:
Brushy Creek Tributary 12
END DESCRIPTION:

--- Brushy Creek Tributary 12.p01 (plan) ---

Plan Title=Multiple Run
Short Identifier=Multiple
Geom File=g01
Flow File=f01
Subcritical Flow
K Sum by GR= 0
Std Step Tol= 0.01
Critical Tol= 0.01
Num of Std Step Trials= 20
Max Error Tol= 0.3
Flow Tol Ratio= 0.001
Split Flow NTrial= 30
Split Flow Tol= 0.02
Split Flow Ratio= 0.02
Log Output Level= 0
Friction Slope Method= 1
Unsteady Friction Slope Method= 2
Unsteady Bridges Friction Slope Method= 1
Parabolic Critical Depth
Global Vel Dist=  1 , 1 , 1
Global Log Level= 0
CheckData=True
Encroach Param= -1, 0, 0, 0
BEGIN DESCRIPTION:
Multiple Run
END DESCRIPTION:

--- Brushy Creek Tributary 12.f01 (steady flow) ---

Flow Title=Multiple
Number of Profiles=7
Profile Names=10-year,25-year,50-year,1pct_min,100-year,1pct_plu,500-year
River Rch & RM= Brushy Creek Tri,Reach-1,1627
     376     491     582     343     684    1366     944
Boundary for River Rch & Prof#=Brushy Creek Tri,Reach-1,1
Up Type=0
Dn Type=3
Dn Slope=0.005
Boundary for River Rch & Prof#=Brushy Creek Tri,Reach-1,2
Up Type=0
Dn Type=3
Dn Slope=0.005
Boundary for River Rch & Prof#=Brushy Creek Tri,Reach-1,3
Up Type=0
Dn Type=3
Dn Slope=0.005
Boundary for River Rch & Prof#=Brushy Creek Tri,Reach-1,4
Up Type=0
Dn Type=3
Dn Slope=0.005
Boundary for River Rch & Prof#=Brushy Creek Tri,Reach-1,5
Up Type=0
Dn Type=3
Dn Slope=0.005
Boundary for River Rch & Prof#=Brushy Creek Tri,Reach-1,6
Up Type=0
Dn Type=3
Dn Slope=0.005
Boundary for River Rch & Prof#=Brushy Creek Tri,Reach-1,7
Up Type=0
Dn Type=3
Dn Slope=0.005

--- Brushy Creek Tributary 12.g01 (geometry) ---

Geom Title=Existing Conditions

River Reach=Brushy Creek Tri,Reach-1
Reach XY= 30
      2614725.06      7006756.29      2614869.80      7006618.79
      2614891.21      7006611.51      2614970.03      7006608.67
      2614985.65      7006600.16      2615023.83      7006567.14
      2615078.30      7006555.17      2615266.32      7006371.76
      2615282.03      7006363.49      2615328.19      7006354.82
      2615382.11      7006312.79      2615405.82      7006310.70
      2615424.28      7006314.34      2615473.81      7006354.87
      2615524.37      7006365.43      2615576.08      7006403.70
      2615592.69      7006394.69      2615669.94      7006319.18
      2615682.03      7006313.51      2615724.25      7006306.78
      2615769.95      7006269.04      2615786.55      7006262.08
      2615846.08      7006260.33      2615874.50      7006264.47
      2615896.14      7006280.63      2615962.78      7006347.83
      2615986.55      7006360.50      2616010.57      7006361.32
      2616028.35      7006356.43      2616076.00      7006311.00

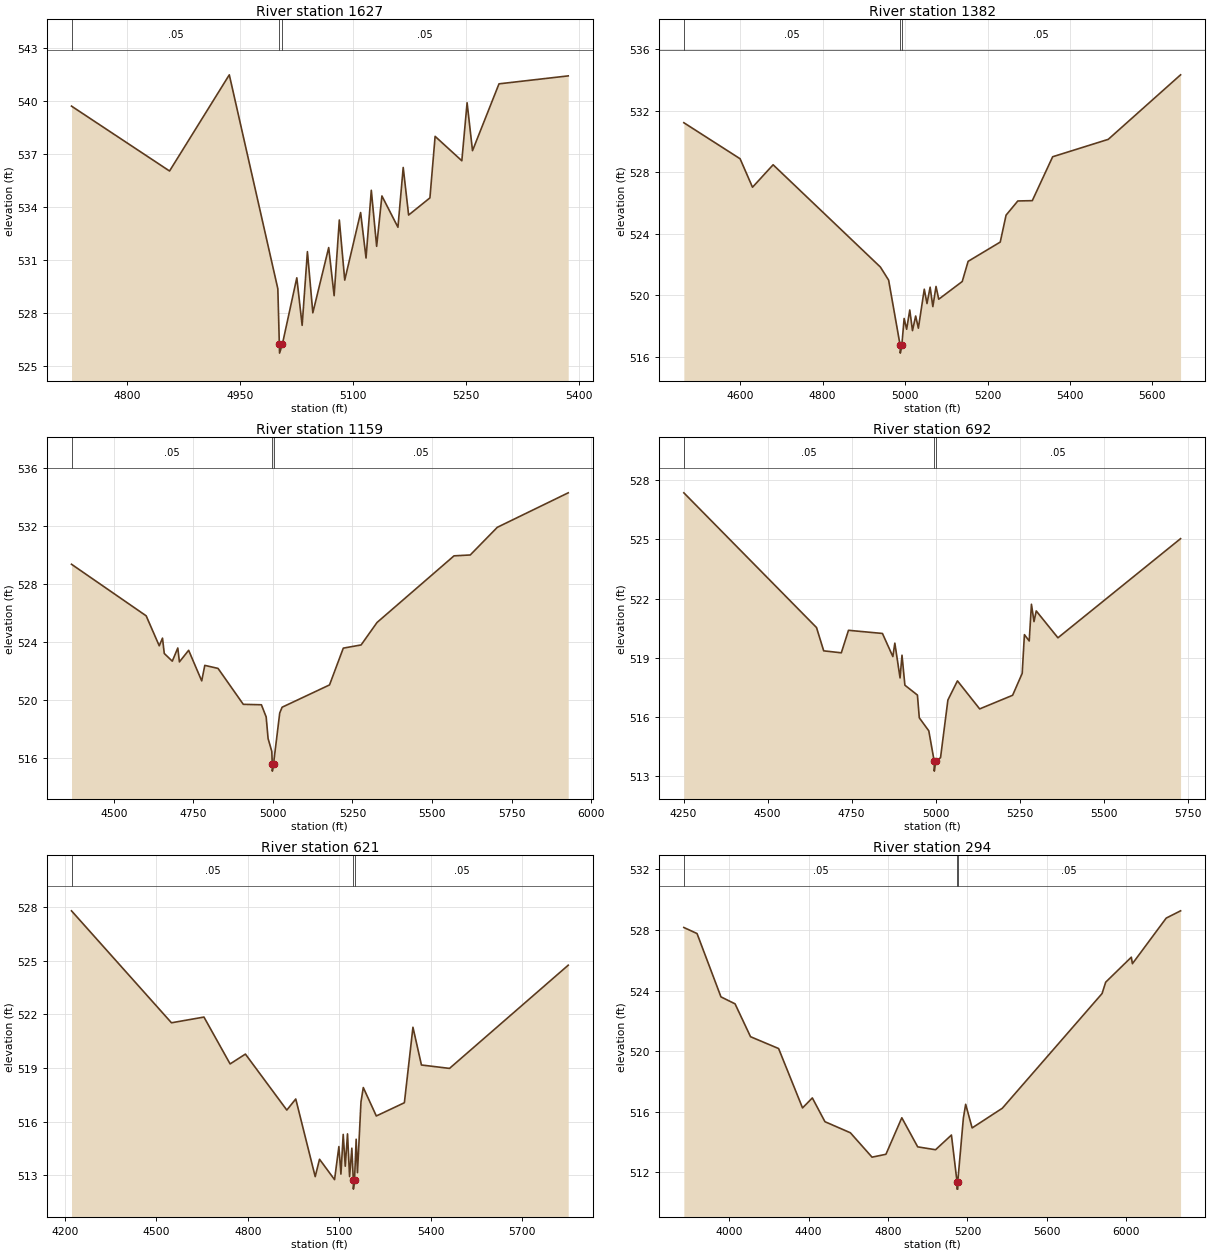
Type RM Length L Ch R = 1,1627,245,245,245
BEGIN DESCRIPTION:
Brushy Creek Tributary 12 2.0
END DESCRIPTION:
XS GIS Cut Line= 3
      2614726.00      7007010.96      2614745.22      7006737.43
      2614475.98      7006460.98
#Sta/Elev= 30
  4725.8  539.72  4856.1  536.05  4935.5  541.49  5000.0  529.39  5002.0  526.25
  5002.3  525.75  5006.0  526.25  5025.2  530.01  5032.3  527.32  5039.3  531.49
  5046.5  528.03  5067.6  531.72  5074.8  529.00  5081.7  533.28  5088.9  529.88
  5110.0  533.70  5117.2  531.13  5124.2  534.96  5131.3  531.79  5138.3  534.64
  5159.6  532.87  5166.6  536.25  5173.8  533.56  5202.1  534.53  5209.0  538.01
  5244.5  536.63  5251.5  539.91  5258.7  537.20  5293.9  540.98  5385.9  541.43
#Mann=3,-1,0
  4725.8    0.05       0  5002.0    0.04       0  5006.0    0.05       0
Bank Sta=5002,5006
Exp/Cntr=0.3,0.1

Type RM Length L Ch R = 1,1382,223,223,223
BEGIN DESCRIPTION:
Mapping XS 70f47e33
END DESCRIPTION:
XS GIS Cut Line= 3
      2614965.70      7007147.39      2614941.40      7006610.89
      2614504.79      7006104.99
#Sta/Elev= 30
  4463.2  531.21  4599.7  528.87  4629.8  527.02  4679.8  528.48  4940.1  521.84
  4960.1  520.99  4988.1  516.75  4988.4  516.25  4992.1  516.75  4997.7  518.50
  5003.8  517.80  5011.4  519.05  5018.0  517.71  5025.7  518.66  5032.3  517.87
  5046.6  520.40  5053.2  519.47  5060.8  520.53  5067.4  519.27  5075.1  520.58
  5081.7  519.75  5138.7  520.90  5153.0  522.21  5230.9  523.46  5245.1  525.21
  5273.6  526.13  5308.7  526.15  5358.1  529.00  5493.0  530.13  5668.5  534.32
#Mann=3,-1,0
  4463.2    0.05       0  4988.1    0.04       0  4992.1    0.05       0
Bank Sta=4988.1,4992.1
Exp/Cntr=0.3,0.1

Type RM Length L Ch R = 1,1159,467,467,467
BEGIN DESCRIPTION:
Mapping XS 9144d8ee
END DESCRIPTION:
XS GIS Cut Line= 4
      2615064.38      7007109.49      2615185.90      7006590.86
      2615131.65      7006510.57      2614554.38      7005779.22
#Sta/Elev= 30
  4366.9  529.34  4601.6  525.78  4642.7  523.71  4652.9  524.24  4658.5  523.18
  4683.7  522.65  4701.0  523.56  4706.1  522.60  4735.1  523.40  4776.2  521.29
  4785.9  522.36  4827.5  522.15  4906.9  519.67  4963.8  519.64  4978.8  518.80
  4984.8  517.31  4996.5  516.42  4997.9  515.56  4998.2  515.06  5001.9  515.56
  5021.4  519.07  5028.8  519.47  5177.9  521.01  5221.2  523.55  5277.2  523.77
  5327.2  525.32  5569.2  529.92  5620.2  529.98  5705.3  531.89  5928.2  534.27
#Mann=3,-1,0
  4366.9    0.05       0  4997.9    0.04       0  5001.9    0.05       0
Bank Sta=4997.9,5001.9
Exp/Cntr=0.3,0.1

Type RM Length L Ch R = 1,692,71,71,71
BEGIN DESCRIPTION:
Mapping XS 845e8c38
END DESCRIPTION:
XS GIS Cut Line= 5
      2615107.34      7006994.10      2615463.26      7006403.79
      2615506.66      7006360.38      2615591.73      7006263.16
      2615140.68      7005871.10
#Sta/Elev= 30
  4250.9  527.36  4645.5  520.54  4666.9  519.36  4719.3  519.26  4740.6  520.40
  4841.6  520.24  4872.6  519.07  4878.5  519.75  4894.0  517.99  4899.8  519.14
  4908.4  517.62  4945.7  517.12  4951.2  515.97  4979.5  515.31  4995.6  513.77
  4995.9  513.27  4999.6  513.77  5014.4  513.95  5036.3  516.87  5064.7  517.84
  5130.8  516.42  5228.8  517.11  5257.3  518.22  5263.9  520.18  5278.2  519.86
  5284.8  521.72  5292.4  520.84  5299.1  521.38  5363.6  520.02  5728.4  525.04
#Mann=3,-1,0
  4250.9    0.05       0  4995.6    0.03       0  4999.6    0.05       0
Bank Sta=4995.6,4999.6
Exp/Cntr=0.3,0.1

Type RM Length L Ch R = 1,621,327,327,327
BEGIN DESCRIPTION:
Mapping XS 1e19ffbd
END DESCRIPTION:
XS GIS Cut Line= 4
      2615104.73      7007027.08      2615563.08      7006399.45
      2615672.46      7006279.65      2615151.59      7005826.50
#Sta/Elev= 30
  4221.2  527.79  4549.2  521.53  4655.8  521.85  4741.6  519.23  4791.8  519.78
  4927.7  516.65  4957.0  517.27  5020.8  512.93  5035.0  513.90  5084.3  512.76
  5098.5  514.61  5105.2  513.07  5112.7  515.29  5119.4  513.51  5126.8  515.32
  5133.6  512.93  5141.0  514.52  5145.8  512.73  5146.1  512.23  5149.8  512.73
  5155.2  515.02  5159.5  513.15  5171.0  517.11  5178.6  517.91  5221.3  516.32
  5313.4  517.06  5341.5  521.28  5369.4  519.17  5461.5  518.98  5851.0  524.75
#Mann=3,-1,0
  4221.2    0.05       0  5145.8    0.03       0  5149.8    0.05       0
Bank Sta=5145.8,5149.8
Exp/Cntr=0.3,0.1

Type RM Length L Ch R = 1,294,0,0,0
BEGIN DESCRIPTION:
Brushy Creek Tributary 12 1.0
END DESCRIPTION:
XS GIS Cut Line= 4
      2615131.92      7007170.61      2615834.34      7006555.21
      2615842.15      7006076.05      2614839.31      7005650.49
#Sta/Elev= 30
  3771.1  528.17  3837.6  527.77  3958.1  523.59  4029.1  523.13  4107.1  520.96
  4248.5  520.18  4369.0  516.26  4418.4  516.92  4482.0  515.35  4610.1  514.62
  4719.2  513.01  4789.2  513.20  4869.2  515.61  4949.2  513.69  5039.2  513.50
  5119.2  514.47  5147.2  511.40  5147.5  510.90  5151.0  510.90  5151.2  511.40
  5179.2  515.57  5190.9  516.50  5223.5  514.94  5375.6  516.24  5878.1  523.81
  5896.3  524.56  6025.5  526.21  6030.9  525.78  6201.2  528.79  6273.6  529.27
#Mann=3,-1,0
  3771.1    0.05       0  5147.2    0.04       0  5151.2    0.05       0
Bank Sta=5147.2,5151.2
Exp/Cntr=0.3,0.1

Chan Stop Cuts=-1