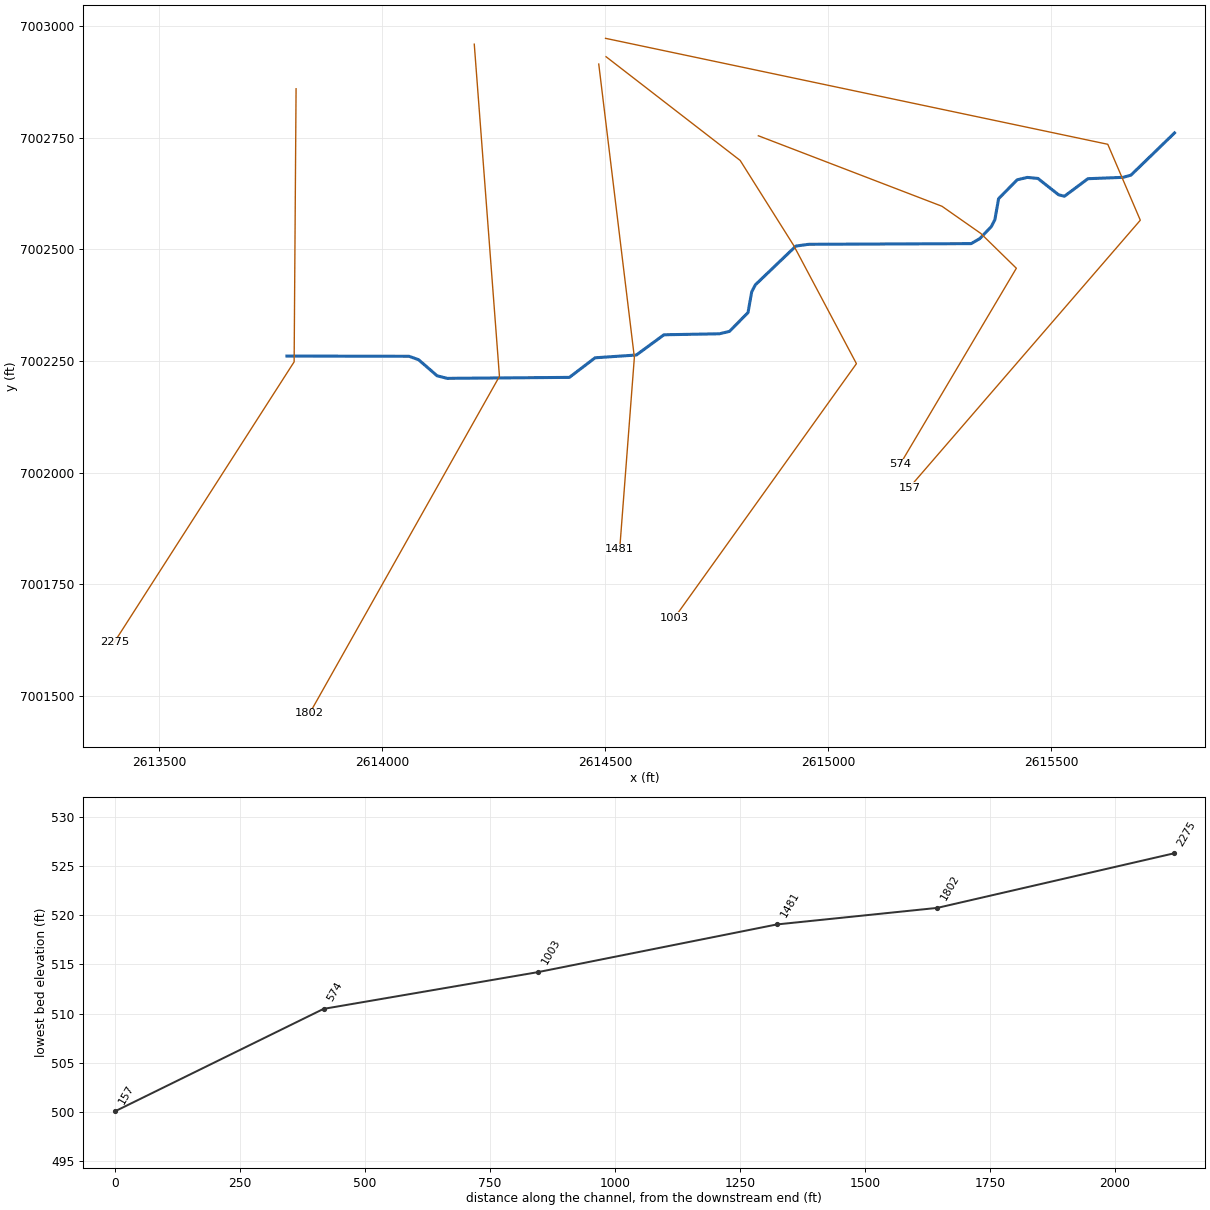
--- Brushy Creek Tributary 13.prj (project) ---

Proj Title=Brushy Creek Tributary 13 Base Level Engineering
Current Plan=p01
Default Exp/Contr=0.3,0.1
English Units
Geom File=g01
Flow File=f01
Plan File=p01
BEGIN DESCRIPTION:
Brushy Creek Tributary 13
END DESCRIPTION:

--- Brushy Creek Tributary 13.p01 (plan) ---

Plan Title=Multiple Run
Short Identifier=Multiple
Geom File=g01
Flow File=f01
Subcritical Flow
K Sum by GR= 0
Std Step Tol= 0.01
Critical Tol= 0.01
Num of Std Step Trials= 20
Max Error Tol= 0.3
Flow Tol Ratio= 0.001
Split Flow NTrial= 30
Split Flow Tol= 0.02
Split Flow Ratio= 0.02
Log Output Level= 0
Friction Slope Method= 1
Unsteady Friction Slope Method= 2
Unsteady Bridges Friction Slope Method= 1
Parabolic Critical Depth
Global Vel Dist=  1 , 1 , 1
Global Log Level= 0
CheckData=True
Encroach Param= -1, 0, 0, 0
BEGIN DESCRIPTION:
Multiple Run
END DESCRIPTION:

--- Brushy Creek Tributary 13.f01 (steady flow) ---

Flow Title=Multiple
Number of Profiles=7
Profile Names=10-year,25-year,50-year,1pct_min,100-year,1pct_plu,500-year
River Rch & RM= Brushy Creek Tri,Reach-1,2275
     201     252     291     167     334     667     438
Boundary for River Rch & Prof#=Brushy Creek Tri,Reach-1,1
Up Type=0
Dn Type=3
Dn Slope=0.005
Boundary for River Rch & Prof#=Brushy Creek Tri,Reach-1,2
Up Type=0
Dn Type=3
Dn Slope=0.005
Boundary for River Rch & Prof#=Brushy Creek Tri,Reach-1,3
Up Type=0
Dn Type=3
Dn Slope=0.005
Boundary for River Rch & Prof#=Brushy Creek Tri,Reach-1,4
Up Type=0
Dn Type=3
Dn Slope=0.005
Boundary for River Rch & Prof#=Brushy Creek Tri,Reach-1,5
Up Type=0
Dn Type=3
Dn Slope=0.005
Boundary for River Rch & Prof#=Brushy Creek Tri,Reach-1,6
Up Type=0
Dn Type=3
Dn Slope=0.005
Boundary for River Rch & Prof#=Brushy Creek Tri,Reach-1,7
Up Type=0
Dn Type=3
Dn Slope=0.005

--- Brushy Creek Tributary 13.g01 (geometry) ---

Geom Title=Existing Conditions

River Reach=Brushy Creek Tri,Reach-1
Reach XY= 30
      2613787.14      7002261.05      2614060.78      7002260.48
      2614082.06      7002252.86      2614123.67      7002216.75
      2614146.03      7002211.07      2614420.06      7002213.26
      2614477.60      7002257.14      2614570.02      7002263.36
      2614631.94      7002308.73      2614756.11      7002310.93
      2614778.70      7002316.36      2614820.26      7002358.43
      2614828.55      7002404.92      2614836.78      7002420.68
      2614927.45      7002507.47      2614955.82      7002511.43
      2615320.33      7002512.98      2615339.67      7002524.23
      2615365.37      7002550.96      2615373.54      7002566.89
      2615381.76      7002613.59      2615423.46      7002655.99
      2615446.06      7002661.37      2615469.91      7002659.04
      2615516.07      7002622.53      2615529.29      7002619.10
      2615581.89      7002658.45      2615660.79      7002661.50
      2615678.45      7002666.46      2615776.00      7002761.00

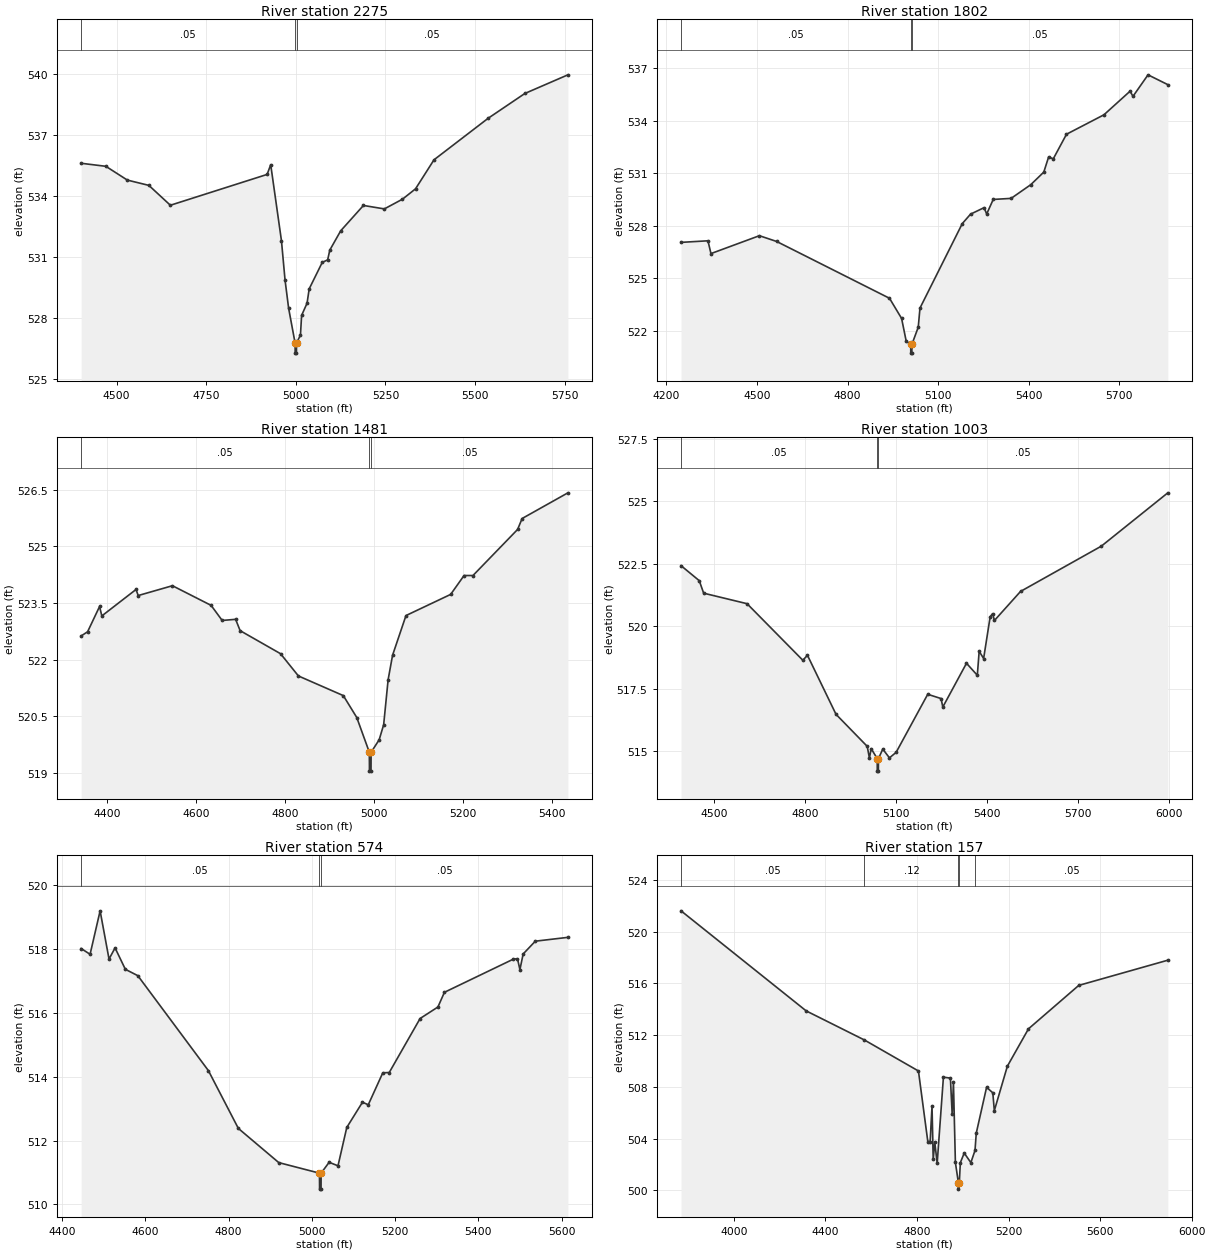
Type RM Length L Ch R = 1,2275,473,473,473
BEGIN DESCRIPTION:
Brushy Creek Tributary 13 3.0
END DESCRIPTION:
XS GIS Cut Line= 3
      2613807.55      7002860.03      2613803.20      7002248.06
      2613400.27      7001619.86
#Sta/Elev= 30
  4401.0  535.62  4470.0  535.47  4530.0  534.79  4590.0  534.53  4650.0  533.55
  4920.0  535.07  4930.0  535.55  4960.0  531.80  4970.0  529.86  4980.0  528.47
  4998.0  526.76  4998.3  526.26  5001.8  526.26  5002.0  526.76  5013.0  527.15
  5016.2  528.12  5031.4  528.72  5037.4  529.43  5073.7  530.73  5088.9  530.86
  5094.9  531.34  5125.3  532.29  5188.7  533.54  5247.1  533.37  5297.7  533.85
  5334.1  534.36  5385.6  535.79  5536.9  537.84  5639.1  539.06  5759.3  539.98
#Mann=3,-1,0
  4401.0    0.05       0  4998.0    0.03       0  5002.0    0.05       0
Bank Sta=4998,5002
Exp/Cntr=0.3,0.1

Type RM Length L Ch R = 1,1802,321,321,321
BEGIN DESCRIPTION:
Mapping XS cf8784ed
END DESCRIPTION:
XS GIS Cut Line= 3
      2614206.85      7002959.96      2614263.28      7002215.55
      2613837.93      7001460.34
#Sta/Elev= 30
  4248.2  527.05  4337.4  527.14  4347.4  526.41  4507.9  527.43  4565.3  527.10
  4939.1  523.86  4979.2  522.71  4994.5  521.41  5009.4  521.23  5009.7  520.73
  5013.2  520.73  5013.4  521.23  5034.4  522.21  5040.1  523.30  5180.3  528.12
  5207.7  528.66  5252.5  529.03  5261.2  528.67  5282.9  529.50  5342.2  529.56
  5407.2  530.34  5450.5  531.06  5466.4  531.92  5482.0  531.82  5525.7  533.22
  5649.9  534.33  5736.6  535.68  5746.0  535.38  5795.9  536.61  5861.5  536.05
#Mann=3,-1,0
  4248.2    0.05       0  5009.4    0.04       0  5013.4    0.05       0
Bank Sta=5009.4,5013.4
Exp/Cntr=0.3,0.1

Type RM Length L Ch R = 1,1481,478,478,478
BEGIN DESCRIPTION:
Mapping XS b26b1ee7
END DESCRIPTION:
XS GIS Cut Line= 3
      2614485.80      7002915.39      2614565.61      7002258.08
      2614532.75      7001828.47
#Sta/Elev= 30
  4342.1  522.63  4356.6  522.74  4383.5  523.41  4388.6  523.16  4465.3  523.86
  4470.3  523.70  4547.1  523.96  4633.9  523.44  4658.8  523.04  4689.0  523.07
  4699.1  522.77  4789.8  522.16  4830.0  521.57  4930.8  521.05  4961.0  520.47
  4989.2  519.55  4989.5  519.05  4993.0  519.05  4993.2  519.55  5011.3  519.88
  5021.4  520.28  5031.4  521.47  5041.4  522.12  5071.5  523.17  5171.8  523.73
  5201.9  524.23  5221.9  524.23  5322.1  525.45  5332.3  525.74  5435.1  526.42
#Mann=3,-1,0
  4342.1    0.05       0  4989.2    0.04       0  4993.2    0.05       0
Bank Sta=4989.2,4993.2
Exp/Cntr=0.3,0.1

Type RM Length L Ch R = 1,1003,429,429,429
BEGIN DESCRIPTION:
Mapping XS 50604295
END DESCRIPTION:
XS GIS Cut Line= 5
      2614502.19      7002931.80      2614802.70      7002699.39
      2614922.41      7002509.25      2615063.25      7002244.00
      2614655.67      7001674.78
#Sta/Elev= 30
  4391.6  522.42  4451.7  521.82  4466.2  521.32  4609.3  520.90  4793.2  518.64
  4808.4  518.84  4902.6  516.48  5005.5  515.20  5012.8  514.73  5018.5  515.11
  5038.5  514.71  5038.7  514.21  5042.2  514.21  5042.5  514.71  5056.8  515.09
  5078.8  514.74  5100.8  514.96  5205.0  517.28  5249.0  517.11  5254.7  516.77
  5332.8  518.52  5368.5  518.04  5374.6  519.00  5389.3  518.71  5410.9  520.38
  5418.8  520.50  5425.0  520.23  5511.0  521.39  5777.5  523.20  5996.6  525.33
#Mann=3,-1,0
  4391.6    0.05       0  5038.5    0.03       0  5042.5    0.05       0
Bank Sta=5038.5,5042.5
Exp/Cntr=0.3,0.1

Type RM Length L Ch R = 1,574,417,417,417
BEGIN DESCRIPTION:
Mapping XS 2696bb3c
END DESCRIPTION:
XS GIS Cut Line= 5
      2614843.45      7002754.68      2615254.93      7002596.69
      2615341.73      7002535.92      2615421.59      7002457.80
      2615161.16      7002018.54
#Sta/Elev= 30
  4446.0  518.01  4467.5  517.83  4491.6  519.19  4513.0  517.68  4527.5  518.03
  4552.2  517.36  4582.2  517.16  4751.6  514.19  4823.6  512.38  4920.7  511.31
  5018.4  510.98  5018.7  510.48  5022.2  510.48  5022.4  510.98  5041.6  511.32
  5062.9  511.21  5084.0  512.41  5121.7  513.20  5135.6  513.12  5170.5  514.12
  5186.0  514.13  5260.1  515.82  5302.9  516.18  5318.5  516.64  5484.4  517.68
  5494.0  517.69  5499.8  517.35  5507.6  517.84  5536.8  518.24  5615.1  518.36
#Mann=3,-1,0
  4446.0    0.05       0  5018.4    0.03       0  5022.4    0.05       0
Bank Sta=5018.4,5022.4
Exp/Cntr=0.3,0.1

Type RM Length L Ch R = 1,157,0,0,0
BEGIN DESCRIPTION:
Brushy Creek Tributary 13 2.0
END DESCRIPTION:
XS GIS Cut Line= 4
      2614501.04      7002973.00      2615626.46      7002735.58
      2615699.37      7002565.44      2615181.98      7001966.45
#Sta/Elev= 30
  3769.0  521.62  4315.7  513.88  4570.0  511.63  4806.3  509.23  4847.2  503.77
  4857.4  503.77  4865.6  506.51  4870.7  502.42  4877.8  503.70  4888.1  502.09
  4915.4  508.75  4945.9  508.68  4953.7  505.87  4959.2  508.35  4967.7  502.15
  4980.8  500.59  4981.0  500.09  4984.8  500.59  4989.4  502.14  5006.3  502.88
  5035.3  502.14  5053.4  503.08  5058.9  504.42  5104.0  507.97  5131.2  507.54
  5137.8  506.16  5194.8  509.60  5287.0  512.49  5506.6  515.85  5895.8  517.80
#Mann=5,-1,0
  3769.0    0.05       0  4570.0    0.12       0  4980.8    0.07       0
  4984.8    0.12       0  5053.4    0.05       0
Bank Sta=4980.8,4984.8
Exp/Cntr=0.3,0.1

Chan Stop Cuts=-1