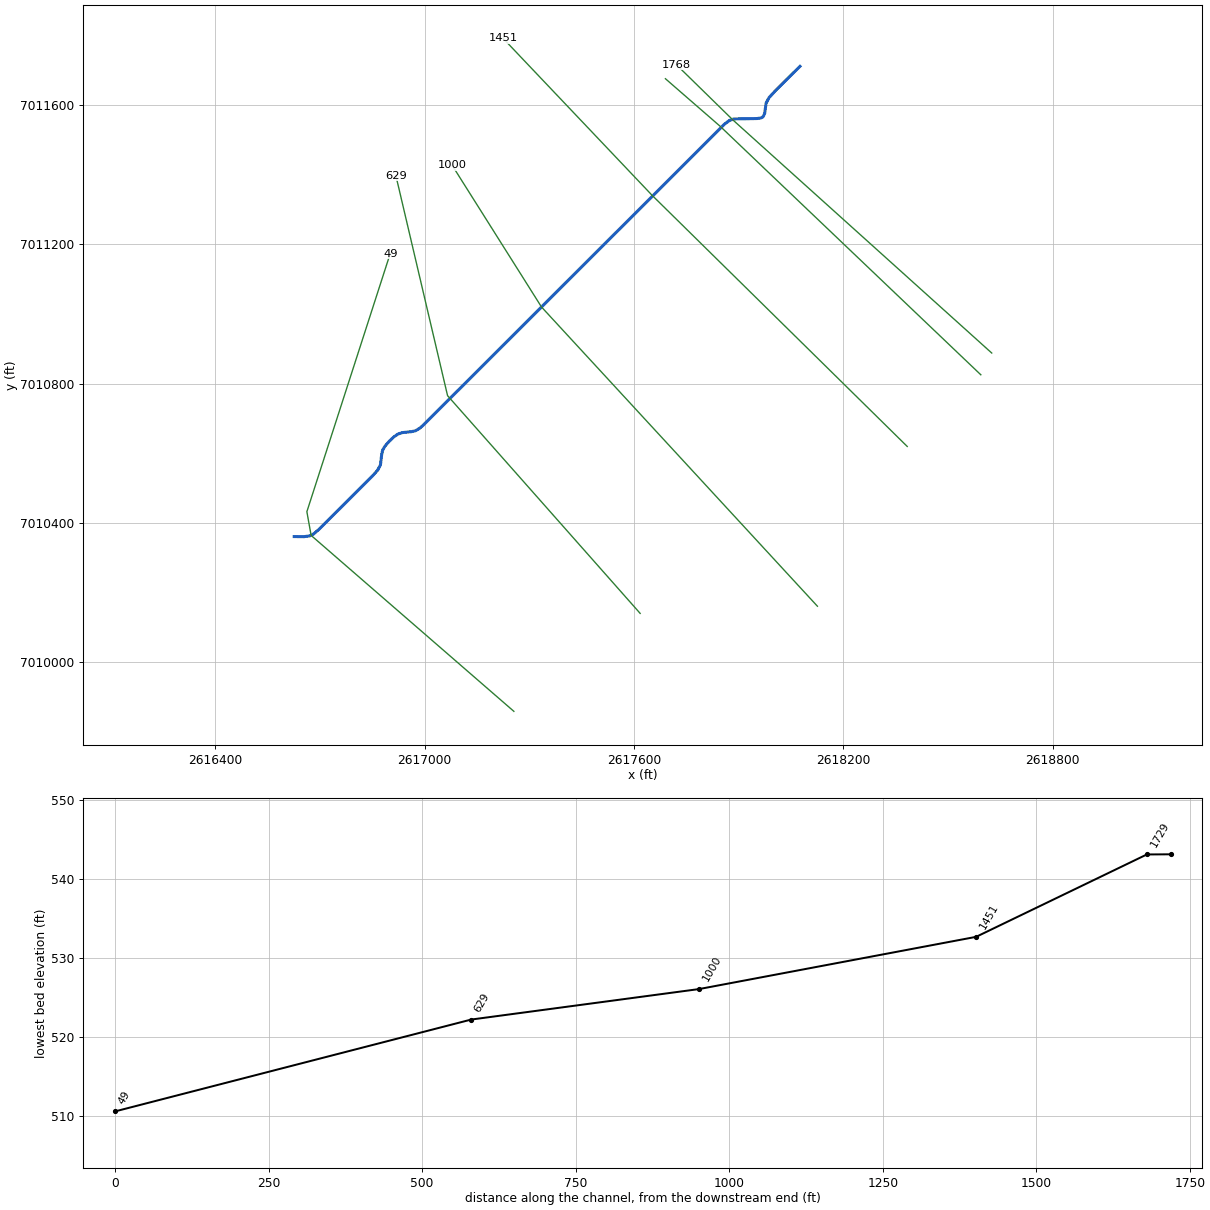
--- Brushy Creek Tributary 14.prj (project) ---

Proj Title=Brushy Creek Tributary 14 Base Level Engineering
Current Plan=p01
Default Exp/Contr=0.3,0.1
English Units
Geom File=g01
Flow File=f01
Plan File=p01
Y Axis Title=Elevation
X Axis Title(PF)=Main Channel Distance
X Axis Title(XS)=Station
BEGIN DESCRIPTION:
Brushy Creek Tributary 14
END DESCRIPTION:
DSS Export Rating Curves= 0
DSS Export Rating Curve Sorted= 0
DSS Export Volume Flow Curves= 0
DXF OffsetX= 0
DXF OffsetY= 0
DXF ScaleX= 1
DXF ScaleY= 10

--- Brushy Creek Tributary 14.p01 (plan) ---

Plan Title=Multiple Run
Short Identifier=Multiple
Geom File=g01
Flow File=f01
Subcritical Flow
K Sum by GR= 0
Std Step Tol= 0.01
Critical Tol= 0.01
Num of Std Step Trials= 20
Max Error Tol= 0.3
Flow Tol Ratio= 0.001
Split Flow NTrial= 30
Split Flow Tol= 0.02
Split Flow Ratio= 0.02
Log Output Level= 0
Friction Slope Method= 1
Unsteady Friction Slope Method= 2
Unsteady Bridges Friction Slope Method= 1
Parabolic Critical Depth
Global Vel Dist=  1 , 1 , 1
Global Log Level= 0
CheckData=True
Encroach Param= -1, 0, 0, 0
BEGIN DESCRIPTION:
Multiple Run
END DESCRIPTION:

--- Brushy Creek Tributary 14.f01 (steady flow) ---

Flow Title=Multiple
Number of Profiles=7
Profile Names=10-year,25-year,50-year,1pct_min,100-year,1pct_plu,500-year
River Rch & RM= Brushy Creek Tri,Reach-1,1768
     140     172     195     111     221     441     282
River Rch & RM= Brushy Creek Tri,Reach-1,49
    1896    2675    3333    2050    4091    8163    6170
Boundary for River Rch & Prof#=Brushy Creek Tri,Reach-1,1
Up Type=0
Dn Type=3
Dn Slope=0.005
Boundary for River Rch & Prof#=Brushy Creek Tri,Reach-1,2
Up Type=0
Dn Type=3
Dn Slope=0.005
Boundary for River Rch & Prof#=Brushy Creek Tri,Reach-1,3
Up Type=0
Dn Type=3
Dn Slope=0.005
Boundary for River Rch & Prof#=Brushy Creek Tri,Reach-1,4
Up Type=0
Dn Type=3
Dn Slope=0.005
Boundary for River Rch & Prof#=Brushy Creek Tri,Reach-1,5
Up Type=0
Dn Type=3
Dn Slope=0.005
Boundary for River Rch & Prof#=Brushy Creek Tri,Reach-1,6
Up Type=0
Dn Type=3
Dn Slope=0.005
Boundary for River Rch & Prof#=Brushy Creek Tri,Reach-1,7
Up Type=0
Dn Type=3
Dn Slope=0.005

--- Brushy Creek Tributary 14.g01 (geometry) ---

Geom Title=Existing Conditions
Program Version=4.10

River Reach=Brushy Creek Tri,Reach-1
Reach XY= 30
        2618076.        7011711.      2618005.57      7011641.07
      2617986.85      7011620.38      2617978.83      7011604.88
      2617974.75      7011575.62      2617970.54      7011566.25
      2617964.82      7011562.95      2617953.25      7011561.01
      2617886.59      7011559.79      2617873.63      7011555.45
      2617859.27      7011544.53      2616996.08      7010680.79
      2616985.66      7010671.79      2616974.32      7010664.99
      2616961.88      7010662.05      2616935.64      7010659.36
      2616923.46      7010655.25      2616912.44      7010647.51
      2616898.86      7010634.84      2616886.65        7010621.
      2616879.89      7010609.57      2616876.98      7010597.07
      2616873.34      7010566.68      2616865.21      7010551.34
       2616849.7      7010534.18      2616696.09      7010380.78
      2616682.21      7010368.76      2616670.33       7010362.8
      2616653.74      7010360.68        2616626.        7010361.

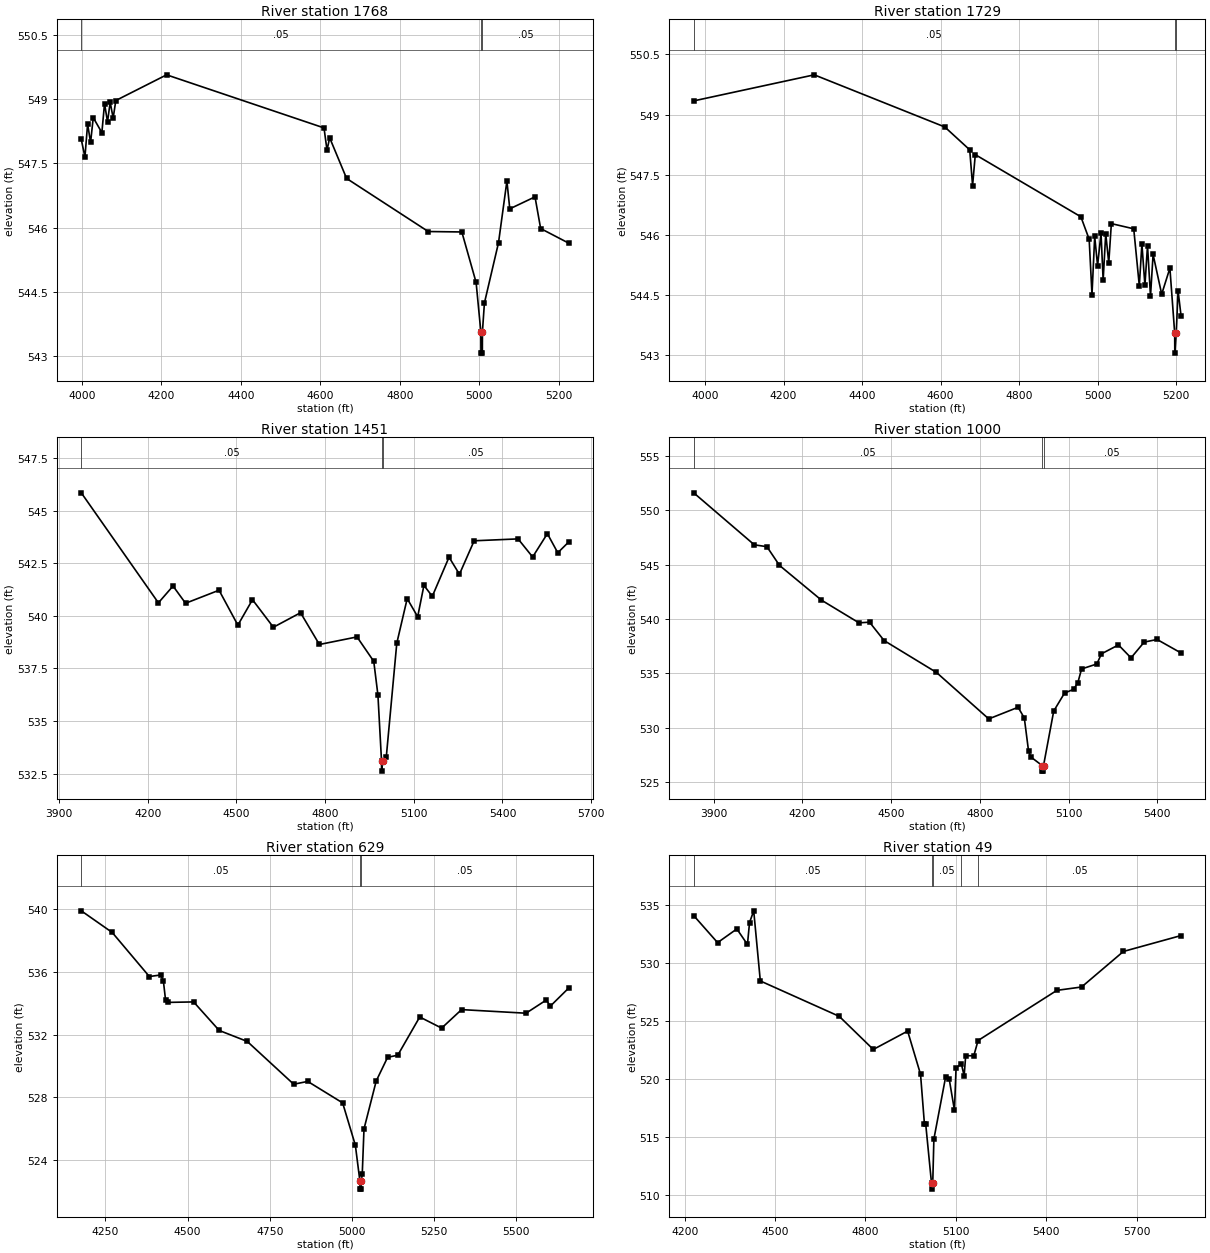
Type RM Length L Ch R = 1 ,1768    ,39,39,39
BEGIN DESCRIPTION:
Mapping XS a14d6975
END DESCRIPTION:
XS GIS Cut Line= 3
      2618625.65      7010887.86      2617883.47      7011557.13
      2617721.39      7011715.95
#Sta/Elev= 30
  3998.3  548.06  4007.5  547.65  4014.2  548.42  4021.7  547.99  4028.4  548.57
  4050.1  548.22  4056.8   548.9  4064.3  548.47    4071  548.93  4078.5  548.56
  4085.2  548.97    4213  549.57  4609.1  548.33  4616.6  547.81  4623.3   548.1
  4665.9  547.15  4871.4  545.91  4955.9   545.9  4991.8  544.72  5003.7  543.57
    5004  543.07  5007.5  543.07  5007.7  543.57  5012.7  544.24  5048.2  545.65
  5069.3  547.09  5076.5  546.44    5140  546.72  5154.2  545.98  5224.6  545.64
#Mann= 3 ,-1 , 0
  3998.3     .05       0  5003.7     .03       0  5007.7     .05       0
Bank Sta=5003.7,5007.7
XS Rating Curve= 0 ,0
Exp/Cntr=0.3,0.1

Type RM Length L Ch R = 1 ,1729    ,278,278,278
BEGIN DESCRIPTION:
Mapping XS 757697f5
END DESCRIPTION:
XS GIS Cut Line= 3
      2618594.41      7010825.36      2617847.01       7011538.9
      2617690.26      7011675.29
#Sta/Elev= 30
  3971.1  549.34  4278.1  549.99  4610.5  548.69    4674  548.12  4681.3  547.23
  4688.2     548  4957.1  546.45  4978.2  545.89  4985.4  544.51  4992.3  545.96
  4999.6  545.23  5008.4  546.04  5013.8  544.87  5020.4  546.03  5028.1   545.3
  5034.7  546.28  5091.7  546.15  5105.9  544.73  5112.5  545.77  5120.2  544.74
  5126.8  545.73  5134.4  544.47    5141  545.51  5162.9  544.52  5183.8  545.17
    5196  543.55  5196.3  543.05    5200  543.55  5204.6  544.61  5212.2  543.98
#Mann= 3 ,-1 , 0
  3971.1     .05       0    5196     .03       0    5200     .05       0
Bank Sta=5196,5200
XS Rating Curve= 0 ,0
Exp/Cntr=0.3,0.1

Type RM Length L Ch R = 1 ,1451    ,451,451,451
BEGIN DESCRIPTION:
Mapping XS 4e4dbcdc
END DESCRIPTION:
XS GIS Cut Line= 3
      2618383.45      7010619.64       2617651.7      7011340.98
      2617224.62       7011791.5
#Sta/Elev= 30
  3975.5  545.85  4236.3  540.62  4285.8  541.42  4328.2   540.6  4441.4  541.22
  4505.1  539.56  4554.5  540.77  4625.2  539.46  4717.1  540.15  4780.8  538.64
  4908.1     539  4964.7  537.84  4978.8  536.24  4990.9  533.12  4991.2  532.62
  4994.9  533.12    5007  533.28  5042.6   538.7  5077.8  540.82  5113.3  539.96
  5134.4  541.45  5162.7  540.93  5219.3  542.79  5254.5  541.98  5304.3  543.57
  5452.8  543.66  5502.1   542.8  5551.9  543.91  5587.1     543  5623.8  543.51
#Mann= 3 ,-1 , 0
  3975.5     .05       0  4990.9     .04       0  4994.9     .05       0
Bank Sta=4990.9,4994.9
XS Rating Curve= 0 ,0
Exp/Cntr=0.3,0.1

Type RM Length L Ch R = 1 ,1000    ,371,371,371
BEGIN DESCRIPTION:
Brushy Creek Tributary 17 2.0
END DESCRIPTION:
XS GIS Cut Line= 3
      2618125.99      7010161.01      2617335.03      7011020.03
      2617079.08      7011426.45
#Sta/Elev= 30
  3832.3  551.59  4037.3  546.81  4079.8  546.64  4122.4  544.92  4264.1  541.73
  4391.2  539.64  4426.9   539.7  4476.2  538.01  4653.2  535.08  4830.1  530.81
  4929.3  531.88  4950.3  530.89  4964.5  527.88  4971.9  527.32  5011.2  526.51
  5011.5  526.01    5015  526.01  5015.2  526.51  5049.7  531.53  5086.2  533.18
  5116.8  533.53  5131.1  534.12  5143.9   535.4  5195.7  535.86    5211  536.79
  5268.7  537.61  5311.1  536.42  5355.7  537.87  5399.3  538.11  5480.3  536.87
#Mann= 3 ,-1 , 0
  3832.3     .05       0  5011.2     .05       0  5015.2     .05       0
Bank Sta=5011.2,5015.2
XS Rating Curve= 0 ,0
Exp/Cntr=0.3,0.1

Type RM Length L Ch R = 1 ,629     ,580,580,580
BEGIN DESCRIPTION:
Mapping XS 30ccfb5d
END DESCRIPTION:
XS GIS Cut Line= 3
      2617617.86      7010140.44      2617065.76      7010765.46
      2616917.58      7011397.17
#Sta/Elev= 30
  4176.5   539.9  4270.6  538.52  4383.6  535.71  4418.8  535.81  4426.3  535.42
    4433   534.2  4440.5  534.06  4518.3  534.09  4596.1  532.27  4681.5  531.57
  4822.8  528.84  4865.5  529.02  4971.7  527.65  5010.4  524.95  5024.3  522.65
  5024.5  522.15    5028  522.15  5028.3  522.65  5031.4  523.13  5036.7  525.99
  5073.9  529.05  5108.6  530.56  5139.4  530.69  5206.3  533.13  5272.9  532.42
  5333.6   533.6  5529.7  533.37  5591.3  534.21  5603.6  533.82  5659.3  534.97
#Mann= 3 ,-1 , 0
  4176.5     .05       0  5024.3      .1       0  5028.3     .05       0
Bank Sta=5024.3,5028.3
XS Rating Curve= 0 ,0
Exp/Cntr=0.3,0.1

Type RM Length L Ch R = 1 ,49      ,0,0,0
BEGIN DESCRIPTION:
Brushy Creek Tributary 17 1.0
END DESCRIPTION:
XS GIS Cut Line= 4
      2617255.86      7009859.21      2616674.64      7010364.27
      2616662.44      7010432.38      2616901.35      7011173.22
#Sta/Elev= 30
    4230  534.08  4309.3  531.75  4373.2  532.93  4408.4  531.59  4415.3  533.48
  4429.2  534.49  4451.1  528.45  4713.2   525.4  4826.1  522.55  4940.1  524.13
  4982.9  520.41  4995.8  516.14    5000  516.14  5019.4  511.02  5019.6  510.52
  5023.4  511.02  5027.2  514.83  5065.9  520.14  5078.2  519.98  5095.5  517.31
  5100.8  520.97  5118.6   521.3  5127.6  520.27  5132.8  522.02  5159.6     522
  5173.9  523.32  5435.5  527.64  5517.5  527.93  5656.2  530.99  5847.6  532.36
#Mann= 5 ,-1 , 0
    4230     .05       0  5019.4      .1       0  5023.4     .05       0
  5118.6     .12       0  5173.9     .05       0
Bank Sta=5019.4,5023.4
XS Rating Curve= 0 ,0
Exp/Cntr=0.3,0.1

Chan Stop Cuts=-1
Use User Specified Reach Order=0
Composite Channel Slope=5