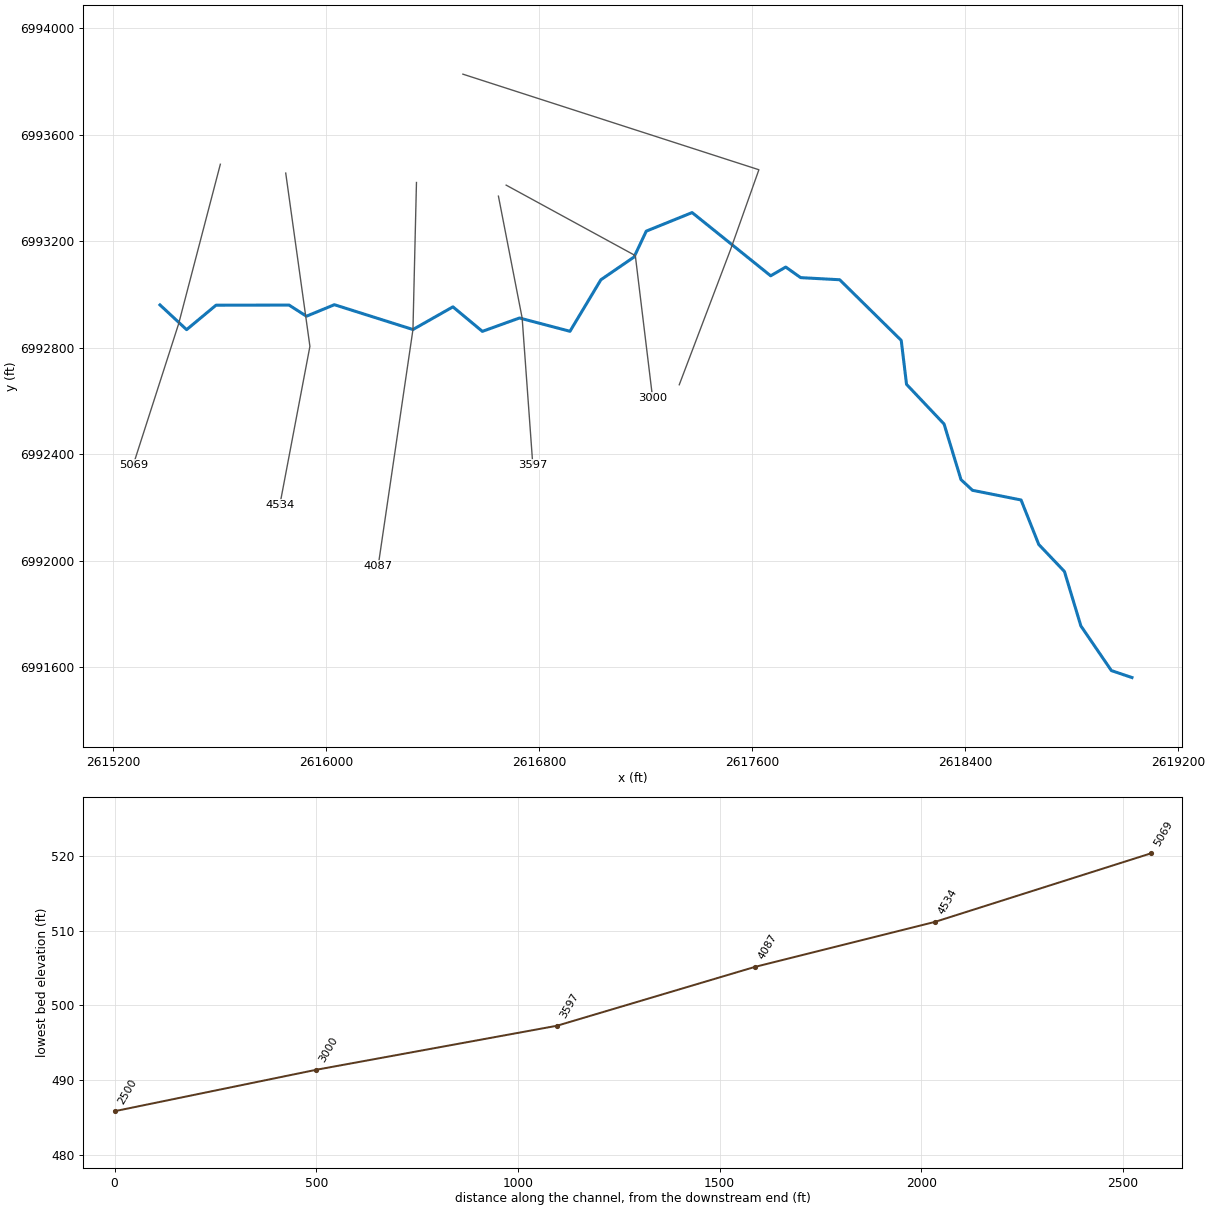
--- Brushy Creek Tributary 15.prj (project) ---

Proj Title=Brushy Creek Tributary 15 Base Level Engineering
Current Plan=p01
Default Exp/Contr=0.3,0.1
English Units
Geom File=g01
Flow File=f01
Plan File=p01
BEGIN DESCRIPTION:
Brushy Creek Tributary 15
END DESCRIPTION:

--- Brushy Creek Tributary 15.p01 (plan) ---

Plan Title=Multiple Run
Short Identifier=Multiple
Geom File=g01
Flow File=f01
Subcritical Flow
K Sum by GR= 0
Std Step Tol= 0.01
Critical Tol= 0.01
Num of Std Step Trials= 20
Max Error Tol= 0.3
Flow Tol Ratio= 0.001
Split Flow NTrial= 30
Split Flow Tol= 0.02
Split Flow Ratio= 0.02
Log Output Level= 0
Friction Slope Method= 1
Unsteady Friction Slope Method= 2
Unsteady Bridges Friction Slope Method= 1
Parabolic Critical Depth
Global Vel Dist=  1 , 1 , 1
Global Log Level= 0
CheckData=True
Encroach Param= -1, 0, 0, 0
BEGIN DESCRIPTION:
Multiple Run
END DESCRIPTION:

--- Brushy Creek Tributary 15.f01 (steady flow) ---

Flow Title=Multiple
Number of Profiles=7
Profile Names=10-year,25-year,50-year,1pct_min,100-year,1pct_plu,500-year
River Rch & RM= Brushy Creek Tri,Reach-1,5069
     216     272     314     181     361     720     475
Boundary for River Rch & Prof#=Brushy Creek Tri,Reach-1,1
Up Type=0
Dn Type=3
Dn Slope=0.005
Boundary for River Rch & Prof#=Brushy Creek Tri,Reach-1,2
Up Type=0
Dn Type=3
Dn Slope=0.005
Boundary for River Rch & Prof#=Brushy Creek Tri,Reach-1,3
Up Type=0
Dn Type=3
Dn Slope=0.005
Boundary for River Rch & Prof#=Brushy Creek Tri,Reach-1,4
Up Type=0
Dn Type=3
Dn Slope=0.005
Boundary for River Rch & Prof#=Brushy Creek Tri,Reach-1,5
Up Type=0
Dn Type=3
Dn Slope=0.005
Boundary for River Rch & Prof#=Brushy Creek Tri,Reach-1,6
Up Type=0
Dn Type=3
Dn Slope=0.005
Boundary for River Rch & Prof#=Brushy Creek Tri,Reach-1,7
Up Type=0
Dn Type=3
Dn Slope=0.005

--- Brushy Creek Tributary 15.g01 (geometry) ---

Geom Title=Existing Conditions

River Reach=Brushy Creek Tri,Reach-1
Reach XY= 30
      2615376.00      6992961.00      2615475.99      6992867.98
      2615586.43      6992959.94      2615860.84      6992960.34
      2615926.00      6992918.56      2616031.02      6992961.78
      2616326.01      6992868.53      2616476.08      6992953.70
      2616586.62      6992861.61      2616726.00      6992911.81
      2616915.67      6992861.87      2617031.59      6993055.39
      2617156.22      6993140.88      2617202.16      6993238.15
      2617374.36      6993307.88      2617669.34      6993070.31
      2617725.90      6993103.19      2617781.86      6993063.46
      2617928.45      6993055.53      2618159.57      6992827.76
      2618179.54      6992662.47      2618320.48      6992513.43
      2618384.00      6992304.61      2618427.25      6992264.45
      2618609.56      6992228.15      2618676.00      6992061.00
      2618772.44      6991959.52      2618834.16      6991754.95
      2618948.73      6991587.15      2619026.00      6991561.00

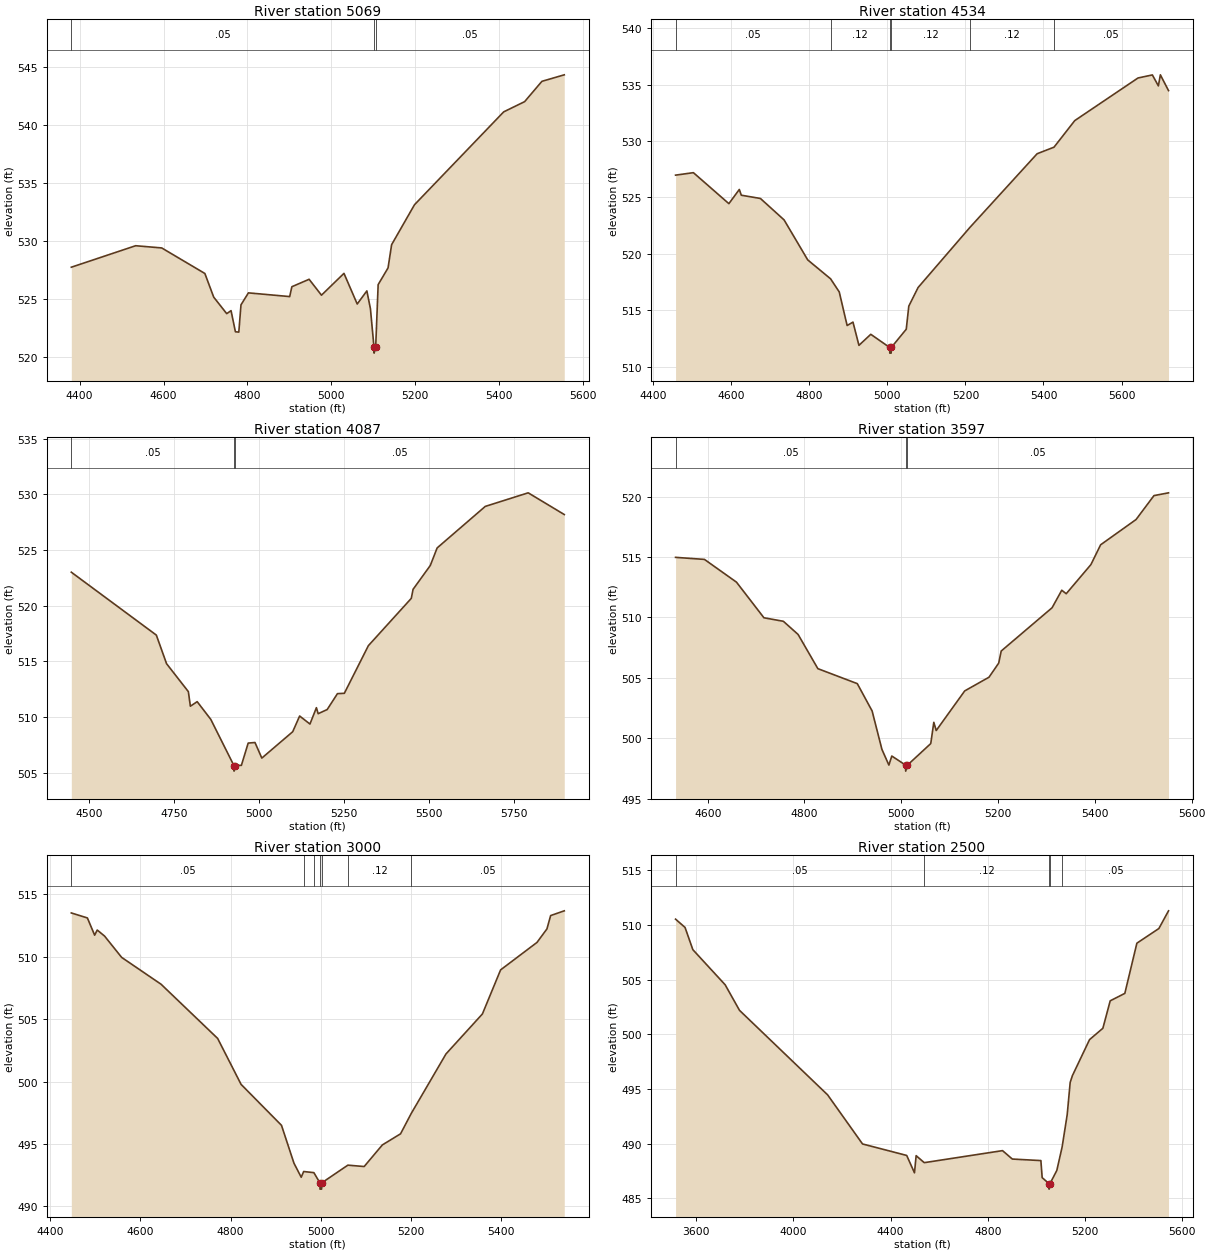
Type RM Length L Ch R = 1,5069,535,535,535
BEGIN DESCRIPTION:
Brushy Creek Tributary 15 10.0
END DESCRIPTION:
XS GIS Cut Line= 3
      2615602.69      6993489.46      2615446.00      6992889.79
      2615276.01      6992361.04
#Sta/Elev= 30
  4380.2  527.76  4533.6  529.61  4595.7  529.42  4698.6  527.22  4719.7  525.18
  4750.7  523.76  4761.0  524.02  4771.4  522.20  4779.5  522.17  4784.7  524.52
  4802.4  525.55  4900.8  525.23  4906.0  526.08  4947.1  526.72  4976.6  525.35
  5030.2  527.23  5061.8  524.59  5084.8  525.72  5093.3  524.18  5101.8  520.86
  5102.0  520.36  5105.8  520.86  5111.7  526.26  5135.3  527.70  5143.8  529.70
  5198.3  533.14  5411.0  541.14  5460.9  542.02  5502.1  543.77  5555.4  544.33
#Mann=3,-1,0
  4380.2    0.05       0  5101.8    0.03       0  5105.8    0.05       0
Bank Sta=5101.8,5105.8
Exp/Cntr=0.3,0.1

Type RM Length L Ch R = 1,4534,447,447,447
BEGIN DESCRIPTION:
Brushy Creek Tributary 15 9.0
END DESCRIPTION:
XS GIS Cut Line= 3
      2615848.22      6993456.30      2615939.05      6992805.34
      2615826.20      6992210.31
#Sta/Elev= 30
  4457.5  526.98  4503.2  527.20  4594.1  524.45  4620.8  525.71  4625.9  525.20
  4674.9  524.91  4735.5  523.01  4796.1  519.46  4854.7  517.78  4876.8  516.62
  4897.0  513.64  4912.0  513.94  4927.3  511.88  4957.6  512.86  5006.1  511.69
  5006.3  511.19  5009.8  511.19  5010.1  511.69  5048.5  513.31  5055.0  515.36
  5078.8  517.01  5211.5  522.34  5383.8  528.88  5427.0  529.46  5480.2  531.82
  5642.2  535.60  5679.0  535.87  5694.4  534.90  5699.5  535.88  5720.4  534.48
#Mann=6,-1,0
  4457.5    0.05       0  4854.7    0.12       0  5006.1    0.07       0
  5010.1    0.12       0  5211.5    0.12       0  5427.0    0.05       0
Bank Sta=5006.1,5010.1
Exp/Cntr=0.3,0.1

Type RM Length L Ch R = 1,4087,490,490,490
BEGIN DESCRIPTION:
Brushy Creek Tributary 15 8.0
END DESCRIPTION:
XS GIS Cut Line= 3
      2616339.18      6993420.97      2616326.01      6992868.53
      2616195.55      6991981.17
#Sta/Elev= 30
  4447.4  523.02  4697.4  517.37  4727.5  514.80  4791.6  512.29  4797.5  510.98
  4817.5  511.39  4857.5  509.80  4925.5  505.65  4925.8  505.15  4929.5  505.65
  4947.5  505.67  4967.5  507.67  4987.5  507.72  5007.6  506.32  5098.4  508.69
  5118.8  510.10  5149.1  509.38  5168.1  510.85  5173.2  510.31  5199.7  510.68
  5230.0  512.11  5250.2  512.14  5320.9  516.42  5447.1  520.67  5452.3  521.48
  5502.9  523.62  5523.1  525.20  5664.6  528.93  5790.8  530.15  5896.9  528.20
#Mann=3,-1,0
  4447.4    0.05       0  4925.5    0.03       0  4929.5    0.05       0
Bank Sta=4925.5,4929.5
Exp/Cntr=0.3,0.1

Type RM Length L Ch R = 1,3597,597,597,597
BEGIN DESCRIPTION:
Brushy Creek Tributary 15 7.0
END DESCRIPTION:
XS GIS Cut Line= 3
      2616646.98      6993369.59      2616736.05      6992911.77
      2616776.00      6992361.02
#Sta/Elev= 30
  4533.6  514.97  4593.3  514.80  4659.4  512.92  4716.2  509.97  4756.3  509.68
  4786.8  508.59  4827.6  505.76  4909.1  504.52  4939.7  502.26  4960.0  499.08
  4974.4  497.78  4980.4  498.53  5008.8  497.78  5009.1  497.28  5012.8  497.78
  5060.9  499.56  5067.2  501.32  5072.2  500.64  5131.1  503.92  5181.2  505.05
  5201.3  506.22  5206.5  507.22  5311.6  510.80  5331.6  512.25  5340.8  511.96
  5391.8  514.37  5411.9  516.01  5485.1  518.10  5522.1  520.08  5552.2  520.31
#Mann=3,-1,0
  4533.6    0.05       0  5008.8    0.03       0  5012.8    0.05       0
Bank Sta=5008.8,5012.8
Exp/Cntr=0.3,0.1

Type RM Length L Ch R = 1,3000,500,500,500
BEGIN DESCRIPTION:
Brushy Creek Tributary 15 6.0
END DESCRIPTION:
XS GIS Cut Line= 3
      2616676.00      6993411.00      2617161.06      6993146.27
      2617226.00      6992610.99
#Sta/Elev= 30
  4447.4  513.50  4483.0  513.10  4499.1  511.72  4504.8  512.13  4521.0  511.65
  4558.9  509.94  4646.2  507.79  4771.5  503.45  4823.4  499.77  4912.9  496.49
  4940.5  493.46  4956.6  492.33  4962.0  492.79  4984.6  492.70  4998.0  491.88
  4998.2  491.38  5001.7  491.38  5002.0  491.88  5059.9  493.30  5096.0  493.19
  5136.3  494.92  5176.6  495.81  5200.4  497.45  5277.3  502.21  5357.9  505.41
  5398.2  508.94  5478.8  511.14  5500.8  512.22  5509.0  513.29  5539.2  513.67
#Mann=7,-1,0
  4447.4    0.05       0  4962.0    0.12       0  4984.6    0.05       0
  4998.0    0.03       0  5002.0    0.05       0  5059.9    0.12       0
  5200.4    0.05       0
Bank Sta=4998,5002
Exp/Cntr=0.3,0.1

Type RM Length L Ch R = 1,2500,0,0,0
BEGIN DESCRIPTION:
Brushy Creek Tributary 15 5.0
END DESCRIPTION:
XS GIS Cut Line= 4
      2616513.56      6993827.91      2617625.07      6993468.81
      2617519.01      6993169.84      2617326.01      6992661.01
#Sta/Elev= 30
  3514.7  510.52  3553.7  509.76  3585.8  507.73  3719.1  504.51  3777.9  502.18
  4140.7  494.45  4284.4  489.96  4466.3  488.91  4498.3  487.32  4505.1  488.89
  4538.5  488.25  4860.8  489.35  4901.1  488.58  5018.7  488.44  5024.0  486.88
  5052.2  486.33  5052.4  485.83  5056.2  486.33  5084.3  487.54  5106.2  489.69
  5127.1  492.65  5139.3  495.59  5148.5  496.21  5219.0  499.50  5273.9  500.54
  5304.1  503.05  5364.3  503.73  5413.9  508.32  5504.4  509.66  5544.2  511.28
#Mann=5,-1,0
  3514.7    0.05       0  4538.5    0.12       0  5052.2    0.07       0
  5056.2    0.12       0  5106.2    0.05       0
Bank Sta=5052.2,5056.2
Exp/Cntr=0.3,0.1

Chan Stop Cuts=-1