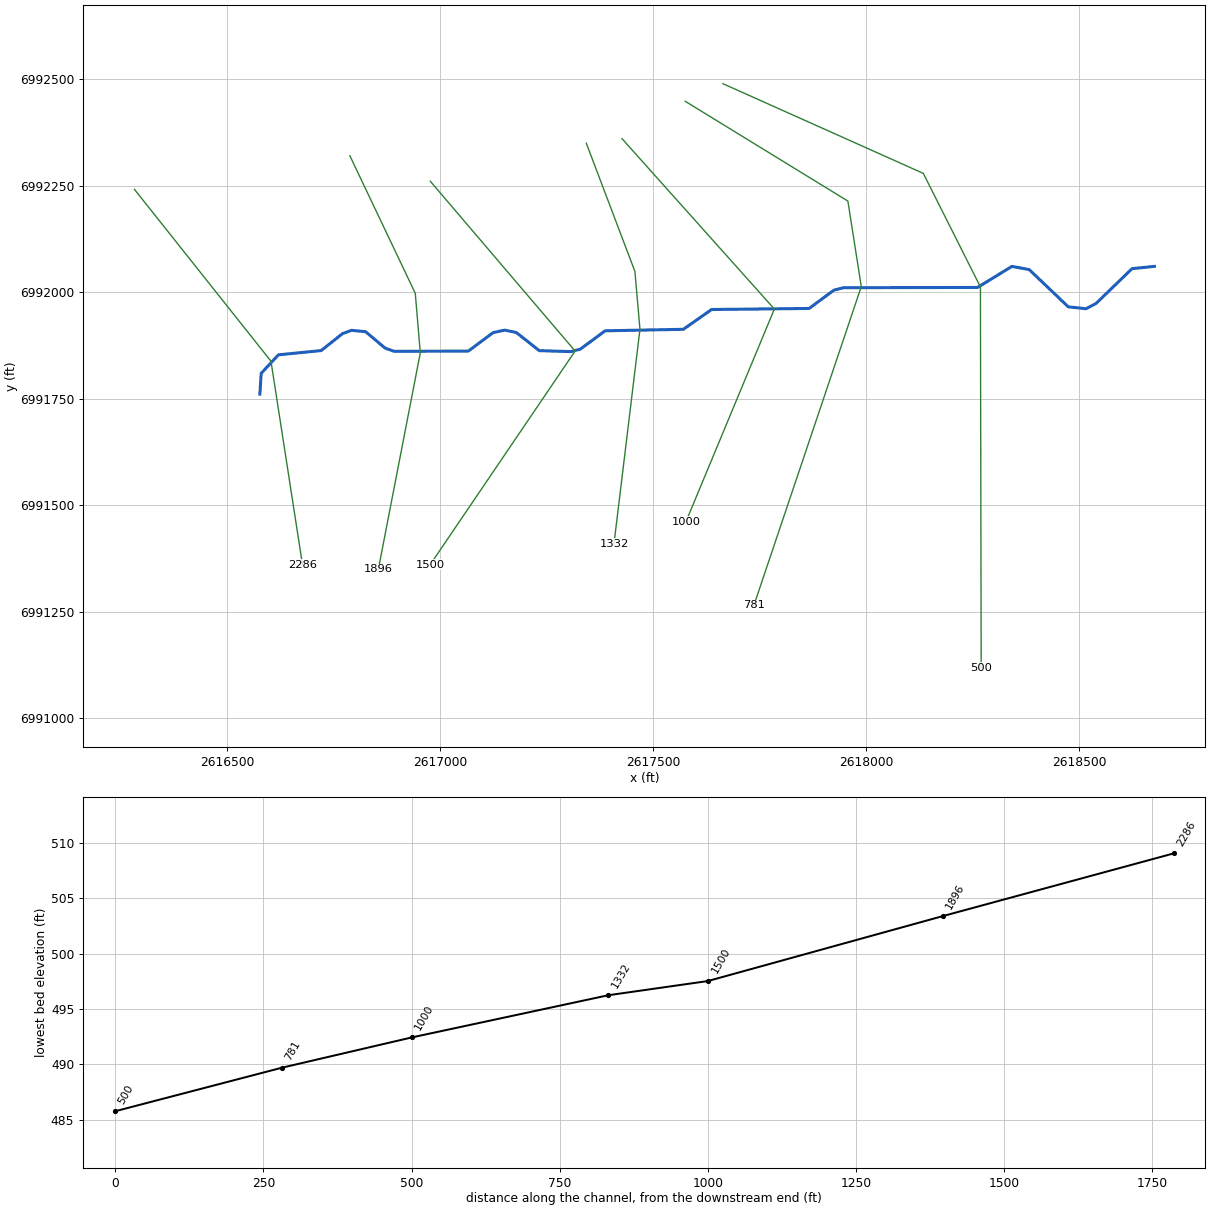
--- Brushy Creek Tributary 15_1.prj (project) ---

Proj Title=Brushy Creek Tributary 15_1 Base Level Engineering
Current Plan=p01
Default Exp/Contr=0.3,0.1
English Units
Geom File=g01
Flow File=f01
Plan File=p01
BEGIN DESCRIPTION:
Brushy Creek Tributary 15_1
END DESCRIPTION:

--- Brushy Creek Tributary 15_1.p01 (plan) ---

Plan Title=Multiple Run
Short Identifier=Multiple
Geom File=g01
Flow File=f01
Subcritical Flow
K Sum by GR= 0
Std Step Tol= 0.01
Critical Tol= 0.01
Num of Std Step Trials= 20
Max Error Tol= 0.3
Flow Tol Ratio= 0.001
Split Flow NTrial= 30
Split Flow Tol= 0.02
Split Flow Ratio= 0.02
Log Output Level= 0
Friction Slope Method= 1
Unsteady Friction Slope Method= 2
Unsteady Bridges Friction Slope Method= 1
Parabolic Critical Depth
Global Vel Dist=  1 , 1 , 1
Global Log Level= 0
CheckData=True
Encroach Param= -1, 0, 0, 0
BEGIN DESCRIPTION:
Multiple Run
END DESCRIPTION:

--- Brushy Creek Tributary 15_1.f01 (steady flow) ---

Flow Title=Multiple
Number of Profiles=7
Profile Names=10-year,25-year,50-year,1pct_min,100-year,1pct_plu,500-year
River Rch & RM= Brushy Creek Tri,Reach-1,2286
     148     181     206     117     233     465     297
Boundary for River Rch & Prof#=Brushy Creek Tri,Reach-1,1
Up Type=0
Dn Type=3
Dn Slope=0.005
Boundary for River Rch & Prof#=Brushy Creek Tri,Reach-1,2
Up Type=0
Dn Type=3
Dn Slope=0.005
Boundary for River Rch & Prof#=Brushy Creek Tri,Reach-1,3
Up Type=0
Dn Type=3
Dn Slope=0.005
Boundary for River Rch & Prof#=Brushy Creek Tri,Reach-1,4
Up Type=0
Dn Type=3
Dn Slope=0.005
Boundary for River Rch & Prof#=Brushy Creek Tri,Reach-1,5
Up Type=0
Dn Type=3
Dn Slope=0.005
Boundary for River Rch & Prof#=Brushy Creek Tri,Reach-1,6
Up Type=0
Dn Type=3
Dn Slope=0.005
Boundary for River Rch & Prof#=Brushy Creek Tri,Reach-1,7
Up Type=0
Dn Type=3
Dn Slope=0.005

--- Brushy Creek Tributary 15_1.g01 (geometry) ---

Geom Title=Existing Conditions

River Reach=Brushy Creek Tri,Reach-1
Reach XY= 30
      2616576.00      6991761.00      2616579.12      6991810.01
      2616619.55      6991853.36      2616720.03      6991863.38
      2616770.08      6991903.19      2616791.39      6991910.91
      2616824.26      6991907.63      2616869.93      6991869.19
      2616891.21      6991861.54      2617065.50      6991862.24
      2617123.82      6991905.62      2617151.00      6991911.40
      2617178.18      6991905.62      2617231.97      6991863.19
      2617305.90      6991860.91      2617328.31      6991866.68
      2617386.50      6991909.78      2617570.06      6991913.26
      2617636.50      6991959.78      2617865.50      6991962.22
      2617923.67      6992005.25      2617946.03      6992010.93
      2618260.79      6992011.54      2618341.42      6992060.97
      2618382.05      6992053.50      2618473.72      6991966.08
      2618515.36      6991961.55      2618539.21      6991974.11
      2618623.49      6992055.67      2618676.00      6992061.00

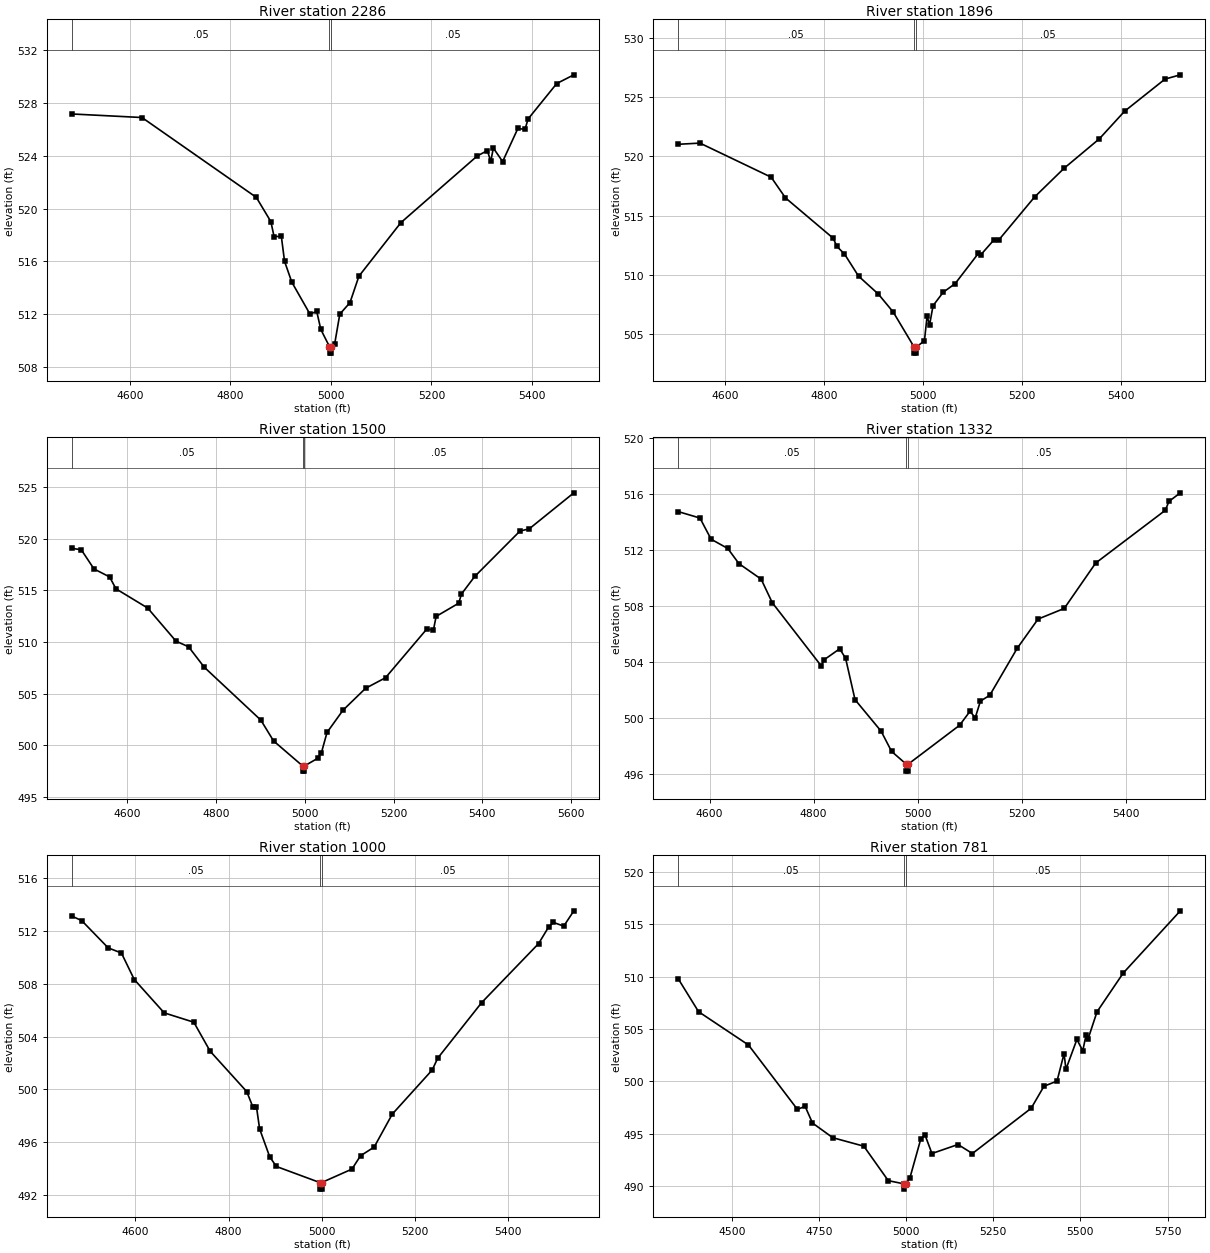
Type RM Length L Ch R = 1,2286,390,390,390
BEGIN DESCRIPTION:
Brushy Creek Tributary 15_1 4.0
END DESCRIPTION:
XS GIS Cut Line= 3
      2616281.50      6992241.88      2616602.08      6991838.44
      2616675.99      6991361.03
#Sta/Elev= 30
  4484.7  527.18  4624.3  526.91  4851.7  520.85  4880.6  519.01  4887.0  517.87
  4901.4  517.90  4907.8  516.00  4922.2  514.42  4958.4  511.99  4971.8  512.20
  4979.9  510.83  4997.1  509.53  4997.4  509.03  5000.9  509.03  5001.1  509.53
  5007.5  509.73  5017.7  511.99  5037.9  512.86  5055.7  514.87  5139.1  518.93
  5290.9  523.99  5311.1  524.40  5317.9  523.58  5323.0  524.59  5341.5  523.57
  5371.8  526.08  5386.0  526.01  5392.1  526.80  5449.1  529.49  5483.1  530.15
#Mann=3,-1,0
  4484.7    0.05       0  4997.1    0.03       0  5001.1    0.05       0
Bank Sta=4997.1,5001.1
Exp/Cntr=0.3,0.1

Type RM Length L Ch R = 1,1896,396,396,396
BEGIN DESCRIPTION:
Mapping XS 35e4bed4
END DESCRIPTION:
XS GIS Cut Line= 4
      2616787.30      6992320.64      2616940.82      6991997.85
      2616952.63      6991858.11      2616854.22      6991350.33
#Sta/Elev= 30
  4505.0  521.02  4548.9  521.12  4692.8  518.24  4721.8  516.49  4818.2  513.08
  4825.7  512.39  4841.0  511.75  4869.4  509.88  4909.5  508.36  4939.6  506.84
  4982.0  503.87  4982.3  503.37  4985.8  503.37  4986.0  503.87  5002.7  504.42
  5008.0  506.48  5013.1  505.77  5020.1  507.38  5040.5  508.51  5064.9  509.25
  5111.5  511.79  5116.6  511.68  5142.3  512.90  5152.5  512.91  5225.2  516.56
  5284.9  518.99  5356.2  521.48  5407.2  523.81  5489.0  526.53  5519.9  526.89
#Mann=3,-1,0
  4505.0    0.05       0  4982.0    0.03       0  4986.0    0.05       0
Bank Sta=4982,4986
Exp/Cntr=0.3,0.1

Type RM Length L Ch R = 1,1500,168,168,168
BEGIN DESCRIPTION:
Brushy Creek Tributary 15_1 3.0
END DESCRIPTION:
XS GIS Cut Line= 3
      2616975.98      6992261.03      2617316.06      6991862.25
      2616976.01      6991361.01
#Sta/Elev= 30
  4475.9  519.07  4497.4  518.92  4525.9  517.07  4561.0  516.30  4575.3  515.15
  4646.7  513.29  4710.4  510.09  4738.8  509.54  4774.0  507.57  4901.4  502.45
  4930.0  500.44  4995.5  498.02  4995.8  497.52  4999.3  497.52  4999.5  498.02
  5029.3  498.76  5037.8  499.32  5050.3  501.26  5086.2  503.41  5137.1  505.53
  5181.9  506.55  5274.8  511.26  5289.7  511.16  5295.8  512.48  5346.7  513.76
  5352.7  514.64  5382.6  516.34  5484.4  520.73  5505.4  520.95  5605.7  524.43
#Mann=3,-1,0
  4475.9    0.05       0  4995.5    0.03       0  4999.5    0.05       0
Bank Sta=4995.5,4999.5
Exp/Cntr=0.3,0.1

Type RM Length L Ch R = 1,1332,332,332,332
BEGIN DESCRIPTION:
Mapping XS d7865393
END DESCRIPTION:
XS GIS Cut Line= 4
      2617342.33      6992350.13      2617456.47      6992049.02
      2617468.28      6991913.22      2617407.26      6991409.33
#Sta/Elev= 30
  4539.5  514.76  4581.3  514.30  4602.7  512.79  4634.8  512.13  4656.2  511.05
  4699.0  509.94  4720.4  508.26  4814.6  503.75  4819.9  504.18  4850.1  504.97
  4861.5  504.29  4879.6  501.34  4929.8  499.09  4949.9  497.65  4978.0  496.74
  4978.2  496.24  4981.7  496.24  4982.0  496.74  5080.7  499.51  5100.8  500.51
  5110.9  500.05  5120.9  501.24  5138.8  501.65  5191.5  505.00  5231.7  507.09
  5282.1  507.85  5342.6  511.09  5476.4  514.85  5483.6  515.49  5505.4  516.10
#Mann=3,-1,0
  4539.5    0.05       0  4978.0    0.03       0  4982.0    0.05       0
Bank Sta=4978,4982
Exp/Cntr=0.3,0.1

Type RM Length L Ch R = 1,1000,219,219,219
BEGIN DESCRIPTION:
Brushy Creek Tributary 15_1 2.0
END DESCRIPTION:
XS GIS Cut Line= 3
      2617425.98      6992361.02      2617783.83      6991960.89
      2617575.99      6991460.98
#Sta/Elev= 30
  4463.2  513.14  4484.5  512.80  4541.4  510.73  4569.8  510.34  4597.4  508.33
  4661.7  505.80  4725.3  505.09  4760.4  502.89  4838.9  499.83  4852.4  498.64
  4859.9  498.66  4866.6  497.00  4888.3  494.88  4902.5  494.15  4995.9  492.93
  4996.1  492.43  4999.6  492.43  4999.9  492.93  5064.9  493.95  5083.3  494.96
  5112.6  495.62  5151.5  498.12  5237.3  501.47  5249.0  502.36  5343.5  506.58
  5465.6  511.05  5487.2  512.31  5497.5  512.66  5519.7  512.38  5541.4  513.54
#Mann=3,-1,0
  4463.2    0.05       0  4995.9    0.03       0  4999.9    0.05       0
Bank Sta=4995.9,4999.9
Exp/Cntr=0.3,0.1

Type RM Length L Ch R = 1,781,281,281,281
BEGIN DESCRIPTION:
Mapping XS 0787d09e
END DESCRIPTION:
XS GIS Cut Line= 4
      2617574.59      6992448.53      2617956.38      6992214.34
      2617987.87      6992013.59      2617736.01      6991265.87
#Sta/Elev= 30
  4346.5  509.78  4404.8  506.64  4548.0  503.46  4688.4  497.31  4710.3  497.61
  4731.6  496.01  4789.7  494.61  4878.8  493.80  4948.9  490.51  4994.4  490.20
  4994.6  489.70  4998.4  490.20  5010.9  490.76  5042.5  494.52  5054.4  494.86
  5074.2  493.10  5148.9  493.96  5190.3  493.10  5358.8  497.42  5395.5  499.52
  5433.0  500.02  5453.2  502.64  5458.5  501.14  5490.0  503.99  5506.8  502.91
  5516.2  504.40  5521.5  503.99  5547.7  506.63  5622.9  510.33  5786.6  516.27
#Mann=3,-1,0
  4346.5    0.05       0  4994.4    0.03       0  4998.4    0.05       0
Bank Sta=4994.4,4998.4
Exp/Cntr=0.3,0.1

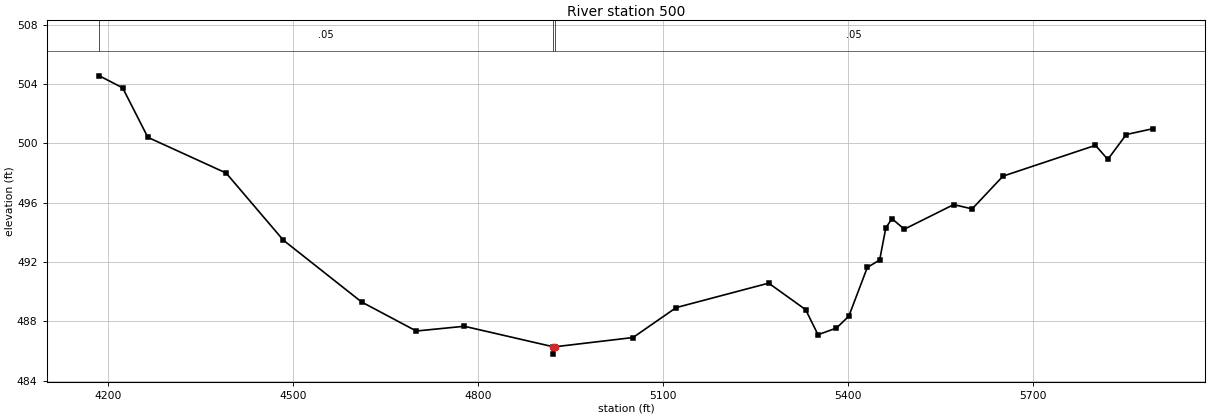
Type RM Length L Ch R = 1,500,0,0,0
BEGIN DESCRIPTION:
Brushy Creek Tributary 15_1 1.0
END DESCRIPTION:
XS GIS Cut Line= 4
      2617663.09      6992489.90      2618133.51      6992279.29
      2618267.55      6992012.71      2618269.31      6991118.11
#Sta/Elev= 30
  4186.2  504.56  4224.0  503.75  4264.9  500.41  4391.8  498.00  4484.6  493.47
  4611.5  489.30  4700.2  487.34  4778.1  487.66  4921.9  486.28  4922.1  485.78
  4925.9  486.28  5051.7  486.90  5121.7  488.92  5271.7  490.57  5331.7  488.78
  5351.7  487.09  5381.7  487.54  5401.7  488.34  5431.7  491.63  5451.7  492.13
  5461.7  494.30  5471.7  494.92  5491.7  494.21  5571.7  495.87  5601.7  495.58
  5651.7  497.79  5801.7  499.87  5821.7  498.92  5851.7  500.60  5894.6  500.99
#Mann=3,-1,0
  4186.2    0.05       0  4921.9    0.03       0  4925.9    0.05       0
Bank Sta=4921.9,4925.9
Exp/Cntr=0.3,0.1

Chan Stop Cuts=-1