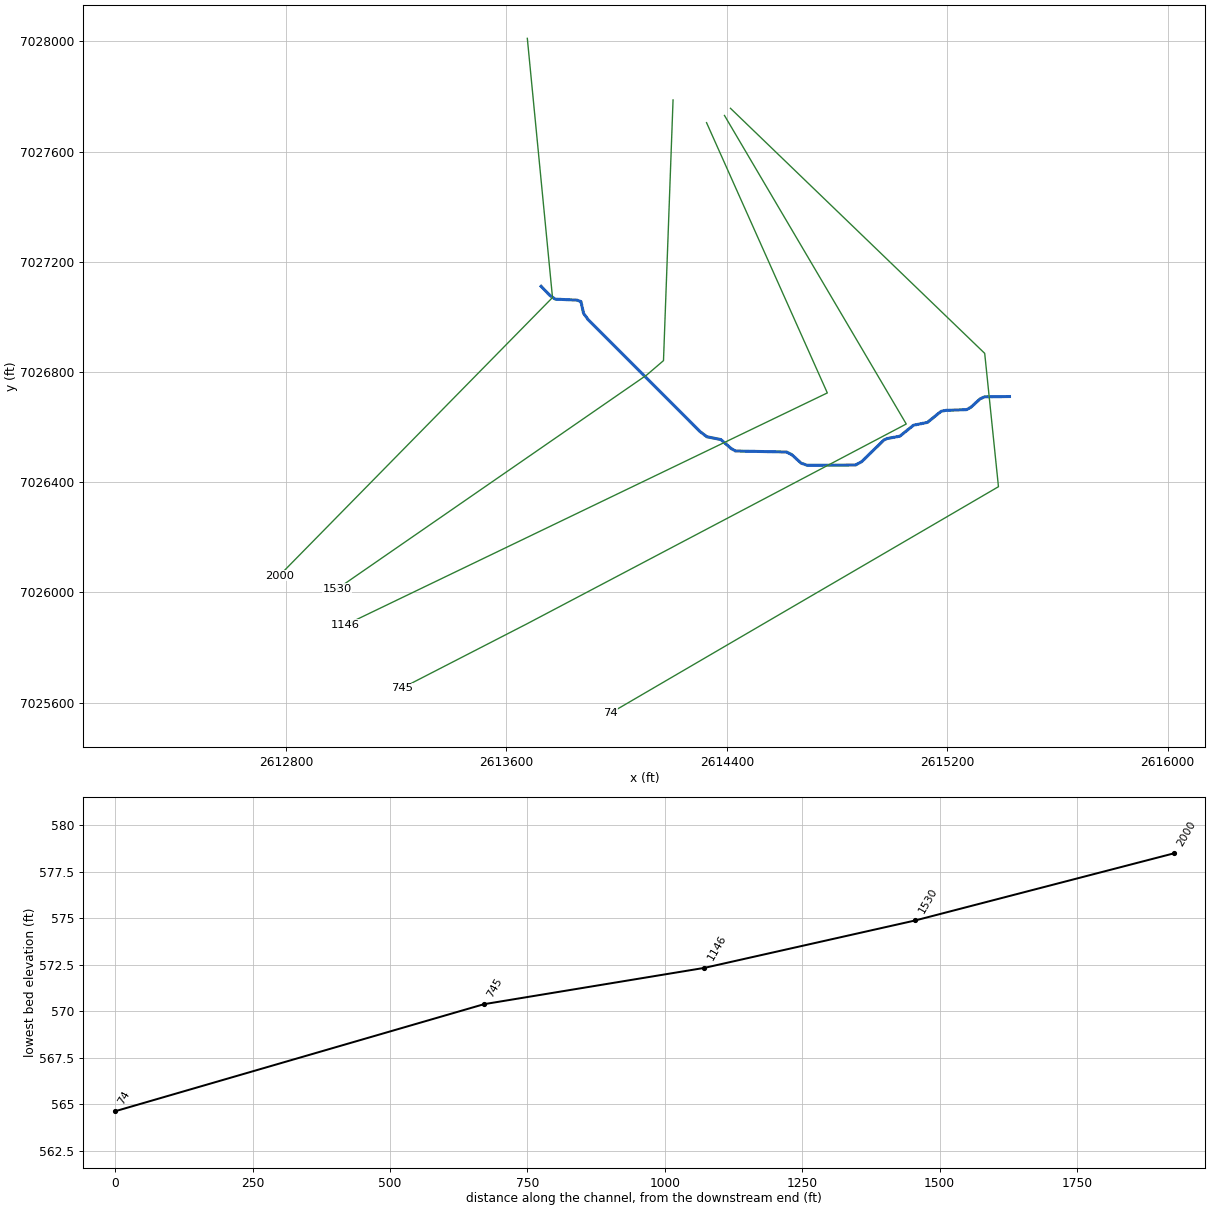
--- Brushy Creek Tributary 16.prj (project) ---

Proj Title=Brushy Creek Tributary 16 Base Level Engineering
Current Plan=p01
Default Exp/Contr=0.3,0.1
English Units
Geom File=g01
Flow File=f01
Plan File=p01
Y Axis Title=Elevation
X Axis Title(PF)=Main Channel Distance
X Axis Title(XS)=Station
BEGIN DESCRIPTION:
Brushy Creek Tributary 16
END DESCRIPTION:
DSS Export Rating Curves= 0
DSS Export Rating Curve Sorted= 0
DSS Export Volume Flow Curves= 0
DXF OffsetX= 0
DXF OffsetY= 0
DXF ScaleX= 1
DXF ScaleY= 10

--- Brushy Creek Tributary 16.p01 (plan) ---

Plan Title=Multiple Run
Short Identifier=Multiple
Geom File=g01
Flow File=f01
Subcritical Flow
K Sum by GR= 0
Std Step Tol= 0.01
Critical Tol= 0.01
Num of Std Step Trials= 20
Max Error Tol= 0.3
Flow Tol Ratio= 0.001
Split Flow NTrial= 30
Split Flow Tol= 0.02
Split Flow Ratio= 0.02
Log Output Level= 0
Friction Slope Method= 1
Unsteady Friction Slope Method= 2
Unsteady Bridges Friction Slope Method= 1
Parabolic Critical Depth
Global Vel Dist=  1 , 1 , 1
Global Log Level= 0
CheckData=True
Encroach Param= -1, 0, 0, 0
BEGIN DESCRIPTION:
Multiple Run
END DESCRIPTION:

--- Brushy Creek Tributary 16.f01 (steady flow) ---

Flow Title=Multiple
Program Version=4.10
Number of Profiles= 7
Profile Names=10-year,25-year,50-year,1pct_min,100-year,1pct_plu,500-year
River Rch & RM=Brushy Creek Tri,Reach-1         ,2000
     279     357     418     244     486     970     654
River Rch & RM=Brushy Creek Tri,Reach-1         ,74
     484     640     764     453     904    1804    1264
Boundary for River Rch & Prof#=Brushy Creek Tri,Reach-1         , 1
Up Type= 0
Dn Type= 3
Dn Slope=0.00867
Boundary for River Rch & Prof#=Brushy Creek Tri,Reach-1         , 2
Up Type= 0
Dn Type= 3
Dn Slope=0.00867
Boundary for River Rch & Prof#=Brushy Creek Tri,Reach-1         , 3
Up Type= 0
Dn Type= 3
Dn Slope=0.00867
Boundary for River Rch & Prof#=Brushy Creek Tri,Reach-1         , 4
Up Type= 0
Dn Type= 3
Dn Slope=0.00867
Boundary for River Rch & Prof#=Brushy Creek Tri,Reach-1         , 5
Up Type= 0
Dn Type= 3
Dn Slope=0.00867
Boundary for River Rch & Prof#=Brushy Creek Tri,Reach-1         , 6
Up Type= 0
Dn Type= 3
Dn Slope=0.00867
Boundary for River Rch & Prof#=Brushy Creek Tri,Reach-1         , 7
Up Type= 0
Dn Type= 3
Dn Slope=0.00867
DSS Import GetInterval= 0
DSS Import GetPeak= 0
DSS Import FillOption= 0

--- Brushy Creek Tributary 16.g01 (geometry) ---

Geom Title=Existing Conditions

River Reach=Brushy Creek Tri,Reach-1
Reach XY= 30
      2613726.00      7027111.00      2613758.99      7027077.14
      2613777.50      7027064.43      2613855.79      7027060.86
      2613870.55      7027055.77      2613880.15      7027013.08
      2613895.87      7026991.10      2614302.53      7026584.01
      2614327.63      7026564.94      2614378.17      7026554.86
      2614416.33      7026521.79      2614431.93      7026513.24
      2614616.34      7026509.62      2614635.65      7026500.15
      2614669.94      7026469.14      2614691.22      7026461.52
      2614866.41      7026462.21      2614889.31      7026474.40
      2614969.95      7026552.84      2614981.63      7026558.38
      2615028.19      7026567.10      2615077.72      7026606.84
      2615128.18      7026617.12      2615177.58      7026657.17
      2615194.33      7026660.64      2615270.44      7026663.45
      2615285.65      7026671.84      2615319.93      7026702.89
      2615335.58      7026709.81      2615426.00      7026711.00

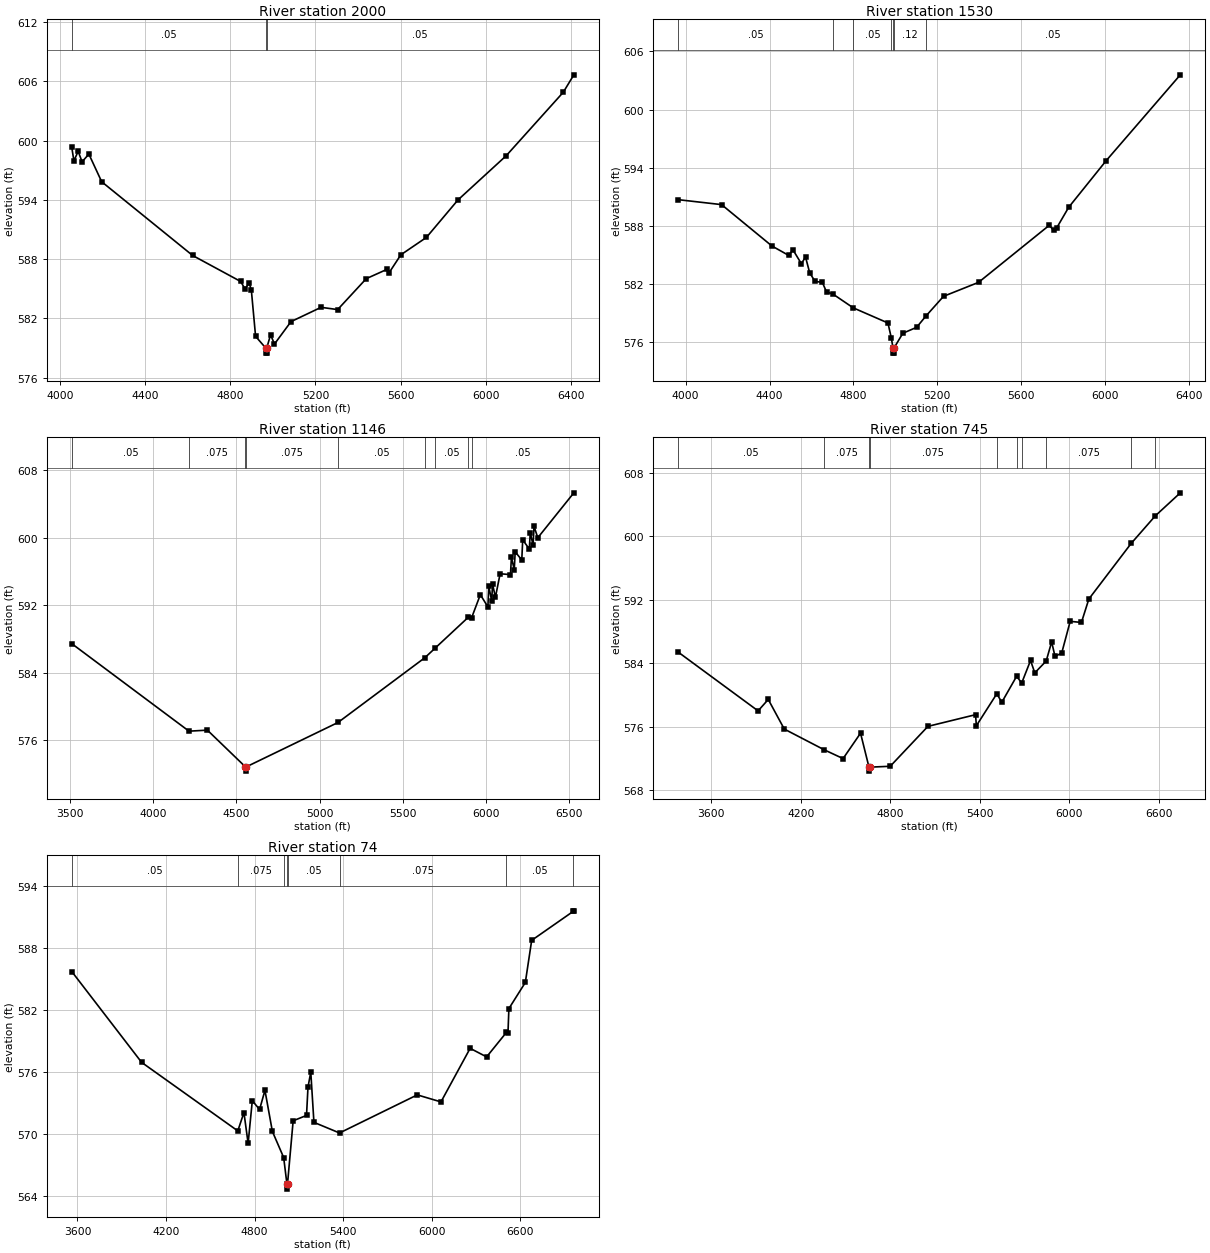
Type RM Length L Ch R = 1,2000,470,470,470
BEGIN DESCRIPTION:
Brushy Creek Tributary 16 4.0
END DESCRIPTION:
XS GIS Cut Line= 3
      2613676.00      7028010.98      2613767.40      7027070.21
      2612776.00      7026061.00
#Sta/Elev= 30
  4054.8  599.32  4064.8  597.96  4084.9  598.92  4103.2  597.86  4135.2  598.64
  4195.4  595.84  4623.0  588.37  4848.5  585.74  4868.6  585.00  4888.7  585.56
  4898.7  584.90  4918.8  580.18  4967.1  578.98  4967.3  578.48  4970.8  578.48
  4971.1  578.98  4989.2  580.34  5007.5  579.40  5085.2  581.67  5226.7  583.12
  5304.5  582.89  5438.8  586.02  5537.8  586.98  5545.0  586.58  5601.6  588.44
  5721.7  590.20  5870.2  594.00  6096.5  598.47  6365.2  604.91  6414.7  606.67
#Mann=3,-1,0
  4054.8    0.05       0  4967.1    0.03       0  4971.1    0.05       0
Bank Sta=4967.1,4971.1
Exp/Cntr=0.3,0.1

Type RM Length L Ch R = 1,1530,384,384,384
BEGIN DESCRIPTION:
Mapping XS aae7c3b5
END DESCRIPTION:
XS GIS Cut Line= 4
      2614204.94      7027787.42      2614170.22      7026841.27
      2614109.45      7026789.19      2612985.32      7026012.28
#Sta/Elev= 30
  3964.8  590.71  4171.4  590.20  4411.5  585.93  4491.6  584.96  4511.6  585.54
  4551.6  584.11  4571.6  584.79  4591.6  583.15  4617.1  582.28  4651.7  582.18
  4671.7  581.19  4701.1  580.99  4799.1  579.55  4964.5  577.99  4980.9  576.41
  4988.6  575.38  4988.9  574.88  4992.4  574.88  4992.6  575.38  5035.4  576.93
  5101.0  577.54  5144.9  578.69  5229.4  580.74  5396.3  582.18  5733.6  588.07
  5754.5  587.54  5769.4  587.82  5826.2  589.93  6005.3  594.75  6358.1  603.59
#Mann=7,-1,0
  3964.8    0.05       0  4701.1   0.075       0  4799.1    0.05       0
  4980.9    0.12       0  4988.6    0.07       0  4992.6    0.12       0
  5144.9    0.05       0
Bank Sta=4988.6,4992.6
Exp/Cntr=0.3,0.1

Type RM Length L Ch R = 1,1146,401,401,401
BEGIN DESCRIPTION:
Mapping XS 1fde4194
END DESCRIPTION:
XS GIS Cut Line= 3
      2614326.48      7027704.96      2614764.84      7026724.08
      2613015.73      7025882.08
#Sta/Elev= 30
  3511.6  587.45  4215.7  577.07  4326.2  577.19  4555.0  572.83  4555.3  572.33
  4559.0  572.83  5110.6  578.10  5632.9  585.79  5695.8  586.95  5893.7  590.59
  5913.2  590.52  5965.6  593.26  6010.9  591.81  6016.4  594.26  6033.5  592.53
  6039.1  594.50  6056.1  592.95  6084.3  595.74  6146.6  595.64  6152.2  597.70
  6169.3  596.23  6174.8  598.34  6214.5  597.38  6220.1  599.77  6259.8  598.66
  6265.3  600.63  6282.4  599.12  6287.9  601.38  6310.6  600.01  6527.2  605.34
#Mann=9,-1,0
  3511.6    0.05       0  4215.7   0.075       0  4555.0    0.07       0
  4559.0   0.075       0  5110.6    0.05       0  5632.9   0.075       0
  5695.8    0.05       0  5893.7   0.075       0  5913.2    0.05       0
Bank Sta=4555,4559
Exp/Cntr=0.3,0.1

Type RM Length L Ch R = 1,745,671,671,671
BEGIN DESCRIPTION:
Mapping XS e0262d4e
END DESCRIPTION:
XS GIS Cut Line= 4
      2614391.57      7027731.03      2615051.30      7026611.23
      2613675.43      7025886.41      2613220.38      7025652.38
#Sta/Elev= 30
  3377.6  585.37  3912.9  577.97  3981.2  579.41  4088.6  575.68  4357.2  573.06
  4482.9  571.96  4600.0  575.16  4656.6  570.88  4656.8  570.38  4660.6  570.88
  4798.9  570.99  5051.9  576.02  5371.1  577.49  5376.7  576.10  5513.5  580.12
  5547.3  579.06  5646.3  582.32  5680.8  581.49  5739.9  584.32  5768.3  582.76
  5844.8  584.25  5881.4  586.66  5904.0  584.83  5948.9  585.26  6005.7  589.25
  6081.1  589.11  6130.8  592.06  6414.3  599.06  6576.5  602.54  6744.1  605.44
#Mann=10,-1,0
  3377.6    0.05       0  4357.2   0.075       0  4656.6    0.07       0
  4660.6   0.075       0  5513.5     0.1       0  5646.3   0.075       0
  5680.8    0.05       0  5844.8   0.075       0  6414.3     0.1       0
  6576.5   0.075       0
Bank Sta=4656.6,4660.6
Exp/Cntr=0.3,0.1

Type RM Length L Ch R = 1,74,0,0,0
BEGIN DESCRIPTION:
Brushy Creek Tributary 16 1.0
END DESCRIPTION:
XS GIS Cut Line= 4
      2614413.28      7027757.07      2615336.03      7026867.62
      2615385.94      7026383.67      2613976.04      7025561.02
#Sta/Elev= 30
  3561.4  585.71  4034.5  576.91  4685.9  570.27  4727.5  572.05  4755.8  569.06
  4784.1  573.19  4833.5  572.35  4869.8  574.20  4920.1  570.22  4996.6  567.69
  5018.6  565.13  5018.8  564.63  5022.6  565.13  5060.8  571.25  5151.3  571.77
  5161.3  574.51  5180.2  575.97  5201.5  571.10  5374.9  570.07  5901.5  573.76
  6061.9  573.08  6259.5  578.27  6371.1  577.44  6505.7  579.82  6515.8  579.77
  6522.0  582.12  6633.3  584.65  6676.3  588.73  6958.0  591.54  6961.9  591.59
#Mann=8,-1,0
  3561.4    0.05       0  4685.9   0.075       0  4996.6    0.05       0
  5018.6    0.05       0  5022.6    0.05       0  5374.9   0.075       0
  6505.7    0.05       0  6958.0   0.075       0
Bank Sta=5018.6,5022.6
Exp/Cntr=0.3,0.1

Chan Stop Cuts=-1