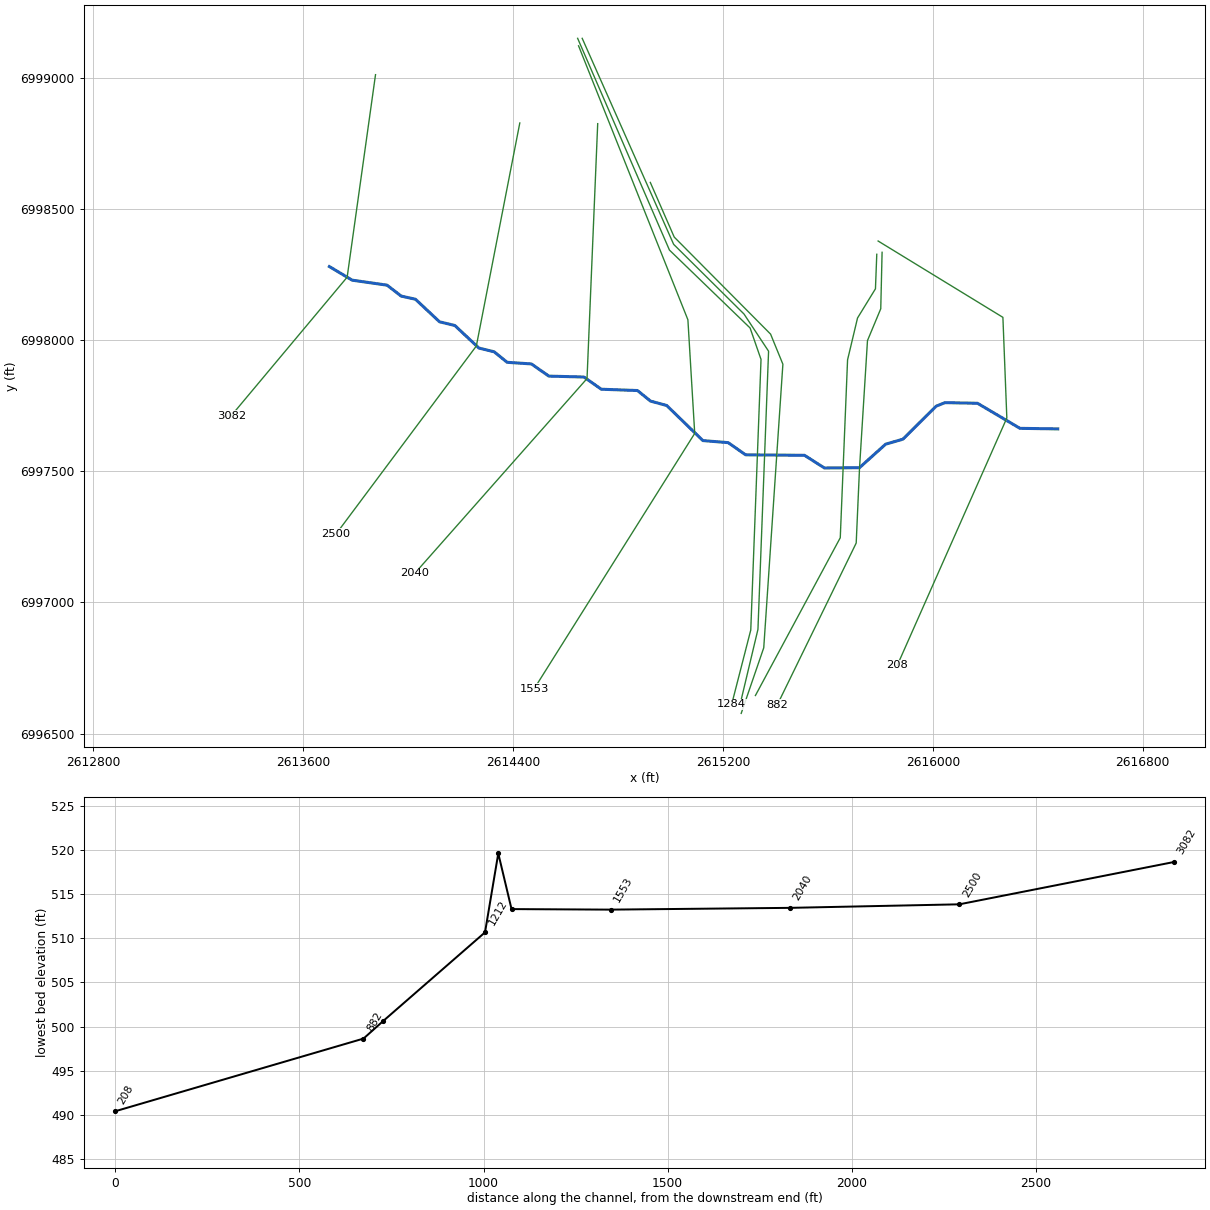
--- Brushy Creek Tributary 18.prj (project) ---

Proj Title=Brushy Creek Tributary 18 Base Level Engineering
Current Plan=p01
Default Exp/Contr=0.3,0.1
English Units
Geom File=g01
Flow File=f01
Plan File=p01
BEGIN DESCRIPTION:
Brushy Creek Tributary 18
END DESCRIPTION:

--- Brushy Creek Tributary 18.p01 (plan) ---

Plan Title=Multiple Run
Short Identifier=Multiple
Geom File=g01
Flow File=f01
Subcritical Flow
K Sum by GR= 0
Std Step Tol= 0.01
Critical Tol= 0.01
Num of Std Step Trials= 20
Max Error Tol= 0.3
Flow Tol Ratio= 0.001
Split Flow NTrial= 30
Split Flow Tol= 0.02
Split Flow Ratio= 0.02
Log Output Level= 0
Friction Slope Method= 1
Unsteady Friction Slope Method= 2
Unsteady Bridges Friction Slope Method= 1
Parabolic Critical Depth
Global Vel Dist=  1 , 1 , 1
Global Log Level= 0
CheckData=True
Encroach Param= -1, 0, 0, 0
BEGIN DESCRIPTION:
Multiple Run
END DESCRIPTION:

--- Brushy Creek Tributary 18.f01 (steady flow) ---

Flow Title=Multiple
Number of Profiles=7
Profile Names=10-year,25-year,50-year,1pct_min,100-year,1pct_plu,500-year
River Rch & RM= Brushy Creek Tri,Reach-1,3082
     439     580     692     411     819    1635    1146
Boundary for River Rch & Prof#=Brushy Creek Tri,Reach-1,1
Up Type=0
Dn Type=3
Dn Slope=0.005
Boundary for River Rch & Prof#=Brushy Creek Tri,Reach-1,2
Up Type=0
Dn Type=3
Dn Slope=0.005
Boundary for River Rch & Prof#=Brushy Creek Tri,Reach-1,3
Up Type=0
Dn Type=3
Dn Slope=0.005
Boundary for River Rch & Prof#=Brushy Creek Tri,Reach-1,4
Up Type=0
Dn Type=3
Dn Slope=0.005
Boundary for River Rch & Prof#=Brushy Creek Tri,Reach-1,5
Up Type=0
Dn Type=3
Dn Slope=0.005
Boundary for River Rch & Prof#=Brushy Creek Tri,Reach-1,6
Up Type=0
Dn Type=3
Dn Slope=0.005
Boundary for River Rch & Prof#=Brushy Creek Tri,Reach-1,7
Up Type=0
Dn Type=3
Dn Slope=0.005

--- Brushy Creek Tributary 18.g01 (geometry) ---

Geom Title=Existing Conditions

River Reach=Brushy Creek Tri,Reach-1
Reach XY= 30
      2613700.17      6998279.71      2613786.92      6998227.87
      2613920.09      6998208.81      2613973.83      6998167.14
      2614028.29      6998155.16      2614119.96      6998069.18
      2614178.28      6998055.13      2614269.95      6997969.16
      2614328.17      6997954.86      2614377.58      6997914.83
      2614470.02      6997908.64      2614536.51      6997862.23
      2614670.06      6997858.73      2614736.51      6997812.23
      2614874.44      6997807.24      2614923.83      6997767.14
      2614985.68      6997750.24      2615123.57      6997616.52
      2615220.02      6997608.64      2615286.50      6997562.22
      2615510.78      6997560.48      2615586.51      6997512.21
      2615720.14      6997513.05      2615819.96      6997602.82
      2615885.68      6997621.78      2616012.68      6997747.63
      2616045.99      6997761.06      2616170.07      6997758.77
      2616331.91      6997663.20      2616476.00      6997661.00

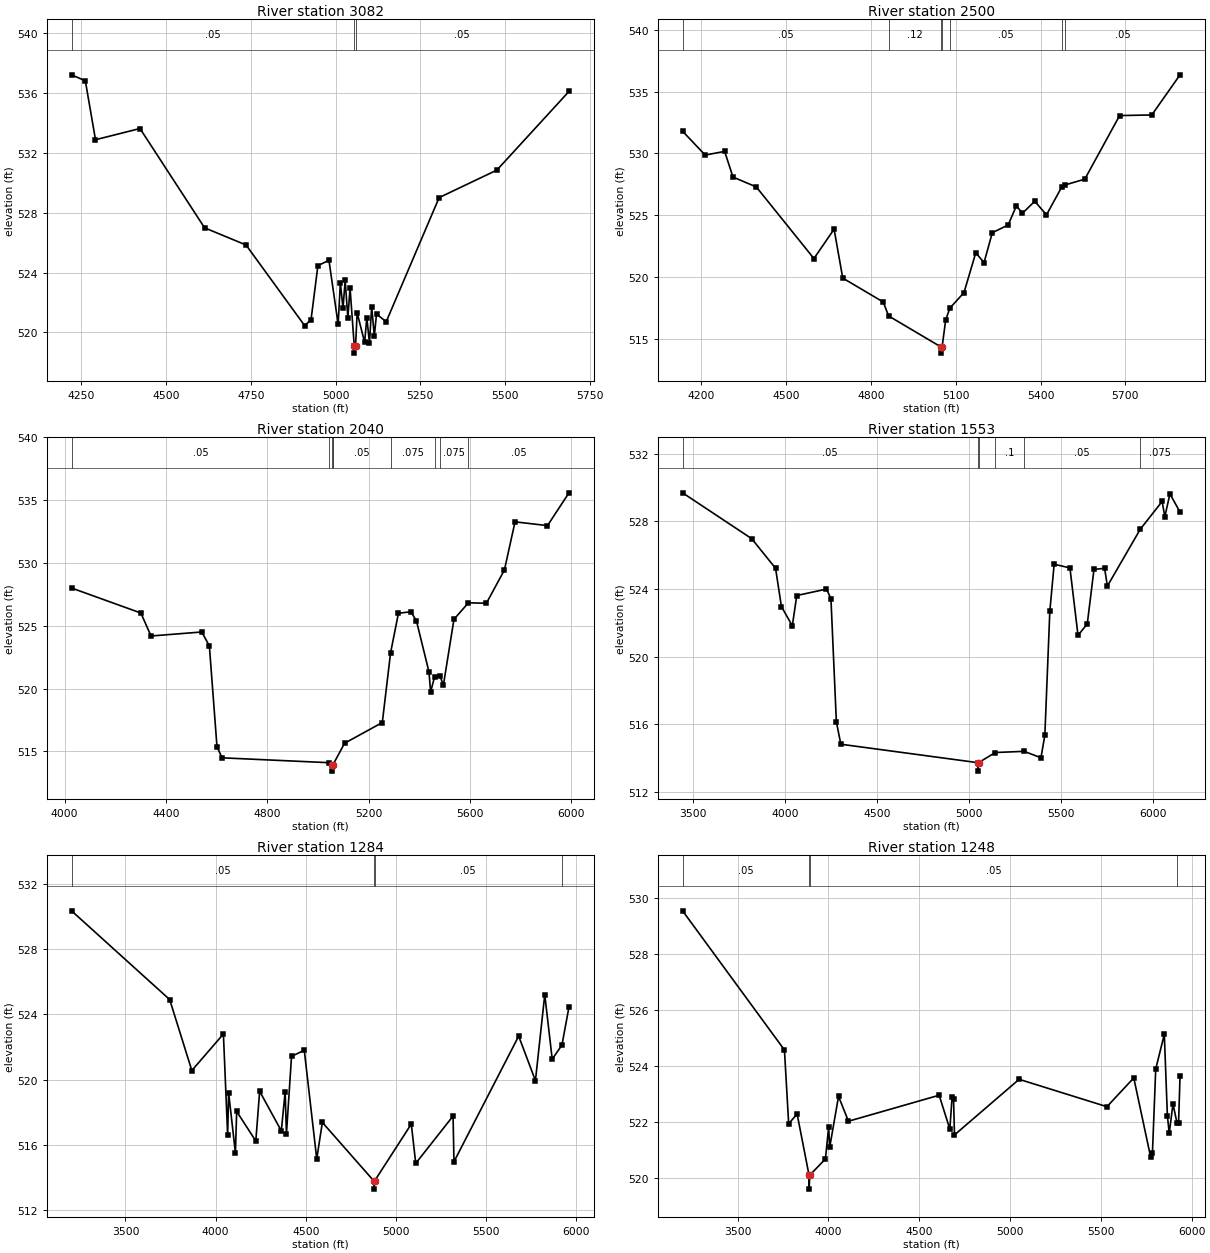
Type RM Length L Ch R = 1,3082,582,582,582
BEGIN DESCRIPTION:
Brushy Creek Tributary 14 6.0
END DESCRIPTION:
XS GIS Cut Line= 3
      2613876.00      6999011.01      2613767.89      6998239.24
      2613326.00      6997711.00
#Sta/Elev= 30
  4220.7  537.22  4261.4  536.82  4291.4  532.88  4422.7  533.63  4613.3  526.99
  4735.7  525.84  4908.9  520.44  4927.5  520.85  4947.7  524.46  4980.3  524.82
  5007.5  520.53  5014.0  523.30  5021.8  521.63  5028.3  523.48  5036.1  520.95
  5042.6  522.97  5054.9  519.11  5055.2  518.61  5058.9  519.11  5063.5  521.31
  5085.6  519.33  5092.1  520.99  5099.9  519.27  5106.4  521.72  5114.2  519.76
  5120.7  521.22  5149.3  520.71  5305.5  529.01  5475.9  530.85  5688.7  536.11
#Mann=3,-1,0
  4220.7    0.05       0  5054.9    0.04       0  5058.9    0.05       0
Bank Sta=5054.9,5058.9
Exp/Cntr=0.3,0.1

Type RM Length L Ch R = 1,2500,460,460,460
BEGIN DESCRIPTION:
Brushy Creek Tributary 14 5.0
END DESCRIPTION:
XS GIS Cut Line= 3
      2614425.85      6998826.91      2614260.22      6997976.90
      2613725.97      6997260.96
#Sta/Elev= 30
  4134.0  531.80  4214.0  529.87  4282.7  530.17  4312.2  528.09  4394.7  527.29
  4598.5  521.49  4669.8  523.87  4700.4  519.91  4843.6  517.97  4862.7  516.84
  5047.9  514.33  5048.2  513.83  5051.9  514.33  5064.5  516.52  5079.4  517.48
  5129.2  518.73  5170.9  521.96  5200.1  521.16  5229.3  523.58  5285.5  524.21
  5314.7  525.77  5335.6  525.15  5379.4  526.13  5421.0  525.03  5474.6  527.27
  5486.4  527.45  5556.5  527.92  5679.6  533.07  5793.4  533.12  5893.3  536.37
#Mann=7,-1,0
  4134.0    0.05       0  4862.7    0.12       0  5047.9    0.07       0
  5051.9    0.12       0  5079.4    0.05       0  5474.6   0.075       0
  5486.4    0.05       0
Bank Sta=5047.9,5051.9
Exp/Cntr=0.3,0.1

Type RM Length L Ch R = 1,2040,487,487,487
BEGIN DESCRIPTION:
Brushy Creek Tributary 14 4.0
END DESCRIPTION:
XS GIS Cut Line= 3
      2614722.73      6998824.30      2614682.05      6997852.85
      2614026.02      6997111.02
#Sta/Elev= 30
  4027.7  528.01  4301.2  526.02  4341.3  524.19  4541.5  524.51  4571.5  523.40
  4601.5  515.38  4621.5  514.49  5045.0  514.10  5053.6  513.93  5053.8  513.43
  5057.6  513.93  5059.5  513.95  5104.9  515.65  5253.8  517.30  5286.3  522.84
  5317.4  526.00  5366.7  526.12  5388.5  525.39  5437.8  521.34  5444.5  519.74
  5459.9  520.93  5481.6  521.00  5494.7  520.26  5536.5  525.52  5593.3  526.83
  5664.5  526.80  5735.6  529.45  5777.4  533.28  5905.4  532.98  5990.3  535.59
#Mann=9,-1,0
  4027.7    0.05       0  5045.0     0.1       0  5053.6    0.03       0
  5057.6     0.1       0  5059.5    0.05       0  5286.3   0.075       0
  5459.9    0.05       0  5481.6   0.075       0  5593.3    0.05       0
Bank Sta=5053.6,5057.6
Exp/Cntr=0.3,0.1

Type RM Length L Ch R = 1,1553,269,269,269
BEGIN DESCRIPTION:
Brushy Creek Tributary 14 3.0
END DESCRIPTION:
XS GIS Cut Line= 4
      2614649.82      6999120.93      2615066.48      6998076.92
      2615092.48      6997643.88      2614480.76      6996671.02
#Sta/Elev= 30
  3442.1  529.68  3818.2  526.97  3948.1  525.22  3979.9  522.96  4039.2  521.82
  4063.5  523.61  4225.1  523.99  4249.4  523.43  4279.0  516.14  4303.3  514.82
  5048.7  513.73  5048.9  513.23  5052.7  513.73  5143.8  514.33  5300.8  514.40
  5392.3  514.02  5413.5  515.35  5440.6  522.68  5464.1  525.46  5550.1  525.24
  5594.0  521.25  5644.4  521.94  5680.9  525.15  5738.6  525.22  5753.9  524.17
  5932.9  527.53  6051.8  529.17  6066.5  528.27  6094.2  529.62  6149.2  528.54
#Mann=6,-1,0
  3442.1    0.05       0  5048.7    0.03       0  5052.7    0.05       0
  5143.8     0.1       0  5300.8    0.05       0  5932.9   0.075       0
Bank Sta=5048.7,5052.7
Exp/Cntr=0.3,0.1

Type RM Length L Ch R = 1,1284,36,36,36
BEGIN DESCRIPTION:
Mapping XS b8850be8
END DESCRIPTION:
XS GIS Cut Line= 6
      2614646.27      6999149.48      2614996.17      6998342.54
      2615303.46      6998045.67      2615345.13      6997925.88
      2615306.06      6996894.63      2615233.15      6996610.79
#Sta/Elev= 30
  3201.0  530.35  3745.3  524.91  3868.1  520.56  4043.2  522.80  4066.7  516.61
  4072.1  519.20  4109.7  515.52  4116.9  518.05  4222.9  516.24  4244.2  519.29
  4364.4  516.86  4385.7  519.27  4392.7  516.66  4421.0  521.43  4491.7  521.80
  4560.8  515.14  4591.9  517.38  4877.6  513.79  4877.9  513.29  4881.6  513.79
  5085.2  517.28  5109.8  514.87  5316.8  517.77  5321.8  514.97  5680.7  522.67
  5773.6  519.94  5825.3  525.21  5866.6  521.26  5920.6  522.12  5959.7  524.46
#Mann=4,-1,0
  3201.0    0.05       0  4877.6    0.03       0  4881.6    0.05       0
  5920.6   0.075       0
Bank Sta=4877.6,4881.6
Exp/Cntr=0.3,0.1

Type RM Length L Ch R = 1,1248,36,36,36
BEGIN DESCRIPTION:
Mapping XS 87f4439d
END DESCRIPTION:
XS GIS Cut Line= 6
      2614663.65      6999149.45      2615012.16      6998364.43
      2615280.32      6998098.80      2615373.92      6997957.13
      2615333.44      6996897.14      2615270.59      6996633.15
#Sta/Elev= 30
  3196.4  529.55  3757.4  524.57  3780.7  521.93  3827.2  522.28  3892.9  520.09
  3893.2  519.59  3896.9  520.09  3983.2  520.67  4001.0  521.82  4006.5  521.08
  4055.3  522.91  4109.9  522.02  4609.4  522.95  4668.3  521.74  4680.9  522.89
  4688.8  522.82  4693.9  521.53  5050.0  523.52  5533.5  522.54  5681.4  523.57
  5773.9  520.75  5784.2  520.88  5802.3  523.89  5849.6  525.13  5866.5  522.22
  5876.7  521.59  5897.3  522.64  5919.5  521.96  5928.1  521.95  5936.2  523.64
#Mann=4,-1,0
  3196.4    0.05       0  3892.9    0.03       0  3896.9    0.05       0
  5919.5   0.075       0
Bank Sta=3892.9,3896.9
Exp/Cntr=0.3,0.1

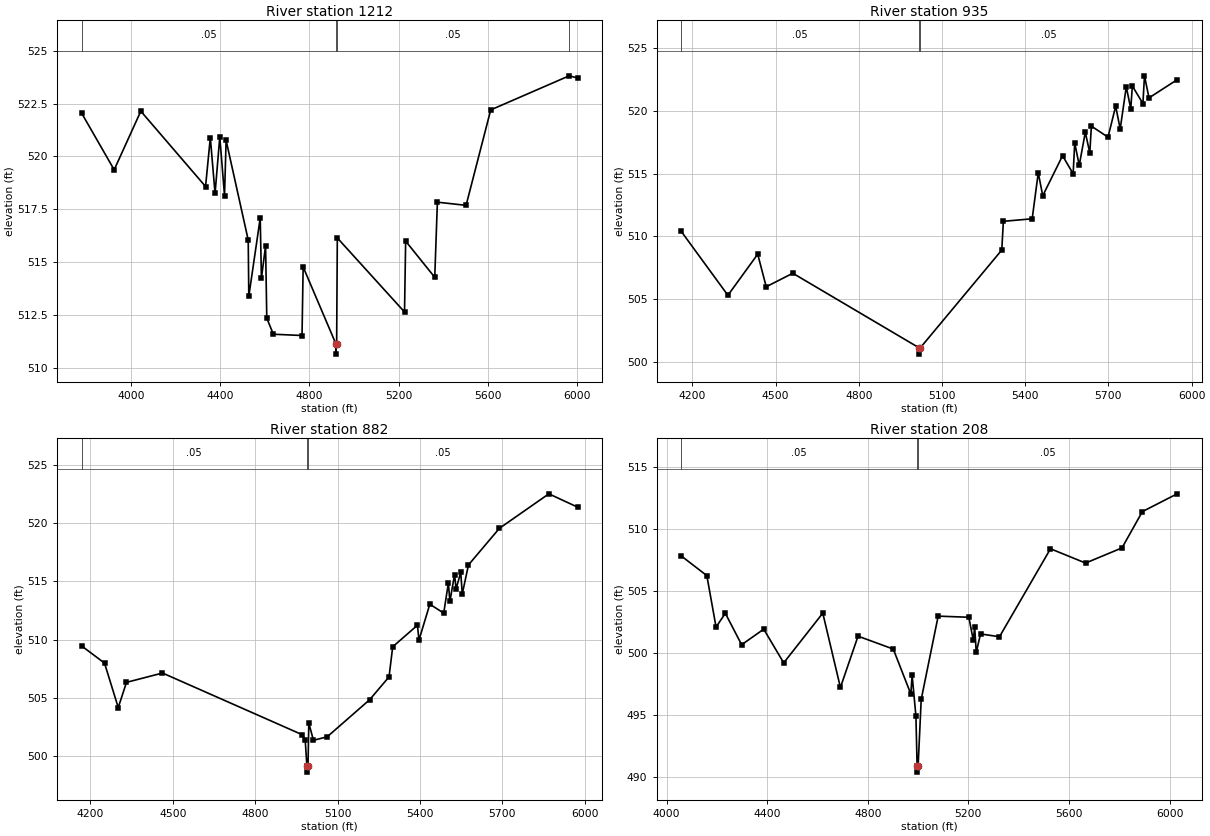
Type RM Length L Ch R = 1,1212,277,277,277
BEGIN DESCRIPTION:
Mapping XS 5edd7855
END DESCRIPTION:
XS GIS Cut Line= 6
      2614923.24      6998600.38      2615014.40      6998392.02
      2615381.58      6998022.23      2615428.46      6997907.65
      2615355.54      6996826.92      2615269.61      6996576.92
#Sta/Elev= 30
  3780.3  522.04  3925.7  519.37  4044.9  522.14  4334.8  518.58  4356.1  520.89
  4377.3  518.25  4398.5  520.92  4419.7  518.15  4426.8  520.76  4525.8  516.05
  4528.4  513.39  4579.5  517.09  4584.9  514.25  4603.5  515.78  4608.9  512.36
  4638.3  511.60  4766.7  511.54  4771.7  514.78  4917.7  511.16  4918.0  510.66
  4921.7  511.16  4924.7  516.15  5225.6  512.65  5230.6  516.00  5360.9  514.29
  5372.7  517.84  5501.2  517.69  5611.5  522.20  5962.7  523.81  6000.2  523.71
#Mann=4,-1,0
  3780.3    0.05       0  4917.7    0.03       0  4921.7    0.05       0
  5962.7   0.075       0
Bank Sta=4917.7,4921.7
Exp/Cntr=0.3,0.1

Type RM Length L Ch R = 1,935,53,53,53
BEGIN DESCRIPTION:
Mapping XS ef47f08f
END DESCRIPTION:
XS GIS Cut Line= 6
      2615786.28      6998326.53      2615781.22      6998194.93
      2615712.92      6998083.62      2615674.97      6997924.24
      2615647.14      6997246.25      2615323.80      6996645.04
#Sta/Elev= 30
  4160.1  510.39  4328.1  505.30  4435.6  508.58  4466.2  505.98  4562.0  507.06
  5017.6  501.11  5017.8  500.61  5021.6  501.11  5315.5  508.91  5321.2  511.20
  5425.1  511.40  5447.0  515.07  5463.2  513.24  5534.6  516.43  5572.8  514.99
  5578.4  517.46  5594.7  515.66  5616.6  518.30  5632.8  516.65  5638.5  518.79
  5698.5  517.91  5726.1  520.38  5742.4  518.56  5764.3  521.92  5780.5  520.18
  5786.2  521.99  5824.3  520.59  5830.0  522.80  5846.2  521.04  5947.7  522.49
#Mann=3,-1,0
  4160.1    0.05       0  5017.6    0.03       0  5021.6    0.05       0
Bank Sta=5017.6,5021.6
Exp/Cntr=0.3,0.1

Type RM Length L Ch R = 1,882,674,674,674
BEGIN DESCRIPTION:
Mapping XS 13fbf718
END DESCRIPTION:
XS GIS Cut Line= 6
      2615806.52      6998334.08      2615801.46      6998119.04
      2615750.86      6997997.61      2615720.51      6997511.88
      2615707.86      6997226.02      2615406.83      6996608.78
#Sta/Elev= 30
  4168.0  509.46  4251.1  507.99  4301.1  504.18  4331.1  506.34  4462.3  507.14
  4972.2  501.84  4982.2  501.38  4988.3  499.14  4988.5  498.64  4992.3  499.14
  4995.3  502.84  5012.2  501.37  5062.3  501.67  5216.9  504.85  5287.5  506.81
  5300.9  509.39  5391.0  511.24  5396.6  509.97  5436.1  513.04  5486.7  512.28
  5503.7  514.86  5509.2  513.28  5526.2  515.58  5531.8  514.36  5548.7  515.77
  5554.3  513.92  5576.8  516.41  5689.5  519.55  5869.7  522.51  5974.2  521.37
#Mann=3,-1,0
  4168.0    0.05       0  4988.3    0.03       0  4992.3    0.05       0
Bank Sta=4988.3,4992.3
Exp/Cntr=0.3,0.1

Type RM Length L Ch R = 1,208,0,0,0
BEGIN DESCRIPTION:
Brushy Creek Tributary 14 1.0
END DESCRIPTION:
XS GIS Cut Line= 4
      2615791.37      6998377.06      2616266.95      6998086.15
      2616281.92      6997702.53      2615864.69      6996760.50
#Sta/Elev= 30
  4058.6  507.81  4160.1  506.23  4196.8  502.09  4233.6  503.20  4298.5  500.67
  4386.4  501.92  4465.8  499.21  4621.2  503.21  4691.3  497.23  4761.4  501.36
  4901.5  500.32  4971.4  496.70  4976.4  498.23  4991.5  494.95  4996.3  490.92
  4996.5  490.42  5000.3  490.92  5012.6  496.27  5080.0  502.97  5201.9  502.88
  5219.7  501.03  5225.2  502.10  5231.4  500.06  5248.5  501.54  5323.8  501.31
  5526.7  508.39  5666.2  507.24  5811.0  508.46  5892.1  511.38  6030.3  512.81
#Mann=3,-1,0
  4058.6    0.05       0  4996.3    0.03       0  5000.3    0.05       0
Bank Sta=4996.3,5000.3
Exp/Cntr=0.3,0.1

Chan Stop Cuts=-1