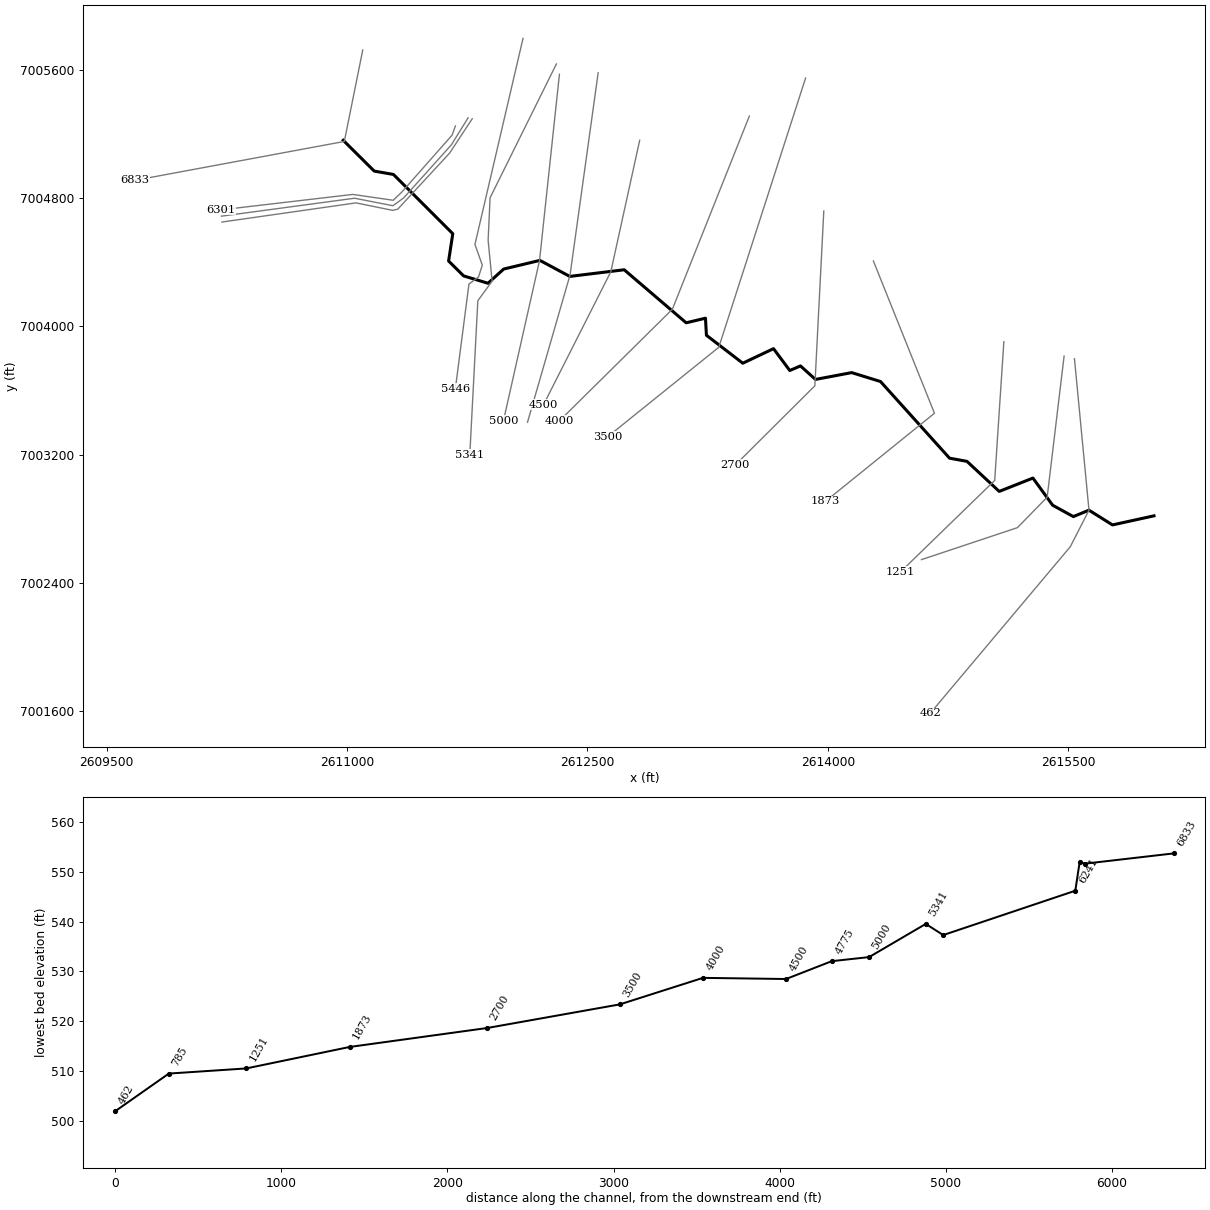
--- Brushy Creek Tributary 6.prj (project) ---

Proj Title=Brushy Creek Tributary 6 Base Level Engineering
Current Plan=p01
Default Exp/Contr=0.3,0.1
English Units
Geom File=g01
Flow File=f01
Plan File=p01
BEGIN DESCRIPTION:
Brushy Creek Tributary 6
END DESCRIPTION:

--- Brushy Creek Tributary 6.p01 (plan) ---

Plan Title=Multiple Run
Short Identifier=Multiple
Geom File=g01
Flow File=f01
Subcritical Flow
K Sum by GR= 0
Std Step Tol= 0.01
Critical Tol= 0.01
Num of Std Step Trials= 20
Max Error Tol= 0.3
Flow Tol Ratio= 0.001
Split Flow NTrial= 30
Split Flow Tol= 0.02
Split Flow Ratio= 0.02
Log Output Level= 0
Friction Slope Method= 1
Unsteady Friction Slope Method= 2
Unsteady Bridges Friction Slope Method= 1
Parabolic Critical Depth
Global Vel Dist=  1 , 1 , 1
Global Log Level= 0
CheckData=True
Encroach Param= -1, 0, 0, 0
BEGIN DESCRIPTION:
Multiple Run
END DESCRIPTION:

--- Brushy Creek Tributary 6.f01 (steady flow) ---

Flow Title=Multiple
Number of Profiles=7
Profile Names=10-year,25-year,50-year,1pct_min,100-year,1pct_plu,500-year
River Rch & RM= Brushy Creek Tri,Reach-1,6833
     425     561     669     396     790    1577    1103
Boundary for River Rch & Prof#=Brushy Creek Tri,Reach-1,1
Up Type=0
Dn Type=3
Dn Slope=0.005
Boundary for River Rch & Prof#=Brushy Creek Tri,Reach-1,2
Up Type=0
Dn Type=3
Dn Slope=0.005
Boundary for River Rch & Prof#=Brushy Creek Tri,Reach-1,3
Up Type=0
Dn Type=3
Dn Slope=0.005
Boundary for River Rch & Prof#=Brushy Creek Tri,Reach-1,4
Up Type=0
Dn Type=3
Dn Slope=0.005
Boundary for River Rch & Prof#=Brushy Creek Tri,Reach-1,5
Up Type=0
Dn Type=3
Dn Slope=0.005
Boundary for River Rch & Prof#=Brushy Creek Tri,Reach-1,6
Up Type=0
Dn Type=3
Dn Slope=0.005
Boundary for River Rch & Prof#=Brushy Creek Tri,Reach-1,7
Up Type=0
Dn Type=3
Dn Slope=0.005

--- Brushy Creek Tributary 6.g01 (geometry) ---

Geom Title=Existing Conditions

River Reach=Brushy Creek Tri,Reach-1
Reach XY= 30
      2610976.00      7005161.00      2611169.55      7004968.75
      2611289.65      7004947.74      2611659.75      7004578.13
      2611633.79      7004407.57      2611727.47      7004314.61
      2611879.41      7004268.81      2611977.47      7004357.43
      2612203.25      7004411.51      2612389.86      7004311.54
      2612729.33      7004353.02      2613115.95      7004022.11
      2613236.39      7004050.80      2613242.38      7003944.30
      2613469.34      7003769.98      2613660.91      7003860.81
      2613762.32      7003724.51      2613829.32      7003752.96
      2613922.58      7003668.82      2614148.84      7003711.29
      2614328.67      7003655.58      2614759.24      7003177.45
      2614867.94      7003157.65      2615069.27      7002970.14
      2615279.67      7003053.31      2615402.48      7002883.99
      2615531.72      7002812.95      2615629.31      7002852.95
      2615776.00      7002761.00      2616034.95      7002817.67

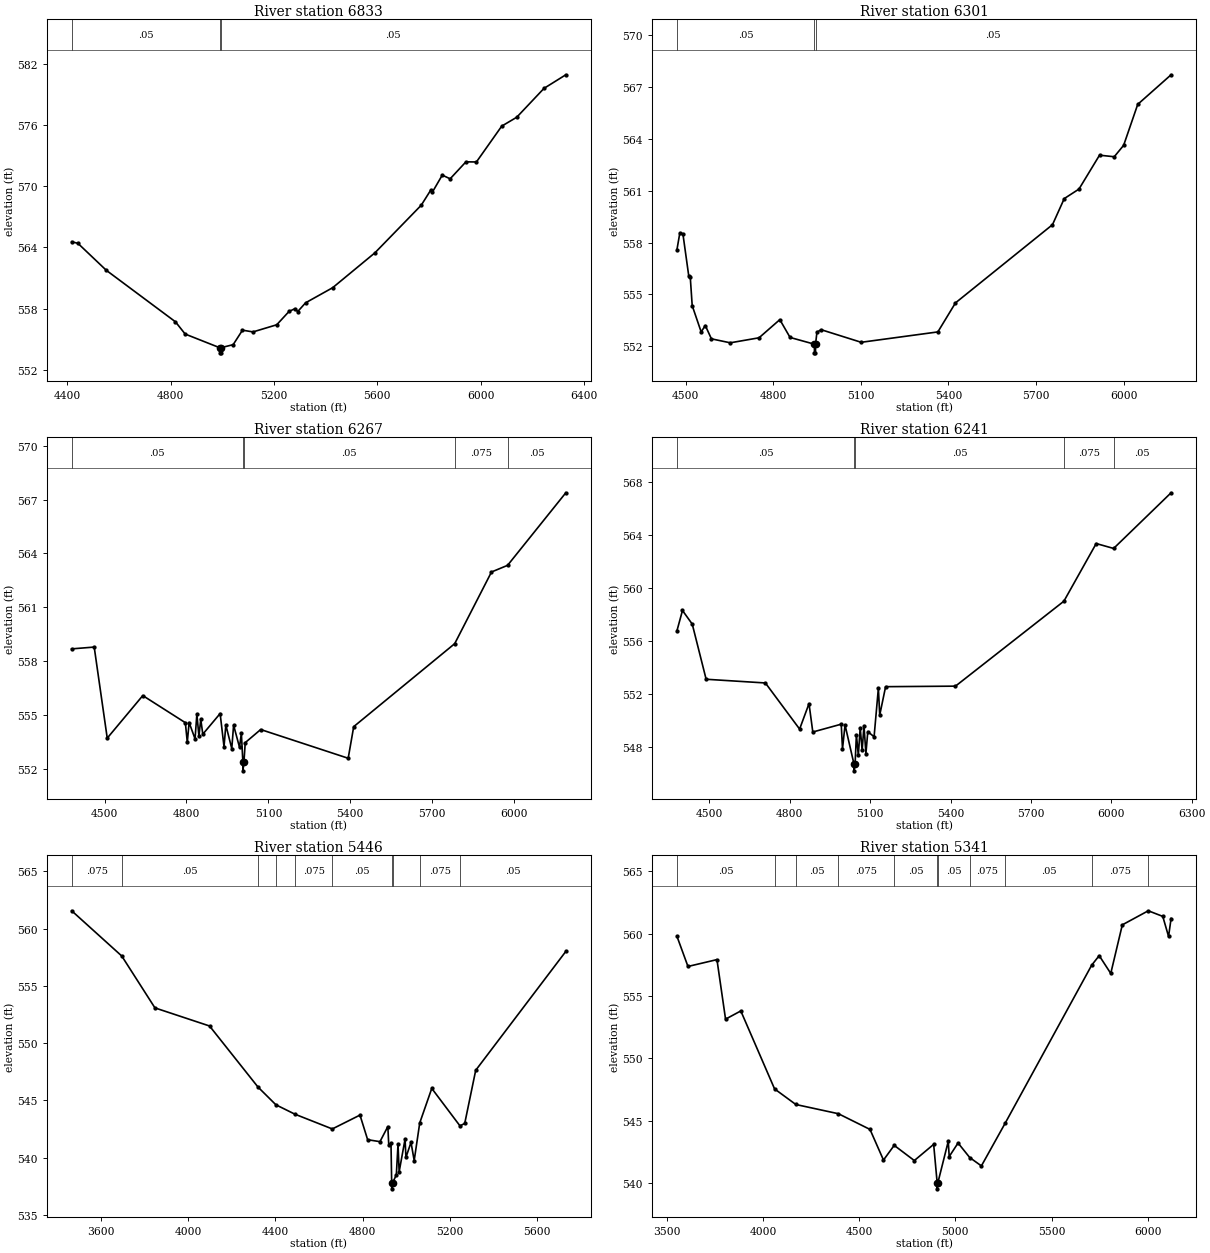
Type RM Length L Ch R = 1,6833,532,532,532
BEGIN DESCRIPTION:
Brushy Creek Tributary 6 13.0
END DESCRIPTION:
XS GIS Cut Line= 3
      2611098.13      7005724.56      2610983.08      7005153.64
      2609676.01      7004911.00
#Sta/Elev= 30
  4417.6  564.55  4441.6  564.40  4551.8  561.75  4819.1  556.71  4856.7  555.51
  4990.5  554.17  4990.7  553.67  4994.2  553.67  4994.5  554.17  5042.3  554.47
  5078.4  555.89  5119.1  555.72  5211.0  556.42  5258.7  557.73  5281.8  558.00
  5292.0  557.71  5322.5  558.57  5427.3  560.05  5590.9  563.47  5770.0  568.13
  5807.3  569.63  5812.4  569.38  5851.4  571.08  5881.9  570.72  5942.9  572.38
  5983.6  572.37  6081.5  575.88  6139.5  576.75  6245.1  579.58  6329.4  580.91
#Mann=3,-1,0
  4417.6    0.05       0  4990.5    0.04       0  4994.5    0.05       0
Bank Sta=4990.5,4994.5
Exp/Cntr=0.3,0.1

Type RM Length L Ch R = 1,6301,34,34,34
BEGIN DESCRIPTION:
Mapping XS 698369f4
END DESCRIPTION:
XS GIS Cut Line= 6
      2611676.11      7005250.05      2611655.26      7005192.89
      2611342.76      7004838.72      2611288.08      7004786.64
      2611035.47      7004823.10      2610212.60      7004726.75
#Sta/Elev= 30
  4470.2  557.59  4479.8  558.53  4490.5  558.51  4510.4  556.09  4515.7  556.02
  4522.4  554.35  4553.1  552.83  4567.3  553.20  4588.2  552.43  4652.7  552.20
  4751.3  552.49  4822.5  553.54  4857.6  552.51  4940.9  552.12  4941.2  551.62
  4944.7  551.62  4944.9  552.12  4949.6  552.81  4963.8  552.96  5101.2  552.23
  5363.8  552.83  5424.2  554.51  5756.4  559.03  5796.7  560.54  5847.1  561.09
  5917.5  563.05  5967.9  562.96  6000.1  563.62  6048.4  565.99  6162.6  567.70
#Mann=3,-1,0
  4470.2    0.05       0  4940.9    0.03       0  4944.9    0.05       0
Bank Sta=4940.9,4944.9
Exp/Cntr=0.3,0.1

Type RM Length L Ch R = 1,6267,26,26,26
BEGIN DESCRIPTION:
Mapping XS de0c2043
END DESCRIPTION:
XS GIS Cut Line= 6
      2611755.34      7005300.84      2611651.10      7005132.74
      2611354.22      7004802.01      2611286.51      7004752.53
      2611046.93      7004799.40      2610216.21      7004687.42
#Sta/Elev= 30
  4379.6  558.69  4462.1  558.79  4509.8  553.72  4640.0  556.09  4795.9  554.58
  4803.0  553.49  4809.7  554.59  4831.4  553.68  4838.1  555.06  4845.6  553.83
  4852.3  554.77  4859.8  553.94  4923.3  555.09  4937.5  553.24  4944.2  554.45
  4965.9  553.14  4972.6  554.44  4994.3  553.21  5001.0  554.00  5006.5  552.40
  5006.8  551.90  5010.5  552.40  5015.2  553.47  5071.8  554.20  5392.3  552.60
  5412.5  554.36  5782.4  558.98  5917.1  562.97  5976.0  563.34  6189.3  567.38
#Mann=5,-1,0
  4379.6    0.05       0  5006.5    0.03       0  5010.5    0.05       0
  5782.4   0.075       0  5976.0    0.05       0
Bank Sta=5006.5,5010.5
Exp/Cntr=0.3,0.1

Type RM Length L Ch R = 1,6241,795,795,795
BEGIN DESCRIPTION:
Mapping XS f50d80f9
END DESCRIPTION:
XS GIS Cut Line= 6
      2611781.03      7005294.93      2611639.47      7005080.22
      2611316.55      7004731.26      2611285.30      7004723.45
      2611056.13      7004770.32      2610219.27      7004650.77
#Sta/Elev= 30
  4378.8  556.75  4399.4  558.28  4435.9  557.25  4487.7  553.09  4708.9  552.81
  4836.6  549.33  4871.7  551.25  4885.9  549.11  4992.0  549.70  4996.7  547.84
  5006.2  549.64  5039.7  546.68  5039.9  546.18  5043.7  546.68  5048.6  548.91
  5055.8  547.35  5062.8  549.44  5070.0  547.72  5076.9  549.59  5084.1  547.48
  5091.1  549.14  5114.6  548.75  5130.6  552.41  5135.7  550.39  5157.6  552.53
  5418.4  552.57  5823.1  558.98  5943.7  563.33  6008.7  562.96  6223.2  567.16
#Mann=5,-1,0
  4378.8    0.05       0  5039.7    0.03       0  5043.7    0.05       0
  5823.1   0.075       0  6008.7    0.05       0
Bank Sta=5039.7,5043.7
Exp/Cntr=0.3,0.1

Type RM Length L Ch R = 1,5446,105,105,105
BEGIN DESCRIPTION:
Brushy Creek Tributary 6 11.0
END DESCRIPTION:
XS GIS Cut Line= 6
      2612098.05      7005797.01      2611798.10      7004511.38
      2611843.89      7004382.09      2611820.52      7004308.32
      2611760.58      7004263.65      2611675.99      7003610.96
#Sta/Elev= 30
  3465.3  561.56  3695.1  557.61  3847.4  553.08  4097.9  551.50  4320.2  546.17
  4402.4  544.62  4489.6  543.80  4661.3  542.51  4788.3  543.72  4823.5  541.57
  4880.0  541.40  4916.2  542.72  4920.5  541.08  4930.6  541.29  4933.8  537.78
  4934.1  537.28  4937.8  537.78  4955.2  538.51  4962.9  541.17  4968.1  538.77
  4995.2  541.62  4999.2  540.02  5022.5  541.34  5037.1  539.75  5062.5  543.03
  5117.8  546.05  5247.1  542.78  5269.0  542.99  5319.4  547.63  5732.9  558.01
#Mann=10,-1,0
  3465.3   0.075       0  3695.1    0.05       0  4320.2   0.075       0
  4402.4    0.05       0  4489.6   0.075       0  4661.3    0.05       0
  4933.8    0.05       0  4937.8    0.05       0  5062.5   0.075       0
  5247.1    0.05       0
Bank Sta=4933.8,4937.8
Exp/Cntr=0.3,0.1

Type RM Length L Ch R = 1,5341,341,341,341
BEGIN DESCRIPTION:
Mapping XS a7ba8261
END DESCRIPTION:
XS GIS Cut Line= 6
      2612306.39      7005637.31      2611892.50      7004802.23
      2611880.34      7004536.60      2611905.20      7004282.02
      2611816.11      7004159.87      2611765.87      7003197.89
#Sta/Elev= 30
  3553.0  559.79  3610.2  557.37  3760.9  557.92  3805.6  553.14  3884.8  553.80
  4060.4  547.54  4170.9  546.29  4392.0  545.55  4556.3  544.29  4626.4  541.83
  4682.1  543.01  4786.7  541.79  4887.2  543.09  4905.3  540.02  4905.5  539.52
  4909.3  540.02  4963.0  543.33  4968.0  542.11  5014.0  543.20  5074.8  542.03
  5135.3  541.36  5258.9  544.79  5708.4  557.47  5747.6  558.24  5807.7  556.81
  5867.7  560.71  6002.7  561.84  6078.0  561.39  6108.1  559.78  6121.2  561.22
#Mann=11,-1,0
  3553.0    0.05       0  4060.4   0.075       0  4170.9    0.05       0
  4392.0   0.075       0  4682.1    0.05       0  4905.3    0.05       0
  4909.3    0.05       0  5074.8   0.075       0  5258.9    0.05       0
  5708.4   0.075       0  6002.7    0.05       0
Bank Sta=4905.3,4909.3
Exp/Cntr=0.3,0.1

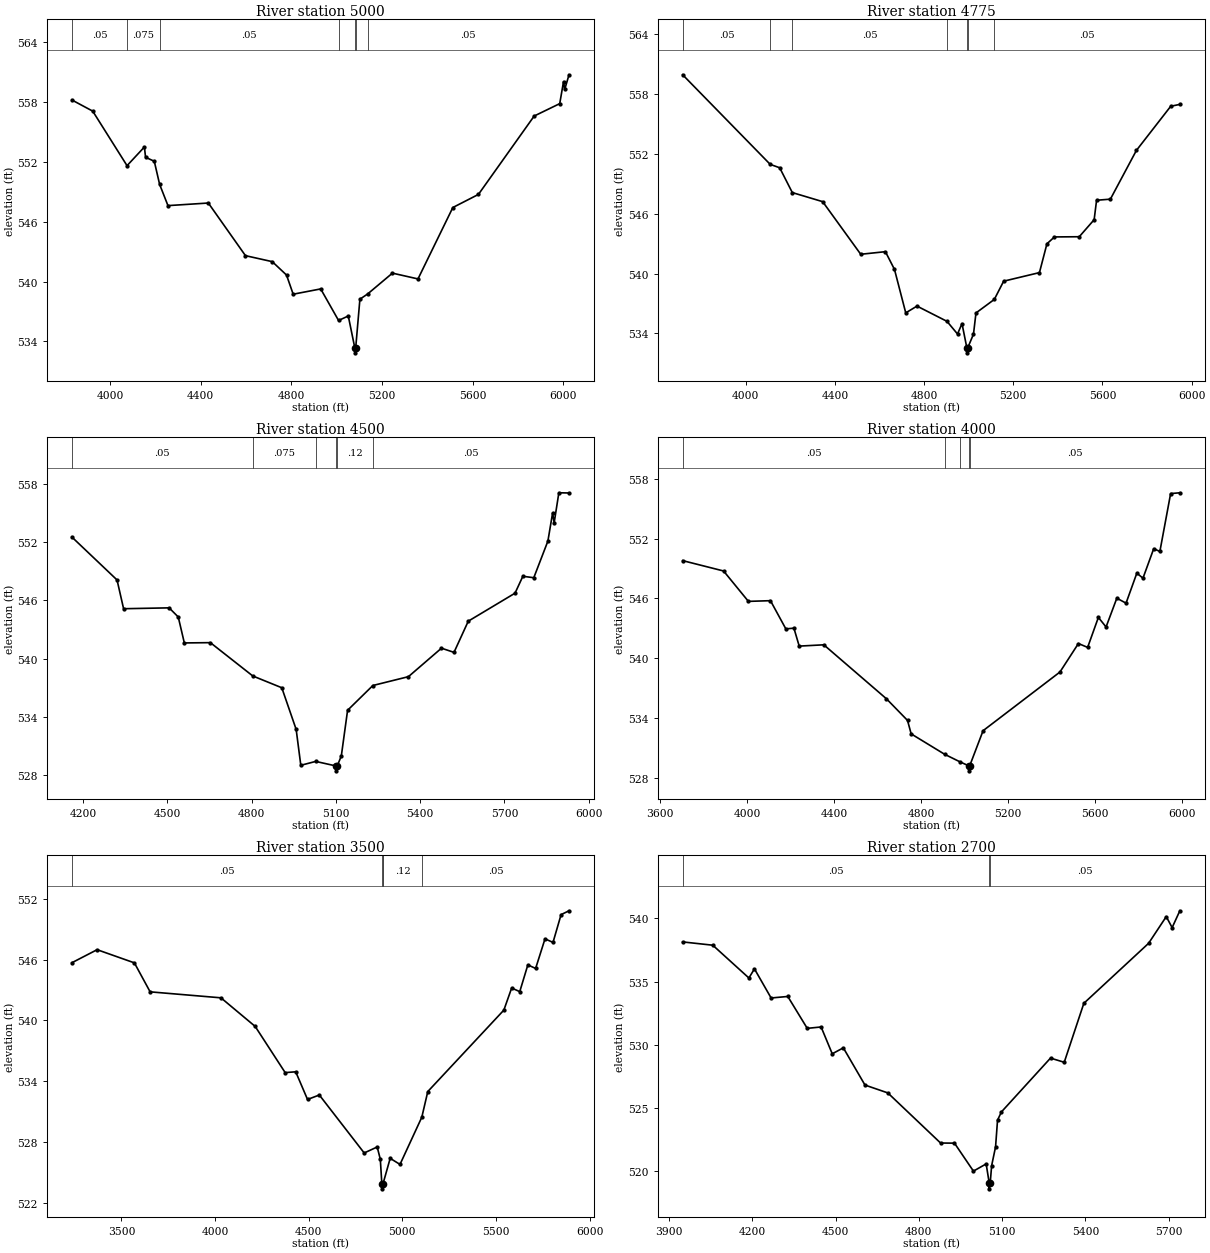
Type RM Length L Ch R = 1,5000,225,225,225
BEGIN DESCRIPTION:
Brushy Creek Tributary 6 10.0
END DESCRIPTION:
XS GIS Cut Line= 3
      2612325.19      7005572.60      2612201.13      7004411.41
      2611976.01      7003411.02
#Sta/Elev= 30
  3832.2  558.18  3924.3  557.06  4075.7  551.60  4152.3  553.47  4157.4  552.44
  4195.9  552.04  4219.4  549.73  4256.2  547.60  4434.3  547.86  4598.1  542.59
  4716.3  541.99  4779.2  540.65  4808.6  538.73  4930.0  539.26  5008.8  536.10
  5051.7  536.55  5080.4  533.36  5080.7  532.86  5084.4  533.36  5102.9  538.23
  5136.8  538.75  5246.4  540.84  5359.2  540.26  5512.9  547.41  5625.7  548.72
  5871.7  556.57  5984.4  557.81  6001.2  560.02  6006.3  559.23  6025.4  560.70
#Mann=7,-1,0
  3832.2    0.05       0  4075.7   0.075       0  4219.4    0.05       0
  5008.8    0.12       0  5080.4    0.03       0  5084.4    0.12       0
  5136.8    0.05       0
Bank Sta=5080.4,5084.4
Exp/Cntr=0.3,0.1

Type RM Length L Ch R = 1,4775,275,275,275
BEGIN DESCRIPTION:
Mapping XS 25044a87
END DESCRIPTION:
XS GIS Cut Line= 3
      2612566.94      7005582.08      2612391.56      7004321.25
      2612126.11      7003401.66
#Sta/Elev= 30
  3717.1  559.94  4109.8  550.95  4152.3  550.61  4208.9  548.12  4345.0  547.21
  4515.8  541.93  4626.5  542.19  4667.2  540.41  4717.7  536.05  4768.2  536.73
  4902.7  535.20  4949.9  533.93  4970.1  534.97  4991.8  532.54  4992.1  532.04
  4995.8  532.54  5021.6  533.92  5032.7  536.04  5115.0  537.40  5156.9  539.23
  5317.4  540.09  5351.0  542.98  5384.7  543.67  5496.0  543.69  5562.8  545.40
  5573.7  547.35  5635.6  547.46  5752.3  552.35  5906.3  556.78  5947.2  556.97
#Mann=7,-1,0
  3717.1    0.05       0  4109.8   0.075       0  4208.9    0.05       0
  4902.7    0.12       0  4991.8    0.07       0  4995.8    0.12       0
  5115.0    0.05       0
Bank Sta=4991.8,4995.8
Exp/Cntr=0.3,0.1

Type RM Length L Ch R = 1,4500,500,500,500
BEGIN DESCRIPTION:
Brushy Creek Tributary 6 9.0
END DESCRIPTION:
XS GIS Cut Line= 3
      2612825.99      7005160.96      2612645.95      7004340.89
      2612226.00      7003510.99
#Sta/Elev= 30
  4160.4  552.52  4321.3  548.10  4344.6  545.14  4506.7  545.23  4539.2  544.29
  4560.8  541.62  4653.5  541.65  4804.5  538.22  4907.7  537.01  4958.9  532.72
  4975.4  529.03  5028.5  529.43  5101.0  528.96  5101.2  528.46  5105.0  528.96
  5119.6  529.99  5141.9  534.69  5231.9  537.24  5358.5  538.15  5476.1  541.08
  5520.7  540.65  5571.5  543.86  5737.9  546.74  5765.8  548.48  5804.7  548.33
  5854.9  552.10  5871.6  554.98  5877.2  553.98  5893.9  557.07  5930.1  557.05
#Mann=6,-1,0
  4160.4    0.05       0  4804.5   0.075       0  5028.5    0.12       0
  5101.0    0.07       0  5105.0    0.12       0  5231.9    0.05       0
Bank Sta=5101,5105
Exp/Cntr=0.3,0.1

Type RM Length L Ch R = 1,4000,500,500,500
BEGIN DESCRIPTION:
Brushy Creek Tributary 6 8.0
END DESCRIPTION:
XS GIS Cut Line= 3
      2613510.22      7005311.93      2613030.19      7004107.03
      2612326.02      7003411.02
#Sta/Elev= 30
  3703.0  549.79  3891.2  548.75  4005.4  545.70  4106.9  545.77  4177.6  542.94
  4214.8  543.01  4239.1  541.21  4352.3  541.34  4640.5  535.92  4737.4  533.75
  4754.1  532.40  4908.2  530.35  4977.1  529.61  5019.3  529.19  5019.6  528.69
  5023.3  529.19  5085.0  532.72  5438.6  538.61  5523.5  541.47  5565.9  541.08
  5615.3  544.09  5650.7  543.13  5700.2  546.02  5742.6  545.52  5792.2  548.53
  5820.5  548.03  5869.9  550.99  5898.2  550.71  5947.7  556.52  5990.1  556.60
#Mann=5,-1,0
  3703.0    0.05       0  4908.2    0.12       0  4977.1    0.05       0
  5019.3    0.03       0  5023.3    0.05       0
Bank Sta=5019.3,5023.3
Exp/Cntr=0.3,0.1

Type RM Length L Ch R = 1,3500,800,800,800
BEGIN DESCRIPTION:
Brushy Creek Tributary 6 7.0
END DESCRIPTION:
XS GIS Cut Line= 3
      2613860.97      7005548.89      2613319.59      7003869.39
      2612626.03      7003311.02
#Sta/Elev= 30
  3235.4  545.68  3370.4  546.97  3569.4  545.67  3653.5  542.81  4031.7  542.22
  4214.4  539.40  4374.6  534.84  4430.9  534.92  4494.0  532.19  4557.0  532.63
  4796.6  526.91  4866.0  527.50  4882.7  526.29  4890.8  523.87  4891.1  523.37
  4894.8  523.87  4897.6  523.90  4935.4  526.38  4987.8  525.78  5104.3  530.44
  5136.2  532.97  5542.5  541.01  5584.1  543.19  5627.3  542.83  5670.5  545.47
  5712.1  545.12  5762.1  548.04  5804.9  547.69  5848.0  550.43  5890.4  550.81
#Mann=5,-1,0
  3235.4    0.05       0  4890.8    0.07       0  4894.8    0.05       0
  4897.6    0.12       0  5104.3    0.05       0
Bank Sta=4890.8,4894.8
Exp/Cntr=0.3,0.1

Type RM Length L Ch R = 1,2700,827,827,827
BEGIN DESCRIPTION:
Brushy Creek Tributary 6 6.0
END DESCRIPTION:
XS GIS Cut Line= 3
      2613974.74      7004719.39      2613918.93      7003629.05
      2613422.62      7003135.08
#Sta/Elev= 30
  3948.7  538.13  4057.2  537.87  4187.4  535.28  4207.4  536.00  4267.5  533.70
  4327.6  533.82  4397.7  531.30  4447.7  531.41  4487.8  529.29  4527.8  529.76
  4605.8  526.82  4688.1  526.20  4878.3  522.24  4928.4  522.23  4996.7  520.02
  5042.6  520.59  5053.3  519.12  5053.6  518.62  5057.3  519.12  5062.4  520.46
  5076.5  521.94  5083.6  524.05  5097.7  524.70  5274.5  528.95  5324.0  528.62
  5394.7  533.28  5628.1  538.02  5691.7  540.13  5712.9  539.26  5740.7  540.59
#Mann=3,-1,0
  3948.7    0.05       0  5053.3    0.04       0  5057.3    0.05       0
Bank Sta=5053.3,5057.3
Exp/Cntr=0.3,0.1

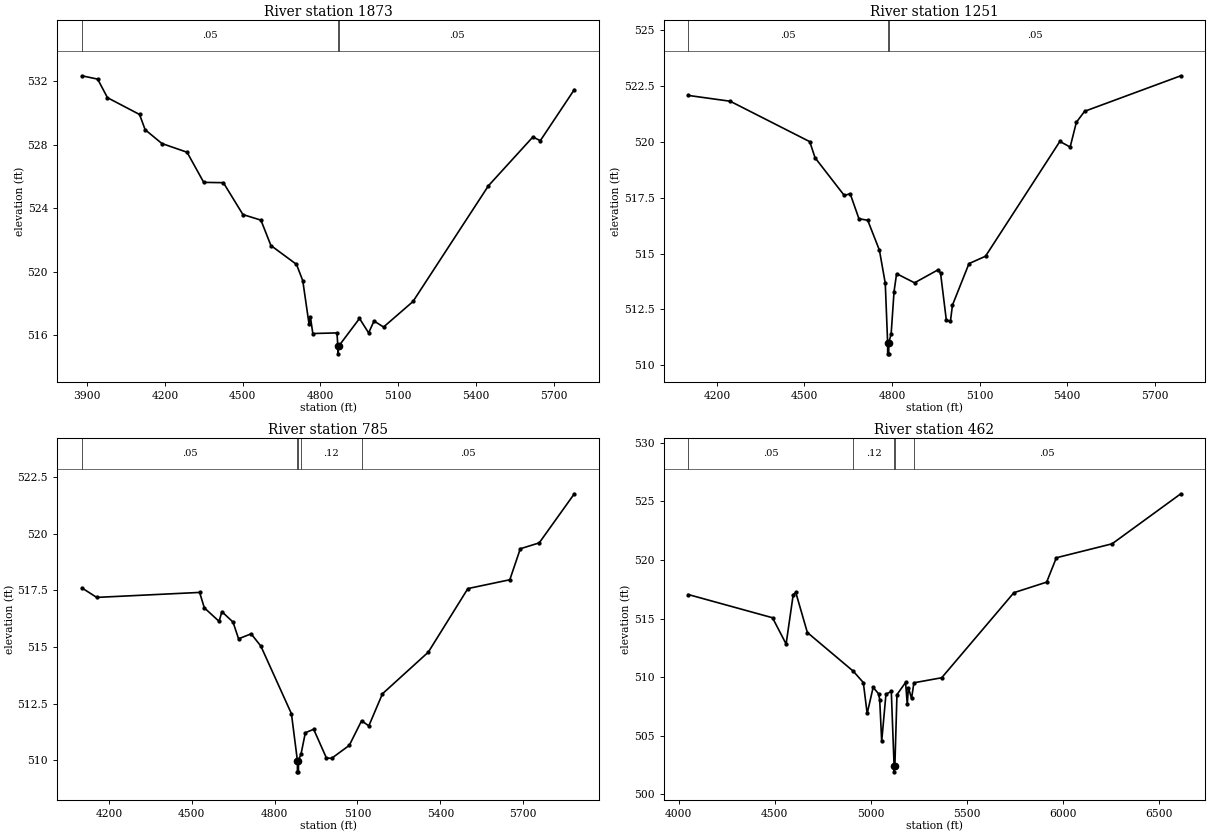
Type RM Length L Ch R = 1,1873,622,622,622
BEGIN DESCRIPTION:
Brushy Creek Tributary 6 5.0
END DESCRIPTION:
XS GIS Cut Line= 3
      2614284.24      7004407.49      2614665.19      7003457.75
      2613984.23      7002907.46
#Sta/Elev= 30
  3880.1  532.35  3941.0  532.14  3978.8  530.97  4102.6  529.91  4124.1  528.95
  4188.6  528.08  4285.7  527.53  4350.0  525.63  4425.8  525.61  4501.2  523.60
  4570.5  523.25  4609.0  521.65  4707.7  520.46  4731.9  519.43  4756.1  516.69
  4761.5  517.13  4770.6  516.10  4863.7  516.14  4867.1  515.32  4867.4  514.82
  4871.1  515.32  4950.6  517.05  4985.8  516.14  5006.6  516.89  5043.4  516.51
  5156.9  518.12  5447.9  525.42  5619.0  528.49  5647.8  528.26  5778.9  531.48
#Mann=3,-1,0
  3880.1    0.05       0  4867.1    0.04       0  4871.1    0.05       0
Bank Sta=4867.1,4871.1
Exp/Cntr=0.3,0.1

Type RM Length L Ch R = 1,1251,466,466,466
BEGIN DESCRIPTION:
Brushy Creek Tributary 6 4.0
END DESCRIPTION:
XS GIS Cut Line= 3
      2615098.14      7003904.08      2615041.09      7003038.38
      2614453.47      7002467.85
#Sta/Elev= 30
  4102.4  522.08  4245.8  521.82  4518.3  520.01  4536.4  519.29  4636.6  517.60
  4656.7  517.68  4686.7  516.56  4716.8  516.49  4756.9  515.15  4776.9  513.67
  4785.0  511.01  4785.2  510.51  4788.7  510.51  4789.0  511.01  4797.0  511.40
  4807.0  513.30  4815.7  514.10  4877.2  513.69  4957.3  514.27  4966.2  514.13
  4985.9  512.03  5000.0  511.96  5007.0  512.69  5063.6  514.55  5120.2  514.88
  5374.8  520.02  5410.1  519.77  5431.4  520.88  5459.7  521.37  5789.0  522.96
#Mann=3,-1,0
  4102.4    0.05       0  4785.0    0.03       0  4789.0    0.05       0
Bank Sta=4785,4789
Exp/Cntr=0.3,0.1

Type RM Length L Ch R = 1,785,323,323,323
BEGIN DESCRIPTION:
Mapping XS 6b52830d
END DESCRIPTION:
XS GIS Cut Line= 4
      2615474.04      7003814.39      2615368.41      7002934.12
      2615182.97      7002743.99      2614584.42      7002544.47
#Sta/Elev= 30
  4102.0  517.61  4155.8  517.19  4528.4  517.41  4545.4  516.73  4598.9  516.13
  4609.0  516.56  4649.3  516.10  4669.4  515.36  4714.9  515.58  4750.0  515.04
  4860.8  512.05  4882.4  509.98  4882.7  509.48  4886.2  509.48  4886.4  509.98
  4896.0  510.29  4911.2  511.21  4941.4  511.36  4987.6  510.09  5006.7  510.08
  5070.3  510.65  5114.9  511.74  5141.0  511.51  5190.4  512.93  5356.4  514.77
  5499.7  517.58  5651.5  517.97  5689.5  519.34  5758.0  519.60  5885.1  521.77
#Mann=5,-1,0
  4102.0    0.05       0  4882.4    0.07       0  4886.4    0.05       0
  4896.0    0.12       0  5114.9    0.05       0
Bank Sta=4882.4,4886.4
Exp/Cntr=0.3,0.1

Type RM Length L Ch R = 1,462,0,0,0
BEGIN DESCRIPTION:
Brushy Creek Tributary 6 1.0
END DESCRIPTION:
XS GIS Cut Line= 4
      2615538.77      7003797.83      2615629.31      7002852.95
      2615512.76      7002625.02      2614638.45      7001585.13
#Sta/Elev= 30
  4050.8  517.05  4489.1  515.07  4559.9  512.83  4596.8  517.03  4610.2  517.23
  4670.5  513.81  4909.5  510.51  4961.8  509.54  4981.9  506.90  5013.0  509.13
  5040.9  508.59  5047.1  508.08  5057.5  504.52  5079.7  508.55  5107.5  508.78
  5122.1  502.42  5122.3  501.92  5126.1  502.42  5137.0  508.51  5181.9  509.55
  5190.7  507.68  5196.4  509.10  5213.0  508.19  5225.2  509.52  5369.9  509.95
  5745.8  517.21  5916.2  518.11  5966.8  520.19  6257.0  521.38  6614.6  525.65
#Mann=5,-1,0
  4050.8    0.05       0  4909.5    0.12       0  5122.1    0.07       0
  5126.1    0.12       0  5225.2    0.05       0
Bank Sta=5122.1,5126.1
Exp/Cntr=0.3,0.1

Chan Stop Cuts=-1