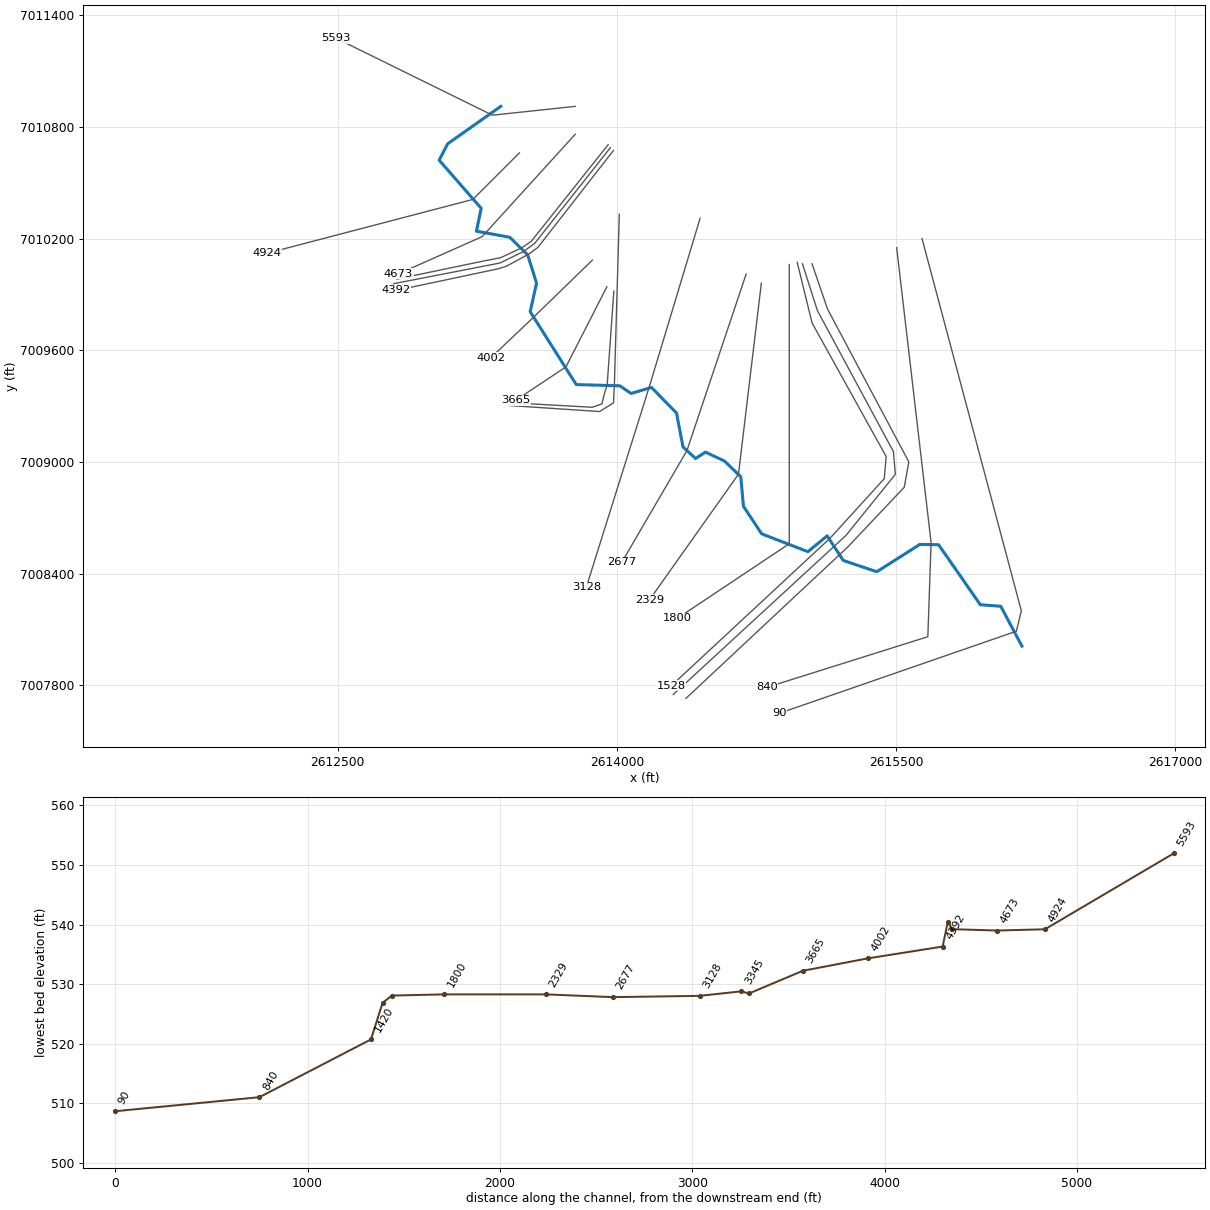
--- Brushy Creek Tributary 9.prj (project) ---

Proj Title=Brushy Creek Tributary 9 Base Level Engineering
Current Plan=p01
Default Exp/Contr=0.3,0.1
English Units
Geom File=g01
Flow File=f01
Plan File=p01
BEGIN DESCRIPTION:
Brushy Creek Tributary 9
END DESCRIPTION:

--- Brushy Creek Tributary 9.p01 (plan) ---

Plan Title=Multiple Run
Short Identifier=Multiple
Geom File=g01
Flow File=f01
Subcritical Flow
K Sum by GR= 0
Std Step Tol= 0.01
Critical Tol= 0.01
Num of Std Step Trials= 20
Max Error Tol= 0.3
Flow Tol Ratio= 0.001
Split Flow NTrial= 30
Split Flow Tol= 0.02
Split Flow Ratio= 0.02
Log Output Level= 0
Friction Slope Method= 1
Unsteady Friction Slope Method= 2
Unsteady Bridges Friction Slope Method= 1
Parabolic Critical Depth
Global Vel Dist=  1 , 1 , 1
Global Log Level= 0
CheckData=True
Encroach Param= -1, 0, 0, 0
BEGIN DESCRIPTION:
Multiple Run
END DESCRIPTION:

--- Brushy Creek Tributary 9.f01 (steady flow) ---

Flow Title=Multiple
Number of Profiles=7
Profile Names=10-year,25-year,50-year,1pct_min,100-year,1pct_plu,500-year
River Rch & RM= Brushy Creek Tri,Reach-1,5593
     275     351     410     238     476     949     638
River Rch & RM= Brushy Creek Tri,Reach-1,3128
     282     360     421     245     489     975     657
River Rch & RM= Brushy Creek Tri,Reach-1,2677
     327     423     497     290     579    1155     786
River Rch & RM= Brushy Creek Tri,Reach-1,840
     344     447     526     309     616    1229     840
Boundary for River Rch & Prof#=Brushy Creek Tri,Reach-1,1
Up Type=0
Dn Type=3
Dn Slope=0.005
Boundary for River Rch & Prof#=Brushy Creek Tri,Reach-1,2
Up Type=0
Dn Type=3
Dn Slope=0.005
Boundary for River Rch & Prof#=Brushy Creek Tri,Reach-1,3
Up Type=0
Dn Type=3
Dn Slope=0.005
Boundary for River Rch & Prof#=Brushy Creek Tri,Reach-1,4
Up Type=0
Dn Type=3
Dn Slope=0.005
Boundary for River Rch & Prof#=Brushy Creek Tri,Reach-1,5
Up Type=0
Dn Type=3
Dn Slope=0.005
Boundary for River Rch & Prof#=Brushy Creek Tri,Reach-1,6
Up Type=0
Dn Type=3
Dn Slope=0.005
Boundary for River Rch & Prof#=Brushy Creek Tri,Reach-1,7
Up Type=0
Dn Type=3
Dn Slope=0.005

--- Brushy Creek Tributary 9.g01 (geometry) ---

Geom Title=Existing Conditions

River Reach=Brushy Creek Tri,Reach-1
Reach XY= 30
      2613376.00      7010911.00      2613090.75      7010710.12
      2613044.91      7010621.92      2613270.87      7010363.28
      2613245.09      7010240.48      2613424.54      7010207.46
      2613520.49      7010113.44      2613568.22      7009960.90
      2613534.00      7009807.67      2613781.44      7009416.18
      2614015.56      7009409.62      2614076.01      7009368.59
      2614185.68      7009400.80      2614320.19      7009263.29
      2614355.10      7009080.84      2614422.63      7009018.99
      2614475.91      7009053.22      2614578.30      7009005.20
      2614665.53      7008920.82      2614679.76      7008762.56
      2614777.28      7008614.52      2615026.09      7008518.31
      2615129.58      7008603.50      2615215.90      7008471.39
      2615396.21      7008410.64      2615627.59      7008557.33
      2615728.44      7008555.61      2615952.30      7008233.37
      2616062.37      7008225.00      2616176.00      7008011.00

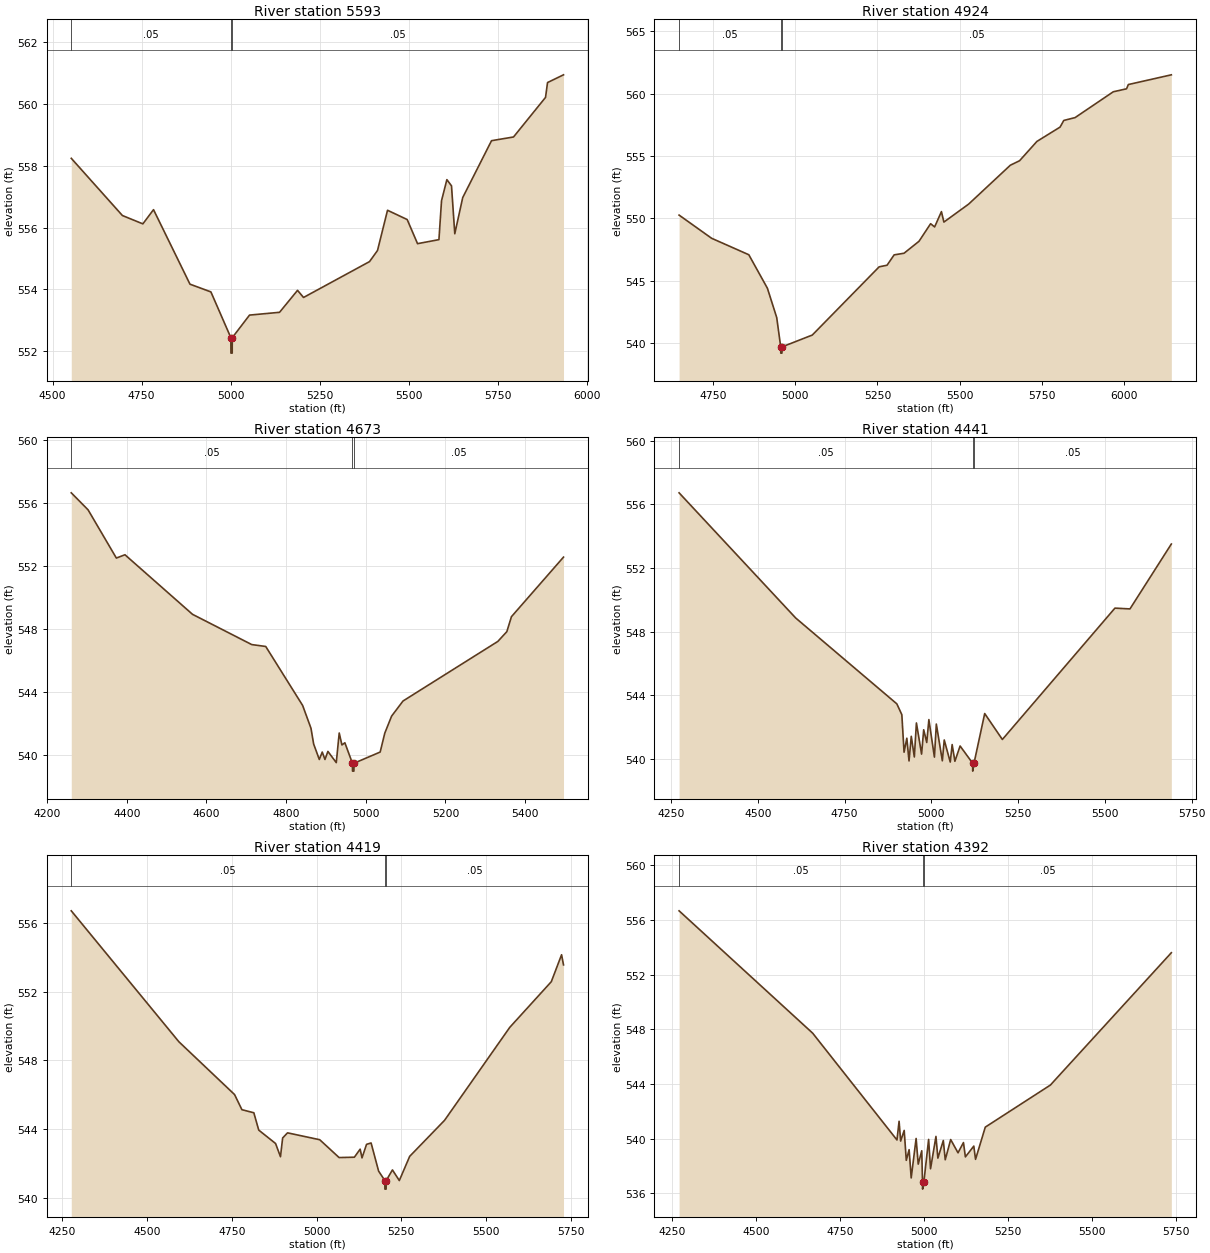
Type RM Length L Ch R = 1,5593,669,669,669
BEGIN DESCRIPTION:
Brushy Creek Tributary 9 12.0
END DESCRIPTION:
XS GIS Cut Line= 3
      2613776.00      7010911.00      2613331.23      7010863.55
      2612492.02      7011276.48
#Sta/Elev= 30
  4552.7  558.24  4696.3  556.39  4753.8  556.12  4783.7  556.58  4886.1  554.17
  4944.9  553.92  5000.9  552.44  5001.2  551.94  5004.7  551.94  5004.9  552.44
  5053.4  553.17  5137.7  553.26  5188.2  553.97  5205.1  553.74  5390.5  554.90
  5412.9  555.26  5441.0  556.56  5496.2  556.26  5525.3  555.48  5585.4  555.61
  5592.7  556.87  5607.7  557.55  5620.7  557.35  5629.9  555.80  5652.2  556.97
  5733.1  558.81  5794.9  558.93  5884.8  560.21  5890.4  560.69  5935.3  560.94
#Mann=3,-1,0
  4552.7    0.05       0  5000.9    0.04       0  5004.9    0.05       0
Bank Sta=5000.9,5004.9
Exp/Cntr=0.3,0.1

Type RM Length L Ch R = 1,4924,251,251,251
BEGIN DESCRIPTION:
Brushy Creek Tributary 9 11.0
END DESCRIPTION:
XS GIS Cut Line= 3
      2613475.98      7010660.98      2613226.00      7010411.00
      2612119.47      7010121.49
#Sta/Elev= 30
  4646.5  550.27  4745.5  548.41  4858.6  547.09  4915.2  544.40  4943.5  542.05
  4955.6  539.70  4955.8  539.20  4959.3  539.20  4959.6  539.70  5051.7  540.65
  5255.0  546.12  5279.1  546.25  5300.6  547.08  5330.7  547.21  5376.3  548.17
  5411.6  549.58  5423.8  549.32  5444.5  550.55  5452.0  549.71  5527.2  551.15
  5654.1  554.27  5682.2  554.63  5735.0  556.18  5805.5  557.33  5816.6  557.86
  5851.1  558.09  5967.2  560.16  6007.7  560.40  6013.0  560.74  6143.8  561.52
#Mann=3,-1,0
  4646.5    0.05       0  4955.6    0.04       0  4959.6    0.05       0
Bank Sta=4955.6,4959.6
Exp/Cntr=0.3,0.1

Type RM Length L Ch R = 1,4673,232,232,232
BEGIN DESCRIPTION:
Brushy Creek Tributary 9 10.0
END DESCRIPTION:
XS GIS Cut Line= 3
      2613776.01      7010761.01      2613276.00      7010211.00
      2612825.96      7010010.98
#Sta/Elev= 30
  4260.7  556.65  4302.9  555.57  4373.9  552.51  4395.5  552.72  4565.1  548.94
  4713.8  547.02  4748.9  546.90  4841.5  543.16  4862.5  541.71  4869.2  540.71
  4883.4  539.73  4890.8  540.20  4897.6  539.73  4905.0  540.24  4926.0  539.53
  4933.4  541.41  4940.2  540.65  4947.6  540.79  4966.5  539.49  4966.8  538.99
  4970.3  538.99  4970.5  539.49  5036.2  540.20  5047.8  541.40  5064.9  542.48
  5093.6  543.44  5331.6  547.22  5354.2  547.84  5365.8  548.79  5496.5  552.57
#Mann=3,-1,0
  4260.7    0.05       0  4966.5    0.03       0  4970.5    0.05       0
Bank Sta=4966.5,4970.5
Exp/Cntr=0.3,0.1

Type RM Length L Ch R = 1,4441,22,22,22
BEGIN DESCRIPTION:
Mapping XS 6305fac3
END DESCRIPTION:
XS GIS Cut Line= 6
      2613953.10      7010705.30      2613539.92      7010186.21
      2613489.57      7010151.49      2613374.99      7010097.67
      2613284.71      7010080.31      2612819.32      7009983.43
#Sta/Elev= 30
  4272.9  556.72  4608.9  548.85  4900.4  543.45  4914.8  542.77  4921.2  540.41
  4929.2  541.29  4935.5  539.86  4942.0  541.41  4950.8  540.11  4956.8  542.25
  4971.7  540.29  4977.8  541.82  4986.6  541.02  4992.7  542.46  5008.7  540.10
  5014.2  542.18  5031.5  539.87  5037.0  541.18  5054.3  539.79  5059.8  540.89
  5067.7  539.84  5082.7  540.80  5118.8  539.72  5119.0  539.22  5122.8  539.72
  5153.6  542.84  5204.5  541.21  5528.9  549.47  5572.2  549.42  5691.4  553.50
#Mann=3,-1,0
  4272.9    0.05       0  5118.8    0.03       0  5122.8    0.05       0
Bank Sta=5118.8,5122.8
Exp/Cntr=0.3,0.1

Type RM Length L Ch R = 1,4419,27,27,27
BEGIN DESCRIPTION:
Mapping XS 1e1df84d
END DESCRIPTION:
XS GIS Cut Line= 5
      2613964.77      7010689.03      2613558.49      7010175.10
      2613499.47      7010131.70      2613370.99      7010069.20
      2612800.45      7009958.21
#Sta/Elev= 30
  4276.3  556.71  4593.8  549.08  4758.2  546.00  4779.8  545.12  4815.0  544.94
  4829.5  543.93  4879.1  543.15  4893.6  542.38  4900.0  543.47  4914.4  543.77
  5009.4  543.37  5066.6  542.33  5111.7  542.35  5128.7  542.82  5134.2  542.31
  5147.6  543.10  5161.0  543.18  5183.2  541.54  5201.6  540.99  5201.8  540.49
  5205.3  540.49  5205.6  540.99  5224.0  541.61  5244.3  540.99  5274.9  542.40
  5377.8  544.50  5570.3  549.92  5692.8  552.58  5723.1  554.15  5728.8  553.56
#Mann=3,-1,0
  4276.3    0.05       0  5201.6    0.04       0  5205.6    0.05       0
Bank Sta=5201.6,5205.6
Exp/Cntr=0.3,0.1

Type RM Length L Ch R = 1,4392,390,390,390
BEGIN DESCRIPTION:
Mapping XS 28ef8055
END DESCRIPTION:
XS GIS Cut Line= 6
      2613981.56      7010674.04      2613575.33      7010153.23
      2613528.46      7010118.50      2613406.93      7010052.53
      2613363.53      7010038.64      2612814.91      7009922.32
#Sta/Elev= 30
  4271.7  556.68  4668.9  547.72  4919.5  539.90  4925.8  541.27  4930.4  539.82
  4941.0  540.60  4947.2  538.41  4955.6  539.19  4961.8  537.12  4976.4  540.01
  4982.7  538.13  4993.2  539.11  4995.4  536.80  4995.7  536.30  4999.4  536.80
  5013.6  539.94  5019.3  537.79  5035.4  540.16  5041.1  538.57  5057.3  539.86
  5063.0  538.45  5079.2  539.93  5101.0  538.96  5117.2  539.71  5122.9  538.66
  5147.9  539.45  5153.1  538.48  5182.1  540.84  5375.6  543.92  5735.2  553.61
#Mann=3,-1,0
  4271.7    0.05       0  4995.4    0.04       0  4999.4    0.05       0
Bank Sta=4995.4,4999.4
Exp/Cntr=0.3,0.1

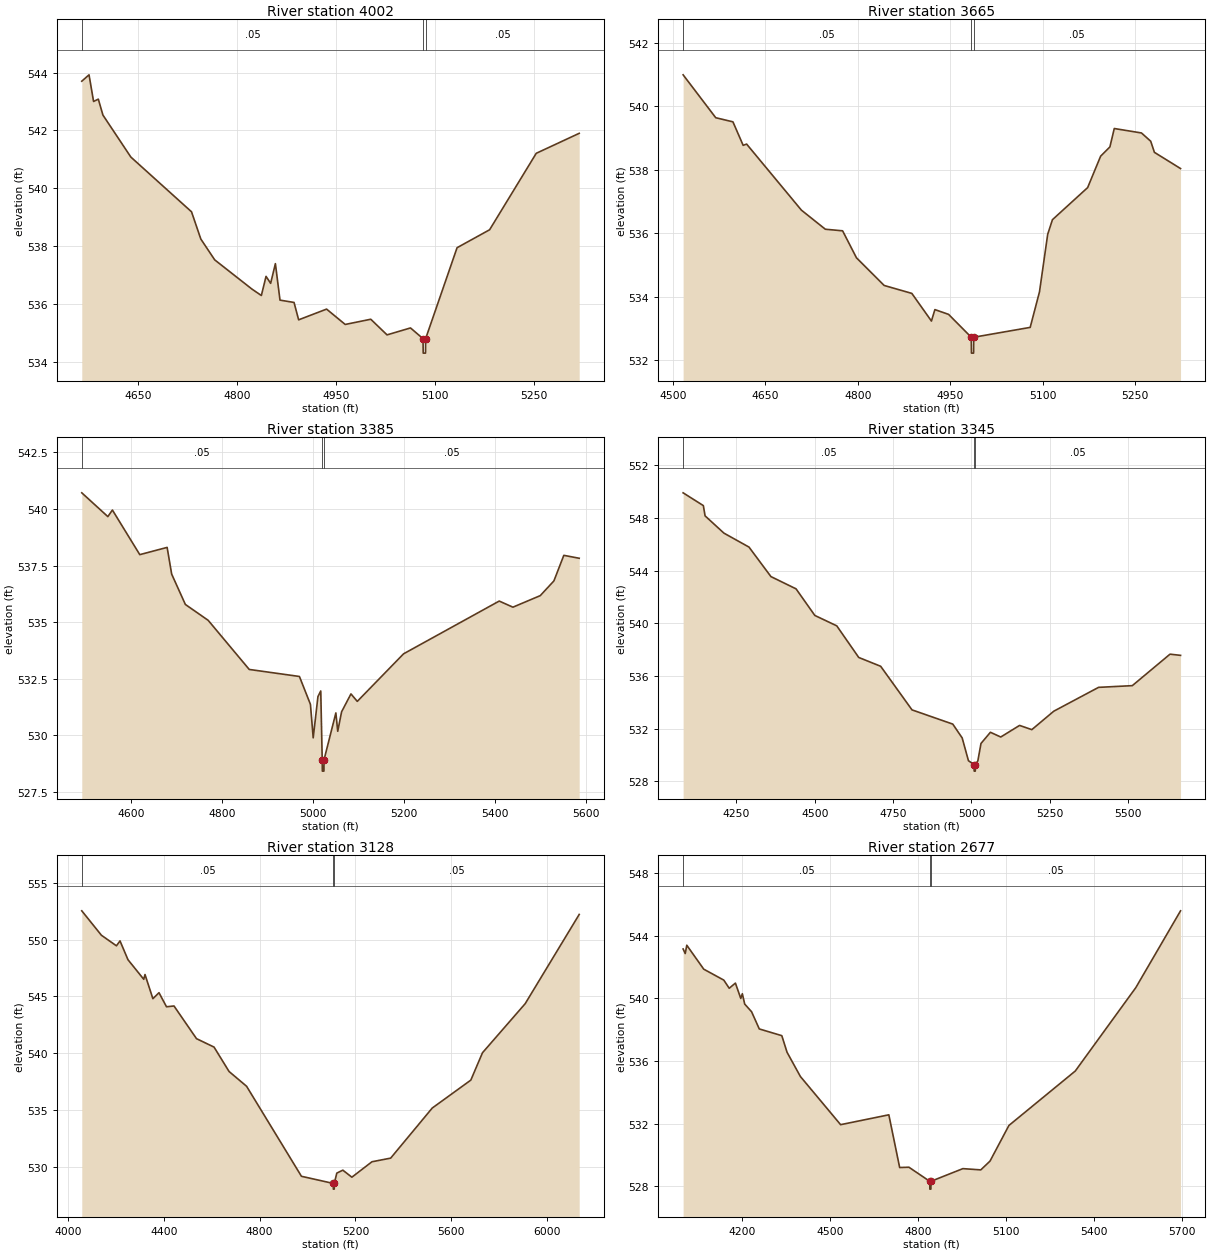
Type RM Length L Ch R = 1,4002,337,337,337
BEGIN DESCRIPTION:
Brushy Creek Tributary 9 8.0
END DESCRIPTION:
XS GIS Cut Line= 3
      2613867.86      7010084.60      2613555.18      7009781.03
      2613323.62      7009561.19
#Sta/Elev= 30
  4564.2  543.70  4575.2  543.92  4582.1  543.00  4589.3  543.08  4596.3  542.53
  4638.7  541.08  4730.8  539.19  4744.9  538.25  4766.0  537.53  4822.6  536.52
  4836.8  536.30  4843.9  536.96  4850.9  536.72  4858.1  537.40  4865.1  536.14
  4886.4  536.06  4893.4  535.46  4935.8  535.83  4964.1  535.30  5002.9  535.48
  5027.6  534.94  5063.2  535.18  5082.2  534.81  5082.5  534.31  5086.0  534.31
  5086.2  534.81  5133.9  537.95  5183.3  538.57  5254.1  541.21  5319.3  541.90
#Mann=3,-1,0
  4564.2    0.05       0  5082.2    0.03       0  5086.2    0.05       0
Bank Sta=5082.2,5086.2
Exp/Cntr=0.3,0.1

Type RM Length L Ch R = 1,3665,280,280,280
BEGIN DESCRIPTION:
Brushy Creek Tributary 9 7.0
END DESCRIPTION:
XS GIS Cut Line= 3
      2613946.01      7009941.38      2613726.00      7009511.00
      2613456.45      7009332.03
#Sta/Elev= 30
  4516.8  540.99  4569.7  539.64  4597.6  539.51  4614.2  538.77  4619.8  538.81
  4708.7  536.73  4747.5  536.13  4775.5  536.08  4798.0  535.23  4842.9  534.36
  4887.8  534.11  4919.6  533.24  4925.2  533.60  4947.4  533.45  4984.2  532.73
  4984.5  532.23  4988.0  532.23  4988.2  532.73  5079.8  533.04  5094.9  534.16
  5108.2  535.97  5115.9  536.43  5173.0  537.44  5194.1  538.43  5209.1  538.72
  5216.2  539.30  5260.3  539.16  5275.3  538.90  5281.3  538.55  5323.7  538.04
#Mann=3,-1,0
  4516.8    0.05       0  4984.2    0.03       0  4988.2    0.05       0
Bank Sta=4984.2,4988.2
Exp/Cntr=0.3,0.1

Type RM Length L Ch R = 1,3385,40,40,40
BEGIN DESCRIPTION:
Mapping XS fd104554
END DESCRIPTION:
XS GIS Cut Line= 6
      2613983.54      7009918.14      2613947.73      7009416.84
      2613930.37      7009358.25      2613919.52      7009312.68
      2613867.44      7009294.23      2613440.49      7009318.07
#Sta/Elev= 30
  4491.5  540.71  4548.8  539.66  4558.8  539.95  4619.0  537.98  4679.1  538.30
  4689.1  537.12  4719.2  535.78  4769.3  535.08  4859.6  532.91  4969.9  532.60
  4994.1  531.37  5000.2  529.89  5010.6  531.71  5016.8  531.96  5020.0  528.92
  5020.3  528.42  5023.8  528.42  5024.0  528.92  5050.0  530.99  5054.1  530.18
  5062.6  531.04  5083.2  531.83  5097.1  531.50  5198.8  533.60  5409.1  535.93
  5439.2  535.66  5499.3  536.17  5529.3  536.82  5551.1  537.95  5584.9  537.82
#Mann=3,-1,0
  4491.5    0.05       0  5020.0    0.04       0  5024.0    0.05       0
Bank Sta=5020,5024
Exp/Cntr=0.3,0.1

Type RM Length L Ch R = 1,3345,217,217,217
BEGIN DESCRIPTION:
Brushy Creek Tributary 9 6.0
END DESCRIPTION:
XS GIS Cut Line= 5
      2614012.85      7010331.12      2613986.21      7009411.40
      2613981.63      7009318.01      2613906.88      7009271.26
      2613422.43      7009303.59
#Sta/Elev= 30
  4079.9  549.91  4144.4  548.94  4150.0  548.16  4210.1  546.85  4290.1  545.79
  4360.1  543.55  4440.2  542.62  4500.2  540.60  4570.2  539.81  4640.3  537.41
  4710.3  536.74  4810.3  533.43  4940.4  532.35  4970.4  531.30  4990.4  529.57
  5008.4  529.28  5008.7  528.78  5012.2  528.78  5012.4  529.28  5020.4  529.56
  5030.4  530.88  5060.5  531.73  5093.5  531.37  5153.5  532.25  5192.6  531.93
  5262.7  533.33  5405.6  535.14  5513.3  535.27  5633.6  537.66  5667.2  537.57
#Mann=3,-1,0
  4079.9    0.05       0  5008.4    0.04       0  5012.4    0.05       0
Bank Sta=5008.4,5012.4
Exp/Cntr=0.3,0.1

Type RM Length L Ch R = 1,3128,451,451,451
BEGIN DESCRIPTION:
Brushy Creek Tributary 9 5.0
END DESCRIPTION:
XS GIS Cut Line= 3
      2614446.88      7010309.45      2614176.00      7009411.00
      2613834.90      7008325.95
#Sta/Elev= 30
  4058.0  552.53  4139.9  550.38  4202.6  549.45  4217.6  549.88  4250.6  548.23
  4316.6  546.50  4321.8  546.92  4354.8  544.79  4380.2  545.32  4411.5  544.08
  4442.8  544.15  4536.8  541.27  4609.9  540.53  4672.6  538.38  4745.7  537.08
  4974.7  529.15  5107.8  528.52  5108.0  528.02  5111.5  528.02  5111.8  528.52
  5122.2  529.43  5147.4  529.69  5185.1  529.07  5268.9  530.43  5347.0  530.75
  5520.5  535.16  5681.5  537.62  5730.2  540.03  5908.3  544.35  6133.8  552.21
#Mann=3,-1,0
  4058.0    0.05       0  5107.8    0.04       0  5111.8    0.05       0
Bank Sta=5107.8,5111.8
Exp/Cntr=0.3,0.1

Type RM Length L Ch R = 1,2677,348,348,348
BEGIN DESCRIPTION:
Brushy Creek Tributary 9 4.0
END DESCRIPTION:
XS GIS Cut Line= 3
      2614694.28      7010009.97      2614376.00      7009061.00
      2614026.02      7008461.03
#Sta/Elev= 30
  3998.4  543.16  4005.6  542.87  4010.9  543.40  4068.7  541.87  4137.1  541.17
  4155.5  540.65  4176.6  540.98  4194.9  540.00  4200.2  540.30  4208.3  539.64
  4231.7  539.15  4258.0  538.05  4334.8  537.62  4352.6  536.56  4398.1  535.01
  4535.2  531.93  4699.6  532.56  4736.5  529.19  4768.0  529.21  4839.1  528.31
  4839.4  527.81  4842.9  527.81  4843.1  528.31  4952.0  529.12  5013.0  529.04
  5044.4  529.60  5108.9  531.88  5335.1  535.36  5541.4  540.69  5693.9  545.60
#Mann=3,-1,0
  3998.4    0.05       0  4839.1    0.03       0  4843.1    0.05       0
Bank Sta=4839.1,4843.1
Exp/Cntr=0.3,0.1

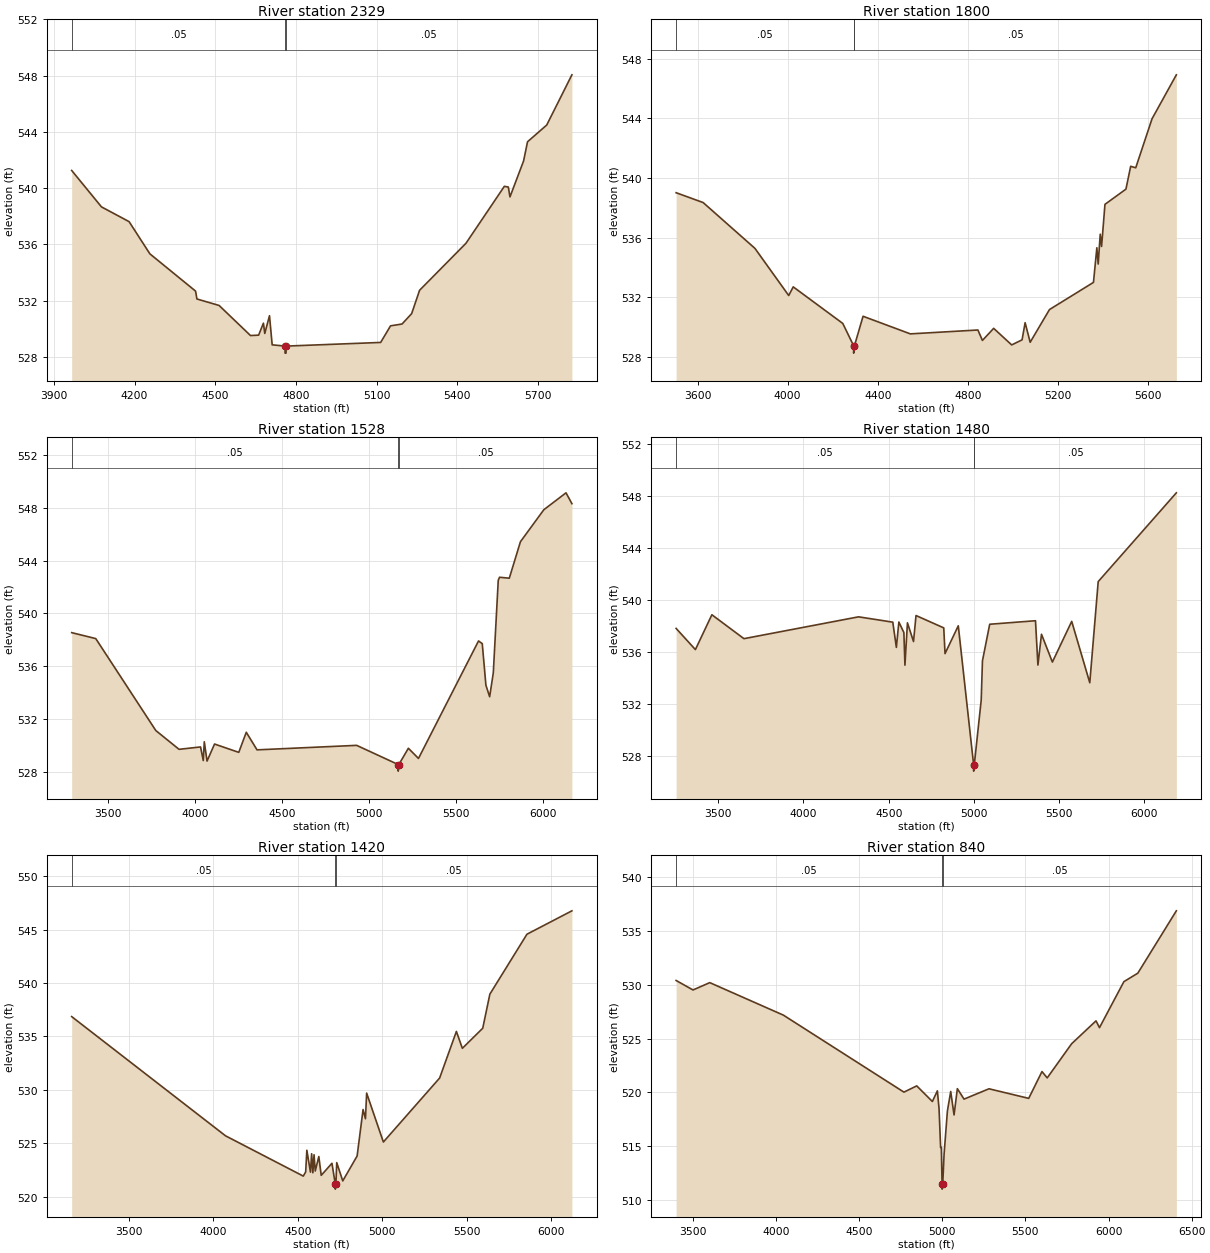
Type RM Length L Ch R = 1,2329,529,529,529
BEGIN DESCRIPTION:
Brushy Creek Tributary 9 3.0
END DESCRIPTION:
XS GIS Cut Line= 3
      2614775.99      7009960.96      2614653.16      7008934.58
      2614175.98      7008260.97
#Sta/Elev= 30
  3966.3  541.26  4077.0  538.67  4179.7  537.62  4257.0  535.33  4426.8  532.68
  4431.8  532.12  4514.2  531.66  4631.0  529.52  4661.2  529.55  4678.9  530.40
  4684.0  529.67  4701.5  530.93  4711.5  528.86  4759.3  528.77  4759.5  528.27
  4763.0  528.27  4763.3  528.77  5114.7  529.03  5151.4  530.21  5194.2  530.34
  5229.9  531.08  5259.4  532.74  5431.7  536.08  5574.4  540.13  5589.2  540.08
  5595.3  539.38  5645.8  541.93  5660.6  543.30  5731.9  544.49  5825.5  548.06
#Mann=3,-1,0
  3966.3    0.05       0  4759.3    0.03       0  4763.3    0.05       0
Bank Sta=4759.3,4763.3
Exp/Cntr=0.3,0.1

Type RM Length L Ch R = 1,1800,272,272,272
BEGIN DESCRIPTION:
Brushy Creek Tributary 9 2.0
END DESCRIPTION:
XS GIS Cut Line= 3
      2614926.00      7010061.02      2614926.00      7008561.00
      2614326.02      7008161.01
#Sta/Elev= 30
  3505.0  539.02  3625.0  538.36  3855.0  535.29  4005.0  532.13  4025.0  532.71
  4245.0  530.26  4293.0  528.77  4293.3  528.27  4297.0  528.77  4335.0  530.74
  4545.0  529.56  4845.0  529.82  4865.0  529.12  4915.0  529.93  4995.0  528.82
  5041.1  529.16  5054.6  530.31  5077.1  529.00  5162.8  531.19  5358.1  533.01
  5373.1  535.33  5379.1  534.24  5388.1  536.24  5394.1  535.42  5409.1  538.24
  5502.3  539.26  5523.3  540.79  5545.8  540.69  5618.0  543.97  5726.1  546.92
#Mann=3,-1,0
  3505.0    0.05       0  4293.0    0.03       0  4297.0    0.05       0
Bank Sta=4293,4297
Exp/Cntr=0.3,0.1

Type RM Length L Ch R = 1,1528,48,48,48
BEGIN DESCRIPTION:
Mapping XS ea16a9dc
END DESCRIPTION:
XS GIS Cut Line= 6
      2614968.62      7010072.83      2615048.60      7009746.95
      2615446.77      7009029.31      2615436.30      7008910.64
      2615146.38      7008591.94      2614291.50      7007797.26
#Sta/Elev= 30
  3292.5  538.55  3430.9  538.10  3776.1  531.14  3909.6  529.72  4033.1  529.90
  4048.8  528.87  4054.6  530.29  4070.4  528.83  4113.5  530.12  4252.8  529.49
  4295.9  531.01  4357.7  529.68  4930.3  530.02  5168.7  528.57  5169.0  528.07
  5172.7  528.57  5227.4  529.80  5285.5  529.03  5630.5  537.92  5652.0  537.72
  5673.0  534.57  5694.5  533.70  5715.5  535.51  5743.9  542.51  5751.2  542.74
  5807.4  542.67  5871.4  545.43  6005.8  547.85  6133.3  549.13  6167.2  548.31
#Mann=3,-1,0
  3292.5    0.05       0  5168.7    0.03       0  5172.7    0.05       0
Bank Sta=5168.7,5172.7
Exp/Cntr=0.3,0.1

Type RM Length L Ch R = 1,1480,60,60,60
BEGIN DESCRIPTION:
Mapping XS e0c27760
END DESCRIPTION:
XS GIS Cut Line= 6
      2614996.91      7010064.82      2615077.19      7009813.51
      2615485.54      7009056.14      2615496.01      7008933.99
      2615230.76      7008605.91      2614302.36      7007750.80
#Sta/Elev= 30
  3253.1  537.81  3366.2  536.18  3462.8  538.86  3650.9  537.02  4323.2  538.70
  4523.9  538.29  4544.8  536.35  4559.5  538.30  4588.9  537.49  4595.1  534.98
  4609.8  538.24  4645.4  536.80  4660.1  538.80  4822.8  537.85  4830.2  535.87
  4908.0  538.01  4997.9  527.33  4998.1  526.83  5001.9  527.33  5042.4  532.29
  5049.8  535.32  5092.3  538.13  5360.8  538.40  5375.0  534.99  5396.0  537.36
  5459.9  535.22  5573.2  538.35  5679.2  533.63  5728.6  541.41  6186.9  548.24
#Mann=3,-1,0
  3253.1    0.05       0  4997.9    0.03       0  5001.9    0.05       0
Bank Sta=4997.9,5001.9
Exp/Cntr=0.3,0.1

Type RM Length L Ch R = 1,1420,580,580,580
BEGIN DESCRIPTION:
Mapping XS 29d68c2d
END DESCRIPTION:
XS GIS Cut Line= 6
      2615048.24      7010065.27      2615132.00      7009820.96
      2615568.27      7009000.77      2615543.84      7008864.65
      2615240.20      7008543.56      2614371.12      7007730.33
#Sta/Elev= 30
  3163.4  536.86  4073.2  525.70  4533.1  521.93  4547.2  522.32  4554.1  524.35
  4575.5  522.30  4582.4  524.02  4589.7  522.24  4596.6  523.93  4603.9  522.41
  4624.9  523.76  4639.1  522.00  4702.6  523.13  4722.0  521.21  4722.3  520.71
  4726.0  521.21  4730.9  523.19  4766.5  521.48  4851.4  523.81  4886.6  528.16
  4900.8  527.30  4907.7  529.70  5006.7  525.12  5339.4  531.11  5438.5  535.47
  5473.7  533.89  5594.3  535.77  5636.4  538.96  5855.7  544.57  6121.6  546.76
#Mann=3,-1,0
  3163.4    0.05       0  4722.0    0.04       0  4726.0    0.05       0
Bank Sta=4722,4726
Exp/Cntr=0.3,0.1

Type RM Length L Ch R = 1,840,750,750,750
BEGIN DESCRIPTION:
Mapping XS bd23ea02
END DESCRIPTION:
XS GIS Cut Line= 4
      2615502.99      7010152.03      2615687.97      7008567.52
      2615670.52      7008061.45      2614804.96      7007789.22
#Sta/Elev= 30
  3399.0  530.39  3500.7  529.51  3601.4  530.19  4044.4  527.17  4769.3  520.02
  4846.4  520.60  4940.4  519.15  4970.6  520.14  4980.7  518.47  4990.0  514.88
  4994.3  514.88  4998.8  511.51  4999.0  511.01  5002.8  511.51  5010.8  514.24
  5030.8  518.26  5050.8  520.08  5070.8  517.90  5090.8  520.34  5130.9  519.37
  5281.0  520.33  5520.0  519.44  5599.7  521.93  5631.2  521.34  5777.9  524.51
  5924.7  526.64  5945.7  526.01  6092.4  530.28  6176.3  531.07  6408.0  536.86
#Mann=3,-1,0
  3399.0    0.05       0  4998.8    0.03       0  5002.8    0.05       0
Bank Sta=4998.8,5002.8
Exp/Cntr=0.3,0.1

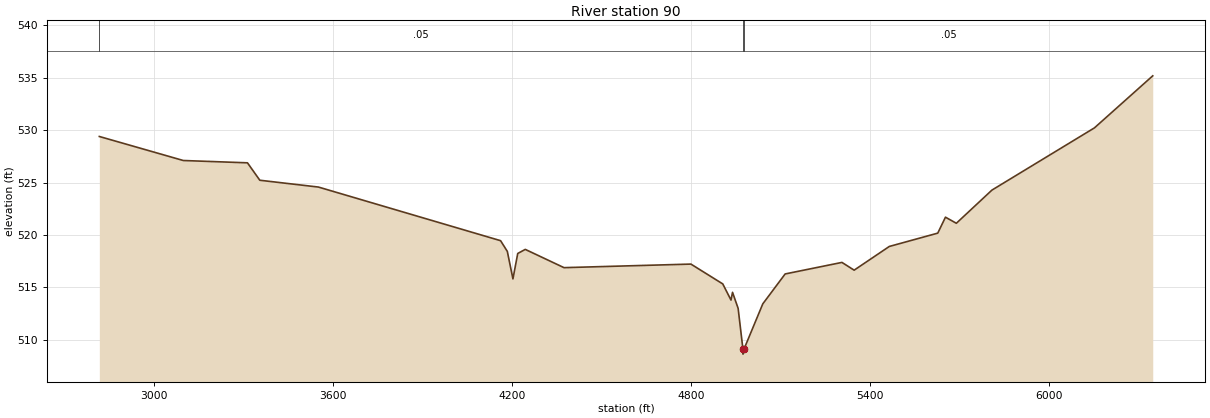
Type RM Length L Ch R = 1,90,0,0,0
BEGIN DESCRIPTION:
Brushy Creek Tributary 9 1.0
END DESCRIPTION:
XS GIS Cut Line= 4
      2615639.12      7010200.87      2616172.76      7008201.19
      2616146.23      7008091.10      2614871.30      7007649.62
#Sta/Elev= 30
  2817.1  529.39  3098.7  527.10  3313.8  526.88  3355.2  525.22  3551.8  524.57
  4162.5  519.46  4185.1  518.44  4203.9  515.82  4220.0  518.24  4245.3  518.63
  4375.2  516.89  4800.7  517.23  4907.5  515.34  4935.1  513.80  4940.2  514.54
  4959.0  513.01  4975.0  509.15  4975.3  508.65  4979.0  509.15  5041.7  513.44
  5116.7  516.29  5307.1  517.39  5348.0  516.65  5465.9  518.91  5628.4  520.18
  5654.2  521.70  5690.7  521.12  5810.0  524.28  6153.7  530.21  6349.2  535.17
#Mann=3,-1,0
  2817.1    0.05       0  4975.0    0.04       0  4979.0    0.05       0
Bank Sta=4975,4979
Exp/Cntr=0.3,0.1

Chan Stop Cuts=-1