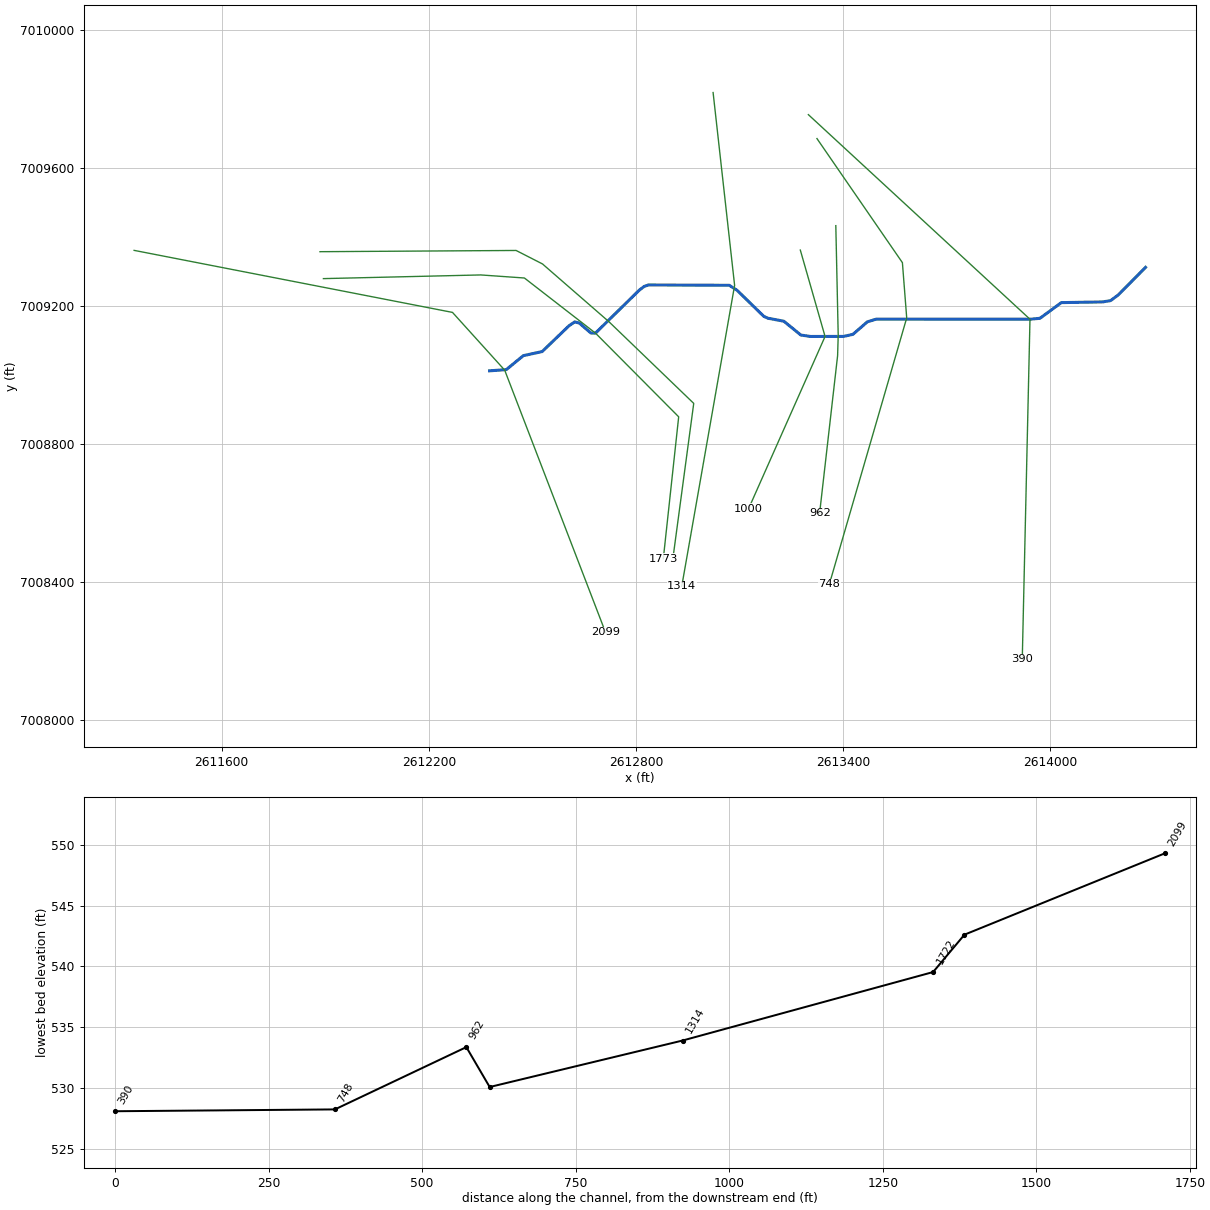
--- Brushy Creek Tributary 9_1.prj (project) ---

Proj Title=Brushy Creek Tributary 9_1 Base Level Engineering
Current Plan=p01
Default Exp/Contr=0.3,0.1
English Units
Geom File=g01
Flow File=f01
Plan File=p01
BEGIN DESCRIPTION:
Brushy Creek Tributary 9_1
END DESCRIPTION:

--- Brushy Creek Tributary 9_1.p01 (plan) ---

Plan Title=Multiple Run
Short Identifier=Multiple
Geom File=g01
Flow File=f01
Subcritical Flow
K Sum by GR= 0
Std Step Tol= 0.01
Critical Tol= 0.01
Num of Std Step Trials= 20
Max Error Tol= 0.3
Flow Tol Ratio= 0.001
Split Flow NTrial= 30
Split Flow Tol= 0.02
Split Flow Ratio= 0.02
Log Output Level= 0
Friction Slope Method= 1
Unsteady Friction Slope Method= 2
Unsteady Bridges Friction Slope Method= 1
Parabolic Critical Depth
Global Vel Dist=  1 , 1 , 1
Global Log Level= 0
CheckData=True
Encroach Param= -1, 0, 0, 0
BEGIN DESCRIPTION:
Multiple Run
END DESCRIPTION:

--- Brushy Creek Tributary 9_1.f01 (steady flow) ---

Flow Title=Multiple
Number of Profiles=7
Profile Names=10-year,25-year,50-year,1pct_min,100-year,1pct_plu,500-year
River Rch & RM= Brushy Creek Tri,Reach-1,2099
     276     355     415     242     484     965     654
Boundary for River Rch & Prof#=Brushy Creek Tri,Reach-1,1
Up Type=0
Dn Type=3
Dn Slope=0.005
Boundary for River Rch & Prof#=Brushy Creek Tri,Reach-1,2
Up Type=0
Dn Type=3
Dn Slope=0.005
Boundary for River Rch & Prof#=Brushy Creek Tri,Reach-1,3
Up Type=0
Dn Type=3
Dn Slope=0.005
Boundary for River Rch & Prof#=Brushy Creek Tri,Reach-1,4
Up Type=0
Dn Type=3
Dn Slope=0.005
Boundary for River Rch & Prof#=Brushy Creek Tri,Reach-1,5
Up Type=0
Dn Type=3
Dn Slope=0.005
Boundary for River Rch & Prof#=Brushy Creek Tri,Reach-1,6
Up Type=0
Dn Type=3
Dn Slope=0.005
Boundary for River Rch & Prof#=Brushy Creek Tri,Reach-1,7
Up Type=0
Dn Type=3
Dn Slope=0.005

--- Brushy Creek Tributary 9_1.g01 (geometry) ---

Geom Title=Existing Conditions

River Reach=Brushy Creek Tri,Reach-1
Reach XY= 30
      2612376.00      7009011.00      2612424.51      7009014.60
      2612473.76      7009055.03      2612528.31      7009066.85
      2612606.02      7009141.59      2612622.67      7009152.98
      2612636.00      7009149.29      2612669.33      7009120.62
      2612682.67      7009120.30      2612809.24      7009244.57
      2612823.55      7009255.54      2612836.43      7009259.95
      2613070.14      7009258.94      2613092.75      7009244.54
      2613169.95      7009169.16      2613182.04      7009163.50
      2613228.17      7009154.86      2613277.56      7009114.74
      2613305.86      7009110.60      2613401.07      7009110.77
      2613428.33      7009116.74      2613469.94      7009152.86
      2613496.03      7009160.93      2613941.18      7009160.57
      2613970.06      7009163.26      2614031.94      7009208.73
      2614151.11      7009210.73      2614174.55      7009214.49
      2614196.21      7009230.50      2614276.00      7009311.00

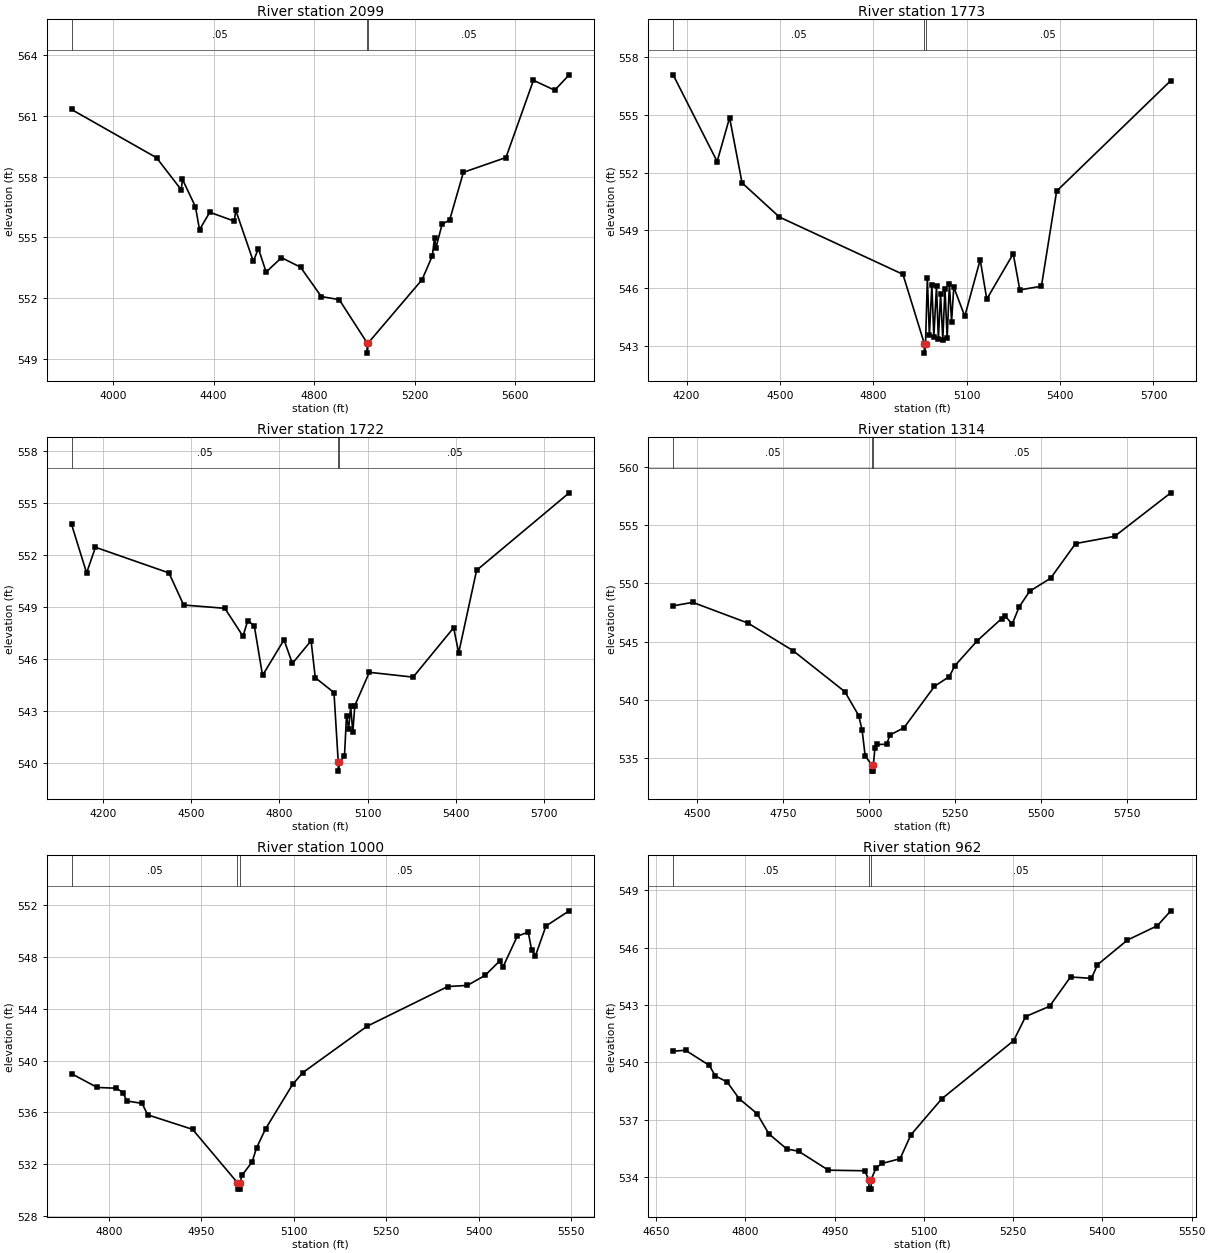
Type RM Length L Ch R = 1,2099,326,326,326
BEGIN DESCRIPTION:
Brushy Creek Tributary 9_1 4.0
END DESCRIPTION:
XS GIS Cut Line= 4
      2611346.40      7009360.17      2612268.54      7009180.37
      2612419.74      7009012.95      2612711.83      7008252.84
#Sta/Elev= 30
  3834.9  561.31  4173.0  558.93  4271.1  557.35  4276.2  557.86  4327.8  556.51
  4343.9  555.38  4384.7  556.24  4482.6  555.80  4487.7  556.35  4557.9  553.82
  4578.2  554.45  4608.8  553.29  4669.9  554.00  4745.7  553.53  4828.5  552.08
  4899.5  551.93  5010.8  549.79  5011.1  549.29  5014.8  549.79  5229.5  552.92
  5269.9  554.09  5278.8  554.99  5284.1  554.48  5308.8  555.65  5338.8  555.86
  5393.5  558.21  5562.8  558.94  5672.1  562.75  5756.8  562.26  5814.3  563.02
#Mann=3,-1,0
  3834.9    0.05       0  5010.8   0.035       0  5014.8    0.05       0
Bank Sta=5010.8,5014.8
Exp/Cntr=0.3,0.1

Type RM Length L Ch R = 1,1773,51,51,51
BEGIN DESCRIPTION:
Mapping XS 50d86ec7
END DESCRIPTION:
XS GIS Cut Line= 6
      2611894.65      7009278.29      2612350.43      7009288.97
      2612476.83      7009280.07      2612682.67      7009120.30
      2612923.67      7008877.73      2612879.16      7008466.47
#Sta/Elev= 30
  4156.8  557.09  4298.2  552.58  4338.2  554.86  4378.2  551.47  4498.2  549.69
  4895.1  546.71  4963.7  543.11  4964.0  542.61  4967.7  543.11  4973.6  546.53
  4980.0  543.53  4988.0  546.14  4994.4  543.47  5003.0  546.10  5008.9  543.32
  5016.0  545.69  5023.1  543.31  5030.1  545.97  5037.2  543.39  5044.3  546.20
  5051.4  544.25  5058.4  546.04  5093.8  544.53  5143.3  547.47  5164.5  545.42
  5249.4  547.78  5270.6  545.90  5340.0  546.09  5388.9  551.04  5755.6  556.79
#Mann=3,-1,0
  4156.8    0.05       0  4963.7    0.03       0  4967.7    0.05       0
Bank Sta=4963.7,4967.7
Exp/Cntr=0.3,0.1

Type RM Length L Ch R = 1,1722,408,408,408
BEGIN DESCRIPTION:
Mapping XS d1055fe0
END DESCRIPTION:
XS GIS Cut Line= 6
      2611884.83      7009356.35      2612452.77      7009359.91
      2612529.32      7009320.75      2612721.59      7009153.41
      2612967.26      7008916.63      2612908.51      7008478.68
#Sta/Elev= 30
  4093.0  553.77  4144.2  550.97  4174.2  552.45  4424.2  550.97  4474.2  549.12
  4614.2  548.93  4675.8  547.32  4692.1  548.22  4714.3  547.92  4742.3  545.06
  4815.3  547.11  4843.8  545.75  4907.4  547.06  4921.6  544.93  4985.2  544.07
  4999.8  540.04  5000.1  539.54  5003.8  540.04  5020.9  540.41  5027.8  542.73
  5035.1  541.98  5042.0  543.28  5049.2  541.79  5056.1  543.32  5105.5  545.24
  5254.2  544.96  5392.1  547.81  5409.2  546.36  5470.1  551.12  5784.9  555.59
#Mann=3,-1,0
  4093.0    0.05       0  4999.8    0.03       0  5003.8    0.05       0
Bank Sta=4999.8,5003.8
Exp/Cntr=0.3,0.1

Type RM Length L Ch R = 1,1314,314,314,314
BEGIN DESCRIPTION:
Mapping XS 3203d8a8
END DESCRIPTION:
XS GIS Cut Line= 3
      2613023.36      7009817.66      2613085.67      7009258.70
      2612932.56      7008386.35
#Sta/Elev= 30
  4430.3  548.08  4487.3  548.38  4648.3  546.60  4779.1  544.24  4930.0  540.72
  4970.3  538.67  4980.3  537.41  4989.0  535.23  5008.7  534.41  5008.9  533.91
  5012.4  533.91  5012.7  534.41  5017.7  535.92  5022.8  536.20  5051.3  536.21
  5061.5  537.01  5102.1  537.63  5190.8  541.18  5234.1  542.02  5250.2  542.95
  5315.3  545.09  5386.3  546.99  5396.5  547.22  5416.8  546.51  5437.1  547.98
  5467.6  549.33  5528.5  550.44  5601.4  553.42  5715.1  554.04  5878.4  557.77
#Mann=3,-1,0
  4430.3    0.05       0  5008.7    0.04       0  5012.7    0.05       0
Bank Sta=5008.7,5012.7
Exp/Cntr=0.3,0.1

Type RM Length L Ch R = 1,1000,38,38,38
BEGIN DESCRIPTION:
Brushy Creek Tributary 9_1 2.0
END DESCRIPTION:
XS GIS Cut Line= 3
      2613275.99      7009361.03      2613347.66      7009110.59
      2613125.98      7008610.96
#Sta/Elev= 30
  4739.5  538.99  4781.1  537.93  4812.3  537.87  4822.7  537.54  4829.2  536.89
  4854.0  536.70  4862.9  535.82  4935.7  534.70  5008.5  530.59  5008.7  530.09
  5012.2  530.09  5012.5  530.59  5016.2  531.17  5032.4  532.19  5039.5  533.27
  5054.2  534.74  5098.0  538.16  5114.7  539.08  5218.8  542.65  5349.6  545.71
  5381.6  545.80  5410.4  546.58  5433.6  547.67  5439.1  547.21  5462.4  549.59
  5480.2  549.91  5485.6  548.55  5491.9  548.08  5508.9  550.38  5546.6  551.55
#Mann=3,-1,0
  4739.5    0.05       0  5008.5    0.04       0  5012.5    0.05       0
Bank Sta=5008.5,5012.5
Exp/Cntr=0.3,0.1

Type RM Length L Ch R = 1,962,214,214,214
BEGIN DESCRIPTION:
Mapping XS 706c5677
END DESCRIPTION:
XS GIS Cut Line= 4
      2613378.78      7009431.82      2613385.72      7009114.17
      2613383.99      7009055.14      2613331.91      7008598.59
#Sta/Elev= 30
  4678.6  540.58  4699.4  540.63  4739.4  539.84  4749.4  539.29  4769.4  538.97
  4789.5  538.10  4819.5  537.32  4839.5  536.26  4869.5  535.47  4889.5  535.35
  4939.5  534.36  5000.4  534.33  5007.5  533.87  5007.8  533.37  5011.3  533.37
  5011.5  533.87  5019.5  534.48  5029.5  534.71  5060.0  534.96  5078.2  536.21
  5130.0  538.09  5250.8  541.13  5270.9  542.39  5311.2  542.93  5346.4  544.46
  5381.6  544.39  5391.7  545.10  5442.0  546.39  5492.3  547.14  5514.9  547.92
#Mann=3,-1,0
  4678.6    0.05       0  5007.5    0.04       0  5011.5    0.05       0
Bank Sta=5007.5,5011.5
Exp/Cntr=0.3,0.1

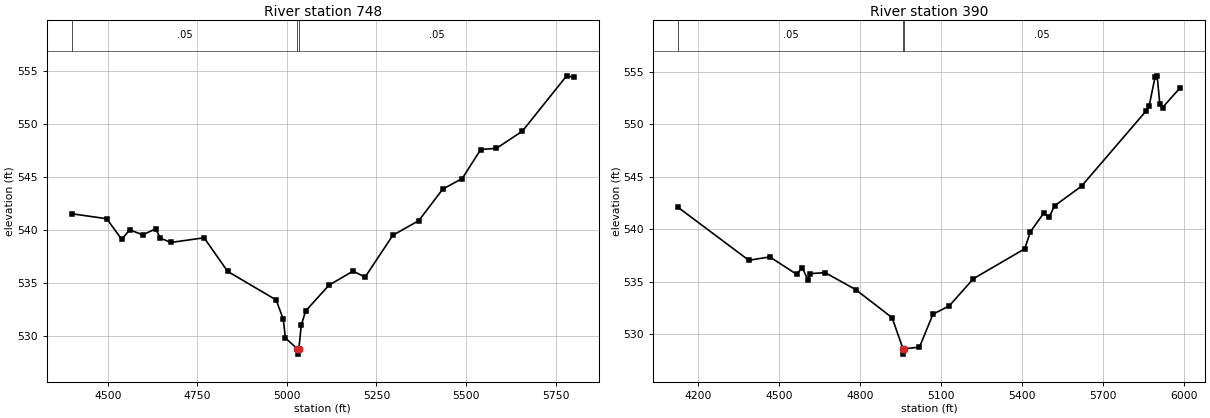
Type RM Length L Ch R = 1,748,358,358,358
BEGIN DESCRIPTION:
Mapping XS 6cc29d04
END DESCRIPTION:
XS GIS Cut Line= 4
      2613324.19      7009684.22      2613571.67      7009324.57
      2613584.13      7009164.35      2613359.82      7008391.73
#Sta/Elev= 30
  4399.3  541.51  4496.9  541.04  4538.8  539.09  4561.0  539.99  4597.4  539.52
  4633.8  540.09  4646.3  539.21  4676.1  538.80  4768.8  539.24  4834.4  536.07
  4969.8  533.37  4989.9  531.55  4995.7  529.77  5029.3  528.75  5029.6  528.25
  5033.3  528.75  5040.1  530.98  5052.1  532.32  5117.6  534.77  5184.7  536.09
  5218.3  535.53  5295.8  539.48  5368.1  540.86  5435.2  543.84  5489.5  544.84
  5541.1  547.58  5585.0  547.69  5657.3  549.31  5781.0  554.54  5801.1  554.41
#Mann=3,-1,0
  4399.3    0.05       0  5029.3    0.04       0  5033.3    0.05       0
Bank Sta=5029.3,5033.3
Exp/Cntr=0.3,0.1

Type RM Length L Ch R = 1,390,0,0,0
BEGIN DESCRIPTION:
Brushy Creek Tributary 9_1 1.0
END DESCRIPTION:
XS GIS Cut Line= 3
      2613299.30      7009753.61      2613941.18      7009160.57
      2613918.83      7008175.22
#Sta/Elev= 30
  4126.1  542.07  4387.5  537.04  4465.1  537.36  4564.4  535.71  4585.4  536.33
  4606.9  535.16  4613.7  535.77  4670.4  535.86  4783.8  534.24  4918.2  531.57
  4958.7  528.60  4959.0  528.10  4962.7  528.60  5019.6  528.77  5069.6  531.91
  5129.6  532.69  5219.6  535.29  5409.7  538.14  5429.7  539.73  5479.7  541.53
  5499.7  541.14  5519.7  542.22  5619.7  544.10  5859.8  551.29  5869.8  551.69
  5892.4  554.54  5899.8  554.61  5909.8  551.90  5919.8  551.59  5985.6  553.49
#Mann=3,-1,0
  4126.1    0.05       0  4958.7    0.03       0  4962.7    0.05       0
Bank Sta=4958.7,4962.7
Exp/Cntr=0.3,0.1

Chan Stop Cuts=-1