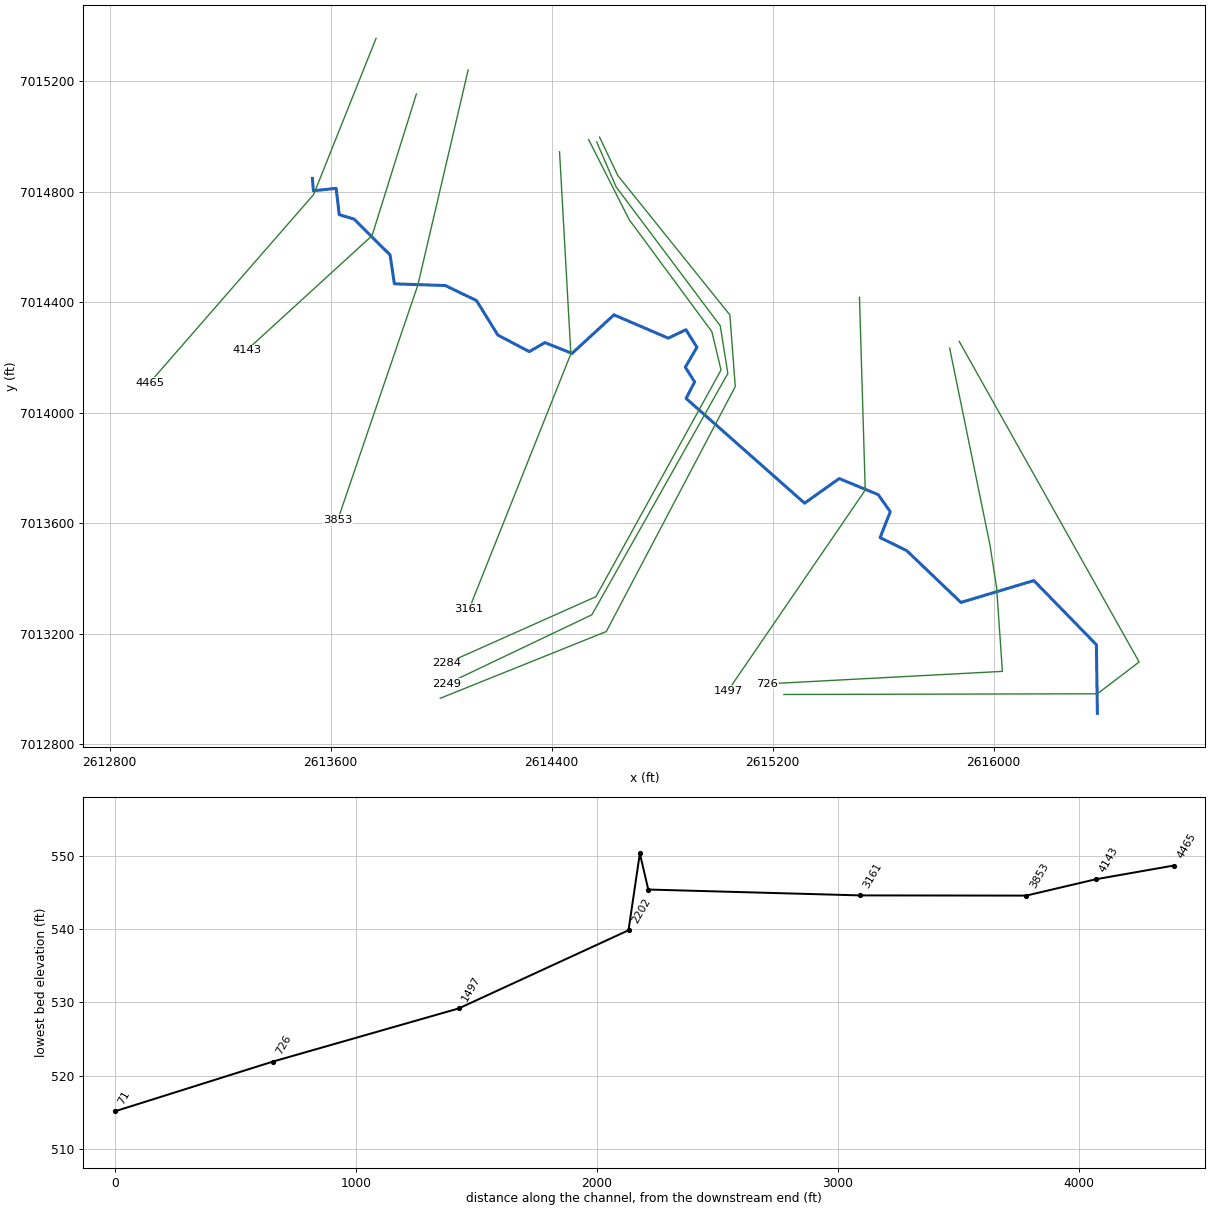
--- Brushy Creek Tributary R.prj (project) ---

Proj Title=Brushy Creek Tributary R Base Level Engineering
Current Plan=p01
Default Exp/Contr=0.3,0.1
English Units
Geom File=g01
Flow File=f01
Plan File=p01
BEGIN DESCRIPTION:
Brushy Creek Tributary R
END DESCRIPTION:

--- Brushy Creek Tributary R.p01 (plan) ---

Plan Title=Multiple Run
Short Identifier=Multiple
Geom File=g01
Flow File=f01
Subcritical Flow
K Sum by GR= 0
Std Step Tol= 0.01
Critical Tol= 0.01
Num of Std Step Trials= 20
Max Error Tol= 0.3
Flow Tol Ratio= 0.001
Split Flow NTrial= 30
Split Flow Tol= 0.02
Split Flow Ratio= 0.02
Log Output Level= 0
Friction Slope Method= 1
Unsteady Friction Slope Method= 2
Unsteady Bridges Friction Slope Method= 1
Parabolic Critical Depth
Global Vel Dist=  1 , 1 , 1
Global Log Level= 0
CheckData=True
Encroach Param= -1, 0, 0, 0
BEGIN DESCRIPTION:
Multiple Run
END DESCRIPTION:

--- Brushy Creek Tributary R.f01 (steady flow) ---

Flow Title=Multiple
Number of Profiles=7
Profile Names=10-year,25-year,50-year,1pct_min,100-year,1pct_plu,500-year
River Rch & RM= Brushy Creek Tri,Reach-1,4465
     383     502     595     352     701    1400     972
River Rch & RM= Brushy Creek Tri,Reach-1,71
    1730    2435    3030    1862    3715    7413    5593
Boundary for River Rch & Prof#=Brushy Creek Tri,Reach-1,1
Up Type=0
Dn Type=3
Dn Slope=0.005
Boundary for River Rch & Prof#=Brushy Creek Tri,Reach-1,2
Up Type=0
Dn Type=3
Dn Slope=0.005
Boundary for River Rch & Prof#=Brushy Creek Tri,Reach-1,3
Up Type=0
Dn Type=3
Dn Slope=0.005
Boundary for River Rch & Prof#=Brushy Creek Tri,Reach-1,4
Up Type=0
Dn Type=3
Dn Slope=0.005
Boundary for River Rch & Prof#=Brushy Creek Tri,Reach-1,5
Up Type=0
Dn Type=3
Dn Slope=0.005
Boundary for River Rch & Prof#=Brushy Creek Tri,Reach-1,6
Up Type=0
Dn Type=3
Dn Slope=0.005
Boundary for River Rch & Prof#=Brushy Creek Tri,Reach-1,7
Up Type=0
Dn Type=3
Dn Slope=0.005

--- Brushy Creek Tributary R.g01 (geometry) ---

Geom Title=Existing Conditions

River Reach=Brushy Creek Tri,Reach-1
Reach XY= 30
      2613534.36      7014847.63      2613537.83      7014802.93
      2613620.30      7014811.61      2613631.44      7014716.51
      2613685.42      7014700.13      2613815.46      7014570.74
      2613831.08      7014466.03      2614015.50      7014459.80
      2614128.55      7014405.27      2614205.53      7014280.62
      2614319.45      7014220.58      2614375.92      7014253.17
      2614474.35      7014214.16      2614625.90      7014353.69
      2614822.79      7014269.29      2614886.44      7014299.89
      2614926.41      7014236.18      2614884.31      7014164.23
      2614917.96      7014111.00      2614887.23      7014051.00
      2615316.00      7013671.96      2615441.34      7013761.04
      2615582.43      7013702.98      2615626.36      7013640.94
      2615589.40      7013547.27      2615685.64      7013500.22
      2615882.03      7013312.62      2616146.03      7013391.71
      2616372.47      7013159.54      2616376.00      7012911.00

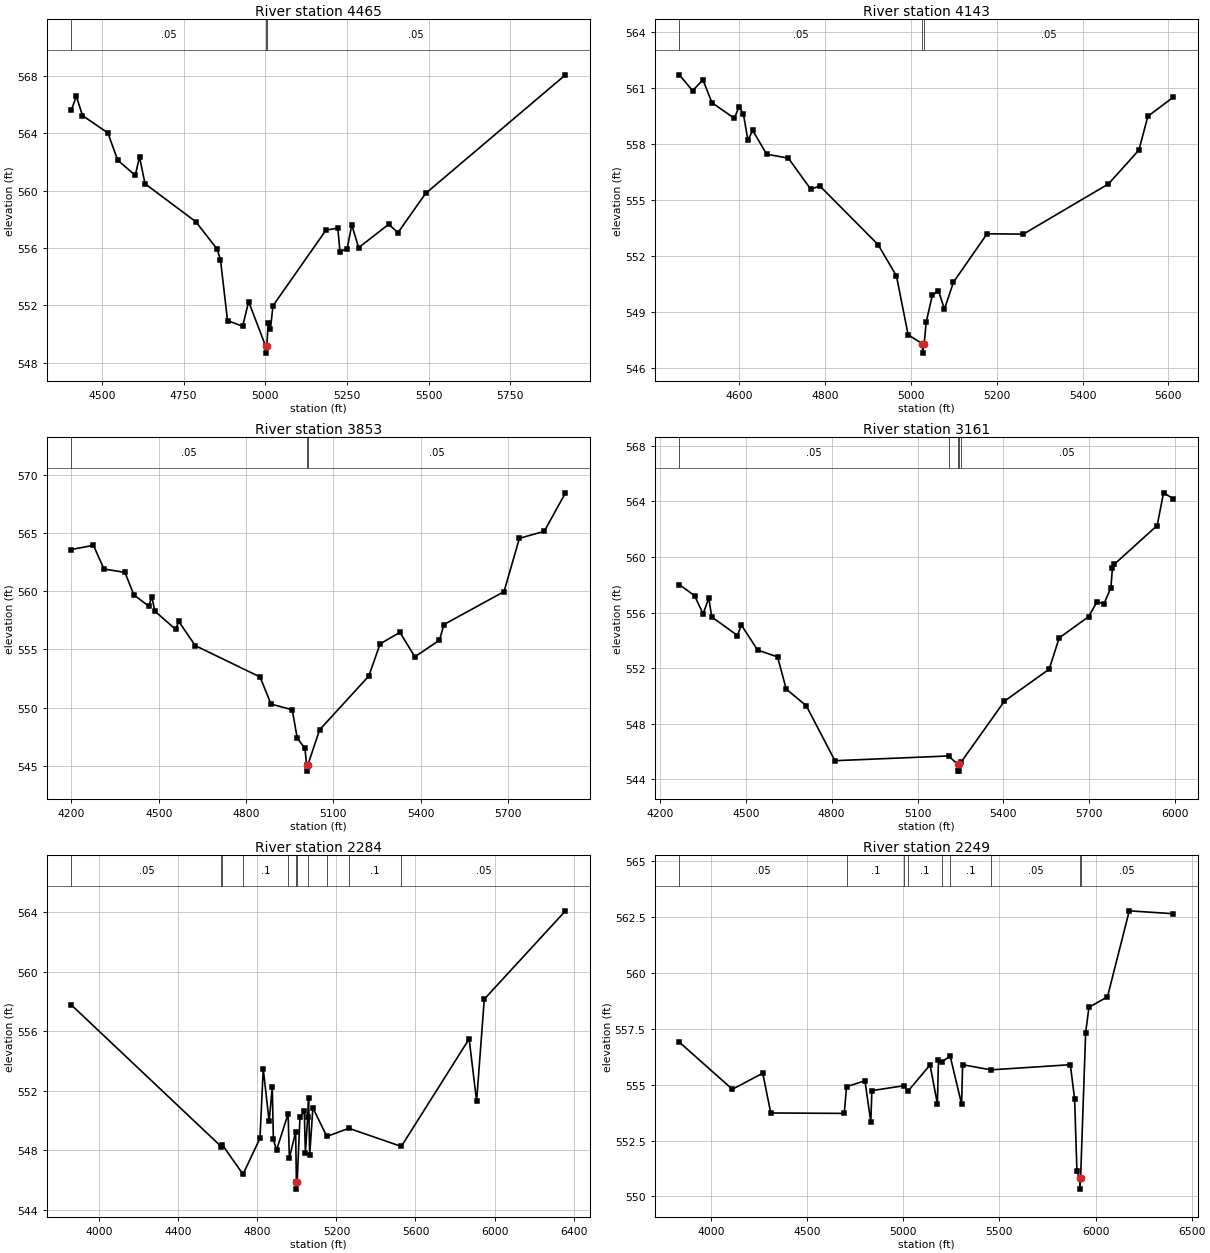
Type RM Length L Ch R = 1,4465,322,322,322
BEGIN DESCRIPTION:
Brushy Creek Tributary 8 8.0
END DESCRIPTION:
XS GIS Cut Line= 3
      2613764.80      7015354.71      2613538.61      7014788.96
      2612945.35      7014108.18
#Sta/Elev= 30
  4406.5  565.61  4421.7  566.58  4440.5  565.23  4518.2  564.02  4548.3  562.12
  4602.1  561.06  4615.1  562.36  4631.8  560.48  4787.4  557.83  4852.6  555.92
  4862.8  555.18  4884.4  550.94  4930.7  550.54  4949.0  552.26  5000.8  549.17
  5001.1  548.67  5004.8  549.17  5008.8  550.77  5015.8  550.36  5023.5  551.97
  5185.9  557.25  5222.0  557.38  5228.6  555.74  5250.5  555.95  5264.7  557.61
  5285.6  556.02  5377.7  557.65  5406.1  557.07  5490.6  559.80  5918.8  568.07
#Mann=3,-1,0
  4406.5    0.05       0  5000.8    0.03       0  5004.8    0.05       0
Bank Sta=5000.8,5004.8
Exp/Cntr=0.3,0.1

Type RM Length L Ch R = 1,4143,290,290,290
BEGIN DESCRIPTION:
Mapping XS 1e04c3db
END DESCRIPTION:
XS GIS Cut Line= 3
      2613910.78      7015153.52      2613750.20      7014640.31
      2613296.77      7014225.93
#Sta/Elev= 30
  4459.9  561.71  4490.7  560.86  4514.9  561.44  4535.9  560.22  4588.1  559.38
  4598.8  559.99  4609.2  559.63  4619.7  558.21  4631.0  558.73  4663.5  557.46
  4714.0  557.25  4766.4  555.58  4787.4  555.76  4923.2  552.62  4966.1  550.94
  4993.3  547.79  5026.7  547.31  5026.9  546.81  5030.7  547.31  5035.4  548.47
  5049.6  549.90  5063.8  550.16  5078.0  549.17  5099.0  550.61  5177.3  553.20
  5261.8  553.18  5460.4  555.87  5531.3  557.68  5552.2  559.49  5611.9  560.52
#Mann=3,-1,0
  4459.9    0.05       0  5026.7    0.03       0  5030.7    0.05       0
Bank Sta=5026.7,5030.7
Exp/Cntr=0.3,0.1

Type RM Length L Ch R = 1,3853,692,692,692
BEGIN DESCRIPTION:
Brushy Creek Tributary 8 7.0
END DESCRIPTION:
XS GIS Cut Line= 3
      2614098.13      7015240.15      2613915.85      7014460.88
      2613626.02      7013611.05
#Sta/Elev= 30
  4199.7  563.57  4275.4  563.93  4311.8  561.90  4383.7  561.61  4414.5  559.68
  4465.8  558.71  4476.1  559.54  4486.4  558.29  4558.3  556.72  4568.5  557.41
  4625.6  555.33  4848.3  552.64  4885.7  550.32  4958.8  549.83  4975.8  547.41
  5002.6  546.51  5008.1  545.07  5008.3  544.57  5012.1  545.07  5052.7  548.11
  5221.8  552.72  5260.8  555.48  5328.8  556.47  5380.2  554.37  5464.8  555.80
  5480.2  557.14  5686.6  559.96  5739.5  564.53  5824.9  565.13  5897.9  568.43
#Mann=3,-1,0
  4199.7    0.05       0  5008.1    0.03       0  5012.1    0.05       0
Bank Sta=5008.1,5012.1
Exp/Cntr=0.3,0.1

Type RM Length L Ch R = 1,3161,877,877,877
BEGIN DESCRIPTION:
Brushy Creek Tributary 8 6.0
END DESCRIPTION:
XS GIS Cut Line= 3
      2614428.96      7014943.91      2614469.95      7014212.65
      2614101.62      7013288.77
#Sta/Elev= 30
  4267.6  558.01  4320.6  557.22  4350.6  555.91  4370.7  557.04  4380.7  555.69
  4470.8  554.35  4484.3  555.11  4540.9  553.31  4611.0  552.81  4641.1  550.50
  4711.2  549.30  4811.4  545.35  5208.4  545.69  5240.1  545.10  5240.3  544.60
  5243.8  544.60  5244.1  545.10  5252.4  545.25  5403.8  549.63  5560.2  551.93
  5595.2  554.18  5697.7  555.70  5727.3  556.77  5751.6  556.62  5775.9  557.80
  5781.3  559.19  5787.7  559.47  5937.6  562.26  5959.9  564.61  5994.6  564.18
#Mann=5,-1,0
  4267.6    0.05       0  5208.4     0.1       0  5240.1    0.03       0
  5244.1     0.1       0  5252.4    0.05       0
Bank Sta=5240.1,5244.1
Exp/Cntr=0.3,0.1

Type RM Length L Ch R = 1,2284,35,35,35
BEGIN DESCRIPTION:
Mapping XS 57414dad
END DESCRIPTION:
XS GIS Cut Line= 6
      2614534.33      7014988.17      2614680.98      7014698.53
      2614980.46      7014292.71      2615013.56      7014153.90
      2614560.68      7013333.48      2614020.70      7013092.46
#Sta/Elev= 30
  3858.7  557.78  4617.9  548.25  4623.0  548.37  4727.3  546.40  4813.1  548.82
  4829.6  553.49  4859.4  549.95  4875.3  552.24  4881.0  548.74  4896.9  548.02
  4955.4  550.46  4961.8  547.50  4993.6  549.24  4997.3  545.90  4997.6  545.40
  5001.3  545.90  5015.4  550.23  5037.2  550.64  5042.9  547.82  5054.5  550.27
  5059.0  551.54  5064.7  547.70  5080.8  550.87  5151.4  548.94  5262.8  549.49
  5528.3  548.27  5871.5  555.50  5909.3  551.31  5948.1  558.17  6359.1  564.11
#Mann=11,-1,0
  3858.7    0.05       0  4617.9     0.1       0  4623.0    0.05       0
  4727.3     0.1       0  4955.4    0.05       0  4997.3    0.03       0
  5001.3    0.05       0  5054.5     0.1       0  5151.4    0.05       0
  5262.8     0.1       0  5528.3    0.05       0
Bank Sta=4997.3,5001.3
Exp/Cntr=0.3,0.1

Type RM Length L Ch R = 1,2249,47,47,47
BEGIN DESCRIPTION:
Mapping XS ffff0091
END DESCRIPTION:
XS GIS Cut Line= 6
      2614563.40      7014979.74      2614634.02      7014816.46
      2615010.74      7014314.19      2615038.24      7014141.44
      2614546.05      7013267.91      2614021.74      7013017.91
#Sta/Elev= 30
  3834.9  556.91  4110.8  554.80  4268.7  555.52  4310.4  553.74  4692.7  553.72
  4704.9  554.92  4800.4  555.18  4830.9  553.34  4836.5  554.74  5003.4  554.96
  5024.8  554.72  5139.1  555.89  5177.3  554.15  5182.9  556.12  5203.4  556.04
  5243.6  556.29  5303.0  554.14  5308.7  555.90  5455.5  555.67  5868.9  555.90
  5891.1  554.37  5903.2  551.13  5918.3  550.83  5918.6  550.33  5922.3  550.83
  5948.6  557.34  5965.7  558.47  6062.1  558.94  6175.5  562.79  6405.4  562.66
#Mann=9,-1,0
  3834.9    0.05       0  4704.9     0.1       0  5003.4    0.05       0
  5024.8     0.1       0  5203.4    0.05       0  5243.6     0.1       0
  5455.5    0.05       0  5918.3    0.07       0  5922.3    0.05       0
Bank Sta=5918.3,5922.3
Exp/Cntr=0.3,0.1

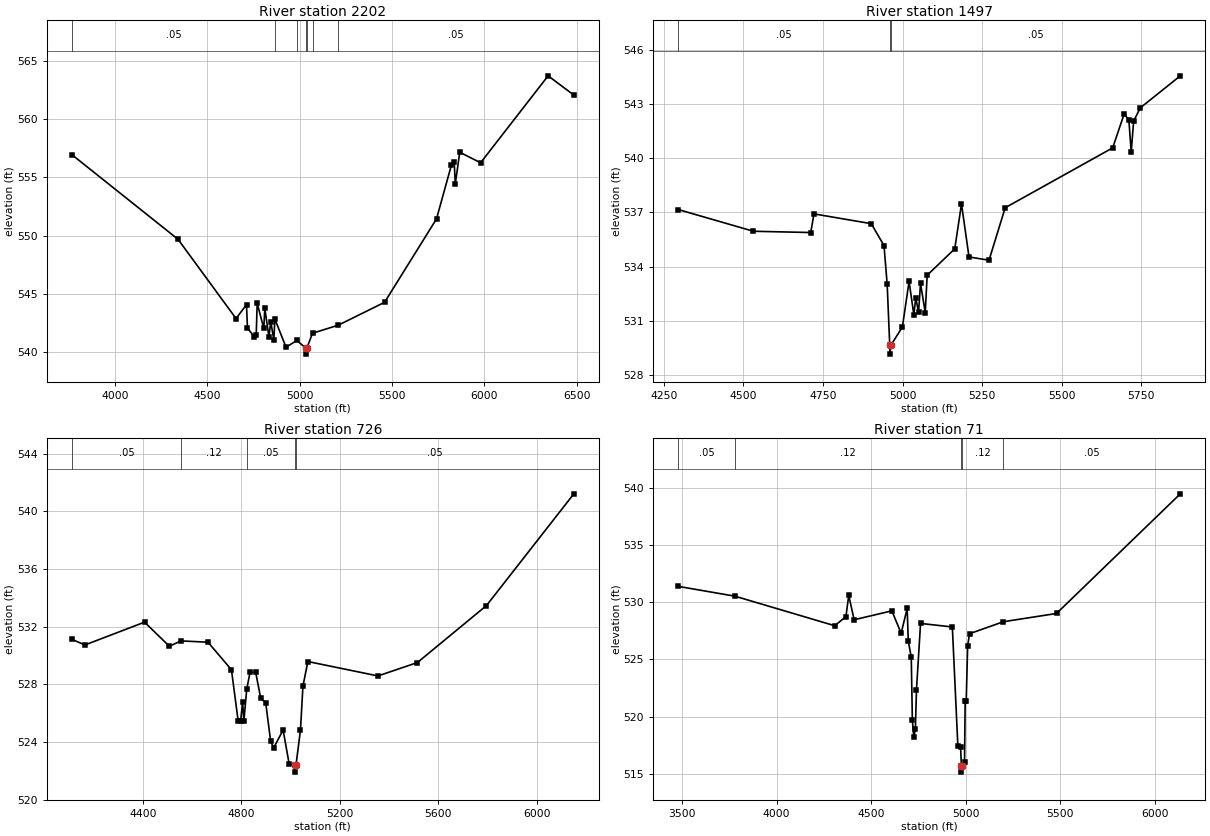
Type RM Length L Ch R = 1,2202,705,705,705
BEGIN DESCRIPTION:
Mapping XS 9ac61506
END DESCRIPTION:
XS GIS Cut Line= 6
      2614573.81      7014997.10      2614639.80      7014858.18
      2615045.57      7014353.48      2615065.10      7014094.15
      2614598.35      7013207.36      2613997.42      7012965.82
#Sta/Elev= 30
  3766.9  556.94  4342.2  549.68  4656.2  542.89  4712.9  544.08  4718.0  542.08
  4756.1  541.30  4765.5  541.50  4770.7  544.20  4806.7  542.04  4811.9  543.77
  4834.4  541.32  4844.3  542.62  4860.8  541.06  4866.6  542.84  4926.9  540.43
  4985.6  541.01  5035.2  540.34  5035.5  539.84  5039.2  540.34  5070.3  541.63
  5209.6  542.32  5460.3  544.28  5741.6  551.43  5822.0  556.03  5837.4  556.30
  5843.2  554.42  5867.4  557.14  5980.3  556.24  6345.8  563.69  6485.1  562.04
#Mann=7,-1,0
  3766.9    0.05       0  4866.6     0.1       0  4985.6    0.05       0
  5035.2    0.03       0  5039.2    0.05       0  5070.3     0.1       0
  5209.6    0.05       0
Bank Sta=5035.2,5039.2
Exp/Cntr=0.3,0.1

Type RM Length L Ch R = 1,1497,771,771,771
BEGIN DESCRIPTION:
Mapping XS 84555598
END DESCRIPTION:
XS GIS Cut Line= 3
      2615514.80      7014417.21      2615535.63      7013719.30
      2615039.12      7012993.62
#Sta/Elev= 30
  4295.2  537.16  4531.5  535.96  4711.6  535.89  4721.6  536.92  4901.7  536.38
  4941.7  535.17  4951.7  533.02  4959.7  529.67  4960.0  529.17  4963.7  529.67
  4999.5  530.67  5020.5  533.19  5035.4  531.35  5041.5  532.27  5050.3  531.49
  5056.4  533.08  5071.3  531.47  5077.3  533.53  5164.0  534.99  5185.2  537.47
  5208.8  534.54  5271.7  534.36  5322.5  537.26  5660.3  540.57  5696.2  542.44
  5711.1  542.11  5718.4  540.33  5726.1  542.05  5747.0  542.78  5872.7  544.55
#Mann=3,-1,0
  4295.2    0.05       0  4959.7    0.03       0  4963.7    0.05       0
Bank Sta=4959.7,4963.7
Exp/Cntr=0.3,0.1

Type RM Length L Ch R = 1,726,655,655,655
BEGIN DESCRIPTION:
Mapping XS 430984a5
END DESCRIPTION:
XS GIS Cut Line= 5
      2615841.19      7014233.18      2615987.02      7013521.38
      2616011.32      7013365.13      2616032.16      7013063.05
      2615181.47      7013017.91
#Sta/Elev= 30
  4111.3  531.13  4164.9  530.74  4406.9  532.32  4507.7  530.65  4554.9  531.02
  4664.7  530.93  4759.9  529.02  4787.2  525.46  4797.4  525.50  4805.2  526.77
  4810.3  525.46  4821.9  527.66  4835.5  528.85  4858.5  528.83  4878.8  527.04
  4899.0  526.74  4919.2  524.05  4931.6  523.61  4969.8  524.84  4994.5  522.47
  5018.2  522.42  5018.5  521.92  5022.2  522.42  5040.2  524.83  5050.3  527.88
  5070.3  529.59  5355.1  528.59  5515.3  529.52  5795.7  533.47  6150.7  541.22
#Mann=5,-1,0
  4111.3    0.05       0  4554.9    0.12       0  4821.9    0.05       0
  5018.2    0.03       0  5022.2    0.05       0
Bank Sta=5018.2,5022.2
Exp/Cntr=0.3,0.1

Type RM Length L Ch R = 1,71,0,0,0
BEGIN DESCRIPTION:
Brushy Creek Tributary 8 3.0
END DESCRIPTION:
XS GIS Cut Line= 4
      2615875.93      7014257.45      2616527.14      7013097.00
      2616376.02      7012981.98      2615241.23      7012979.35
#Sta/Elev= 30
  3479.4  531.38  3779.6  530.52  4306.9  527.94  4366.2  528.73  4381.2  530.59
  4409.6  528.46  4609.2  529.24  4658.3  527.28  4690.2  529.45  4696.0  526.60
  4711.9  525.19  4717.6  519.70  4725.2  518.22  4733.6  518.87  4739.3  522.33
  4761.0  528.14  4929.1  527.83  4958.2  517.46  4972.7  517.35  4977.0  515.64
  4977.3  515.14  4981.0  515.64  4993.6  516.03  4996.9  521.33  5002.5  521.33
  5010.0  526.16  5020.0  527.24  5199.3  528.29  5480.0  529.01  6134.8  539.47
#Mann=5,-1,0
  3479.4    0.05       0  3779.6    0.12       0  4977.0    0.07       0
  4981.0    0.12       0  5199.3    0.05       0
Bank Sta=4977,4981
Exp/Cntr=0.3,0.1

Chan Stop Cuts=-1