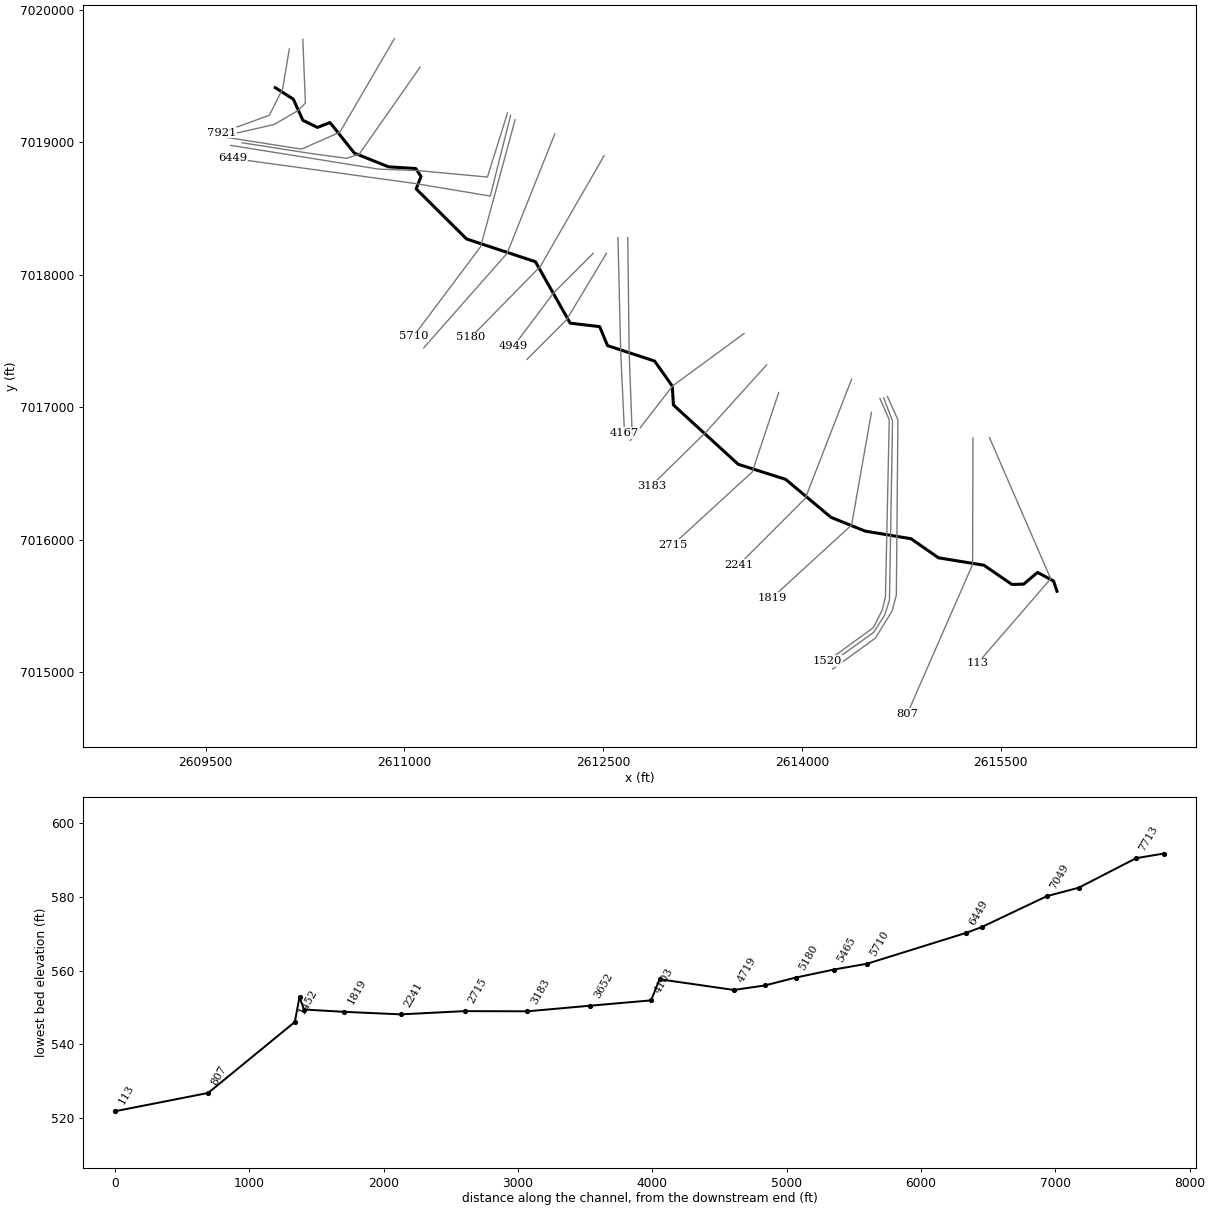
--- Brushy Creek Tributary S.prj (project) ---

Proj Title=Brushy Creek Tributary S Base Level Engineering
Current Plan=p01
Default Exp/Contr=0.3,0.1
English Units
Geom File=g01
Flow File=f01
Plan File=p01
BEGIN DESCRIPTION:
Brushy Creek Tributary S
END DESCRIPTION:

--- Brushy Creek Tributary S.p01 (plan) ---

Plan Title=Multiple Run
Short Identifier=Multiple
Geom File=g01
Flow File=f01
Subcritical Flow
K Sum by GR= 0
Std Step Tol= 0.01
Critical Tol= 0.01
Num of Std Step Trials= 20
Max Error Tol= 0.3
Flow Tol Ratio= 0.001
Split Flow NTrial= 30
Split Flow Tol= 0.02
Split Flow Ratio= 0.02
Log Output Level= 0
Friction Slope Method= 1
Unsteady Friction Slope Method= 2
Unsteady Bridges Friction Slope Method= 1
Parabolic Critical Depth
Global Vel Dist=  1 , 1 , 1
Global Log Level= 0
CheckData=True
Encroach Param= -1, 0, 0, 0
BEGIN DESCRIPTION:
Multiple Run
END DESCRIPTION:

--- Brushy Creek Tributary S.f01 (steady flow) ---

Flow Title=Multiple
Number of Profiles=7
Profile Names=10-year,25-year,50-year,1pct_min,100-year,1pct_plu,500-year
River Rch & RM= Brushy Creek Tri,Reach-1,7921
     448     591     705     417     832    1661    1160
River Rch & RM= Brushy Creek Tri,Reach-1,1520
     522     696     837     499     997    1988    1412
River Rch & RM= Brushy Creek Tri,Reach-1,113
    1697    2391    2977    1830    3652    7287    5505
Boundary for River Rch & Prof#=Brushy Creek Tri,Reach-1,1
Up Type=0
Dn Type=3
Dn Slope=0.005
Boundary for River Rch & Prof#=Brushy Creek Tri,Reach-1,2
Up Type=0
Dn Type=3
Dn Slope=0.005
Boundary for River Rch & Prof#=Brushy Creek Tri,Reach-1,3
Up Type=0
Dn Type=3
Dn Slope=0.005
Boundary for River Rch & Prof#=Brushy Creek Tri,Reach-1,4
Up Type=0
Dn Type=3
Dn Slope=0.005
Boundary for River Rch & Prof#=Brushy Creek Tri,Reach-1,5
Up Type=0
Dn Type=3
Dn Slope=0.005
Boundary for River Rch & Prof#=Brushy Creek Tri,Reach-1,6
Up Type=0
Dn Type=3
Dn Slope=0.005
Boundary for River Rch & Prof#=Brushy Creek Tri,Reach-1,7
Up Type=0
Dn Type=3
Dn Slope=0.005

--- Brushy Creek Tributary S.g01 (geometry) ---

Geom Title=Existing Conditions

River Reach=Brushy Creek Tri,Reach-1
Reach XY= 30
      2610026.00      7019411.00      2610162.40      7019324.24
      2610234.46      7019164.50      2610344.44      7019110.87
      2610439.38      7019147.46      2610623.45      7018916.73
      2610881.53      7018813.38      2611086.24      7018800.66
      2611126.37      7018740.95      2611089.40      7018647.27
      2611469.96      7018269.14      2611989.57      7018097.53
      2612252.09      7017633.70      2612474.78      7017607.56
      2612533.86      7017464.53      2612889.65      7017347.74
      2613022.44      7017159.52      2613031.19      7017016.44
      2613519.94      7016569.14      2613878.30      7016455.17
      2614219.84      7016168.88      2614477.58      7016064.83
      2614824.45      7016007.25      2615031.45      7015863.19
      2615374.53      7015807.45      2615585.70      7015662.24
      2615674.50      7015664.48      2615779.24      7015753.16
      2615899.85      7015688.29      2615926.00      7015611.00

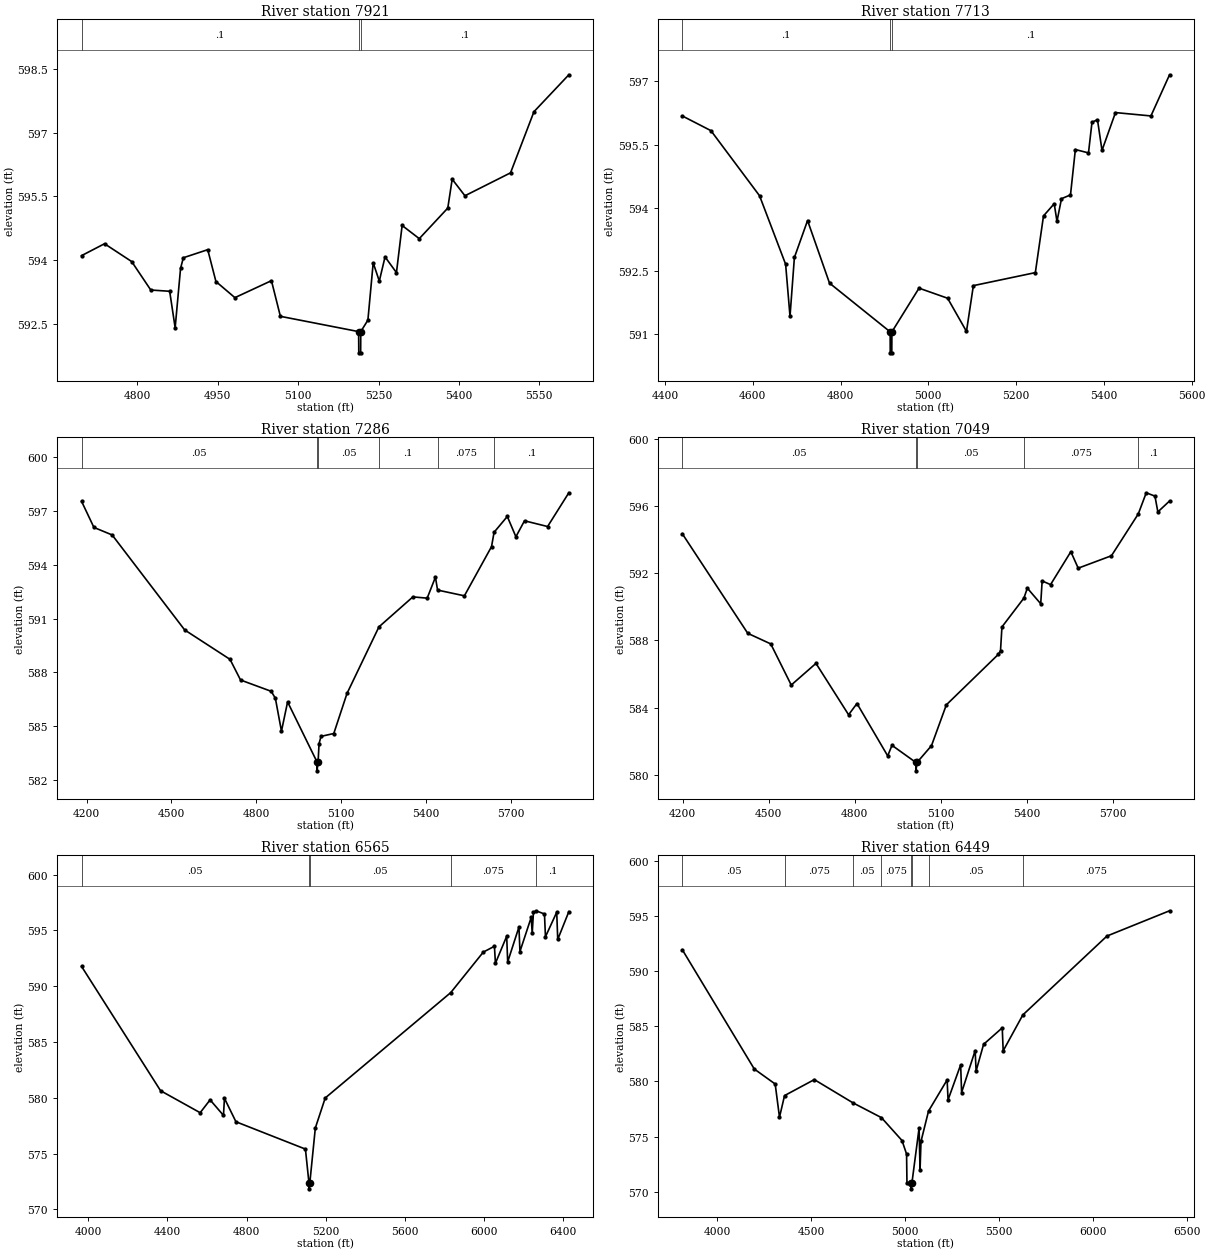
Type RM Length L Ch R = 1,7921,208,208,208
BEGIN DESCRIPTION:
Brushy Creek Tributary S 17.0
END DESCRIPTION:
XS GIS Cut Line= 4
      2610132.23      7019703.21      2610082.24      7019403.25
      2609982.24      7019203.25      2609623.86      7019072.18
#Sta/Elev= 30
  4695.9  594.10  4738.7  594.38  4789.4  593.96  4825.0  593.29  4860.3  593.26
  4870.5  592.40  4880.6  593.80  4885.8  594.05  4931.3  594.24  4946.6  593.49
  4982.0  593.11  5050.2  593.51  5066.9  592.67  5212.9  592.31  5213.2  591.81
  5216.7  591.81  5216.9  592.31  5230.2  592.58  5240.1  593.93  5251.5  593.50
  5262.2  594.07  5283.5  593.70  5294.1  594.81  5326.1  594.50  5379.3  595.22
  5387.5  595.90  5411.3  595.51  5496.4  596.05  5540.1  597.49  5605.2  598.36
#Mann=3,-1,0
  4695.9     0.1       0  5212.9    0.07       0  5216.9     0.1       0
Bank Sta=5212.9,5216.9
Exp/Cntr=0.3,0.1

Type RM Length L Ch R = 1,7713,427,427,427
BEGIN DESCRIPTION:
Mapping XS 0c242c8f
END DESCRIPTION:
XS GIS Cut Line= 5
      2610234.04      7019776.17      2610253.57      7019294.43
      2610196.28      7019237.13      2610017.90      7019132.97
      2609685.91      7019057.46
#Sta/Elev= 30
  4439.4  596.18  4504.6  595.83  4615.4  594.28  4674.8  592.65  4684.8  591.41
  4694.8  592.81  4724.8  593.69  4774.8  592.20  4913.0  591.04  4913.2  590.54
  4916.7  590.54  4917.0  591.04  4978.8  592.08  5043.9  591.84  5086.9  591.05
  5102.6  592.14  5243.8  592.45  5262.4  593.80  5286.8  594.09  5293.1  593.67
  5303.4  594.21  5323.9  594.30  5335.0  595.38  5364.9  595.30  5372.9  596.03
  5385.4  596.09  5395.7  595.36  5426.4  596.26  5507.2  596.18  5549.6  597.16
#Mann=3,-1,0
  4439.4     0.1       0  4913.0    0.07       0  4917.0     0.1       0
Bank Sta=4913,4917
Exp/Cntr=0.3,0.1

Type RM Length L Ch R = 1,7286,237,237,237
BEGIN DESCRIPTION:
Mapping XS d33a15de
END DESCRIPTION:
XS GIS Cut Line= 4
      2610924.89      7019780.43      2610513.43      7019074.70
      2610224.37      7018947.10      2609641.03      7019038.25
#Sta/Elev= 30
  4182.4  597.53  4226.0  596.08  4290.5  595.66  4546.9  590.37  4707.4  588.73
  4744.6  587.58  4853.1  586.95  4867.8  586.56  4889.3  584.73  4911.0  586.36
  5014.9  583.02  5015.1  582.52  5018.9  583.02  5022.3  584.04  5029.3  584.44
  5074.4  584.60  5121.1  586.83  5234.1  590.54  5354.1  592.21  5404.7  592.14
  5433.9  593.31  5441.4  592.59  5536.3  592.27  5632.3  595.01  5641.3  595.81
  5688.1  596.69  5718.5  595.56  5748.9  596.45  5830.6  596.13  5905.7  598.01
#Mann=6,-1,0
  4182.4    0.05       0  5014.9    0.05       0  5018.9    0.05       0
  5234.1     0.1       0  5441.4   0.075       0  5641.3     0.1       0
Bank Sta=5014.9,5018.9
Exp/Cntr=0.3,0.1

Type RM Length L Ch R = 1,7049,484,484,484
BEGIN DESCRIPTION:
Mapping XS 1d454f20
END DESCRIPTION:
XS GIS Cut Line= 5
      2611119.46      7019566.56      2610659.82      7018909.01
      2610564.77      7018877.76      2610286.13      7018915.52
      2609775.69      7018994.95
#Sta/Elev= 30
  4198.9  594.35  4427.3  588.42  4507.5  587.79  4579.0  585.34  4665.3  586.63
  4779.1  583.57  4808.4  584.24  4915.6  581.12  4930.5  581.75  5013.9  580.73
  5014.1  580.23  5017.9  580.73  5068.4  581.73  5120.2  584.16  5301.8  587.17
  5309.2  587.39  5314.2  588.80  5390.9  590.52  5402.8  591.11  5449.5  590.18
  5454.5  591.54  5483.8  591.32  5554.6  593.28  5580.3  592.30  5696.3  593.04
  5789.9  595.53  5817.7  596.79  5848.1  596.59  5858.2  595.65  5899.0  596.30
#Mann=5,-1,0
  4198.9    0.05       0  5013.9    0.03       0  5017.9    0.05       0
  5390.9   0.075       0  5789.9     0.1       0
Bank Sta=5013.9,5017.9
Exp/Cntr=0.3,0.1

Type RM Length L Ch R = 1,6565,116,116,116
BEGIN DESCRIPTION:
Mapping XS ca909b65
END DESCRIPTION:
XS GIS Cut Line= 5
      2611779.06      7019220.54      2611627.53      7018736.48
      2611103.49      7018784.97      2610807.70      7018796.06
      2609689.41      7018975.50
#Sta/Elev= 30
  3966.5  591.77  4365.6  580.64  4565.6  578.67  4615.9  579.82  4683.4  578.43
  4688.4  579.96  4746.4  577.86  5097.6  575.41  5115.6  572.35  5115.8  571.85
  5119.6  572.35  5147.6  577.30  5197.6  579.99  5831.9  589.43  5996.5  593.06
  6052.6  593.58  6057.7  592.06  6114.6  594.48  6119.6  592.18  6176.5  595.30
  6181.6  593.11  6238.5  596.17  6243.5  594.73  6249.7  596.61  6262.9  596.76
  6305.5  596.47  6310.5  594.43  6367.4  596.63  6372.5  594.19  6428.6  596.68
#Mann=5,-1,0
  3966.5    0.05       0  5115.6    0.03       0  5119.6    0.05       0
  5831.9   0.075       0  6262.9     0.1       0
Bank Sta=5115.6,5119.6
Exp/Cntr=0.3,0.1

Type RM Length L Ch R = 1,6449,739,739,739
BEGIN DESCRIPTION:
Mapping XS 6b487db5
END DESCRIPTION:
XS GIS Cut Line= 4
      2611802.50      7019202.33      2611648.85      7018592.93
      2611088.95      7018686.68      2609706.11      7018876.79
#Sta/Elev= 30
  3814.8  591.94  4197.7  581.13  4308.9  579.77  4331.8  576.76  4358.7  578.72
  4517.1  580.17  4722.0  578.07  4874.4  576.72  4983.5  574.65  5007.9  573.42
  5009.9  570.82  5032.1  570.77  5032.4  570.27  5036.1  570.77  5074.4  575.78
  5079.5  571.97  5084.6  574.57  5124.7  577.32  5223.5  580.14  5228.6  578.34
  5295.6  581.51  5300.6  579.00  5372.7  582.80  5377.7  580.95  5417.7  583.37
  5516.8  584.86  5521.8  582.78  5626.3  586.03  6073.8  593.18  6406.8  595.47
#Mann=8,-1,0
  3814.8    0.05       0  4358.7   0.075       0  4722.0    0.05       0
  4874.4   0.075       0  5032.1    0.07       0  5036.1   0.075       0
  5124.7    0.05       0  5626.3   0.075       0
Bank Sta=5032.1,5036.1
Exp/Cntr=0.3,0.1

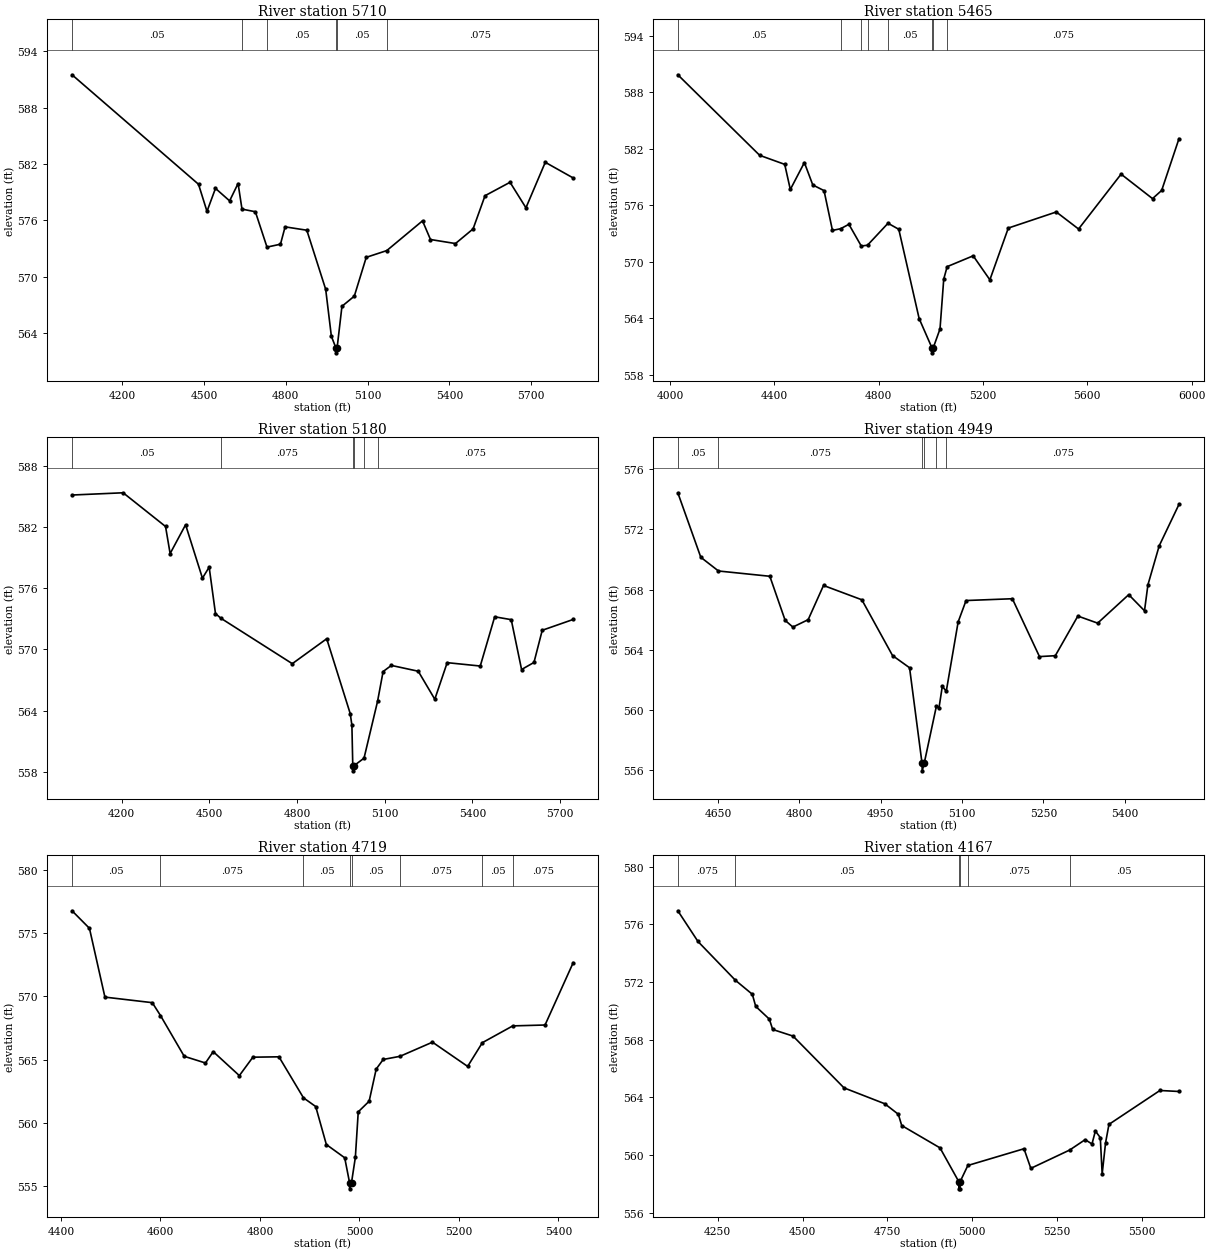
Type RM Length L Ch R = 1,5710,245,245,245
BEGIN DESCRIPTION:
Brushy Creek Tributary S 16.0
END DESCRIPTION:
XS GIS Cut Line= 3
      2611836.35      7019168.47      2611576.00      7018211.00
      2611069.22      7017534.50
#Sta/Elev= 30
  4016.2  591.51  4479.9  579.84  4511.0  576.95  4542.1  579.40  4593.9  578.07
  4625.0  579.92  4639.3  577.19  4688.4  576.91  4731.0  573.14  4780.4  573.45
  4797.4  575.30  4877.0  574.94  4946.2  568.64  4967.0  563.64  4984.0  562.37
  4984.2  561.87  4988.0  562.37  5005.8  566.83  5051.1  567.91  5094.9  572.05
  5170.2  572.77  5301.2  575.94  5330.4  573.95  5422.0  573.52  5486.6  575.08
  5530.4  578.62  5622.1  580.05  5680.4  577.33  5751.3  582.18  5853.7  580.51
#Mann=6,-1,0
  4016.2    0.05       0  4639.3   0.075       0  4731.0    0.05       0
  4984.0   0.035       0  4988.0    0.05       0  5170.2   0.075       0
Bank Sta=4984,4988
Exp/Cntr=0.3,0.1

Type RM Length L Ch R = 1,5465,285,285,285
BEGIN DESCRIPTION:
Brushy Creek Tributary S 15.0
END DESCRIPTION:
XS GIS Cut Line= 3
      2612135.81      7019061.65      2611776.00      7018161.00
      2611146.27      7017447.13
#Sta/Elev= 30
  4029.7  589.86  4343.6  581.30  4439.6  580.34  4461.1  577.67  4515.0  580.53
  4547.3  578.15  4590.4  577.55  4622.7  573.32  4654.0  573.50  4685.7  573.97
  4733.2  571.66  4757.1  571.75  4835.7  574.08  4877.0  573.44  4955.1  563.95
  5004.7  560.81  5004.9  560.31  5008.7  560.81  5035.1  562.85  5049.4  568.15
  5062.5  569.47  5162.3  570.62  5226.3  568.07  5297.0  573.57  5481.0  575.28
  5566.4  573.47  5729.5  579.30  5850.0  576.70  5885.1  577.57  5951.5  583.07
#Mann=8,-1,0
  4029.7    0.05       0  4654.0   0.075       0  4733.2    0.05       0
  4757.1   0.075       0  4835.7    0.05       0  5004.7    0.03       0
  5008.7    0.05       0  5062.5   0.075       0
Bank Sta=5004.7,5008.7
Exp/Cntr=0.3,0.1

Type RM Length L Ch R = 1,5180,231,231,231
BEGIN DESCRIPTION:
Brushy Creek Tributary S 14.0
END DESCRIPTION:
XS GIS Cut Line= 3
      2612508.23      7018897.64      2612026.00      7018061.00
      2611501.11      7017525.94
#Sta/Elev= 30
  4029.7  585.12  4204.6  585.34  4349.7  582.04  4365.4  579.39  4418.3  582.21
  4476.0  576.98  4499.0  578.06  4520.6  573.52  4539.0  573.06  4783.5  568.61
  4901.3  571.05  4981.7  563.73  4987.5  562.59  4990.5  558.62  4990.7  558.12
  4994.5  558.62  5029.0  559.36  5075.2  564.91  5094.3  567.84  5122.6  568.44
  5214.6  567.87  5271.2  565.13  5313.6  568.71  5426.8  568.38  5476.2  573.20
  5532.8  572.92  5568.2  568.04  5610.6  568.73  5638.9  571.88  5744.9  572.94
#Mann=6,-1,0
  4029.7    0.05       0  4539.0   0.075       0  4990.5    0.07       0
  4994.5   0.075       0  5029.0    0.05       0  5075.2   0.075       0
Bank Sta=4990.5,4994.5
Exp/Cntr=0.3,0.1

Type RM Length L Ch R = 1,4949,230,230,230
BEGIN DESCRIPTION:
Brushy Creek Tributary S 13.0
END DESCRIPTION:
XS GIS Cut Line= 3
      2612426.02      7018161.02      2612126.00      7017861.00
      2611825.99      7017460.99
#Sta/Elev= 30
  4575.7  574.42  4618.1  570.14  4650.7  569.23  4745.4  568.88  4773.7  565.95
  4787.9  565.51  4816.1  566.00  4844.4  568.27  4915.1  567.32  4971.7  563.62
  5003.1  562.81  5026.1  556.47  5026.4  555.97  5030.1  556.47  5052.7  560.28
  5057.3  560.13  5063.5  561.58  5070.8  561.25  5092.7  565.85  5107.3  567.27
  5192.7  567.39  5242.7  563.55  5271.9  563.61  5313.5  566.24  5350.0  565.77
  5407.3  567.66  5436.4  566.59  5442.7  568.31  5463.5  570.90  5500.0  573.65
#Mann=6,-1,0
  4575.7    0.05       0  4650.7   0.075       0  5026.1    0.07       0
  5030.1   0.075       0  5052.7    0.05       0  5070.8   0.075       0
Bank Sta=5026.1,5030.1
Exp/Cntr=0.3,0.1

Type RM Length L Ch R = 1,4719,552,552,552
BEGIN DESCRIPTION:
Brushy Creek Tributary S 12.0
END DESCRIPTION:
XS GIS Cut Line= 3
      2612526.00      7018161.01      2612226.00      7017661.00
      2611925.98      7017360.98
#Sta/Elev= 30
  4422.3  576.79  4457.3  575.40  4488.4  569.95  4583.6  569.51  4600.1  568.49
  4647.8  565.26  4690.5  564.73  4706.1  565.63  4758.6  563.73  4785.8  565.19
  4838.2  565.22  4887.5  561.97  4912.1  561.28  4933.5  558.27  4970.4  557.22
  4980.1  555.26  4980.3  554.76  4984.1  555.26  4991.8  557.25  4997.6  560.86
  5019.5  561.70  5033.7  564.25  5047.8  565.01  5081.6  565.26  5146.8  566.38
  5217.5  564.46  5247.1  566.34  5308.2  567.67  5373.1  567.74  5429.7  572.68
#Mann=8,-1,0
  4422.3    0.05       0  4600.1   0.075       0  4887.5    0.05       0
  4980.1    0.03       0  4984.1    0.05       0  5081.6   0.075       0
  5247.1    0.05       0  5308.2   0.075       0
Bank Sta=4980.1,4984.1
Exp/Cntr=0.3,0.1

Type RM Length L Ch R = 1,4167,64,64,64
BEGIN DESCRIPTION:
Mapping XS bbb06638
END DESCRIPTION:
XS GIS Cut Line= 3
      2612612.39      7018280.42      2612633.22      7017418.45
      2612661.82      7016804.94
#Sta/Elev= 30
  4132.3  576.94  4191.7  574.81  4302.0  572.12  4351.8  571.15  4361.8  570.31
  4401.8  569.43  4411.8  568.71  4471.8  568.25  4621.9  564.66  4741.9  563.56
  4781.9  562.83  4791.9  562.05  4904.7  560.50  4960.0  558.16  4960.2  557.66
  4963.7  557.66  4964.0  558.16  4986.7  559.28  5152.1  560.44  5172.2  559.08
  5286.6  560.35  5332.3  561.07  5352.4  560.77  5362.4  561.67  5376.9  561.21
  5382.4  558.69  5392.4  560.85  5402.4  562.13  5552.6  564.48  5608.7  564.41
#Mann=6,-1,0
  4132.3   0.075       0  4302.0    0.05       0  4960.0    0.07       0
  4964.0    0.05       0  4986.7   0.075       0  5286.6    0.05       0
Bank Sta=4960,4964
Exp/Cntr=0.3,0.1

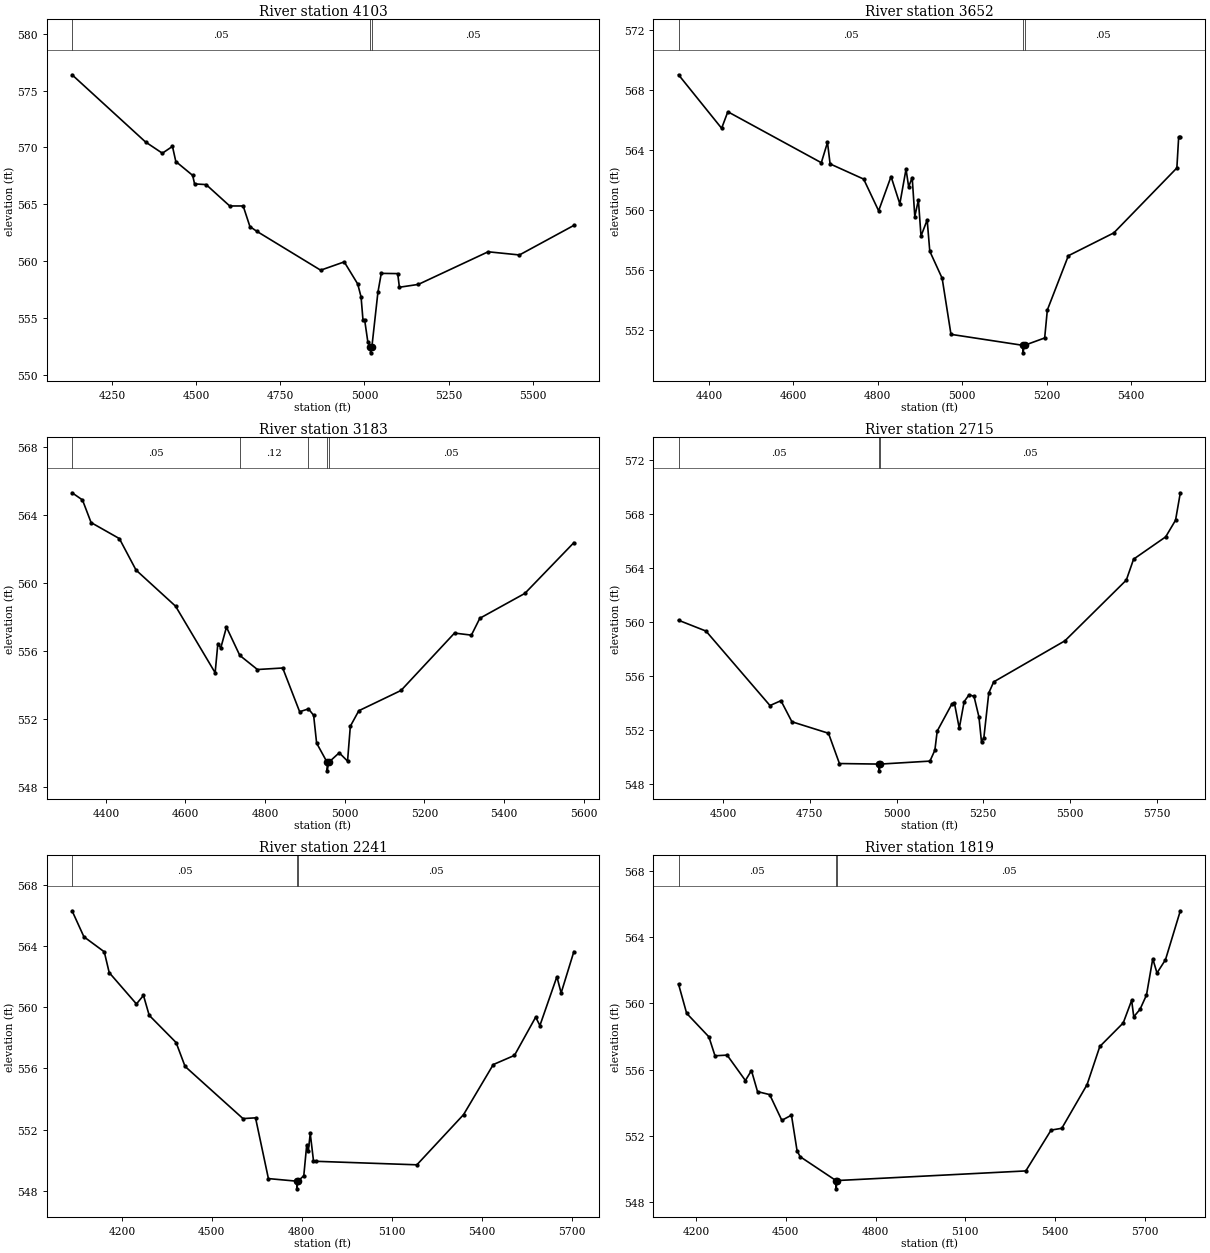
Type RM Length L Ch R = 1,4103,451,451,451
BEGIN DESCRIPTION:
Mapping XS 348a9154
END DESCRIPTION:
XS GIS Cut Line= 3
      2612686.61      7018279.10      2612697.02      7017414.55
      2612720.46      7016789.50
#Sta/Elev= 30
  4131.9  576.39  4350.0  570.48  4400.0  569.49  4430.0  570.09  4440.0  568.76
  4490.0  567.54  4495.7  566.79  4530.0  566.73  4600.0  564.85  4640.0  564.85
  4660.0  563.04  4680.0  562.63  4870.1  559.20  4940.1  559.93  4980.1  557.99
  4990.1  556.85  4995.8  554.81  5000.8  554.81  5010.1  552.91  5018.1  552.43
  5018.3  551.93  5022.1  552.43  5040.1  557.25  5050.1  558.92  5098.9  558.90
  5103.9  557.70  5160.2  557.95  5367.4  560.82  5460.4  560.54  5622.0  563.14
#Mann=3,-1,0
  4131.9    0.05       0  5018.1    0.05       0  5022.1    0.05       0
Bank Sta=5018.1,5022.1
Exp/Cntr=0.3,0.1

Type RM Length L Ch R = 1,3652,469,469,469
BEGIN DESCRIPTION:
Brushy Creek Tributary S 8.0
END DESCRIPTION:
XS GIS Cut Line= 3
      2613564.33      7017555.64      2613026.00      7017161.00
      2612706.16      7016749.21
#Sta/Elev= 30
  4327.9  568.99  4430.0  565.43  4444.7  566.53  4666.2  563.14  4680.8  564.49
  4687.0  563.06  4766.5  562.05  4802.0  559.94  4831.4  562.22  4852.2  560.40
  4866.9  562.71  4873.1  561.54  4881.5  562.15  4887.7  559.56  4896.2  560.66
  4902.4  558.26  4917.0  559.33  4923.2  557.25  4952.5  555.45  4973.4  551.72
  5143.6  550.99  5143.9  550.49  5147.6  550.99  5195.4  551.48  5201.7  553.34
  5251.5  556.95  5359.2  558.47  5508.6  562.79  5512.9  564.86  5516.8  564.86
#Mann=3,-1,0
  4327.9    0.05       0  5143.6    0.03       0  5147.6    0.05       0
Bank Sta=5143.6,5147.6
Exp/Cntr=0.3,0.1

Type RM Length L Ch R = 1,3183,468,468,468
BEGIN DESCRIPTION:
Brushy Creek Tributary S 7.0
END DESCRIPTION:
XS GIS Cut Line= 3
      2613734.80      7017319.52      2613276.00      7016811.00
      2612864.99      7016408.03
#Sta/Elev= 30
  4315.1  565.29  4341.2  564.87  4362.9  563.54  4433.9  562.60  4475.8  560.75
  4575.1  558.63  4674.5  554.72  4681.3  556.43  4688.7  556.18  4702.9  557.40
  4736.4  555.74  4780.7  554.91  4844.2  555.00  4886.8  552.43  4909.0  552.60
  4921.9  552.22  4929.4  550.59  4955.8  549.46  4956.0  548.96  4959.8  549.46
  4986.2  550.02  5007.1  549.53  5014.1  551.58  5035.4  552.49  5141.4  553.68
  5275.8  557.05  5318.2  556.93  5339.4  557.92  5452.5  559.38  5575.6  562.36
#Mann=5,-1,0
  4315.1    0.05       0  4736.4    0.12       0  4909.0    0.05       0
  4955.8    0.03       0  4959.8    0.05       0
Bank Sta=4955.8,4959.8
Exp/Cntr=0.3,0.1

Type RM Length L Ch R = 1,2715,474,474,474
BEGIN DESCRIPTION:
Brushy Creek Tributary S 6.0
END DESCRIPTION:
XS GIS Cut Line= 3
      2613826.01      7017111.04      2613626.00      7016511.00
      2613026.03      7015961.03
#Sta/Elev= 30
  4371.6  560.15  4450.7  559.35  4635.2  553.84  4666.8  554.20  4698.4  552.64
  4803.8  551.79  4835.4  549.55  4949.4  549.51  4949.6  549.01  4953.4  549.51
  5096.3  549.73  5110.5  550.54  5117.2  551.95  5159.8  553.97  5166.9  554.02
  5180.8  552.16  5194.9  554.13  5209.1  554.64  5223.3  554.52  5237.5  553.00
  5244.9  551.14  5251.7  551.46  5265.9  554.77  5280.0  555.59  5485.4  558.63
  5662.3  563.12  5683.3  564.67  5775.8  566.32  5804.2  567.55  5818.0  569.58
#Mann=3,-1,0
  4371.6    0.05       0  4949.4    0.03       0  4953.4    0.05       0
Bank Sta=4949.4,4953.4
Exp/Cntr=0.3,0.1

Type RM Length L Ch R = 1,2241,422,422,422
BEGIN DESCRIPTION:
Brushy Creek Tributary S 5.0
END DESCRIPTION:
XS GIS Cut Line= 3
      2614376.01      7017211.02      2614026.00      7016311.00
      2613525.99      7015810.99
#Sta/Elev= 30
  4034.1  566.30  4073.6  564.60  4141.4  563.62  4157.9  562.26  4248.7  560.21
  4272.1  560.77  4291.2  559.47  4380.9  557.69  4410.8  556.13  4603.9  552.72
  4645.7  552.77  4688.6  548.80  4783.2  548.63  4783.4  548.13  4787.2  548.63
  4806.6  548.99  4816.2  550.97  4821.6  550.59  4828.1  551.75  4838.8  549.98
  4846.1  549.93  5183.6  549.70  5339.2  552.98  5438.2  556.25  5508.9  556.85
  5579.6  559.35  5593.7  558.80  5650.3  561.99  5664.5  560.93  5706.9  563.63
#Mann=3,-1,0
  4034.1    0.05       0  4783.2    0.03       0  4787.2    0.05       0
Bank Sta=4783.2,4787.2
Exp/Cntr=0.3,0.1

Type RM Length L Ch R = 1,1819,299,299,299
BEGIN DESCRIPTION:
Brushy Creek Tributary S 4.0
END DESCRIPTION:
XS GIS Cut Line= 3
      2614526.00      7016960.98      2614376.00      7016111.00
      2613776.04      7015561.03
#Sta/Elev= 30
  4141.6  561.16  4168.7  559.40  4243.1  557.98  4263.4  556.84  4304.0  556.88
  4365.0  555.35  4385.3  555.95  4405.6  554.68  4446.2  554.50  4486.8  552.95
  4519.0  553.26  4537.6  551.13  4547.8  550.76  4667.6  549.32  4667.9  548.82
  4671.6  549.32  5302.2  549.90  5386.7  552.36  5422.5  552.47  5506.9  555.10
  5549.5  557.40  5627.8  558.82  5655.9  560.18  5663.0  559.19  5683.9  559.64
  5705.5  560.50  5726.5  562.69  5740.6  561.83  5769.0  562.63  5818.6  565.58
#Mann=3,-1,0
  4141.6    0.05       0  4667.6    0.03       0  4671.6    0.05       0
Bank Sta=4667.6,4671.6
Exp/Cntr=0.3,0.1

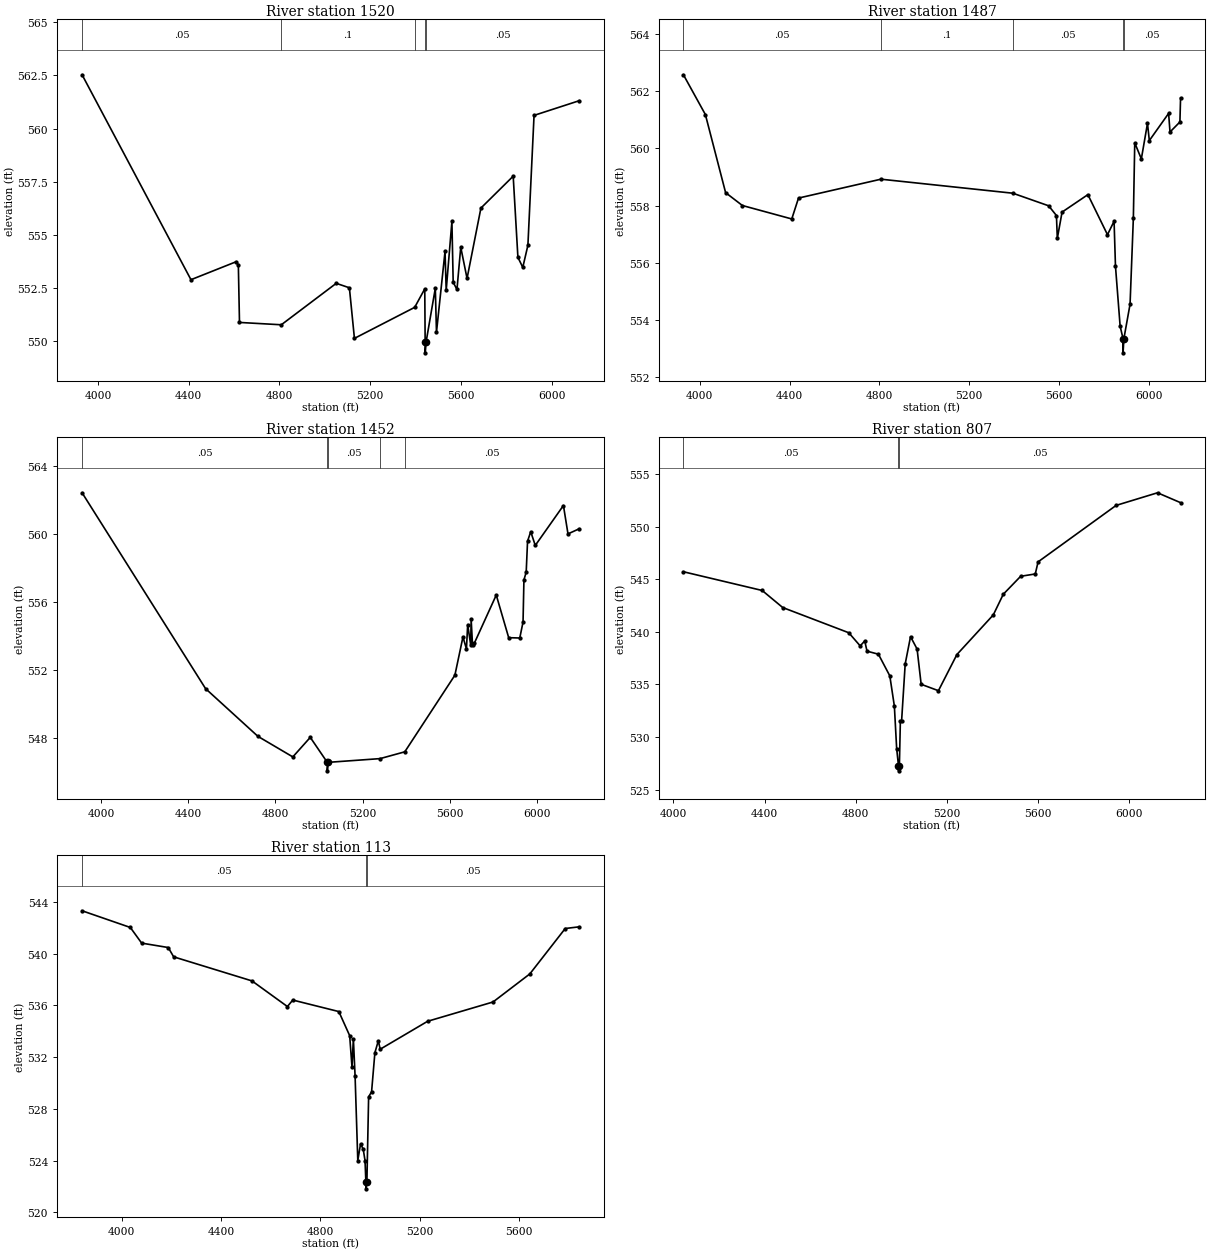
Type RM Length L Ch R = 1,1520,33,33,33
BEGIN DESCRIPTION:
Mapping XS e1536c78
END DESCRIPTION:
XS GIS Cut Line= 6
      2614589.82      7017066.03      2614660.13      7016904.56
      2614631.49      7015571.23      2614608.05      7015469.67
      2614540.34      7015336.86      2614195.17      7015085.11
#Sta/Elev= 30
  3930.4  562.53  4410.1  552.89  4610.2  553.74  4618.9  553.56  4623.9  550.88
  4808.2  550.77  5050.2  552.72  5108.1  552.51  5130.3  550.13  5395.8  551.59
  5440.2  552.46  5441.9  549.95  5442.2  549.45  5445.9  549.95  5486.7  552.49
  5491.8  550.42  5529.5  554.22  5534.6  552.39  5559.8  555.63  5565.4  552.77
  5582.1  552.43  5598.7  554.42  5626.5  552.95  5687.6  556.26  5829.8  557.76
  5850.6  553.94  5872.1  553.47  5894.6  554.51  5921.7  560.62  6120.7  561.31
#Mann=5,-1,0
  3930.4    0.05       0  4808.2     0.1       0  5395.8    0.05       0
  5441.9    0.07       0  5445.9    0.05       0
Bank Sta=5441.9,5445.9
Exp/Cntr=0.3,0.1

Type RM Length L Ch R = 1,1487,35,35,35
BEGIN DESCRIPTION:
Mapping XS b5cbd20a
END DESCRIPTION:
XS GIS Cut Line= 6
      2614617.42      7017071.16      2614684.92      7016895.48
      2614661.69      7015542.51      2614625.24      7015430.53
      2614541.90      7015300.32      2614216.41      7015065.97
#Sta/Elev= 30
  3926.9  562.57  4024.7  561.18  4114.8  558.45  4189.6  558.00  4409.6  557.53
  4439.6  558.26  4806.8  558.92  5394.5  558.43  5554.1  557.99  5588.8  557.65
  5592.7  556.85  5613.9  557.77  5728.9  558.38  5816.2  556.98  5845.6  557.45
  5851.8  555.88  5872.6  553.78  5885.4  553.35  5885.6  552.85  5889.4  553.35
  5916.8  554.55  5931.5  557.56  5937.7  560.19  5967.1  559.63  5994.4  560.87
  6002.7  560.27  6088.6  561.22  6094.8  560.57  6138.9  560.92  6141.8  561.75
#Mann=5,-1,0
  3926.9    0.05       0  4806.8     0.1       0  5394.5    0.05       0
  5885.4    0.07       0  5889.4    0.05       0
Bank Sta=5885.4,5889.4
Exp/Cntr=0.3,0.1

Type RM Length L Ch R = 1,1452,645,645,645
BEGIN DESCRIPTION:
Mapping XS 920cac1b
END DESCRIPTION:
XS GIS Cut Line= 6
      2614646.83      7017080.40      2614725.41      7016904.85
      2614713.69      7015581.93      2614681.57      7015461.45
      2614555.70      7015257.45      2614232.36      7015023.09
#Sta/Elev= 30
  3913.6  562.43  4479.8  550.90  4719.9  548.09  4879.9  546.88  4959.9  548.03
  5037.9  546.56  5038.1  546.06  5041.9  546.56  5280.2  546.78  5393.3  547.18
  5623.0  551.69  5660.0  553.94  5676.0  553.24  5681.7  554.67  5695.5  553.47
  5697.6  554.97  5703.8  553.48  5712.4  553.58  5812.7  556.41  5869.7  553.90
  5920.5  553.88  5935.5  554.82  5939.6  557.30  5950.0  557.76  5956.2  559.58
  5970.8  560.14  5991.6  559.33  6120.7  561.68  6141.6  560.01  6193.1  560.31
#Mann=5,-1,0
  3913.6    0.05       0  5037.9    0.04       0  5041.9    0.05       0
  5280.2     0.1       0  5393.3    0.05       0
Bank Sta=5037.9,5041.9
Exp/Cntr=0.3,0.1

Type RM Length L Ch R = 1,807,694,694,694
BEGIN DESCRIPTION:
Mapping XS ffa6a60d
END DESCRIPTION:
XS GIS Cut Line= 3
      2615291.90      7016766.50      2615289.30      7015813.34
      2614797.12      7014688.36
#Sta/Elev= 30
  4044.1  545.72  4389.6  543.94  4479.6  542.32  4769.6  539.92  4819.6  538.67
  4839.6  539.14  4849.6  538.17  4899.6  537.88  4949.6  535.82  4969.6  532.94
  4979.6  528.91  4987.6  527.29  4987.9  526.79  4991.6  527.29  4995.9  531.53
  5001.3  531.53  5017.1  536.96  5040.5  539.55  5069.3  538.37  5087.1  535.02
  5162.9  534.41  5244.0  537.85  5403.7  541.62  5447.4  543.58  5523.7  545.29
  5587.8  545.51  5600.1  546.66  5942.5  552.03  6124.1  553.23  6225.2  552.29
#Mann=3,-1,0
  4044.1    0.05       0  4987.6    0.04       0  4991.6    0.05       0
Bank Sta=4987.6,4991.6
Exp/Cntr=0.3,0.1

Type RM Length L Ch R = 1,113,0,0,0
BEGIN DESCRIPTION:
Brushy Creek Tributary S 1.0
END DESCRIPTION:
XS GIS Cut Line= 3
      2615416.89      7016769.11      2615878.51      7015705.35
      2615328.38      7015068.57
#Sta/Elev= 30
  3840.4  543.31  4034.6  542.02  4080.2  540.81  4187.2  540.47  4209.0  539.75
  4524.3  537.89  4666.8  535.91  4688.6  536.41  4873.9  535.52  4917.5  533.66
  4926.9  531.22  4932.4  533.42  4939.3  530.54  4950.2  524.01  4961.3  525.29
  4972.0  524.89  4979.3  524.01  4982.8  522.32  4983.0  521.82  4986.8  522.32
  4993.8  528.93  5005.7  529.32  5019.0  532.34  5032.8  533.26  5040.4  532.61
  5231.3  534.77  5494.5  536.26  5642.7  538.43  5785.2  541.94  5841.5  542.07
#Mann=3,-1,0
  3840.4    0.05       0  4982.8    0.03       0  4986.8    0.05       0
Bank Sta=4982.8,4986.8
Exp/Cntr=0.3,0.1

Chan Stop Cuts=-1