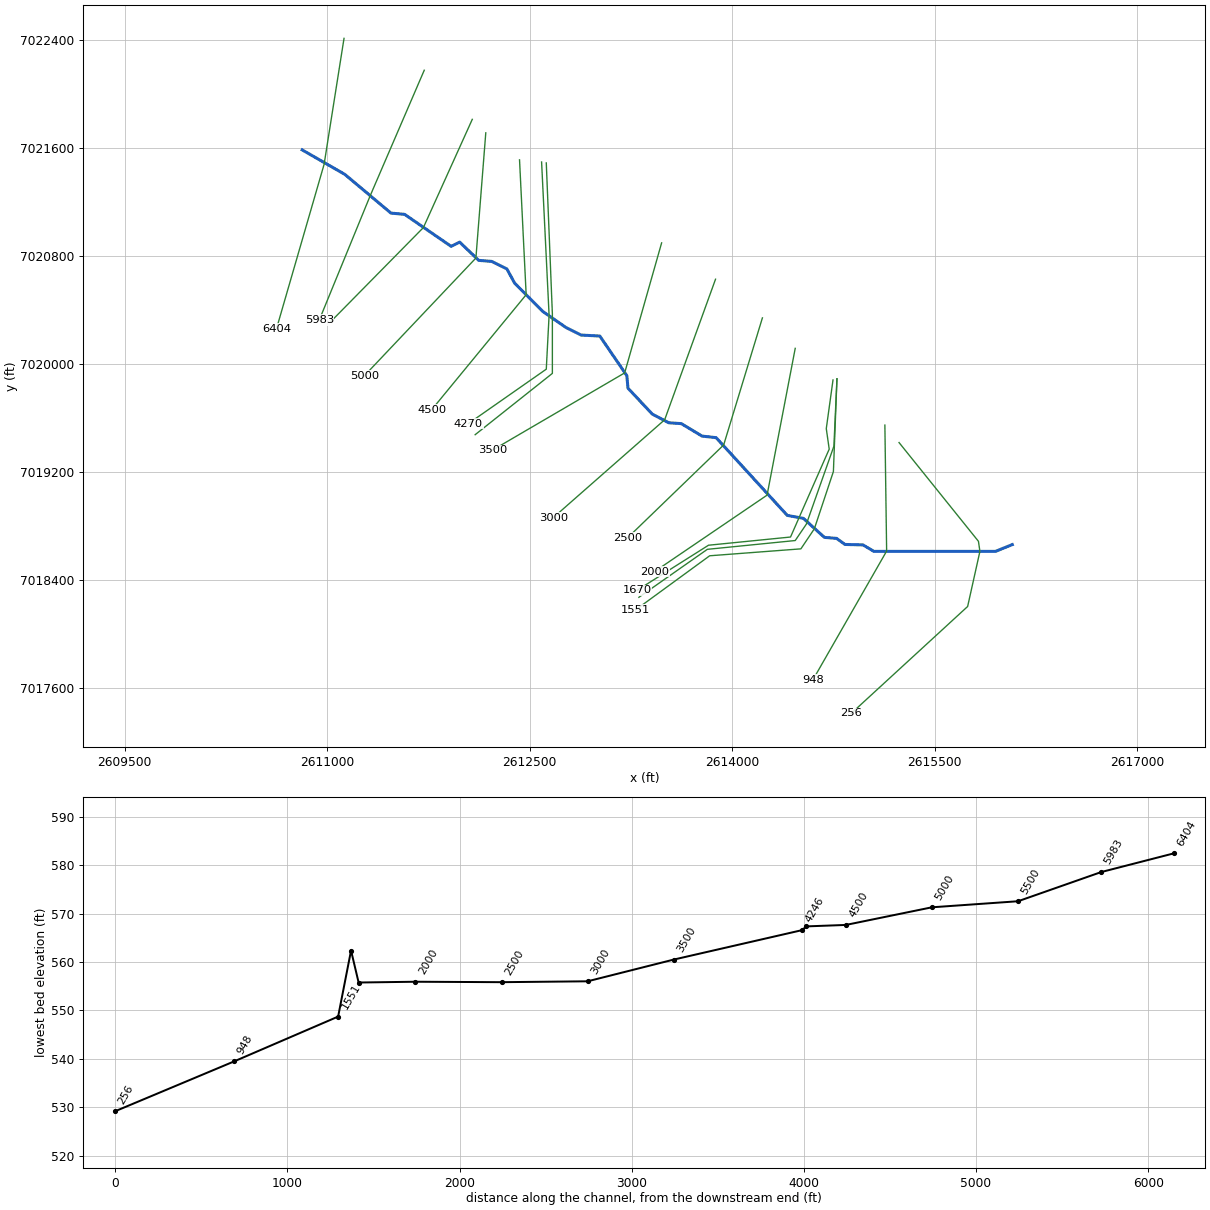
--- Brushy Creek Tributary U.prj (project) ---

Proj Title=Brushy Creek Tributary U Base Level Engineering
Current Plan=p01
Default Exp/Contr=0.3,0.1
English Units
Geom File=g01
Flow File=f01
Plan File=p01
BEGIN DESCRIPTION:
Brushy Creek Tributary U
END DESCRIPTION:

--- Brushy Creek Tributary U.p01 (plan) ---

Plan Title=Multiple Run
Short Identifier=Multiple
Geom File=g01
Flow File=f01
Subcritical Flow
K Sum by GR= 0
Std Step Tol= 0.01
Critical Tol= 0.01
Num of Std Step Trials= 20
Max Error Tol= 0.3
Flow Tol Ratio= 0.001
Split Flow NTrial= 30
Split Flow Tol= 0.02
Split Flow Ratio= 0.02
Log Output Level= 0
Friction Slope Method= 1
Unsteady Friction Slope Method= 2
Unsteady Bridges Friction Slope Method= 1
Parabolic Critical Depth
Global Vel Dist=  1 , 1 , 1
Global Log Level= 0
CheckData=True
Encroach Param= -1, 0, 0, 0
BEGIN DESCRIPTION:
Multiple Run
END DESCRIPTION:

--- Brushy Creek Tributary U.f01 (steady flow) ---

Flow Title=Multiple
Number of Profiles=7
Profile Names=10-year,25-year,50-year,1pct_min,100-year,1pct_plu,500-year
River Rch & RM= Brushy Creek Tri,Reach-1,6404
     420     554     661     392     782    1560    1093
Boundary for River Rch & Prof#=Brushy Creek Tri,Reach-1,1
Up Type=0
Dn Type=3
Dn Slope=0.005
Boundary for River Rch & Prof#=Brushy Creek Tri,Reach-1,2
Up Type=0
Dn Type=3
Dn Slope=0.005
Boundary for River Rch & Prof#=Brushy Creek Tri,Reach-1,3
Up Type=0
Dn Type=3
Dn Slope=0.005
Boundary for River Rch & Prof#=Brushy Creek Tri,Reach-1,4
Up Type=0
Dn Type=3
Dn Slope=0.005
Boundary for River Rch & Prof#=Brushy Creek Tri,Reach-1,5
Up Type=0
Dn Type=3
Dn Slope=0.005
Boundary for River Rch & Prof#=Brushy Creek Tri,Reach-1,6
Up Type=0
Dn Type=3
Dn Slope=0.005
Boundary for River Rch & Prof#=Brushy Creek Tri,Reach-1,7
Up Type=0
Dn Type=3
Dn Slope=0.005

--- Brushy Creek Tributary U.g01 (geometry) ---

Geom Title=Existing Conditions

River Reach=Brushy Creek Tri,Reach-1
Reach XY= 30
      2610815.98      7021584.77      2611132.21      7021403.24
      2611473.57      7021116.52      2611574.50      7021107.37
      2611919.34      7020870.32      2611982.67      7020901.70
      2612123.57      7020766.52      2612220.03      7020758.67
      2612332.34      7020702.98      2612389.64      7020597.80
      2612599.18      7020387.30      2612769.95      7020269.16
      2612881.94      7020213.25      2613020.56      7020205.81
      2613220.44      7019913.36      2613229.50      7019819.48
      2613409.32      7019627.64      2613531.97      7019563.33
      2613624.42      7019557.17      2613777.59      7019464.83
      2613882.17      7019453.14      2614409.25      7018877.46
      2614528.42      7018855.46      2614684.48      7018714.49
      2614774.33      7018707.12      2614836.51      7018662.23
      2614970.06      7018658.73      2615050.92      7018610.80
      2615951.10      7018610.76      2616076.00      7018661.00

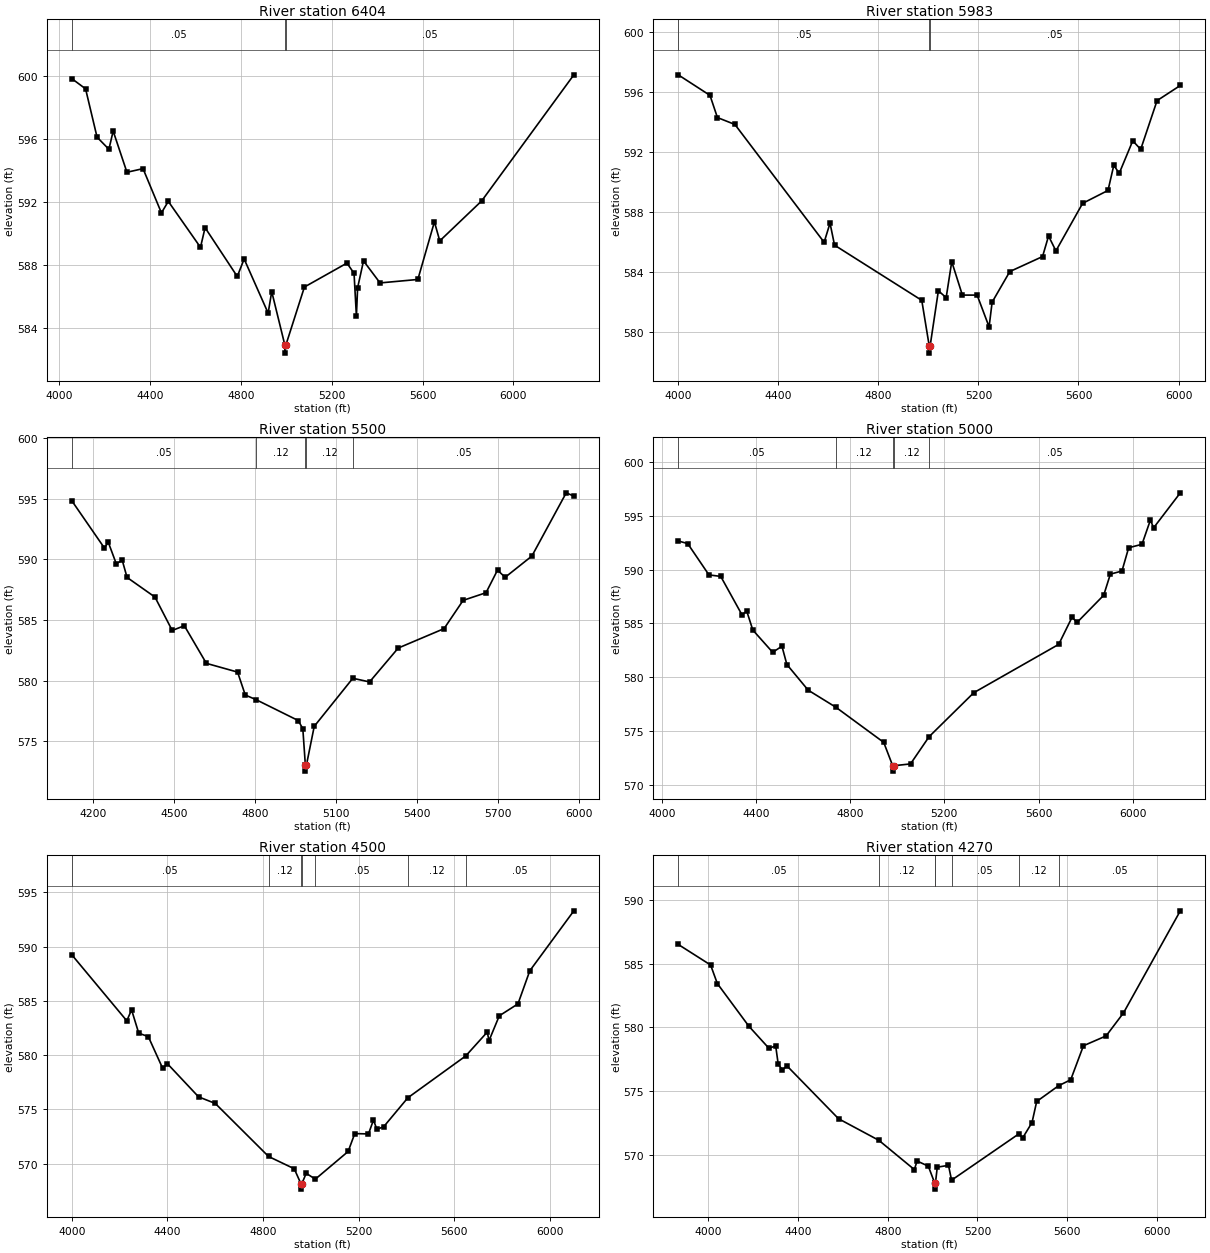
Type RM Length L Ch R = 1,6404,421,421,421
BEGIN DESCRIPTION:
Brushy Creek Tributary 7 12.0
END DESCRIPTION:
XS GIS Cut Line= 3
      2611126.00      7022411.03      2610978.39      7021477.63
      2610626.01      7020261.03
#Sta/Elev= 30
  4055.0  599.85  4115.8  599.20  4166.4  596.13  4218.6  595.36  4237.3  596.52
  4298.0  593.90  4368.9  594.13  4449.9  591.32  4480.2  592.05  4622.0  589.13
  4642.2  590.38  4784.0  587.28  4814.3  588.39  4920.0  584.95  4935.8  586.32
  4993.8  582.91  4994.0  582.41  4997.8  582.91  5079.8  586.61  5267.2  588.13
  5298.4  587.48  5308.8  584.76  5314.1  586.56  5340.1  588.27  5412.9  586.87
  5579.5  587.09  5652.4  590.75  5676.0  589.54  5860.6  592.08  6266.6  600.09
#Mann=3,-1,0
  4055.0    0.05       0  4993.8    0.03       0  4997.8    0.05       0
Bank Sta=4993.8,4997.8
Exp/Cntr=0.3,0.1

Type RM Length L Ch R = 1,5983,483,483,483
BEGIN DESCRIPTION:
Mapping XS bc65a82a
END DESCRIPTION:
XS GIS Cut Line= 3
      2611720.23      7022174.87      2611320.93      7021247.79
      2610942.82      7020325.07
#Sta/Elev= 30
  4000.4  597.12  4127.3  595.75  4157.0  594.27  4226.9  593.81  4583.5  585.95
  4607.0  587.23  4625.1  585.76  4973.7  582.08  5003.3  579.06  5003.5  578.56
  5007.3  579.06  5040.1  582.72  5071.2  582.26  5093.5  584.66  5136.0  582.43
  5194.9  582.43  5242.8  580.31  5254.9  581.96  5325.6  584.00  5456.4  585.00
  5480.4  586.37  5509.8  585.38  5616.6  588.55  5718.0  589.41  5741.2  591.09
  5762.8  590.55  5816.9  592.72  5848.7  592.15  5914.1  595.40  6007.0  596.41
#Mann=3,-1,0
  4000.4    0.05       0  5003.3    0.03       0  5007.3    0.05       0
Bank Sta=5003.3,5007.3
Exp/Cntr=0.3,0.1

Type RM Length L Ch R = 1,5500,500,500,500
BEGIN DESCRIPTION:
Brushy Creek Tributary 7 11.0
END DESCRIPTION:
XS GIS Cut Line= 3
      2612076.01      7021811.02      2611713.92      7021009.51
      2611025.99      7020310.99
#Sta/Elev= 30
  4120.5  594.82  4241.2  590.93  4255.9  591.39  4285.1  589.64  4307.6  589.90
  4325.3  588.50  4428.7  586.88  4492.6  584.13  4537.5  584.52  4619.1  581.42
  4734.7  580.70  4763.3  578.81  4803.1  578.43  4959.2  576.71  4976.4  576.04
  4985.8  573.04  4986.1  572.54  4989.8  573.04  5018.7  576.23  5161.6  580.19
  5223.7  579.89  5329.8  582.68  5499.6  584.28  5570.3  586.61  5655.1  587.24
  5697.6  589.10  5725.9  588.51  5824.9  590.26  5952.2  595.47  5980.4  595.20
#Mann=5,-1,0
  4120.5    0.05       0  4803.1    0.12       0  4985.8    0.07       0
  4989.8    0.12       0  5161.6    0.05       0
Bank Sta=4985.8,4989.8
Exp/Cntr=0.3,0.1

Type RM Length L Ch R = 1,5000,500,500,500
BEGIN DESCRIPTION:
Brushy Creek Tributary 7 10.0
END DESCRIPTION:
XS GIS Cut Line= 3
      2612176.00      7021710.96      2612102.76      7020783.65
      2611276.00      7019911.00
#Sta/Elev= 30
  4069.8  592.66  4109.9  592.42  4200.2  589.51  4250.3  589.37  4340.6  585.80
  4360.7  586.15  4386.5  584.39  4471.0  582.32  4510.2  582.89  4531.2  581.19
  4621.5  578.81  4739.4  577.22  4942.5  573.96  4980.6  571.79  4980.8  571.29
  4984.6  571.79  5056.3  571.96  5135.3  574.49  5324.9  578.57  5685.7  583.06
  5742.4  585.58  5763.4  585.09  5876.7  587.62  5905.0  589.58  5954.3  589.87
  5982.7  592.03  6039.3  592.35  6074.9  594.59  6089.0  593.89  6202.1  597.13
#Mann=5,-1,0
  4069.8    0.05       0  4739.4    0.12       0  4980.6    0.07       0
  4984.6    0.12       0  5135.3    0.05       0
Bank Sta=4980.6,4984.6
Exp/Cntr=0.3,0.1

Type RM Length L Ch R = 1,4500,230,230,230
BEGIN DESCRIPTION:
Brushy Creek Tributary 7 9.0
END DESCRIPTION:
XS GIS Cut Line= 3
      2612426.00      7021510.97      2612475.07      7020511.88
      2611776.02      7019661.02
#Sta/Elev= 30
  3999.7  589.26  4230.0  583.17  4250.0  584.18  4280.0  582.03  4320.1  581.71
  4380.1  578.79  4400.2  579.21  4530.3  576.16  4600.4  575.55  4823.4  570.66
  4930.8  569.53  4958.8  568.15  4959.1  567.65  4962.8  568.15  4980.9  569.11
  5019.2  568.57  5156.4  571.12  5184.2  572.77  5241.6  572.74  5262.5  574.02
  5276.8  573.16  5305.5  573.41  5406.3  576.07  5648.7  579.93  5738.8  582.13
  5746.1  581.34  5789.1  583.63  5867.3  584.73  5916.8  587.78  6101.2  593.31
#Mann=7,-1,0
  3999.7    0.05       0  4823.4    0.12       0  4958.8    0.07       0
  4962.8    0.12       0  5019.2    0.05       0  5406.3    0.12       0
  5648.7    0.05       0
Bank Sta=4958.8,4962.8
Exp/Cntr=0.3,0.1

Type RM Length L Ch R = 1,4270,24,24,24
BEGIN DESCRIPTION:
Mapping XS 3a598d46
END DESCRIPTION:
XS GIS Cut Line= 4
      2612589.39      7021495.20      2612644.94      7020359.82
      2612624.11      7019960.52      2612047.68      7019557.71
#Sta/Elev= 30
  3865.0  586.50  4009.4  584.89  4039.4  583.44  4179.6  580.11  4269.7  578.37
  4299.7  578.56  4311.0  577.13  4329.8  576.67  4349.8  577.00  4580.1  572.86
  4760.0  571.17  4918.3  568.88  4930.5  569.55  4980.5  569.15  5008.6  567.85
  5008.8  567.35  5012.6  567.85  5020.6  569.07  5070.6  569.21  5084.4  568.05
  5384.2  571.67  5401.6  571.36  5443.2  572.56  5464.1  574.21  5561.6  575.44
  5615.9  575.91  5672.6  578.57  5773.7  579.34  5851.3  581.14  6104.8  589.13
#Mann=7,-1,0
  3865.0    0.05       0  4760.0    0.12       0  5008.6    0.07       0
  5012.6    0.12       0  5084.4    0.05       0  5384.2    0.12       0
  5561.6    0.05       0
Bank Sta=5008.6,5012.6
Exp/Cntr=0.3,0.1

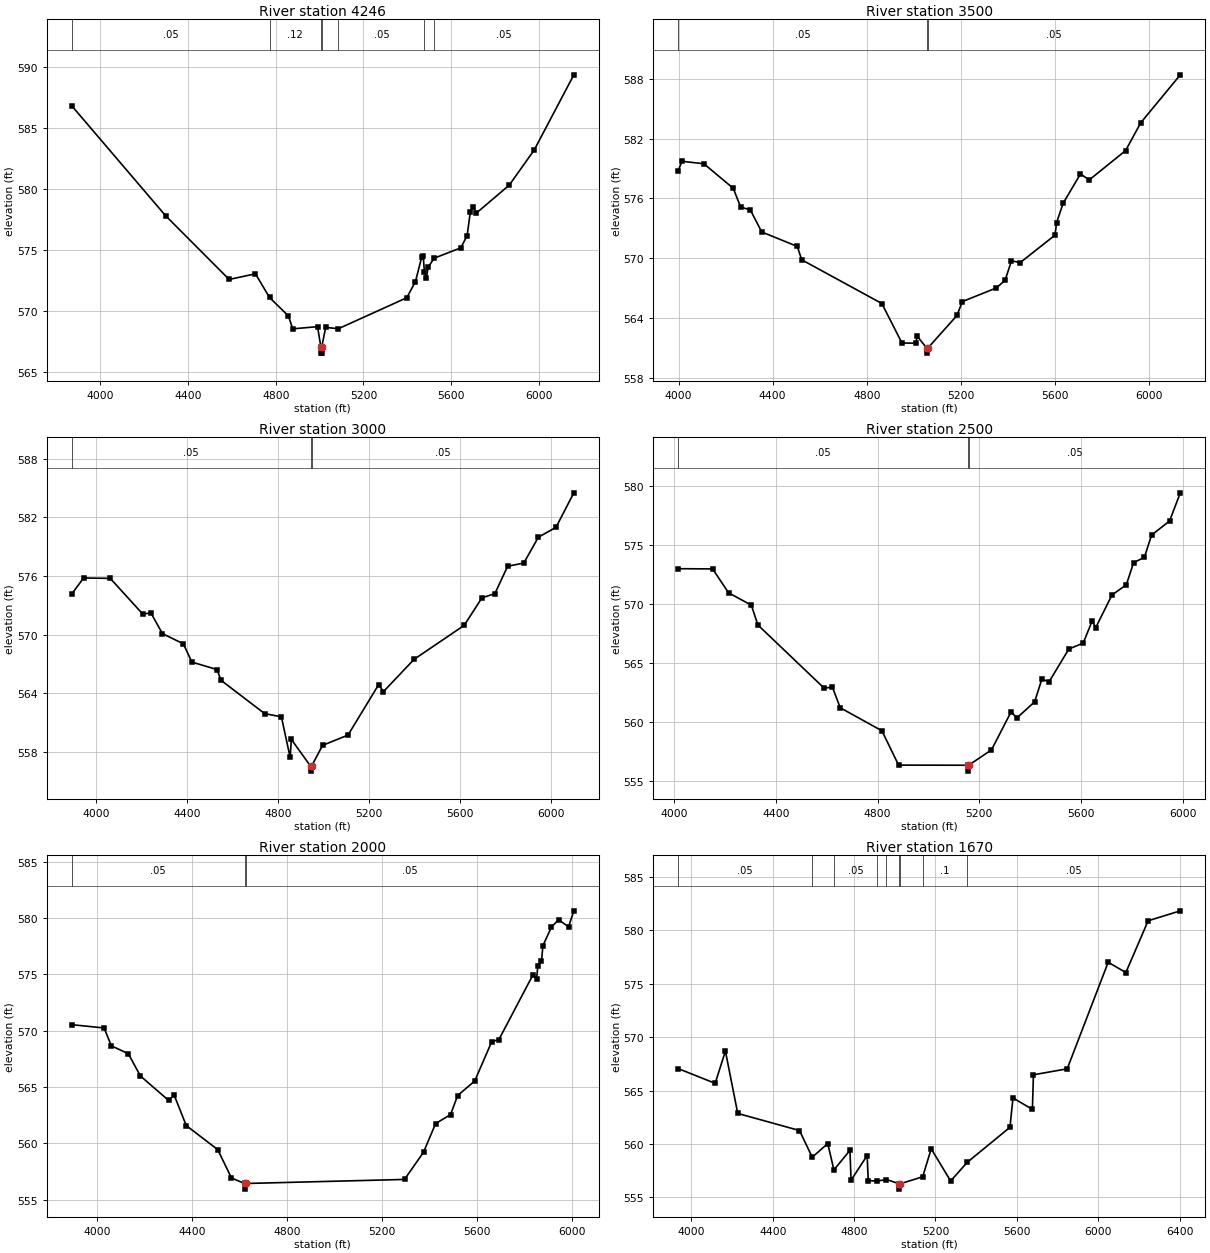
Type RM Length L Ch R = 1,4246,746,746,746
BEGIN DESCRIPTION:
Mapping XS 1bb0cd32
END DESCRIPTION:
XS GIS Cut Line= 4
      2612624.11      7021488.30      2612669.25      7020370.24
      2612669.25      7019929.27      2612097.32      7019475.19
#Sta/Elev= 30
  3869.4  586.85  4297.0  577.85  4587.3  572.62  4707.4  573.08  4771.4  571.14
  4857.5  569.63  4877.5  568.57  4990.5  568.75  5005.6  567.08  5005.9  566.58
  5009.4  566.58  5009.6  567.08  5027.6  568.69  5085.5  568.58  5397.6  571.12
  5437.2  572.45  5466.1  574.49  5472.5  574.53  5478.1  573.21  5486.9  572.75
  5494.9  573.62  5522.5  574.36  5643.9  575.21  5672.8  576.21  5687.2  578.13
  5701.6  578.56  5714.4  578.05  5865.0  580.35  5978.8  583.23  6159.6  589.39
#Mann=7,-1,0
  3869.4    0.05       0  4771.4    0.12       0  5005.6    0.07       0
  5009.6    0.12       0  5085.5    0.05       0  5478.1    0.12       0
  5522.5    0.05       0
Bank Sta=5005.6,5009.6
Exp/Cntr=0.3,0.1

Type RM Length L Ch R = 1,3500,500,500,500
BEGIN DESCRIPTION:
Brushy Creek Tributary 7 7.0
END DESCRIPTION:
XS GIS Cut Line= 3
      2613478.49      7020896.06      2613204.69      7019932.81
      2612225.99      7019360.99
#Sta/Elev= 30
  3998.6  578.77  4014.3  579.72  4107.8  579.47  4232.6  577.01  4263.8  575.14
  4305.3  574.84  4353.6  572.64  4504.8  571.19  4523.7  569.85  4864.4  565.47
  4949.9  561.51  5008.9  561.50  5014.7  562.19  5055.7  561.00  5055.9  560.50
  5059.7  561.00  5183.8  564.27  5206.4  565.66  5351.1  567.03  5388.3  567.79
  5415.6  569.75  5452.8  569.57  5600.7  572.32  5607.4  573.58  5635.5  575.52
  5709.0  578.45  5746.2  577.85  5900.8  580.79  5965.3  583.58  6133.5  588.38
#Mann=3,-1,0
  3998.6    0.05       0  5055.7    0.03       0  5059.7    0.05       0
Bank Sta=5055.7,5059.7
Exp/Cntr=0.3,0.1

Type RM Length L Ch R = 1,3000,500,500,500
BEGIN DESCRIPTION:
Brushy Creek Tributary 7 6.0
END DESCRIPTION:
XS GIS Cut Line= 3
      2613877.79      7020626.95      2613501.02      7019585.83
      2612676.00      7018861.00
#Sta/Elev= 30
  3892.8  574.16  3944.6  575.80  4061.8  575.76  4204.4  572.11  4240.4  572.22
  4291.0  570.10  4383.0  569.06  4420.2  567.19  4530.9  566.42  4547.8  565.33
  4740.1  561.91  4813.7  561.58  4852.0  557.42  4857.3  559.27  4942.0  556.52
  4942.2  556.02  4946.0  556.52  4994.5  558.66  5106.2  559.71  5240.9  564.88
  5261.8  564.16  5396.5  567.47  5616.6  570.95  5694.4  573.76  5751.4  574.20
  5807.4  577.00  5878.5  577.33  5942.1  579.97  6019.9  580.99  6098.2  584.52
#Mann=3,-1,0
  3892.8    0.05       0  4942.0    0.03       0  4946.0    0.05       0
Bank Sta=4942,4946
Exp/Cntr=0.3,0.1

Type RM Length L Ch R = 1,2500,500,500,500
BEGIN DESCRIPTION:
Brushy Creek Tributary 7 5.0
END DESCRIPTION:
XS GIS Cut Line= 3
      2614225.00      7020340.46      2613938.08      7019399.11
      2613226.02      7018711.02
#Sta/Elev= 30
  4015.9  573.00  4151.2  572.98  4214.0  570.95  4303.4  569.91  4329.0  568.23
  4590.3  562.86  4621.7  562.98  4653.0  561.21  4816.8  559.26  4882.4  556.35
  5153.8  556.34  5154.1  555.84  5157.8  556.34  5247.7  557.64  5325.4  560.89
  5346.7  560.33  5417.5  561.72  5445.8  563.64  5474.1  563.41  5551.8  566.19
  5608.3  566.69  5643.6  568.57  5657.7  568.01  5721.5  570.77  5778.1  571.64
  5806.4  573.51  5848.9  573.96  5877.2  575.85  5947.9  577.04  5990.2  579.43
#Mann=3,-1,0
  4015.9    0.05       0  5153.8    0.03       0  5157.8    0.05       0
Bank Sta=5153.8,5157.8
Exp/Cntr=0.3,0.1

Type RM Length L Ch R = 1,2000,330,330,330
BEGIN DESCRIPTION:
Brushy Creek Tributary 7 4.0
END DESCRIPTION:
XS GIS Cut Line= 3
      2614468.07      7020114.80      2614259.56      7019027.41
      2613425.99      7018460.99
#Sta/Elev= 30
  3892.8  570.53  4029.0  570.24  4059.6  568.65  4130.9  567.96  4181.8  565.98
  4300.5  563.81  4324.3  564.27  4375.2  561.57  4507.6  559.44  4565.6  556.92
  4620.7  556.43  4620.9  555.93  4624.7  556.43  5294.5  556.79  5374.6  559.21
  5425.5  561.75  5488.4  562.55  5518.3  564.24  5590.2  565.53  5662.0  569.03
  5691.9  569.20  5835.6  574.96  5850.6  574.62  5856.6  575.77  5871.5  576.16
  5877.6  577.55  5913.5  579.20  5943.4  579.85  5985.4  579.22  6007.8  580.64
#Mann=3,-1,0
  3892.8    0.05       0  4620.7    0.03       0  4624.7    0.05       0
Bank Sta=4620.7,4624.7
Exp/Cntr=0.3,0.1

Type RM Length L Ch R = 1,1670,44,44,44
BEGIN DESCRIPTION:
Mapping XS d5ad3f5c
END DESCRIPTION:
XS GIS Cut Line= 6
      2614747.94      7019880.75      2614698.10      7019520.16
      2614719.80      7019368.25      2614433.34      7018717.21
      2613825.70      7018656.45      2613296.16      7018322.22
#Sta/Elev= 30
  3935.5  567.06  4117.0  565.68  4167.4  568.70  4228.0  562.86  4531.6  561.26
  4594.2  558.76  4670.7  560.04  4700.7  557.57  4779.7  559.40  4785.1  556.60
  4864.2  558.92  4869.6  556.57  4911.8  556.52  4959.2  556.67  5022.5  556.27
  5022.8  555.77  5026.5  556.27  5137.3  556.93  5179.1  559.55  5274.6  556.53
  5356.2  558.28  5566.2  561.56  5581.1  564.31  5676.6  563.24  5681.6  566.48
  5847.7  567.04  6049.1  577.02  6136.1  576.06  6245.5  580.91  6403.7  581.84
#Mann=9,-1,0
  3935.5    0.05       0  4594.2     0.1       0  4700.7    0.05       0
  4911.8     0.1       0  4959.2    0.05       0  5022.5    0.03       0
  5026.5    0.05       0  5137.3     0.1       0  5356.2    0.05       0
Bank Sta=5022.5,5026.5
Exp/Cntr=0.3,0.1

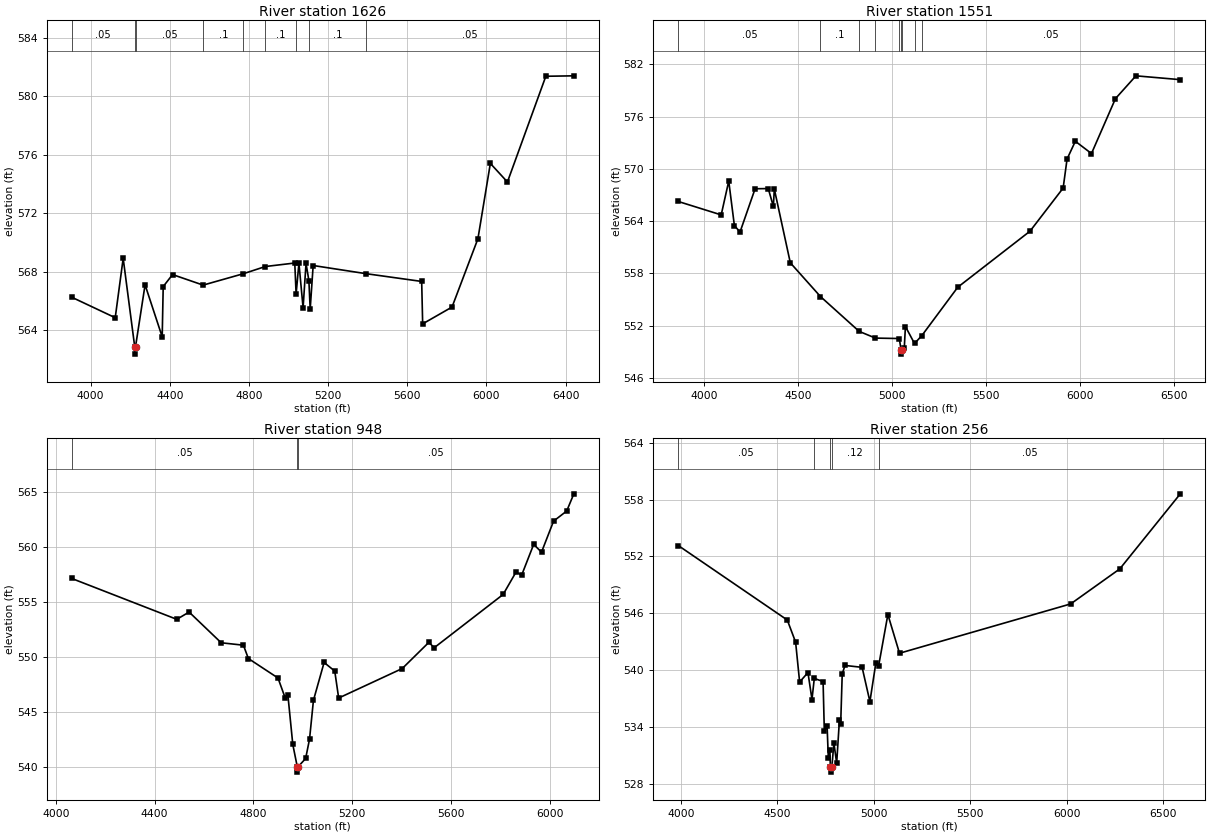
Type RM Length L Ch R = 1,1626,75,75,75
BEGIN DESCRIPTION:
Mapping XS aa744c58
END DESCRIPTION:
XS GIS Cut Line= 6
      2614777.16      7019889.29      2614754.52      7019389.95
      2614550.53      7018812.70      2614468.06      7018691.17
      2613817.02      7018626.06      2613310.07      7018270.76
#Sta/Elev= 30
  3905.1  566.26  4124.6  564.86  4164.8  568.92  4223.1  562.87  4223.4  562.37
  4227.1  562.87  4275.4  567.11  4361.9  563.55  4367.0  566.99  4414.2  567.81
  4568.7  567.09  4772.4  567.87  4882.7  568.36  5031.6  568.60  5038.4  566.48
  5052.6  568.59  5073.6  565.54  5088.5  568.57  5102.9  567.40  5109.5  565.45
  5124.5  568.43  5392.4  567.87  5672.7  567.34  5677.7  564.44  5826.1  565.59
  5956.8  570.26  6019.6  575.41  6105.9  574.14  6299.8  581.37  6441.4  581.40
#Mann=9,-1,0
  3905.1    0.05       0  4223.1    0.07       0  4227.1    0.05       0
  4568.7     0.1       0  4772.4    0.05       0  4882.7     0.1       0
  5038.4    0.05       0  5102.9     0.1       0  5392.4    0.05       0
Bank Sta=4223.1,4227.1
Exp/Cntr=0.3,0.1

Type RM Length L Ch R = 1,1551,603,603,603
BEGIN DESCRIPTION:
Mapping XS 038ef3ad
END DESCRIPTION:
XS GIS Cut Line= 6
      2614777.16      7019889.25      2614750.86      7019202.52
      2614609.52      7018777.74      2614509.98      7018629.60
      2613834.38      7018578.32      2613287.47      7018178.99
#Sta/Elev= 30
  3863.9  566.26  4092.3  564.72  4132.4  568.60  4162.4  563.50  4192.4  562.75
  4272.5  567.72  4342.5  567.74  4369.7  565.69  4374.7  567.69  4459.8  559.22
  4620.0  555.35  4825.9  551.35  4912.4  550.58  5039.0  550.53  5048.7  549.24
  5049.0  548.74  5052.7  549.24  5065.7  549.44  5071.7  551.91  5120.1  549.96
  5158.8  550.86  5350.1  556.42  5734.1  562.85  5910.3  567.80  5931.1  571.13
  5975.1  573.17  6060.9  571.76  6188.3  578.06  6297.2  580.68  6533.2  580.24
#Mann=9,-1,0
  3863.9    0.05       0  4620.0     0.1       0  4825.9    0.05       0
  4912.4     0.1       0  5039.0    0.05       0  5048.7    0.07       0
  5052.7    0.05       0  5120.1     0.1       0  5158.8    0.05       0
Bank Sta=5048.7,5052.7
Exp/Cntr=0.3,0.1

Type RM Length L Ch R = 1,948,692,692,692
BEGIN DESCRIPTION:
Mapping XS c212b66e
END DESCRIPTION:
XS GIS Cut Line= 3
      2615132.13      7019546.23      2615145.15      7018613.04
      2614598.25      7017658.14
#Sta/Elev= 30
  4064.3  557.10  4489.6  553.39  4539.6  554.05  4669.6  551.26  4759.6  551.04
  4779.6  549.83  4899.6  548.06  4929.6  546.20  4939.6  546.53  4959.6  542.02
  4977.6  540.01  4977.9  539.51  4981.6  540.01  5011.6  540.75  5027.4  542.51
  5043.2  546.03  5086.4  549.47  5129.5  548.69  5145.4  546.24  5402.9  548.92
  5510.8  551.30  5532.4  550.81  5811.6  555.65  5864.2  557.70  5886.4  557.39
  5935.3  560.20  5967.0  559.49  6015.9  562.31  6069.1  563.23  6098.0  564.79
#Mann=3,-1,0
  4064.3    0.05       0  4977.6    0.03       0  4981.6    0.05       0
Bank Sta=4977.6,4981.6
Exp/Cntr=0.3,0.1

Type RM Length L Ch R = 1,256,0,0,0
BEGIN DESCRIPTION:
Brushy Creek Tributary 7 1.0
END DESCRIPTION:
XS GIS Cut Line= 5
      2615237.17      7019416.85      2615825.20      7018685.42
      2615836.01      7018610.99      2615745.08      7018202.67
      2614883.10      7017410.97
#Sta/Elev= 30
  3986.3  553.15  4551.5  545.28  4594.7  542.94  4615.5  538.73  4658.7  539.73
  4679.5  536.88  4691.5  539.11  4737.1  538.78  4743.5  533.54  4757.9  534.07
  4764.3  530.68  4772.3  531.60  4774.9  529.71  4776.0  529.21  4782.5  529.71
  4793.1  532.29  4807.5  530.16  4821.9  534.74  4828.3  534.29  4836.3  539.60
  4850.7  540.48  4939.4  540.28  4979.8  536.66  5010.2  540.69  5024.9  540.42
  5072.9  545.86  5133.2  541.77  6020.4  546.98  6275.0  550.68  6588.7  558.61
#Mann=5,-1,0
  3986.3    0.05       0  4691.5    0.12       0  4774.9    0.07       0
  4782.5    0.12       0  5024.9    0.05       0
Bank Sta=4774.9,4782.5
Exp/Cntr=0.3,0.1

Chan Stop Cuts=-1