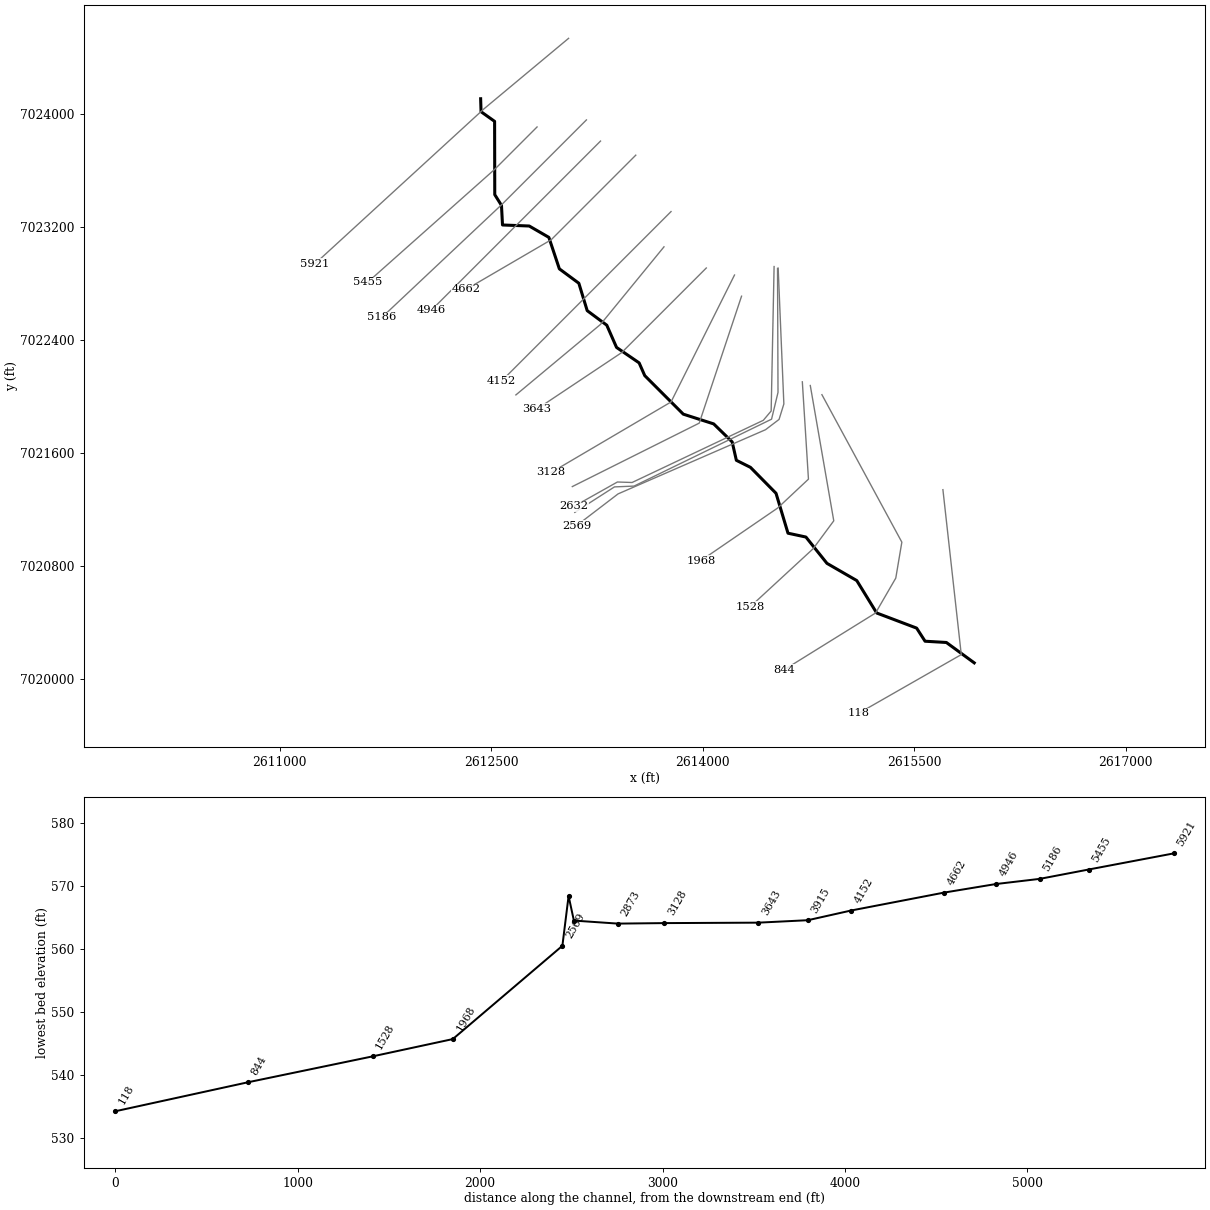
--- Brushy Creek Tributary V.prj (project) ---

Proj Title=Brushy Creek Tributary V Base Level Engineering
Current Plan=p01
Default Exp/Contr=0.3,0.1
English Units
Geom File=g01
Flow File=f01
Plan File=p01
BEGIN DESCRIPTION:
Brushy Creek Tributary V
END DESCRIPTION:

--- Brushy Creek Tributary V.p01 (plan) ---

Plan Title=Multiple Run
Short Identifier=Multiple
Geom File=g01
Flow File=f01
Subcritical Flow
K Sum by GR= 0
Std Step Tol= 0.01
Critical Tol= 0.01
Num of Std Step Trials= 20
Max Error Tol= 0.3
Flow Tol Ratio= 0.001
Split Flow NTrial= 30
Split Flow Tol= 0.02
Split Flow Ratio= 0.02
Log Output Level= 0
Friction Slope Method= 1
Unsteady Friction Slope Method= 2
Unsteady Bridges Friction Slope Method= 1
Parabolic Critical Depth
Global Vel Dist=  1 , 1 , 1
Global Log Level= 0
CheckData=True
Encroach Param= -1, 0, 0, 0
BEGIN DESCRIPTION:
Multiple Run
END DESCRIPTION:

--- Brushy Creek Tributary V.f01 (steady flow) ---

Flow Title=Multiple
Number of Profiles=7
Profile Names=10-year,25-year,50-year,1pct_min,100-year,1pct_plu,500-year
River Rch & RM= Brushy Creek Tri,Reach-1,5921
     309     395     461     267     533    1064     713
River Rch & RM= Brushy Creek Tri,Reach-1,2632
     381     497     587     345     688    1373     944
River Rch & RM= Brushy Creek Tri,Reach-1,844
     398     520     616     362     723    1442     995
Boundary for River Rch & Prof#=Brushy Creek Tri,Reach-1,1
Up Type=0
Dn Type=3
Dn Slope=0.005
Boundary for River Rch & Prof#=Brushy Creek Tri,Reach-1,2
Up Type=0
Dn Type=3
Dn Slope=0.005
Boundary for River Rch & Prof#=Brushy Creek Tri,Reach-1,3
Up Type=0
Dn Type=3
Dn Slope=0.005
Boundary for River Rch & Prof#=Brushy Creek Tri,Reach-1,4
Up Type=0
Dn Type=3
Dn Slope=0.005
Boundary for River Rch & Prof#=Brushy Creek Tri,Reach-1,5
Up Type=0
Dn Type=3
Dn Slope=0.005
Boundary for River Rch & Prof#=Brushy Creek Tri,Reach-1,6
Up Type=0
Dn Type=3
Dn Slope=0.005
Boundary for River Rch & Prof#=Brushy Creek Tri,Reach-1,7
Up Type=0
Dn Type=3
Dn Slope=0.005

--- Brushy Creek Tributary V.g01 (geometry) ---

Geom Title=Existing Conditions

River Reach=Brushy Creek Tri,Reach-1
Reach XY= 30
      2612426.00      7024111.00      2612428.86      7024019.12
      2612525.00      7023950.71      2612526.07      7023431.03
      2612573.72      7023355.05      2612581.01      7023216.00
      2612770.48      7023208.65      2612909.70      7023128.13
      2612984.13      7022904.93      2613122.33      7022802.81
      2613181.52      7022608.56      2613320.41      7022505.39
      2613389.61      7022347.76      2613549.84      7022238.14
      2613589.64      7022147.80      2613862.78      7021874.62
      2614078.43      7021805.48      2614209.54      7021677.75
      2614239.26      7021547.35      2614339.20      7021497.36
      2614520.48      7021313.43      2614605.36      7021030.43
      2614732.43      7021003.21      2614881.63      7020816.65
      2615093.05      7020694.50      2615234.19      7020464.67
      2615517.51      7020357.46      2615577.27      7020264.48
      2615728.44      7020255.52      2615926.00      7020111.00

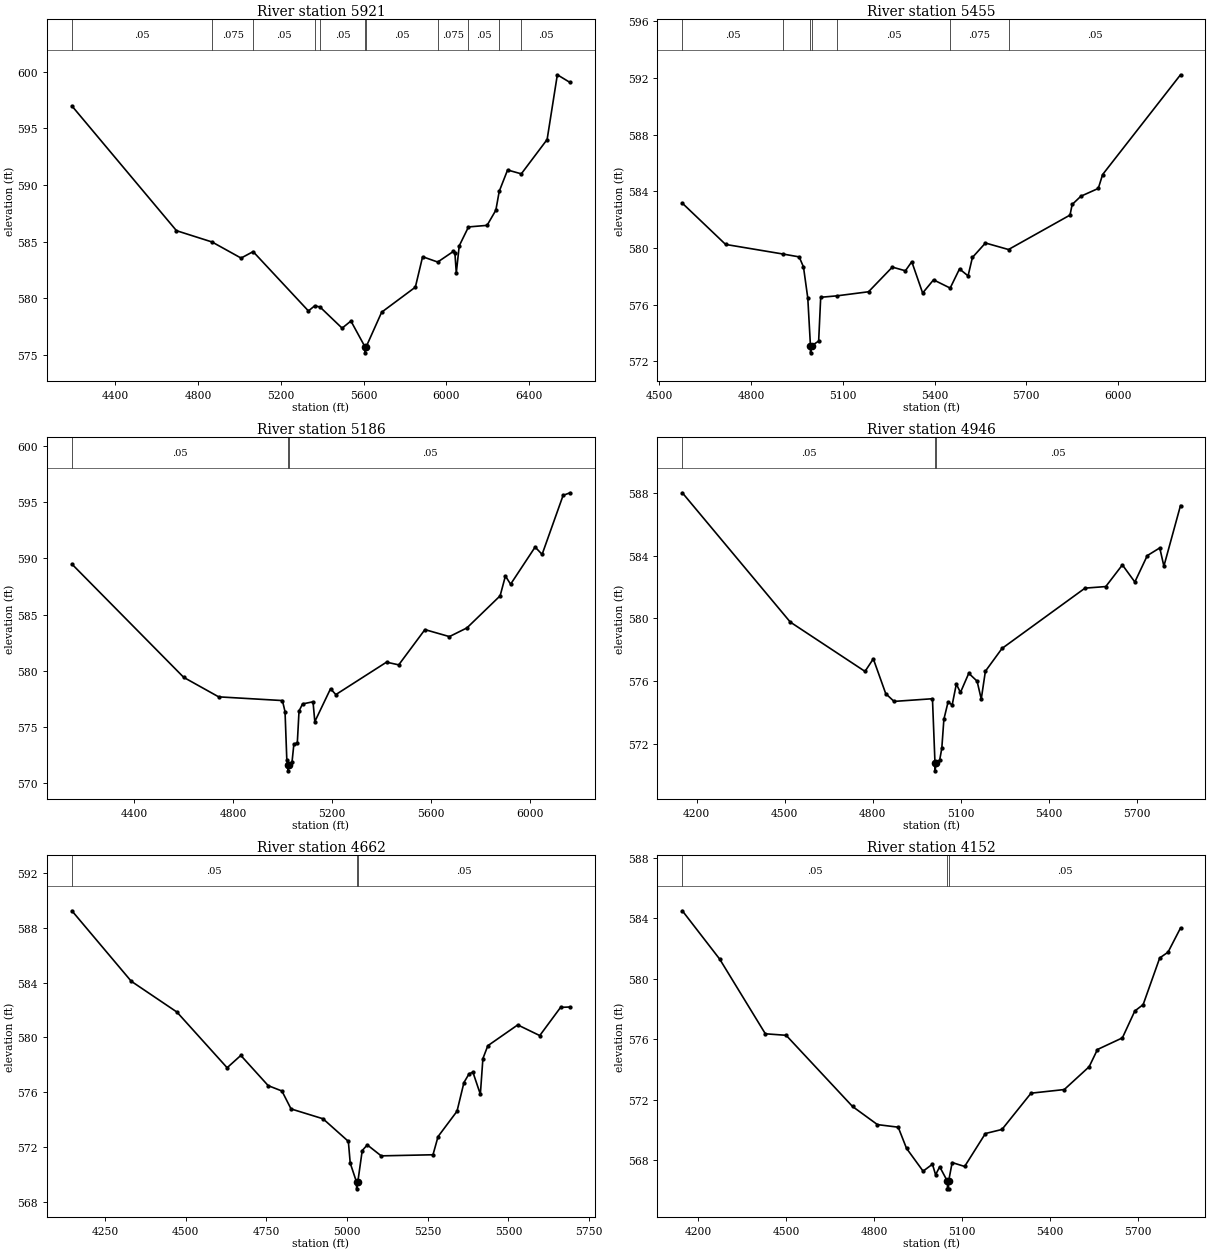
Type RM Length L Ch R = 1,5921,466,466,466
BEGIN DESCRIPTION:
Brushy Creek Tributary V 17.0
END DESCRIPTION:
XS GIS Cut Line= 3
      2613049.58      7024539.45      2612449.61      7024039.47
      2611250.32      7022940.13
#Sta/Elev= 30
  4190.3  596.98  4695.8  585.96  4867.9  584.96  5008.1  583.54  5066.3  584.11
  5333.6  578.87  5363.7  579.32  5389.6  579.22  5496.4  577.35  5539.0  577.98
  5607.9  575.67  5608.1  575.17  5611.9  575.67  5687.6  578.76  5850.4  580.97
  5885.5  583.66  5958.5  583.19  6034.3  584.13  6041.5  584.02  6048.3  582.23
  6062.5  584.62  6107.2  586.29  6197.1  586.43  6239.5  587.77  6255.9  589.44
  6296.2  591.32  6362.5  590.98  6487.3  594.01  6536.7  599.73  6598.2  599.05
#Mann=11,-1,0
  4190.3    0.05       0  4867.9   0.075       0  5066.3    0.05       0
  5363.7   0.075       0  5389.6    0.05       0  5607.9    0.07       0
  5611.9    0.05       0  5958.5   0.075       0  6107.2    0.05       0
  6255.9   0.075       0  6362.5    0.05       0
Bank Sta=5607.9,5611.9
Exp/Cntr=0.3,0.1

Type RM Length L Ch R = 1,5455,269,269,269
BEGIN DESCRIPTION:
Brushy Creek Tributary V 16.0
END DESCRIPTION:
XS GIS Cut Line= 3
      2612826.02      7023911.02      2612526.00      7023611.00
      2611626.04      7022811.03
#Sta/Elev= 30
  4575.7  583.17  4717.1  580.26  4905.3  579.58  4957.6  579.38  4971.7  578.67
  4985.8  576.47  4994.5  573.11  4994.7  572.61  4998.5  573.11  5021.3  573.44
  5028.0  576.53  5080.4  576.63  5184.4  576.92  5262.1  578.66  5304.8  578.40
  5325.7  579.04  5361.2  576.83  5396.8  577.76  5451.2  577.18  5481.7  578.53
  5509.7  578.04  5523.9  579.34  5566.5  580.36  5641.9  579.90  5842.9  582.33
  5850.0  583.08  5878.4  583.66  5935.3  584.21  5949.5  585.19  6204.1  592.23
#Mann=7,-1,0
  4575.7    0.05       0  4905.3   0.075       0  4994.5    0.07       0
  4998.5   0.075       0  5080.4    0.05       0  5451.2   0.075       0
  5641.9    0.05       0
Bank Sta=4994.5,4998.5
Exp/Cntr=0.3,0.1

Type RM Length L Ch R = 1,5186,240,240,240
BEGIN DESCRIPTION:
Brushy Creek Tributary V 15.0
END DESCRIPTION:
XS GIS Cut Line= 3
      2613175.99      7023960.99      2612576.00      7023361.00
      2611725.98      7022560.98
#Sta/Elev= 30
  4147.0  589.48  4599.5  579.42  4740.9  577.69  4998.9  577.36  5009.5  576.37
  5016.7  572.09  5021.6  571.62  5021.9  571.12  5025.6  571.62  5037.8  571.91
  5045.1  573.46  5059.2  573.62  5066.1  576.43  5080.3  577.06  5122.7  577.25
  5130.0  575.49  5193.6  578.41  5215.0  577.89  5420.1  580.77  5469.5  580.53
  5575.5  583.66  5674.6  583.04  5745.4  583.81  5879.8  586.66  5901.2  588.42
  5922.2  587.69  6021.4  590.99  6049.7  590.34  6134.7  595.58  6162.8  595.81
#Mann=3,-1,0
  4147.0    0.05       0  5021.6    0.03       0  5025.6    0.05       0
Bank Sta=5021.6,5025.6
Exp/Cntr=0.3,0.1

Type RM Length L Ch R = 1,4946,284,284,284
BEGIN DESCRIPTION:
Brushy Creek Tributary V 14.0
END DESCRIPTION:
XS GIS Cut Line= 3
      2613276.02      7023811.02      2612676.00      7023211.00
      2612075.99      7022610.99
#Sta/Elev= 30
  4151.4  588.00  4519.1  579.77  4773.7  576.63  4802.0  577.43  4844.4  575.21
  4872.7  574.72  5003.5  574.89  5012.1  570.80  5012.3  570.30  5016.1  570.80
  5028.2  571.00  5035.3  571.73  5042.4  573.58  5056.5  574.67  5070.7  574.50
  5084.8  575.82  5098.9  575.29  5127.2  576.51  5155.5  576.01  5169.7  574.87
  5183.8  576.64  5240.4  578.09  5523.2  581.93  5593.9  582.03  5650.5  583.41
  5692.9  582.32  5735.3  584.00  5777.8  584.49  5791.9  583.33  5848.5  587.19
#Mann=3,-1,0
  4151.4    0.05       0  5012.1    0.03       0  5016.1    0.05       0
Bank Sta=5012.1,5016.1
Exp/Cntr=0.3,0.1

Type RM Length L Ch R = 1,4662,510,510,510
BEGIN DESCRIPTION:
Brushy Creek Tributary V 13.0
END DESCRIPTION:
XS GIS Cut Line= 3
      2613526.03      7023711.03      2612926.00      7023111.00
      2612325.99      7022761.00
#Sta/Elev= 30
  4147.6  589.26  4331.5  584.11  4472.9  581.86  4628.5  577.79  4670.9  578.69
  4755.8  576.48  4798.2  576.09  4826.5  574.78  4925.5  574.06  5004.0  572.41
  5009.8  570.82  5029.3  569.44  5029.6  568.94  5033.3  569.44  5047.0  571.74
  5062.7  572.15  5105.7  571.35  5266.2  571.43  5281.9  572.76  5340.6  574.61
  5362.1  576.71  5377.8  577.34  5389.8  577.47  5412.9  575.85  5420.8  578.46
  5436.1  579.40  5528.7  580.92  5596.9  580.14  5661.4  582.20  5690.8  582.23
#Mann=3,-1,0
  4147.6    0.05       0  5029.3    0.03       0  5033.3    0.05       0
Bank Sta=5029.3,5033.3
Exp/Cntr=0.3,0.1

Type RM Length L Ch R = 1,4152,237,237,237
BEGIN DESCRIPTION:
Brushy Creek Tributary V 11.0
END DESCRIPTION:
XS GIS Cut Line= 3
      2613776.00      7023311.00      2613176.00      7022711.00
      2612575.97      7022110.97
#Sta/Elev= 30
  4146.9  584.49  4274.2  581.29  4429.7  576.35  4500.5  576.25  4726.7  571.54
  4811.6  570.34  4882.3  570.17  4910.6  568.77  4967.1  567.26  4999.0  567.72
  5009.6  567.02  5023.7  567.55  5050.0  566.59  5050.2  566.09  5053.7  566.09
  5054.0  566.59  5066.1  567.83  5108.6  567.57  5179.3  569.75  5235.8  570.02
  5334.8  572.42  5448.0  572.66  5532.8  574.17  5561.1  575.31  5646.0  576.08
  5688.4  577.86  5716.7  578.28  5773.2  581.37  5801.5  581.75  5844.0  583.35
#Mann=3,-1,0
  4146.9    0.05       0  5050.0    0.03       0  5054.0    0.05       0
Bank Sta=5050,5054
Exp/Cntr=0.3,0.1

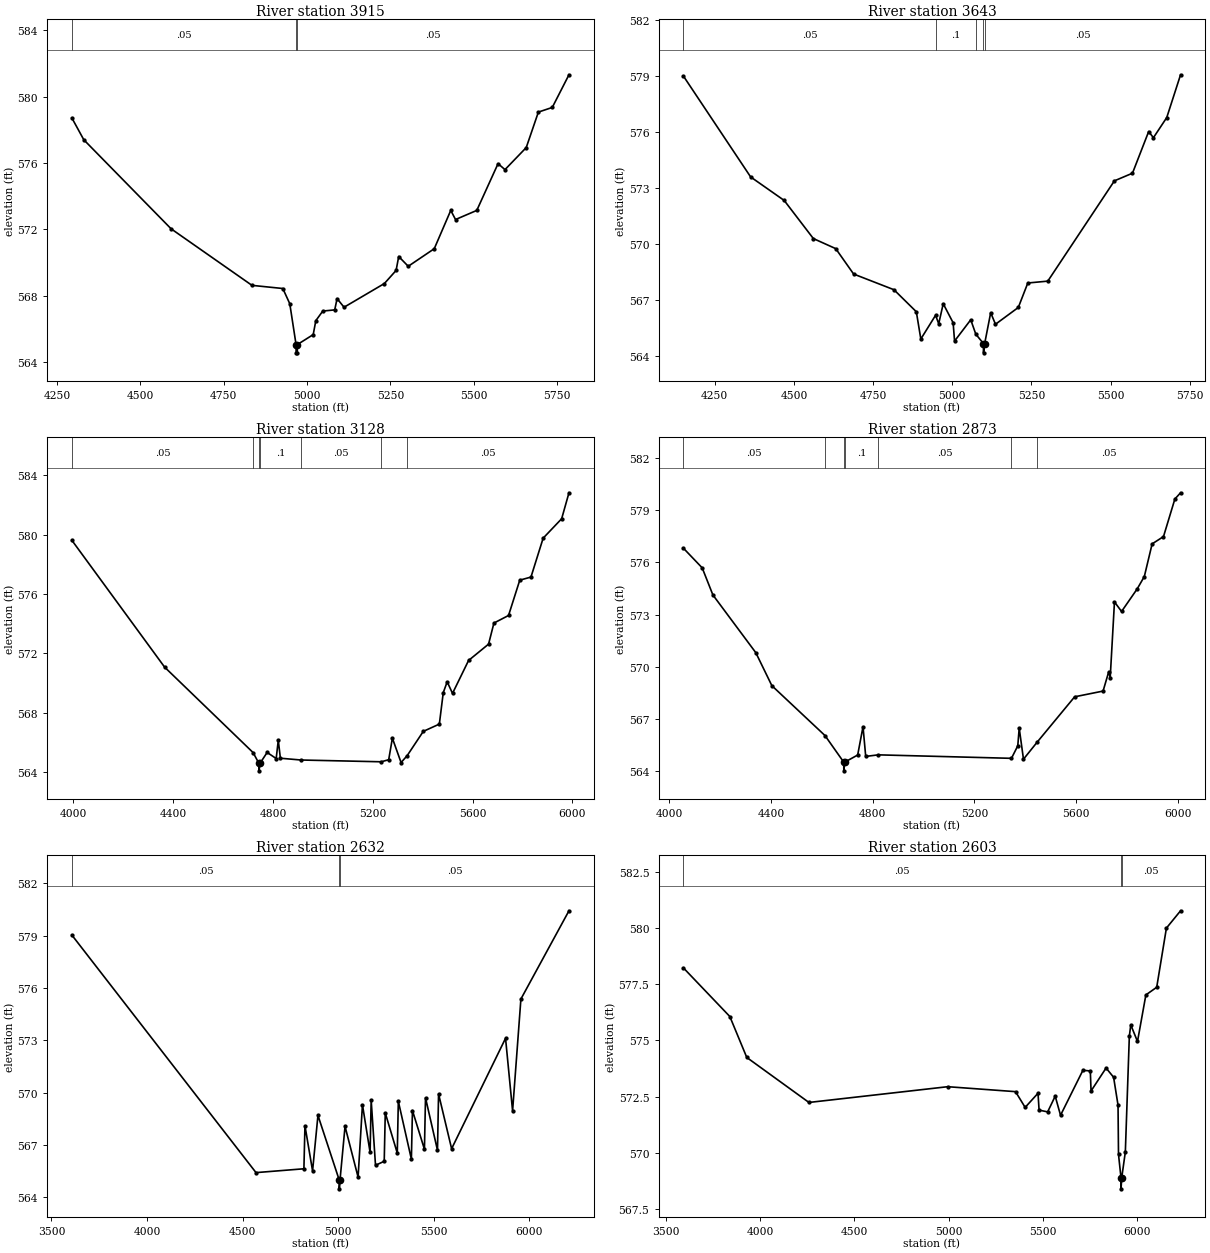
Type RM Length L Ch R = 1,3915,272,272,272
BEGIN DESCRIPTION:
Brushy Creek Tributary V 10.0
END DESCRIPTION:
XS GIS Cut Line= 3
      2613726.02      7023061.02      2613276.00      7022511.00
      2612675.99      7022010.99
#Sta/Elev= 30
  4294.2  578.72  4330.1  577.40  4592.1  572.03  4834.7  568.62  4927.3  568.43
  4948.2  567.51  4967.0  565.05  4967.2  564.55  4970.7  564.55  4971.0  565.05
  5018.5  565.65  5026.3  566.49  5047.2  567.07  5083.0  567.14  5090.1  567.82
  5111.0  567.30  5232.0  568.73  5267.2  569.52  5275.0  570.36  5303.6  569.77
  5381.7  570.83  5431.2  573.14  5445.5  572.59  5509.3  573.14  5573.1  575.96
  5593.9  575.60  5657.7  576.93  5694.1  579.07  5735.8  579.35  5785.9  581.32
#Mann=3,-1,0
  4294.2    0.05       0  4967.0    0.03       0  4971.0    0.05       0
Bank Sta=4967,4971
Exp/Cntr=0.3,0.1

Type RM Length L Ch R = 1,3643,515,515,515
BEGIN DESCRIPTION:
Brushy Creek Tributary V 9.0
END DESCRIPTION:
XS GIS Cut Line= 3
      2614026.02      7022911.02      2613426.00      7022311.00
      2612825.98      7021910.98
#Sta/Elev= 30
  4151.0  578.98  4363.2  573.58  4469.2  572.32  4561.2  570.28  4631.9  569.74
  4688.4  568.38  4815.7  567.54  4886.4  566.36  4900.6  564.90  4947.1  566.17
  4957.1  565.72  4971.3  566.79  5002.6  565.77  5007.1  564.79  5058.2  565.93
  5074.2  565.16  5098.2  564.66  5098.5  564.16  5102.2  564.66  5121.2  566.31
  5136.3  565.69  5208.4  566.59  5238.4  567.90  5301.5  568.00  5511.8  573.37
  5568.9  573.78  5620.0  576.01  5635.0  575.68  5677.1  576.76  5720.7  579.05
#Mann=5,-1,0
  4151.0    0.05       0  4947.1     0.1       0  5074.2    0.05       0
  5098.2    0.07       0  5102.2    0.05       0
Bank Sta=5098.2,5102.2
Exp/Cntr=0.3,0.1

Type RM Length L Ch R = 1,3128,255,255,255
BEGIN DESCRIPTION:
Brushy Creek Tributary V 7.0
END DESCRIPTION:
XS GIS Cut Line= 3
      2614226.01      7022861.03      2613776.00      7021961.00
      2612926.01      7021461.01
#Sta/Elev= 30
  3993.7  579.63  4365.5  571.08  4720.2  565.32  4743.6  564.59  4743.9  564.09
  4747.6  564.59  4776.4  565.33  4812.7  564.92  4821.1  566.15  4829.5  564.94
  4911.8  564.82  5233.9  564.70  5263.6  564.84  5278.4  566.29  5313.2  564.65
  5337.5  565.11  5402.3  566.75  5466.6  567.24  5482.3  569.36  5498.0  570.09
  5519.4  569.31  5583.8  571.53  5663.9  572.63  5685.3  574.05  5743.9  574.56
  5788.9  576.94  5833.8  577.15  5882.6  579.77  5956.8  581.08  5986.1  582.83
#Mann=7,-1,0
  3993.7    0.05       0  4720.2     0.1       0  4743.6    0.03       0
  4747.6     0.1       0  4911.8    0.05       0  5233.9     0.1       0
  5337.5    0.05       0
Bank Sta=4743.6,4747.6
Exp/Cntr=0.3,0.1

Type RM Length L Ch R = 1,2873,241,241,241
BEGIN DESCRIPTION:
Brushy Creek Tributary V 6.0
END DESCRIPTION:
XS GIS Cut Line= 3
      2614276.00      7022710.99      2613976.00      7021811.00
      2613076.00      7021361.00
#Sta/Elev= 30
  4055.5  576.82  4129.3  575.69  4171.4  574.13  4340.1  570.81  4403.3  568.91
  4612.2  566.04  4685.9  564.51  4686.2  564.01  4689.9  564.51  4740.7  564.92
  4761.7  566.55  4772.3  564.84  4821.9  564.93  5345.4  564.73  5370.3  565.45
  5375.9  566.47  5392.7  564.68  5447.0  565.67  5593.9  568.27  5705.7  568.60
  5728.1  569.72  5733.7  569.36  5750.5  573.73  5778.4  573.18  5839.9  574.48
  5867.9  575.19  5898.6  577.07  5943.3  577.49  5988.0  579.65  6010.4  580.01
#Mann=7,-1,0
  4055.5    0.05       0  4612.2     0.1       0  4685.9    0.03       0
  4689.9     0.1       0  4821.9    0.05       0  5345.4     0.1       0
  5447.0    0.05       0
Bank Sta=4685.9,4689.9
Exp/Cntr=0.3,0.1

Type RM Length L Ch R = 1,2632,29,29,29
BEGIN DESCRIPTION:
Mapping XS a550fc82
END DESCRIPTION:
XS GIS Cut Line= 6
      2614506.81      7022921.22      2614485.98      7021896.92
      2614430.42      7021830.95      2613499.87      7021389.98
      2613395.70      7021393.45      2613086.70      7021219.85
#Sta/Elev= 30
  3607.0  579.04  4570.6  565.42  4821.2  565.64  4826.7  568.11  4866.5  565.52
  4894.7  568.70  5006.1  564.99  5006.4  564.49  5010.1  564.99  5036.4  568.07
  5104.7  565.16  5127.5  569.31  5167.5  566.58  5173.1  569.58  5195.8  565.84
  5241.4  566.07  5246.9  568.84  5309.7  566.54  5315.2  569.51  5383.5  566.19
  5389.1  568.98  5451.8  566.76  5457.4  569.71  5520.1  566.70  5525.7  569.93
  5594.0  566.79  5876.2  573.12  5913.0  568.96  5956.5  575.37  6208.0  580.43
#Mann=3,-1,0
  3607.0    0.05       0  5006.1    0.03       0  5010.1    0.05       0
Bank Sta=5006.1,5010.1
Exp/Cntr=0.3,0.1

Type RM Length L Ch R = 1,2603,34,34,34
BEGIN DESCRIPTION:
Mapping XS 4b55cebc
END DESCRIPTION:
XS GIS Cut Line= 6
      2614531.12      7022907.34      2614534.59      7022028.87
      2614488.90      7021838.97      2613513.90      7021364.49
      2613374.87      7021358.73      2613093.61      7021178.17
#Sta/Elev= 30
  3592.3  578.22  3838.6  576.06  3928.6  574.24  4258.6  572.24  4995.2  572.94
  5355.1  572.72  5406.2  572.02  5474.5  572.65  5480.1  571.90  5525.6  571.82
  5565.7  572.52  5594.0  571.67  5712.8  573.67  5752.1  573.64  5756.0  572.75
  5835.7  573.77  5875.7  573.36  5899.2  572.12  5901.7  569.93  5914.9  568.90
  5915.1  568.40  5918.9  568.90  5938.0  570.04  5959.2  575.18  5966.8  575.69
  6002.5  574.95  6047.0  577.02  6104.5  577.36  6156.0  579.99  6231.1  580.76
#Mann=3,-1,0
  3592.3    0.05       0  5914.9    0.03       0  5918.9    0.05       0
Bank Sta=5914.9,5918.9
Exp/Cntr=0.3,0.1

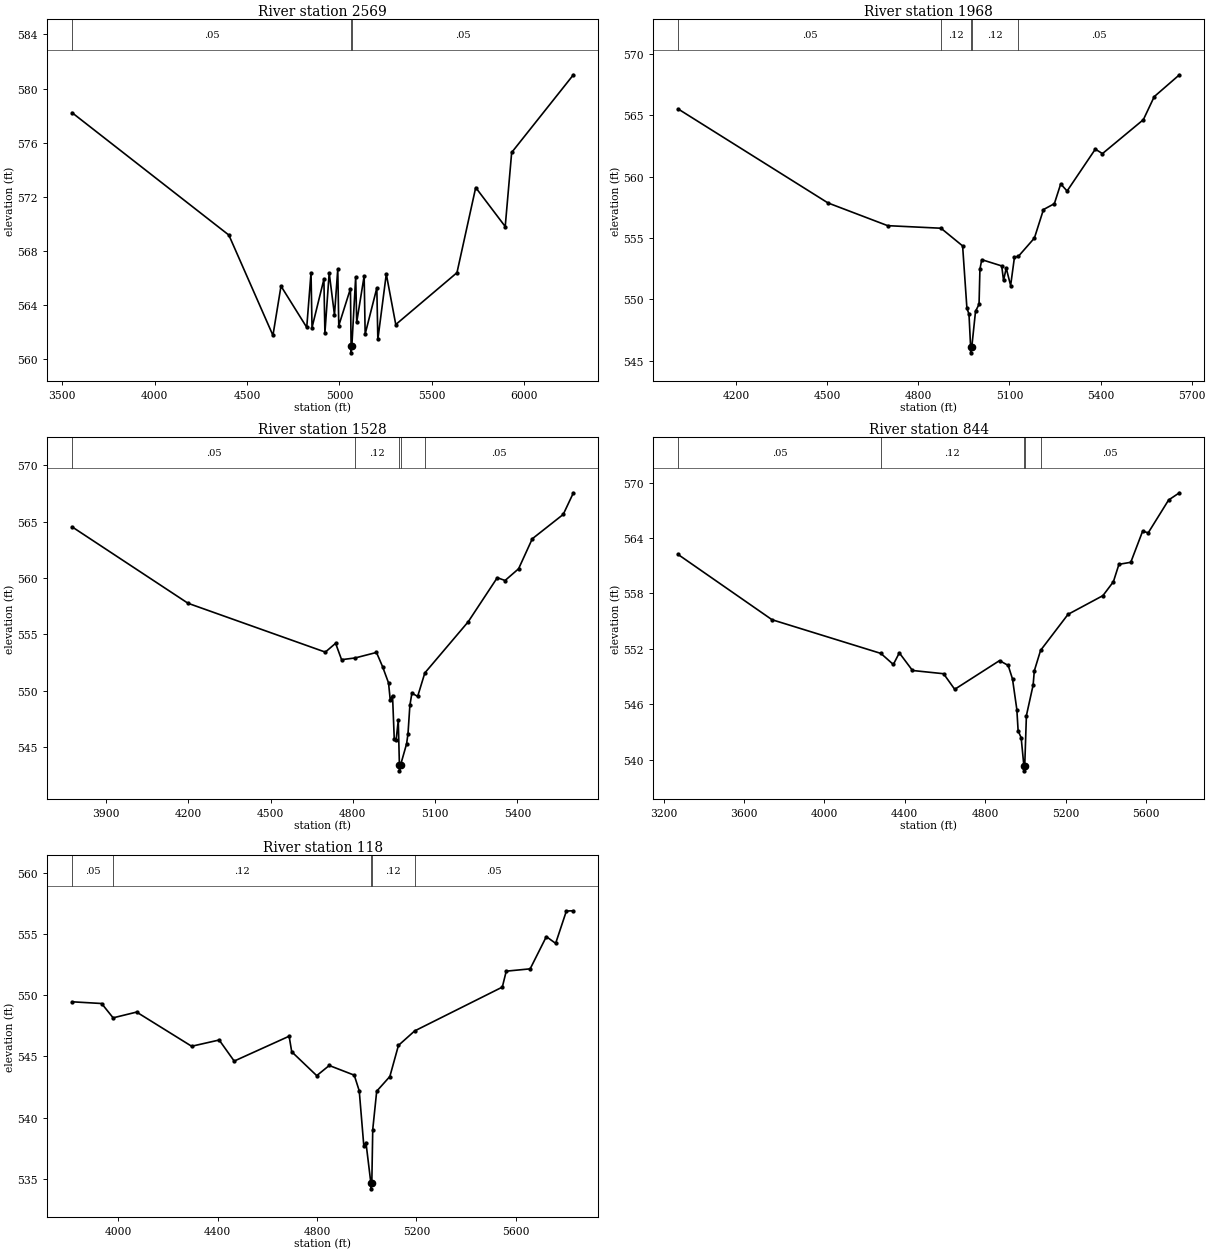
Type RM Length L Ch R = 1,2569,601,601,601
BEGIN DESCRIPTION:
Mapping XS 283e202e
END DESCRIPTION:
XS GIS Cut Line= 6
      2614535.67      7022909.73      2614576.05      7021946.95
      2614542.03      7021837.23      2614446.19      7021764.32
      2613400.26      7021309.03      2613105.08      7021083.31
#Sta/Elev= 30
  3553.1  578.22  4401.7  569.18  4640.3  561.77  4683.9  565.41  4823.2  562.36
  4846.4  566.40  4851.8  562.35  4916.0  565.91  4921.5  561.94  4944.7  566.39
  4973.3  563.28  4991.1  566.66  4996.6  562.49  5059.7  565.22  5063.3  560.98
  5063.5  560.48  5067.3  560.98  5088.1  566.10  5093.6  562.74  5133.9  566.16
  5139.4  561.87  5202.5  565.27  5208.0  561.47  5253.7  566.30  5305.0  562.57
  5636.2  566.40  5737.6  572.69  5897.3  569.81  5932.2  575.28  6266.4  581.02
#Mann=3,-1,0
  3553.1    0.05       0  5063.3    0.03       0  5067.3    0.05       0
Bank Sta=5063.3,5067.3
Exp/Cntr=0.3,0.1

Type RM Length L Ch R = 1,1968,440,440,440
BEGIN DESCRIPTION:
Brushy Creek Tributary V 2.0
END DESCRIPTION:
XS GIS Cut Line= 4
      2614707.03      7022103.72      2614750.43      7021413.66
      2614531.81      7021208.69      2613987.46      7020835.84
#Sta/Elev= 30
  4008.9  565.52  4502.6  557.86  4699.1  556.01  4874.7  555.80  4945.9  554.36
  4960.0  549.30  4966.9  548.79  4972.2  546.15  4972.4  545.65  4976.2  546.15
  4988.4  549.03  5000.0  549.61  5002.9  552.46  5008.9  553.24  5074.6  552.73
  5080.7  551.55  5089.5  552.55  5104.0  551.13  5116.6  553.44  5129.5  553.51
  5182.3  555.00  5212.1  557.32  5248.0  557.80  5268.9  559.41  5289.9  558.83
  5382.8  562.24  5406.4  561.88  5541.0  564.64  5576.9  566.52  5659.8  568.30
#Mann=5,-1,0
  4008.9    0.05       0  4874.7    0.12       0  4972.2    0.07       0
  4976.2    0.12       0  5129.5    0.05       0
Bank Sta=4972.2,4976.2
Exp/Cntr=0.3,0.1

Type RM Length L Ch R = 1,1528,684,684,684
BEGIN DESCRIPTION:
Mapping XS 5e001cfb
END DESCRIPTION:
XS GIS Cut Line= 4
      2614763.45      7022077.72      2614929.93      7021118.31
      2614783.72      7020920.36      2614336.68      7020508.04
#Sta/Elev= 30
  3776.3  564.54  4199.2  557.76  4699.7  553.43  4737.2  554.21  4759.0  552.76
  4808.2  552.91  4886.3  553.40  4908.3  552.15  4930.2  550.70  4936.4  549.20
  4944.8  549.58  4951.0  545.76  4958.0  545.66  4965.7  547.37  4969.9  543.40
  4970.1  542.90  4973.9  543.40  4996.1  545.30  5001.2  546.20  5008.0  548.70
  5015.4  549.79  5036.4  549.50  5062.5  551.58  5220.7  556.12  5326.7  560.03
  5355.1  559.78  5404.4  560.82  5454.3  563.48  5567.1  565.64  5604.3  567.56
#Mann=5,-1,0
  3776.3    0.05       0  4808.2    0.12       0  4969.9    0.07       0
  4973.9    0.12       0  5062.5    0.05       0
Bank Sta=4969.9,4973.9
Exp/Cntr=0.3,0.1

Type RM Length L Ch R = 1,844,726,726,726
BEGIN DESCRIPTION:
Mapping XS cadf7716
END DESCRIPTION:
XS GIS Cut Line= 5
      2614845.91      7022012.62      2615412.67      7020966.92
      2615369.66      7020712.02      2615226.43      7020464.63
      2614580.38      7020063.56
#Sta/Elev= 30
  3272.2  562.22  3739.6  555.15  4281.2  551.50  4343.2  550.30  4372.9  551.56
  4438.5  549.65  4593.1  549.30  4648.5  547.61  4871.4  550.72  4914.5  550.20
  4936.0  548.73  4957.6  545.42  4964.0  543.11  4979.1  542.37  4992.8  539.28
  4993.1  538.78  4996.8  539.28  5005.2  544.77  5038.6  548.07  5044.5  549.61
  5075.7  551.83  5212.2  555.73  5385.8  557.76  5437.8  559.26  5465.5  561.15
  5524.4  561.37  5583.2  564.73  5611.4  564.57  5712.7  568.12  5766.4  568.90
#Mann=5,-1,0
  3272.2    0.05       0  4281.2    0.12       0  4992.8    0.07       0
  4996.8    0.12       0  5075.7    0.05       0
Bank Sta=4992.8,4996.8
Exp/Cntr=0.3,0.1

Type RM Length L Ch R = 1,118,0,0,0
BEGIN DESCRIPTION:
Mapping XS c8d9e49b
END DESCRIPTION:
XS GIS Cut Line= 3
      2615703.87      7021339.15      2615834.07      7020169.49
      2615104.91      7019752.83
#Sta/Elev= 30
  3814.6  549.45  3933.5  549.31  3979.8  548.14  4074.3  548.61  4295.7  545.82
  4406.4  546.33  4466.8  544.61  4687.8  546.64  4698.2  545.37  4798.8  543.42
  4849.1  544.25  4949.7  543.46  4969.8  542.18  4988.2  537.68  4996.8  537.96
  5016.4  534.68  5016.6  534.18  5020.4  534.68  5024.1  539.02  5040.0  542.15
  5092.9  543.35  5127.5  545.89  5192.6  547.07  5545.3  550.65  5561.1  551.95
  5657.3  552.14  5722.4  554.77  5759.8  554.22  5803.0  556.86  5831.3  556.88
#Mann=5,-1,0
  3814.6    0.05       0  3979.8    0.12       0  5016.4    0.07       0
  5020.4    0.12       0  5192.6    0.05       0
Bank Sta=5016.4,5020.4
Exp/Cntr=0.3,0.1

Chan Stop Cuts=-1