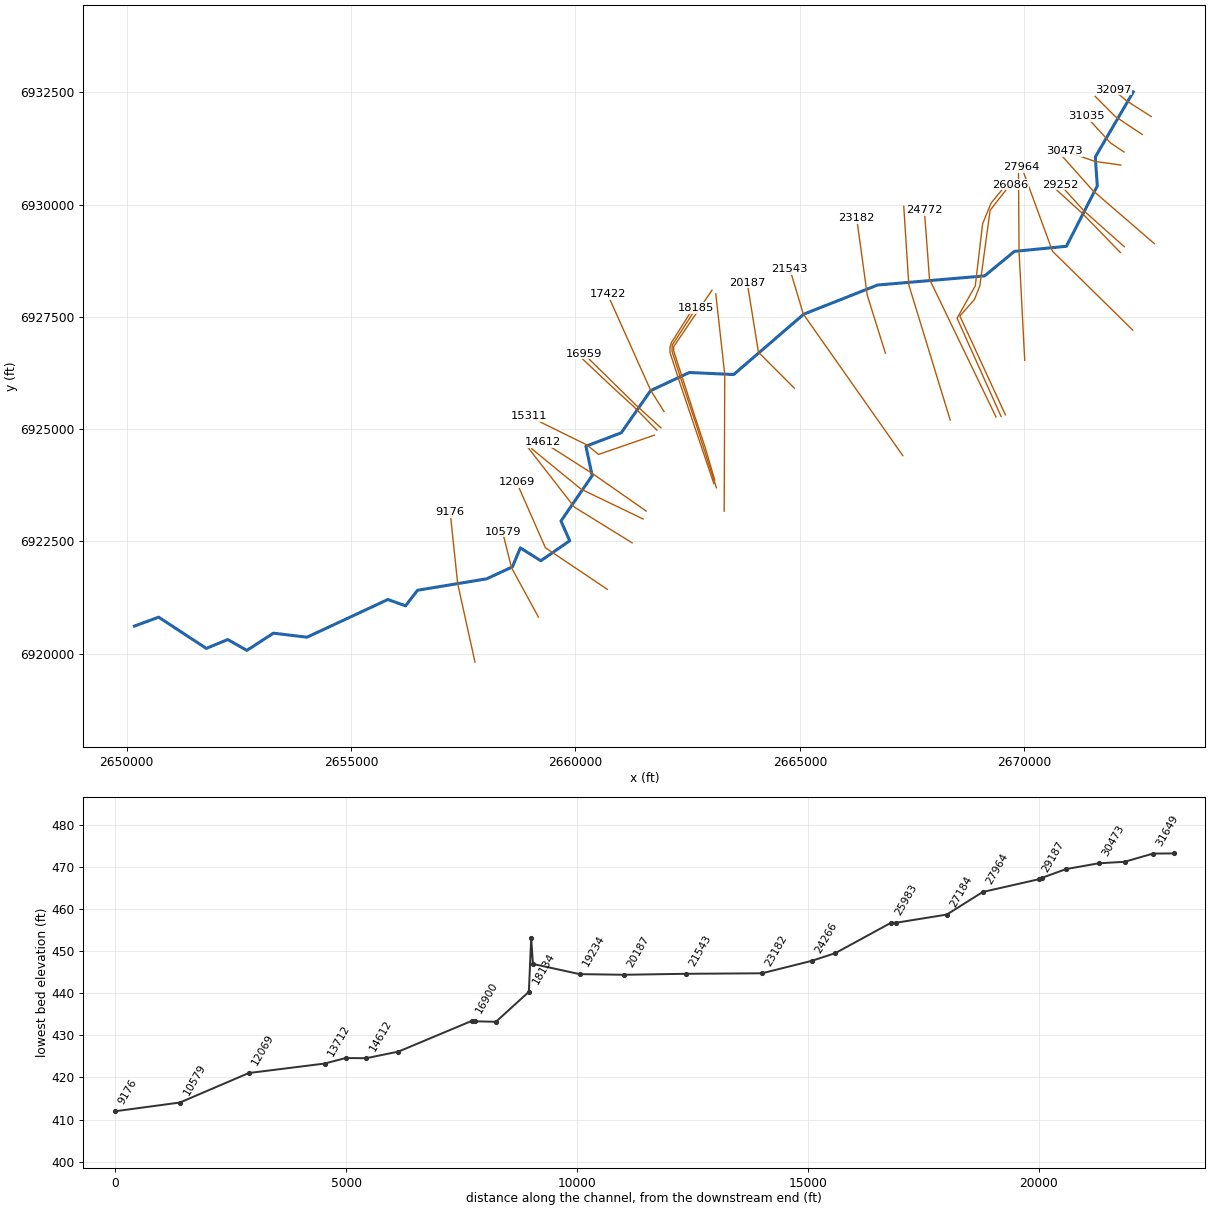
--- Eagans Branch.prj (project) ---

Proj Title=Eagans Branch Base Level Engineering
Current Plan=p01
Default Exp/Contr=0.3,0.1
English Units
Geom File=g01
Flow File=f01
Plan File=p01
Y Axis Title=Elevation
X Axis Title(PF)=Main Channel Distance
X Axis Title(XS)=Station
BEGIN DESCRIPTION:
Eagans Branch
END DESCRIPTION:
DSS Export Rating Curves= 0
DSS Export Rating Curve Sorted= 0
DSS Export Volume Flow Curves= 0
DXF OffsetX= 0
DXF OffsetY= 0
DXF ScaleX= 1
DXF ScaleY= 10

--- Eagans Branch.p01 (plan) ---

Plan Title=Multiple Run
Short Identifier=Multiple
Geom File=g01
Flow File=f01
Subcritical Flow
K Sum by GR= 0
Std Step Tol= 0.01
Critical Tol= 0.01
Num of Std Step Trials= 20
Max Error Tol= 0.3
Flow Tol Ratio= 0.001
Split Flow NTrial= 30
Split Flow Tol= 0.02
Split Flow Ratio= 0.02
Log Output Level= 0
Friction Slope Method= 1
Unsteady Friction Slope Method= 2
Unsteady Bridges Friction Slope Method= 1
Parabolic Critical Depth
Global Vel Dist=  1 , 1 , 1
Global Log Level= 0
CheckData=True
Encroach Param= -1, 0, 0, 0
BEGIN DESCRIPTION:
Multiple Run
END DESCRIPTION:

--- Eagans Branch.f01 (steady flow) ---

Flow Title=Multiple
Program Version=4.10
Number of Profiles= 7
Profile Names=10-year,25-year,50-year,1pct_min,100-year,1pct_plu,500-year
River Rch & RM=Eagans Branch,Reach-1         ,32097
     528     701     840     499     996    1988    1400
River Rch & RM=Eagans Branch,Reach-1         ,31035
     843    1147    1396     842    1679    3350    2430
River Rch & RM=Eagans Branch,Reach-1         ,27964
     863    1180    1439     870    1736    3463    2524
River Rch & RM=Eagans Branch,Reach-1         ,27184
    1194    1661    2050    1252    2499    4985    3714
River Rch & RM=Eagans Branch,Reach-1         ,24772
    1378    1919    2370    1446    2886    5758    4283
River Rch & RM=Eagans Branch,Reach-1         ,19234
    1455    2029    2510    1533    3060    6105    4553
River Rch & RM=Eagans Branch,Reach-1         ,18134
    1652    2321    2883    1770    3531    7045    5301
River Rch & RM=Eagans Branch,Reach-1         ,14612
    1940    2745    3427    2113    4215    8411    6384
River Rch & RM=Eagans Branch,Reach-1         ,13712
    2005    2839    3547    2187    4364    8708    6615
River Rch & RM=Eagans Branch,Reach-1         ,10579
    2358    3363    4221    2614    5216   10407    7975
River Rch & RM=Eagans Branch,Reach-1         ,9176
    2484    3539    4440    2747    5481   10937    8366
River Rch & RM=Eagans Branch,Reach-1         ,4441
    2607    3717    4663    2885    5757   11486    8785
Boundary for River Rch & Prof#=Eagans Branch,Reach-1         , 1
Up Type= 0
Dn Type= 3
Dn Slope=0.00167
Boundary for River Rch & Prof#=Eagans Branch,Reach-1         , 2
Up Type= 0
Dn Type= 3
Dn Slope=0.00167
Boundary for River Rch & Prof#=Eagans Branch,Reach-1         , 3
Up Type= 0
Dn Type= 3
Dn Slope=0.00167
Boundary for River Rch & Prof#=Eagans Branch,Reach-1         , 4
Up Type= 0
Dn Type= 3
Dn Slope=0.00167
Boundary for River Rch & Prof#=Eagans Branch,Reach-1         , 5
Up Type= 0
Dn Type= 3
Dn Slope=0.00167
Boundary for River Rch & Prof#=Eagans Branch,Reach-1         , 6
Up Type= 0
Dn Type= 3
Dn Slope=0.00167
Boundary for River Rch & Prof#=Eagans Branch,Reach-1         , 7
Up Type= 0
Dn Type= 3
Dn Slope=0.00167
DSS Import GetInterval= 0
DSS Import GetPeak= 0
DSS Import FillOption= 0

--- Eagans Branch.g01 (geometry) ---

Geom Title=Existing Conditions
Program Version=4.10

River Reach=Eagans Branch   ,Reach-1
Reach XY= 30
        2672426.        6932511.      2671579.54      6931059.54
      2671624.38      6930417.03      2670935.81      6929071.51
      2669777.22      6928957.56      2669115.52      6928411.93
      2666727.63      6928207.87      2665084.48      6927558.37
      2663524.54      6926214.54      2662536.43      6926259.95
      2661673.57      6925855.48      2661020.42      6924916.58
      2660233.32      6924617.38      2660372.73      6923962.36
      2659677.04      6922950.57      2659872.96      6922512.42
      2659228.28      6922066.08      2658772.31      6922353.35
      2658596.47      6921930.65      2658024.52      6921664.61
      2656481.85      6921408.94      2656215.72      6921061.98
      2655822.59      6921203.23      2654020.03      6920363.14
      2653272.59      6920453.19      2652679.29      6920069.06
      2652255.62      6920311.31      2651777.11      6920114.42
       2650715.4      6920810.12        2650176.        6920611.

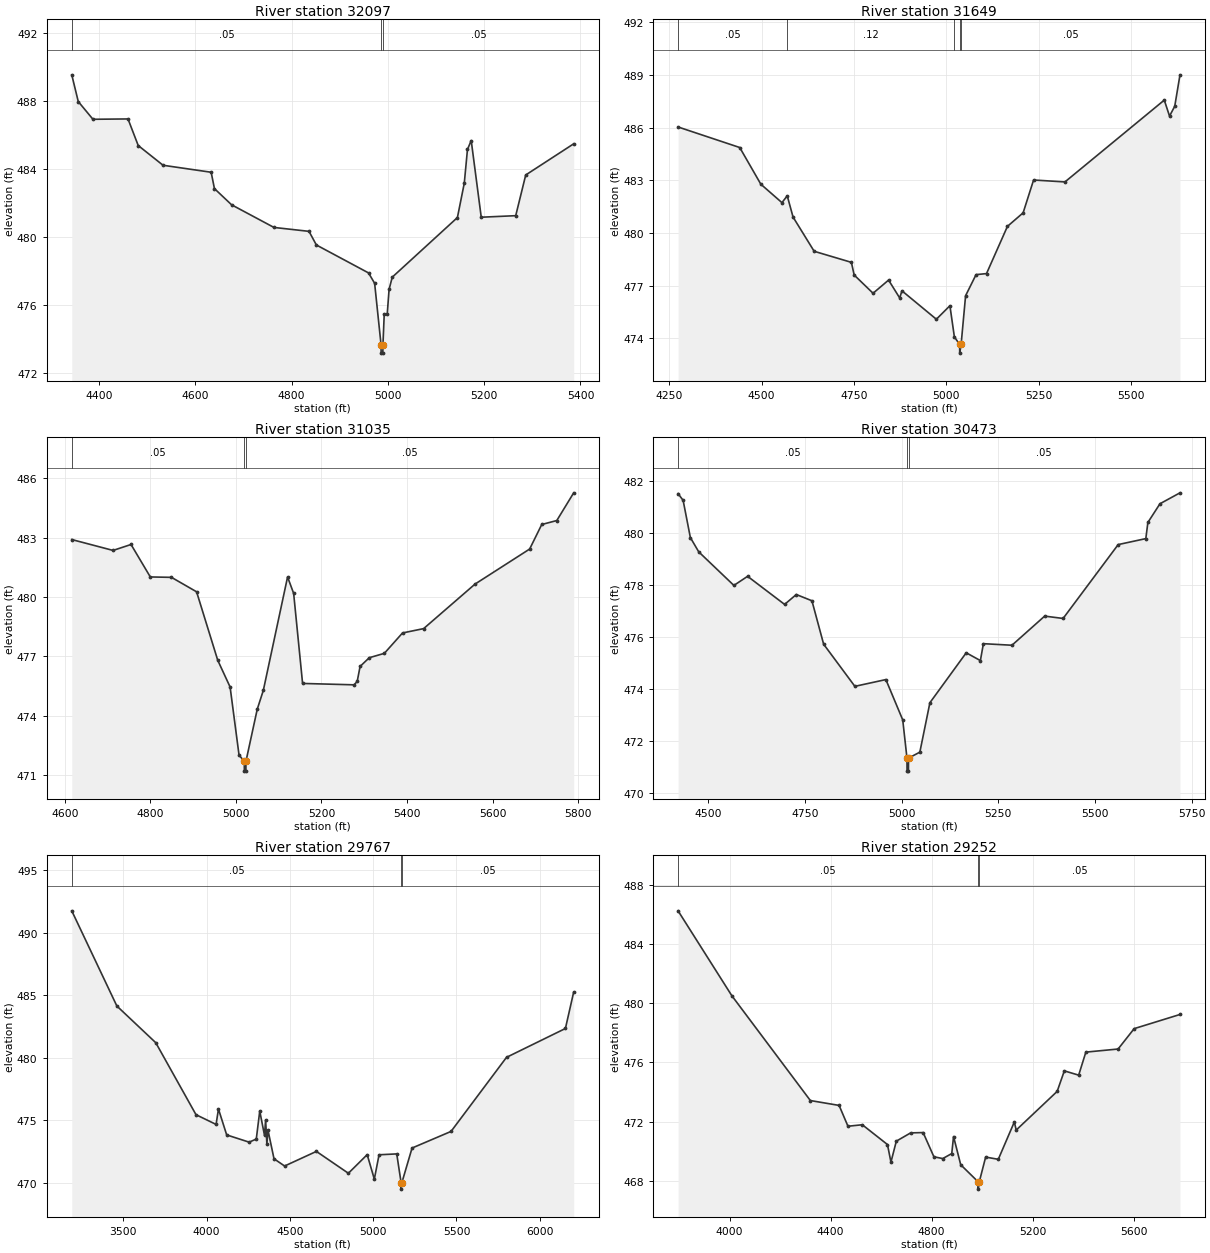
Type RM Length L Ch R = 1 ,32097   ,448,448,448
BEGIN DESCRIPTION:
Eagans Branch 62.0
END DESCRIPTION:
XS GIS Cut Line= 3
      2672825.97      6931961.02        2672276.        6932311.
        2671976.        6932561.
#Sta/Elev= 30
  4343.5  489.53    4357  487.96  4387.5  486.92  4460.3  486.94  4481.5  485.38
  4533.1  484.22    4633  483.81  4639.8  482.85  4675.4   481.9  4763.4  480.57
  4836.2  480.34  4851.5  479.54  4959.8   477.9  4972.5  477.29  4985.8  473.69
    4986  473.19  4989.5  473.19  4989.8  473.69  4992.4  475.46  4998.6  475.46
  5002.5  476.93  5009.1  477.65  5144.4  481.15  5158.7  483.17  5165.3  485.15
  5173.1  485.67  5193.9  481.17  5265.5  481.26  5286.3  483.65  5385.9  485.48
#Mann= 3 ,-1 , 0
  4343.5     .05       0  4985.8     .03       0  4989.8     .05       0
Bank Sta=4985.8,4989.8
XS Rating Curve= 0 ,0
Exp/Cntr=0.3,0.1

Type RM Length L Ch R = 1 ,31649   ,614,614,614
BEGIN DESCRIPTION:
Eagans Branch 61.0
END DESCRIPTION:
XS GIS Cut Line= 3
      2672626.04      6931560.97        2672026.        6931961.
      2671575.97      6932411.03
#Sta/Elev= 30
  4274.2  486.03    4441  484.86  4498.1  482.77  4555.2  481.72  4569.5  482.11
  4585.2   480.9  4642.3  478.95    4743  478.32  4750.5   477.6  4801.6  476.56
  4843.6  477.31  4873.7  476.29  4879.7   476.7  4972.8  475.08  5009.5  475.85
  5021.6  474.07  5035.8  473.65    5036  473.15  5039.8  473.65  5051.9  476.42
  5080.2  477.62  5108.5  477.68  5165.1  480.37  5207.5  481.14  5235.8  483.01
  5320.6   482.9  5589.3  487.56  5603.5  486.65  5617.6  487.21  5631.8     489
#Mann= 5 ,-1 , 0
  4274.2     .05       0  4569.5     .12       0  5021.6     .05       0
  5035.8     .07       0  5039.8     .05       0
Bank Sta=5035.8,5039.8
XS Rating Curve= 0 ,0
Exp/Cntr=0.3,0.1

Type RM Length L Ch R = 1 ,31035   ,562,562,562
BEGIN DESCRIPTION:
Eagans Branch 60.0
END DESCRIPTION:
XS GIS Cut Line= 3
      2672220.07      6931171.57      2671920.07      6931371.57
      2671370.54      6931971.06
#Sta/Elev= 30
    4616   482.9  4712.6  482.35  4754.6  482.65  4799.7  481.01  4849.2  480.99
  4907.9  480.26  4957.4   476.8  4986.3  475.45  5007.2  472.01  5019.4   471.7
  5019.7   471.2  5023.2   471.2  5023.4   471.7  5049.8  474.33    5064  475.28
  5120.7  481.01  5134.9  480.18  5155.8  475.63  5276.1  475.56  5283.5  475.73
  5290.3  476.49  5311.8  476.93    5347  477.15  5389.5  478.18  5438.9   478.4
  5559.1  480.65  5686.8  482.42  5715.1  483.66  5750.3  483.86  5789.8  485.26
#Mann= 3 ,-1 , 0
    4616     .05       0  5019.4     .04       0  5023.4     .05       0
Bank Sta=5019.4,5023.4
XS Rating Curve= 0 ,0
Exp/Cntr=0.3,0.1

Type RM Length L Ch R = 1 ,30473   ,706,706,706
BEGIN DESCRIPTION:
Eagans Branch 58.0
END DESCRIPTION:
XS GIS Cut Line= 3
      2672148.98      6930881.13      2671575.92      6930961.03
      2670894.63      6931193.63
#Sta/Elev= 30
  4421.4  481.51  4434.5  481.25  4453.2  479.82  4474.9  479.27  4565.8  477.98
  4601.3  478.33    4697  477.25  4727.3  477.63  4767.7  477.39    4798  475.72
  4878.8   474.1    4959  474.36  5002.6  472.81  5013.6  471.34  5013.8  470.84
  5017.3  470.84  5017.6  471.34  5046.9  471.57  5072.9  473.47  5166.9  475.39
  5203.5  475.09  5211.3  475.74  5285.2  475.68  5369.8   476.8  5417.5  476.71
    5560  479.55  5631.5  479.78  5636.8   480.4  5668.1  481.12  5719.9  481.54
#Mann= 3 ,-1 , 0
  4421.4     .05       0  5013.6     .04       0  5017.6     .05       0
Bank Sta=5013.6,5017.6
XS Rating Curve= 0 ,0
Exp/Cntr=0.3,0.1

Type RM Length L Ch R = 1 ,29767   ,515,515,515
BEGIN DESCRIPTION:
Eagans Branch 57.0
END DESCRIPTION:
XS GIS Cut Line= 3
      2672896.46      6929129.46        2671526.        6930311.
      2670726.02      6931210.98
#Sta/Elev= 30
  3190.3  491.75  3461.1  484.13  3694.8  481.19  3936.2  475.43  4056.8  474.65
  4071.1  475.88  4120.5  473.81  4255.4  473.23  4298.2  473.48    4319  475.72
  4347.6  473.77  4354.2  475.01  4361.8  473.08  4368.4  474.19  4404.6   471.9
  4468.2  471.32  4659.1  472.49  4851.1  470.74  4964.1  472.23  5006.9  470.27
  5035.3  472.22  5141.5  472.29  5167.9  469.97  5168.2  469.47  5171.9  469.97
  5233.5  472.76  5467.6  474.09  5800.5  480.02  6154.2  482.33  6203.9  485.25
#Mann= 3 ,-1 , 0
  3190.3     .05       0  5167.9     .03       0  5171.9     .05       0
Bank Sta=5167.9,5171.9
XS Rating Curve= 0 ,0
Exp/Cntr=0.3,0.1

Type RM Length L Ch R = 1 ,29252   ,65,65,65
BEGIN DESCRIPTION:
Eagans Branch 56.0
END DESCRIPTION:
XS GIS Cut Line= 3
      2672226.03      6929060.97        2671326.        6929861.
      2670800.16      6930441.69
#Sta/Elev= 30
  3795.8  486.27  4008.7  480.52  4319.7  473.42  4433.5  473.09  4468.6  471.68
  4525.4  471.78    4625  470.44  4638.8  469.25  4660.1  470.67  4716.9  471.23
  4766.3  471.25  4808.9  469.61    4844  469.49  4879.6  469.83  4886.7  470.98
  4915.1  469.07  4983.8  467.92  4984.4  467.42  4988.7  467.92  5013.8  469.59
  5063.9  469.44  5127.4  471.97  5134.8  471.42    5297  474.04  5325.4  475.43
  5382.2  475.14  5410.6   476.7  5538.3  476.91  5601.9  478.29  5783.4  479.25
#Mann= 3 ,-1 , 0
  3795.8     .05       0  4983.8     .03       0  4988.7     .05       0
Bank Sta=4983.8,4988.7
XS Rating Curve= 0 ,0
Exp/Cntr=0.3,0.1

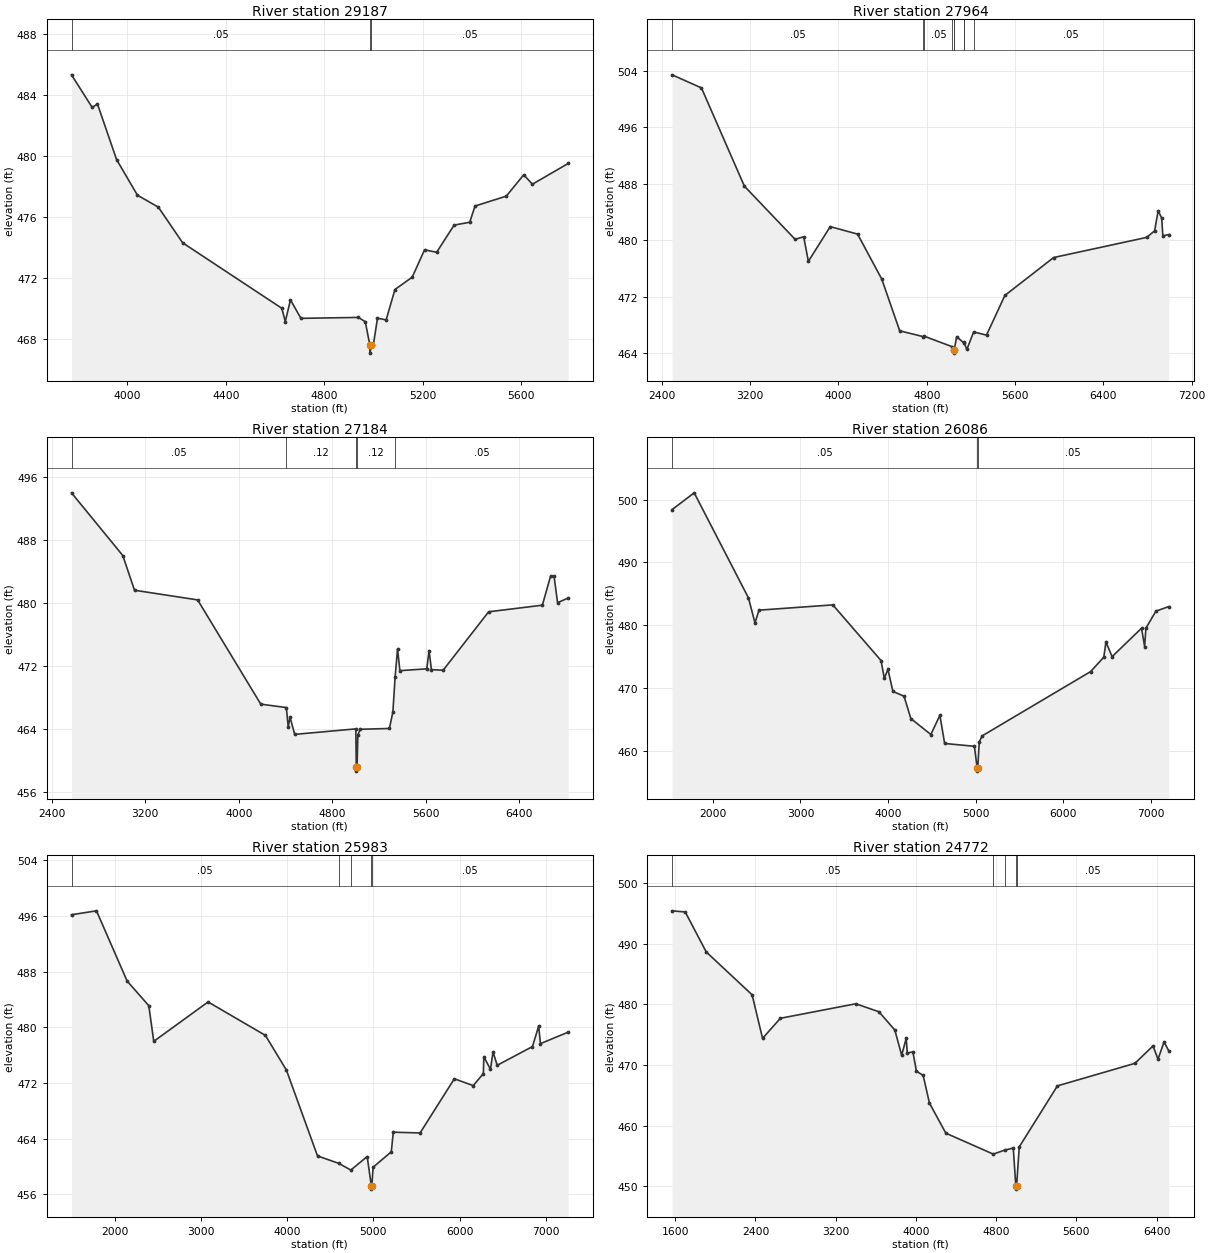
Type RM Length L Ch R = 1 ,29187   ,1223,1223,1223
BEGIN DESCRIPTION:
Eagans Branch 55.0
END DESCRIPTION:
XS GIS Cut Line= 3
      2672137.56      6928933.42      2671281.71      6929813.35
      2670695.64      6930346.07
#Sta/Elev= 30
  3772.5  485.32  3856.7  483.18    3878  483.41  3955.7  479.77  4040.6  477.43
  4125.5  476.65  4224.5  474.31  4627.6  470.02  4641.7  469.15  4662.8  470.57
  4705.3  469.36  4938.8  469.42  4967.1  469.14  4985.8  467.58  4986.4  467.08
  4990.7  467.58    5000  467.64  5016.6  469.37  5051.8  469.26  5087.6  471.25
  5157.9  472.06  5207.9  473.85  5257.2  473.69  5328.2  475.47  5391.7  475.66
  5413.1  476.72  5540.3  477.37  5611.3  478.77  5646.4  478.15    5792  479.51
#Mann= 3 ,-1 , 0
  3772.5     .05       0  4985.8     .03       0  4990.7     .05       0
Bank Sta=4985.8,4990.7
XS Rating Curve= 0 ,0
Exp/Cntr=0.3,0.1

Type RM Length L Ch R = 1 ,27964   ,780,780,780
BEGIN DESCRIPTION:
Eagans Branch 54.0
END DESCRIPTION:
XS GIS Cut Line= 3
      2672414.58      6927203.09        2670626.        6928961.
      2669940.81      6930831.09
#Sta/Elev= 30
  2492.3  503.46  2758.5  501.61  3147.5  487.69  3607.1  480.16  3684.8  480.52
  3727.3  477.04  3925.3  481.96  4172.9   480.9    4392  474.53  4554.6   467.2
  4767.4  466.38  4778.9  466.42  5030.3  464.95  5043.4  464.54    5044  464.04
  5048.5  464.54  5071.1  466.37  5133.7  465.51  5136.8  465.59  5162.6  464.56
  5224.6  467.04  5340.9  466.59  5507.4  472.21  5949.1  477.58  6791.2  480.43
  6863.9  481.36  6895.9  484.21  6927.8  483.17  6938.5  480.67  6991.8  480.83
#Mann= 9 ,-1 , 0
  2492.3     .05       0  4767.4     .12       0  4778.9     .05       0
  5030.3     .12       0  5043.4     .04       0  5048.5     .12       0
  5133.7     .05       0  5136.8     .12       0  5224.6     .05       0
Bank Sta=5043.4,5048.5
XS Rating Curve= 0 ,0
Exp/Cntr=0.3,0.1

Type RM Length L Ch R = 1 ,27184   ,1098,1098,1098
BEGIN DESCRIPTION:
Eagans Branch 52.0
END DESCRIPTION:
XS GIS Cut Line= 3
      2670007.53      6926532.26      2669880.97      6928961.06
      2669868.65      6930782.22
#Sta/Elev= 30
  2567.9  494.04  3007.2  486.07  3107.4  481.66  3648.1  480.43  4188.8  467.18
  4407.6  466.75  4423.6  464.33  4439.2  465.52  4479.2  463.34  5002.5  464.04
  5006.6  459.17  5007.7  458.67  5013.2  459.17  5019.9  463.28  5039.9  463.99
  5289.9  464.09  5319.9  466.18  5338.8  470.57  5359.9   474.2  5379.9  471.44
  5609.9  471.67  5629.9  473.99    5650  471.57    5750  471.49    6140  478.92
    6600  479.76    6670  483.44    6700  483.46    6730  480.08  6821.2  480.67
#Mann= 5 ,-1 , 0
  2567.9     .05       0  4407.6     .12       0  5006.6     .07       0
  5013.2     .12       0  5338.8     .05       0
Bank Sta=5006.6,5013.2
XS Rating Curve= 0 ,0
Exp/Cntr=0.3,0.1

Type RM Length L Ch R = 1 ,26086   ,103,103,103
BEGIN DESCRIPTION:
Mapping XS 6a55acd9
END DESCRIPTION:
XS GIS Cut Line= 6
      2669576.98      6925316.98      2668563.09      6927518.38
      2668888.34      6927886.17      2669007.78      6928190.33
       2669236.7      6929872.54      2669681.09      6930441.92
#Sta/Elev= 30
  1534.9  498.43  1787.6  501.11  2406.7  484.36  2481.1  480.37    2527   482.4
  3369.2  483.24  3919.3  474.37  3957.3  471.53  3998.1  472.97  4055.1  469.44
  4182.2  468.68    4260  465.11  4488.3  462.57  4591.3  465.64  4645.5  461.14
  4985.2  460.69  5016.6  457.23  5017.7  456.73  5023.5  457.23  5040.2  461.38
  5073.4  462.35  6311.9  472.61  6461.6   474.9  6486.1   477.3  6556.7  474.99
  6892.2  479.52  6927.5  476.59    6942  479.52    7056  482.24  7202.7  482.97
#Mann= 3 ,-1 , 0
  1534.9     .05       0  5016.6     .03       0  5023.5     .05       0
Bank Sta=5016.6,5023.5
XS Rating Curve= 0 ,0
Exp/Cntr=0.3,0.1

Type RM Length L Ch R = 1 ,25983   ,1211,1211,1211
BEGIN DESCRIPTION:
Mapping XS 07b521da
END DESCRIPTION:
XS GIS Cut Line= 6
      2669479.75      6925282.27      2668500.59      6927469.76
      2668906.39      6928189.55      2669070.03      6929573.93
      2669257.53      6930032.26      2669667.27      6930532.29
#Sta/Elev= 30
  1498.1  496.18  1787.9  496.74  2143.1  486.66  2395.1  483.11  2452.5  477.99
  3082.9  483.65  3747.5  478.85  3991.7  473.86  4352.3  461.53  4599.1  460.46
  4739.1   459.5  4928.9  461.44  4976.3  457.26  4977.4  456.76  4983.2  457.26
  4997.5  459.91  5208.4  462.12  5231.7  464.94  5542.5  464.83  5939.8  472.61
  6159.4  471.63  6276.6  473.36    6282  475.78  6359.4  473.97  6388.8  476.48
  6436.9  474.55  6846.5  477.24  6918.3  480.18  6939.1  477.66    7261  479.31
#Mann= 5 ,-1 , 0
  1498.1     .05       0  4599.1     .12       0  4739.1     .05       0
  4976.3     .03       0  4983.2     .05       0
Bank Sta=4976.3,4983.2
XS Rating Curve= 0 ,0
Exp/Cntr=0.3,0.1

Type RM Length L Ch R = 1 ,24772   ,506,506,506
BEGIN DESCRIPTION:
Eagans Branch 47.0
END DESCRIPTION:
XS GIS Cut Line= 3
      2669368.64      6925268.39       2667886.5      6928337.94
      2667771.56      6929877.71
#Sta/Elev= 30
  1568.2  495.39  1699.8   495.2  1908.8  488.62  2366.4  481.55  2470.6  474.37
  2648.7  477.68  3400.2  480.07  3631.8  478.75    3790  475.73  3857.8  471.59
  3903.1  474.37  3914.2  471.96  3969.7  472.14  4004.6  468.98  4072.4  468.25
  4134.6  463.71  4298.4  458.74  4771.2  455.29  4888.2  455.97  4970.6  456.28
  4996.2  450.02  4997.4  449.52  5003.7  450.02  5030.1  456.48  5411.1  466.54
  6183.3  470.25  6363.8  473.12  6413.9  470.94  6474.1  473.78  6520.9  472.32
#Mann= 5 ,-1 , 0
  1568.2     .05       0  4771.2     .12       0  4888.2     .05       0
  4996.2     .03       0  5003.7     .05       0
Bank Sta=4996.2,5003.7
XS Rating Curve= 0 ,0
Exp/Cntr=0.3,0.1

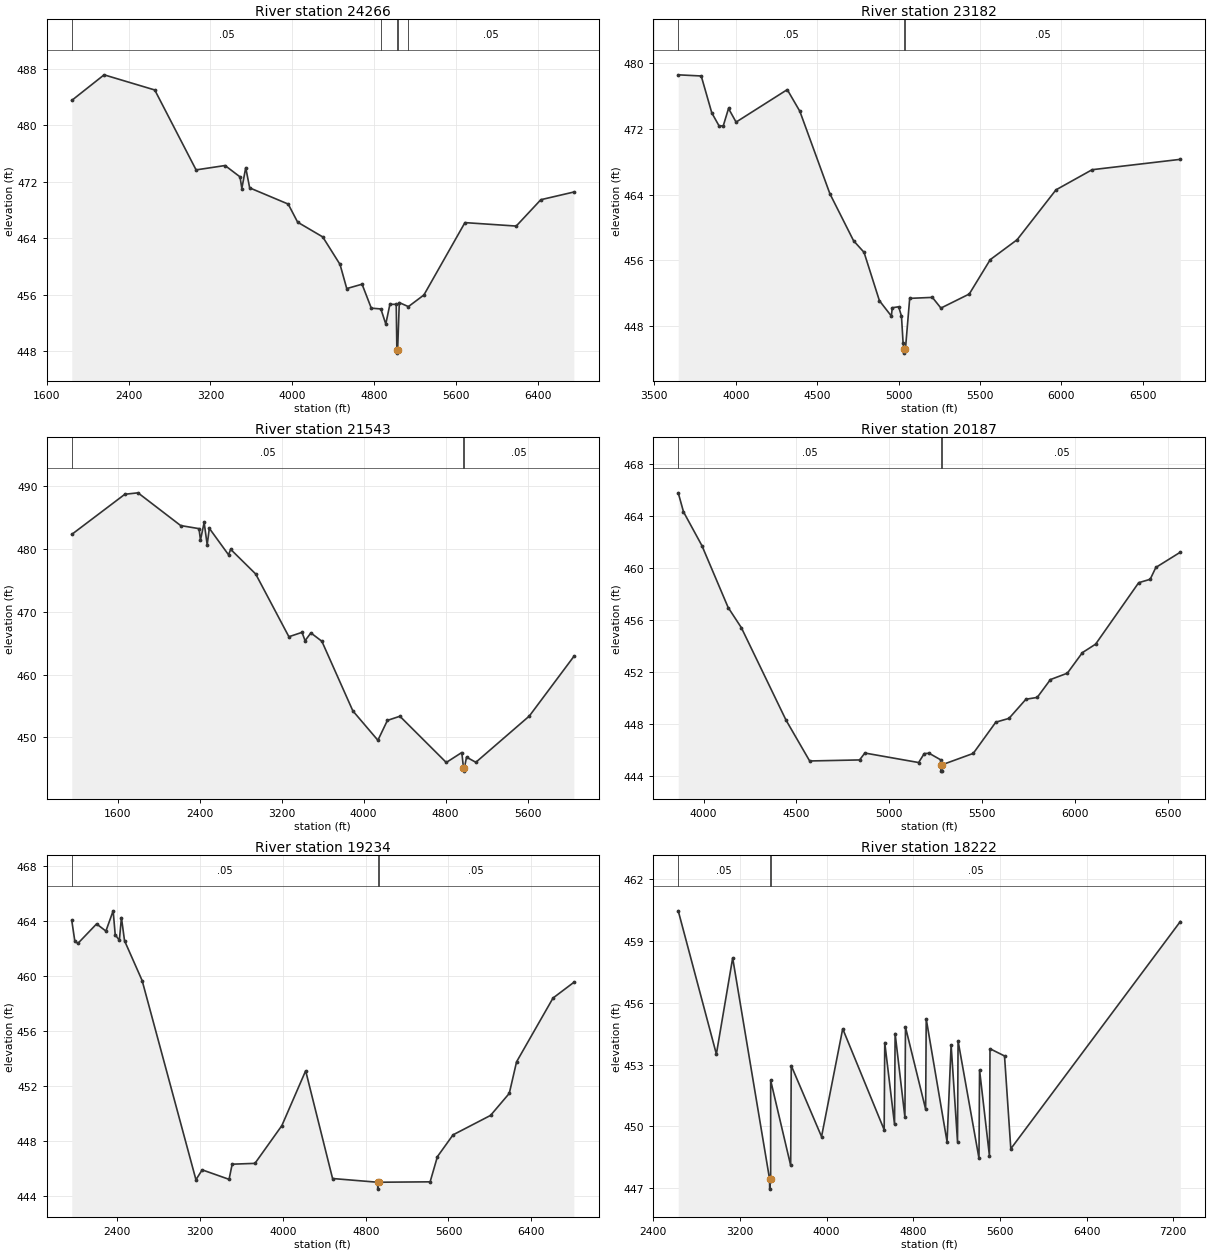
Type RM Length L Ch R = 1 ,24266   ,1084,1084,1084
BEGIN DESCRIPTION:
Eagans Branch 46.0
END DESCRIPTION:
XS GIS Cut Line= 3
       2668347.8      6925198.96        2667426.        6928211.
      2667313.09      6929962.82
#Sta/Elev= 30
  1845.2  483.56  2161.1  487.19  2656.1  485.04  3059.8   473.7  3342.9  474.32
  3489.2  472.71  3506.8  471.06  3544.8  474.02  3583.3  471.15  3959.8  468.85
  4052.1  466.28  4297.2  464.19  4466.3  460.28  4531.8  456.86  4681.4  457.48
  4771.7  454.08  4865.2  453.97  4913.2  451.83  4953.3  454.62  5015.2  454.63
  5021.4   448.2  5022.6   447.7    5029   448.2  5045.2  454.87  5133.9   454.3
  5285.7  455.95  5686.6  466.22  6187.6  465.73  6428.1  469.47  6750.6  470.56
#Mann= 5 ,-1 , 0
  1845.2     .05       0  4865.2     .12       0  5021.4     .07       0
    5029     .12       0  5133.9     .05       0
Bank Sta=5021.4,5029
XS Rating Curve= 0 ,0
Exp/Cntr=0.3,0.1

Type RM Length L Ch R = 1 ,23182   ,1639,1639,1639
BEGIN DESCRIPTION:
Eagans Branch 43.0
END DESCRIPTION:
XS GIS Cut Line= 3
      2666903.37      6926691.99      2666499.52      6927983.84
      2666264.68      6929697.42
#Sta/Elev= 30
  3646.5  478.58  3787.7  478.44  3852.6  473.95  3896.9  472.38  3922.8  472.36
  3955.3  474.49  4001.7  472.83    4316  476.78  4393.2  474.15  4577.9  464.11
  4723.2   458.4  4787.5  456.99  4881.8  451.11  4955.1  449.24  4960.9  450.25
    5000  450.37  5017.3  449.23  5027.4  445.92  5033.4  445.23  5034.6  444.73
  5041.7  445.23  5067.8  451.39  5207.1  451.51  5259.6  450.21  5433.6  451.92
  5562.4   456.1  5727.3  458.52  5966.1  464.59  6188.2  467.04  6729.6   468.3
#Mann= 3 ,-1 , 0
  3646.5     .05       0  5033.4     .04       0  5041.7     .05       0
Bank Sta=5033.4,5041.7
XS Rating Curve= 0 ,0
Exp/Cntr=0.3,0.1

Type RM Length L Ch R = 1 ,21543   ,1356,1356,1356
BEGIN DESCRIPTION:
Eagans Branch 40.0
END DESCRIPTION:
XS GIS Cut Line= 3
      2667292.27      6924407.25        2665076.        6927561.
      2664776.01      6928560.97
#Sta/Elev= 30
  1153.2  482.36  1671.1  488.76  1799.2  488.99  2215.7  483.77  2394.3  483.28
  2409.1  481.46  2444.8  484.27  2474.4   480.7  2495.4  483.33  2682.7  479.11
  2703.6  479.98  2947.6  476.05  3271.7  466.04  3399.8  466.74  3429.4  465.41
  3486.1  466.65  3593.2  465.32  3895.6  454.22    4140  449.53  4232.8   452.7
  4354.7  453.36    4807  445.99  4958.6  447.58  4975.1  445.11  4976.4  444.61
  4983.8  445.11  5004.7  446.84  5095.7  446.02  5617.7   453.4  6051.8   462.9
#Mann= 3 ,-1 , 0
  1153.2     .05       0  4975.1     .03       0  4983.8     .05       0
Bank Sta=4975.1,4983.8
XS Rating Curve= 0 ,0
Exp/Cntr=0.3,0.1

Type RM Length L Ch R = 1 ,20187   ,953,953,953
BEGIN DESCRIPTION:
Eagans Branch 37.0
END DESCRIPTION:
XS GIS Cut Line= 3
      2664875.98      6925911.02        2664076.        6926711.
      2663825.99      6928261.03
#Sta/Elev= 30
  3863.9  465.75  3892.2  464.29  3991.1   461.7  4132.6  456.94  4203.3   455.4
  4443.7   448.3    4571  445.16  4839.7  445.24    4868  445.77  5157.3  445.04
  5187.7  445.73    5214  445.75  5275.8  445.25  5276.1  444.88  5277.5  444.38
  5284.3  444.38  5285.6  444.88  5451.1  445.74  5572.6  448.14  5643.5  448.43
  5734.7   449.9  5795.4  450.04  5866.4  451.41  5957.5   451.9  6038.5  453.48
  6109.5  454.13  6341.4  458.85  6403.2  459.11  6433.6  460.02  6565.3  461.19
#Mann= 3 ,-1 , 0
  3863.9     .05       0  5276.1     .03       0  5285.6     .05       0
Bank Sta=5276.1,5285.6
XS Rating Curve= 0 ,0
Exp/Cntr=0.3,0.1

Type RM Length L Ch R = 1 ,19234   ,1012,1012,1012
BEGIN DESCRIPTION:
Eagans Branch 35.0
END DESCRIPTION:
XS GIS Cut Line= 3
      2663313.09       6923171.2        2663326.        6926211.
        2663126.        6928011.
#Sta/Elev= 30
  1960.2  464.03    1990  462.52    2020  462.37    2200  463.78    2290  463.26
    2360  464.73    2380  462.99    2420  462.59    2440  464.24    2470  462.56
    2640  459.67    3160  445.21    3220  445.93    3480  445.24    3510  446.34
    3730   446.4    3990  449.14    4220  453.12    4480   445.3  4915.2  445.03
  4916.5  444.53  4924.9  445.03  5422.6  445.06    5493  446.89    5644  448.47
  6006.2  449.88  6187.3  451.48  6257.7  453.77  6609.9   458.4  6811.1  459.54
#Mann= 3 ,-1 , 0
  1960.2     .05       0  4915.2     .03       0  4924.9     .05       0
Bank Sta=4915.2,4924.9
XS Rating Curve= 0 ,0
Exp/Cntr=0.3,0.1

Type RM Length L Ch R = 1 ,18222   ,37,37,37
BEGIN DESCRIPTION:
Mapping XS 37f90f64
END DESCRIPTION:
XS GIS Cut Line= 6
      2663102.73      6923863.33      2662881.93      6924613.24
      2662658.29      6925286.06      2662186.88      6926743.63
      2662188.61      6926836.51      2663041.77      6928093.45
#Sta/Elev= 30
  2630.2  460.47  2982.2  453.51  3132.7  458.18    3473  447.45  3474.5  446.95
  3483.3  447.45  3483.5  452.23  3668.1   448.1  3673.4  452.95  3953.1   449.5
  4148.5  454.74  4531.3  449.83  4536.5  454.07    4627  450.09  4632.2  454.51
  4722.7  450.44  4727.9  454.82  4914.1  450.83  4919.3  455.22  5111.7  449.25
  5149.1  453.96  5208.2  449.26  5213.4  454.15  5406.4  448.45  5411.7  452.74
  5502.9  448.57  5508.2  453.77  5642.1  453.42  5700.2  448.91  7264.9  459.95
#Mann= 3 ,-1 , 0
  2630.2     .05       0    3473     .04       0  3483.3     .05       0
Bank Sta=3473,3483.3
XS Rating Curve= 0 ,0
Exp/Cntr=0.3,0.1

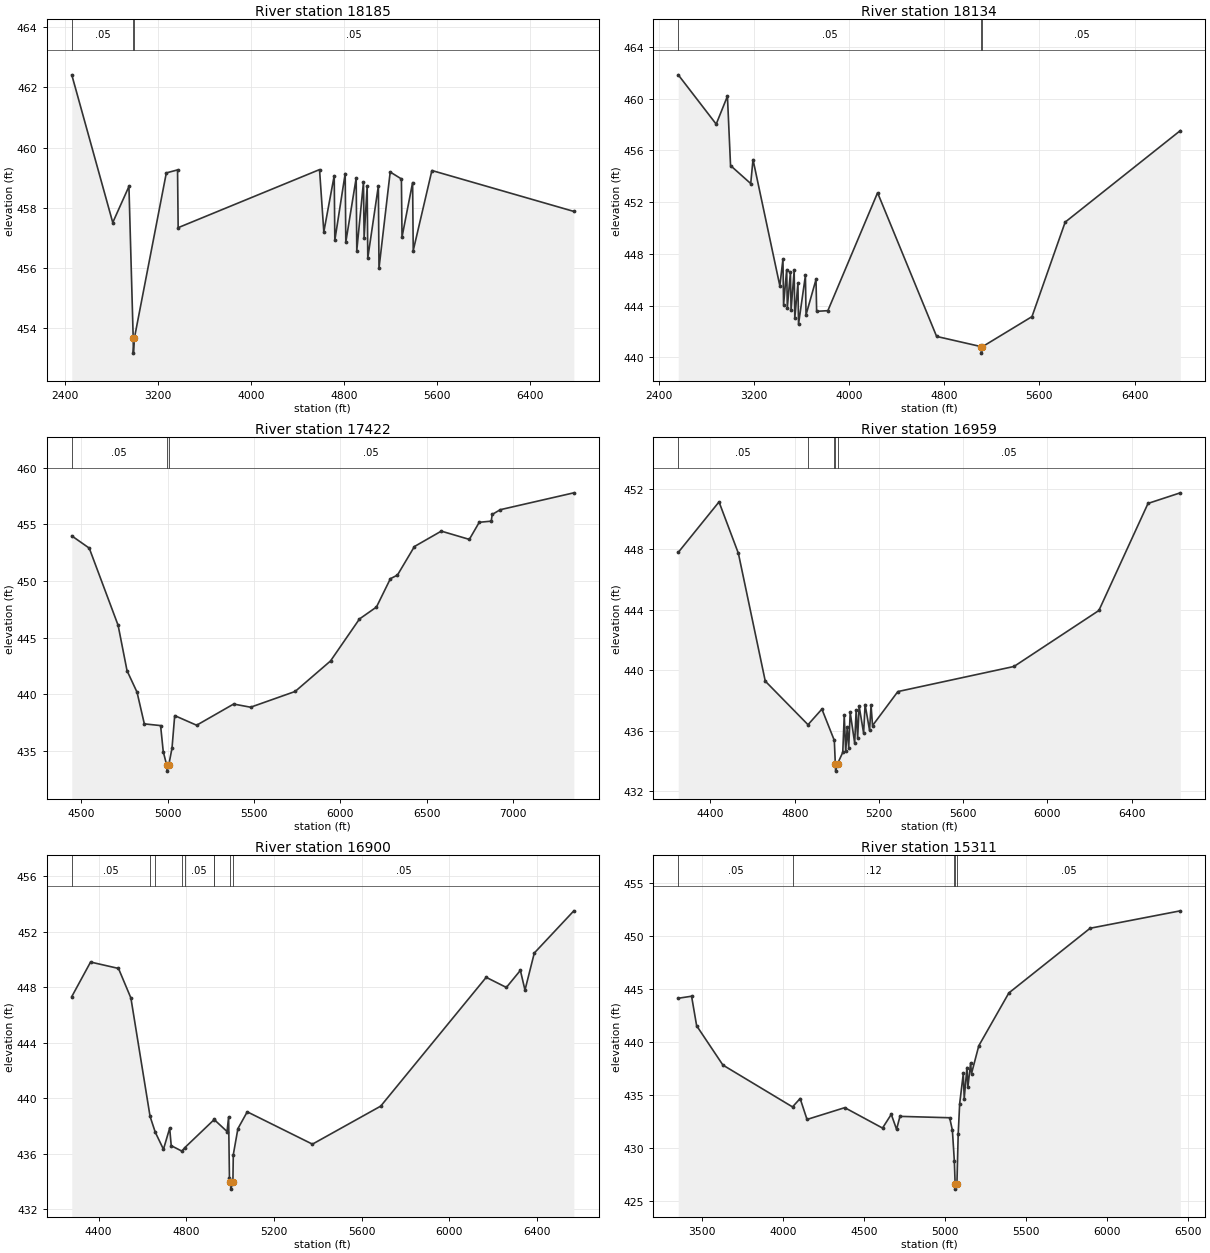
Type RM Length L Ch R = 1 ,18185   ,51,51,51
BEGIN DESCRIPTION:
Mapping XS 3d3237a9
END DESCRIPTION:
XS GIS Cut Line= 6
      2663139.18      6923692.77      2662693.01      6925088.15
      2662352.73      6926105.51      2662151.34      6926733.98
      2662154.81       6926869.4      2662690.97      6927696.11
#Sta/Elev= 30
  2456.6  462.42  2809.1  457.51  2948.3  458.71    2985  453.67  2986.5  453.17
  2995.3  453.67  3269.9  459.16  3366.4  459.26  3371.7  457.34  4587.7  459.27
  4624.6   457.2    4714  459.07  4719.2  456.92  4808.4  459.14  4813.7  456.86
  4902.9  458.99  4908.1  456.58  4965.8  458.86  4971.1  457.01  4997.4  458.71
  5002.7  456.33  5093.8  458.73  5099.1  455.99  5195.5  459.19  5291.9  458.96
  5297.2  457.03  5388.3  458.84  5393.6  456.58  5554.2  459.24  6775.1  457.88
#Mann= 3 ,-1 , 0
  2456.6     .05       0    2985     .04       0  2995.3     .05       0
Bank Sta=2985,2995.3
XS Rating Curve= 0 ,0
Exp/Cntr=0.3,0.1

Type RM Length L Ch R = 1 ,18134   ,712,712,712
BEGIN DESCRIPTION:
Mapping XS 7bea7016
END DESCRIPTION:
XS GIS Cut Line= 6
      2663083.19      6923783.93      2662324.03      6926030.96
      2662105.28      6926709.78       2662106.2      6926824.26
      2662137.45      6926924.95      2662626.01      6927697.63
#Sta/Elev= 30
  2565.8  461.83  2884.8  458.02  2979.2  460.18  3005.4  454.82  3174.9  453.43
  3194.1  455.28  3419.6  445.53  3445.7  447.59    3451  444.07  3477.2  446.78
  3482.5  443.84  3508.7  446.58  3513.9  443.66  3540.1  446.72  3545.4  443.05
  3571.6  445.72  3576.8  442.57  3634.5  446.33  3639.8  443.29  3723.6  446.02
  3728.8  443.56  3823.2  443.61    4241  452.72  4737.1  441.62  5112.3  440.83
  5113.8  440.33  5122.6  440.83  5538.4  443.15  5817.3  450.45  6784.9  457.52
#Mann= 3 ,-1 , 0
  2565.8     .05       0  5112.3     .04       0  5122.6     .05       0
Bank Sta=5112.3,5122.6
XS Rating Curve= 0 ,0
Exp/Cntr=0.3,0.1

Type RM Length L Ch R = 1 ,17422   ,463,463,463
BEGIN DESCRIPTION:
Eagans Branch 32.0
END DESCRIPTION:
XS GIS Cut Line= 3
      2661974.25      6925389.37        2661676.        6925861.
      2660715.56      6928002.25
#Sta/Elev= 30
    4446  453.98  4547.1   452.9  4714.1  446.09  4765.8  442.08  4823.5  440.19
  4865.8  437.39  4959.9  437.24  4975.2  434.95  4995.6  433.72  4997.1  433.22
  5006.6  433.72  5025.9  435.24  5041.5  438.12  5168.4  437.27  5382.4  439.14
  5480.6  438.86  5738.3  440.25  5942.9  442.94  6110.6  446.65  6208.8   447.7
  6289.3   450.2  6330.2  450.52  6428.4  453.04  6583.9   454.4  6746.1  453.67
  6803.4  455.18    6873  455.28  6878.4  455.87  6924.8  456.29  7350.8  457.78
#Mann= 3 ,-1 , 0
    4446     .05       0  4995.6     .03       0  5006.6     .05       0
Bank Sta=4995.6,5006.6
XS Rating Curve= 0 ,0
Exp/Cntr=0.3,0.1

Type RM Length L Ch R = 1 ,16959   ,59,59,59
BEGIN DESCRIPTION:
Eagans Branch 31.0
END DESCRIPTION:
XS GIS Cut Line= 3
      2661905.12      6925026.37      2661348.69      6925533.72
      2660184.68      6926676.48
#Sta/Elev= 30
    4247  447.79  4440.7  451.13  4532.6  447.73  4660.3  439.28  4863.2   436.4
  4929.2  437.43  4988.2  435.36  4992.9  433.83  4994.4  433.33  5003.9  433.83
  5028.3  434.57  5035.3  437.01  5042.4  434.63  5049.4  436.22  5056.6  434.89
  5063.6  437.21  5084.9  435.18  5091.9  437.38    5099  435.53    5106  437.63
  5127.3  435.84  5134.3  437.73  5155.6  436.03  5162.6  437.68  5169.7  436.34
  5289.9  438.59  5841.5  440.25  6244.5  443.95  6477.9  451.03  6631.2  451.73
#Mann= 5 ,-1 , 0
    4247     .05       0  4863.2     .12       0  4988.2     .05       0
  4992.9     .03       0  5003.9     .05       0
Bank Sta=4992.9,5003.9
XS Rating Curve= 0 ,0
Exp/Cntr=0.3,0.1

Type RM Length L Ch R = 1 ,16900   ,1589,1589,1589
BEGIN DESCRIPTION:
Eagans Branch 30.0
END DESCRIPTION:
XS GIS Cut Line= 4
      2661812.82      6924976.58      2661306.58      6925491.65
      2660838.73      6925920.43      2660160.08      6926559.93
#Sta/Elev= 30
  4277.8  447.31  4363.5   449.8  4490.8  449.34  4547.4  447.21  4634.8  438.68
  4658.5  437.54  4695.9  436.31  4724.2  437.83  4731.3  436.57  4779.6  436.18
  4792.6  436.42  4924.4  438.41  4926.6  438.46  4985.8  437.59  4992.9  438.63
  4996.8  434.22  5001.5  433.94    5003  433.44  5012.5  433.94  5014.3  435.92
  5035.4   437.8  5077.9  439.01  5375.1  436.68  5686.5  439.42  6167.5   448.7
  6259.4  447.97  6323.3   449.2  6344.3  447.78  6386.8  450.45  6567.1  453.49
#Mann= 9 ,-1 , 0
  4277.8     .05       0  4634.8     .12       0  4658.5     .05       0
  4779.6     .12       0  4792.6     .05       0  4924.4     .12       0
  4926.6     .05       0  5001.5     .03       0  5012.5     .05       0
Bank Sta=5001.5,5012.5
XS Rating Curve= 0 ,0
Exp/Cntr=0.3,0.1

Type RM Length L Ch R = 1 ,15311   ,699,699,699
BEGIN DESCRIPTION:
Eagans Branch 29.0
END DESCRIPTION:
XS GIS Cut Line= 4
      2661756.37      6924863.75      2660515.06      6924434.07
      2660258.68      6924644.73      2658956.91      6925284.75
#Sta/Elev= 30
  3354.6  444.11  3436.9   444.3  3468.1  441.52  3630.1  437.82  4059.3  433.88
  4106.3  434.67  4148.7   432.7  4381.5  433.81  4614.3  431.89  4668.2  433.18
    4701  431.77  4721.8  432.99  5028.2  432.86  5045.1  431.69  5057.2  428.78
    5062  426.64  5063.5  426.14  5073.1  426.64    5081  431.34  5090.1   434.2
  5112.5  437.03  5118.1  434.67    5135  437.59  5140.6  435.73  5157.5  438.01
  5163.1  437.02    5208  439.64  5393.4  444.61  5894.5   450.7  6450.6  452.34
#Mann= 5 ,-1 , 0
  3354.6     .05       0  4059.3     .12       0  5057.2     .05       0
    5062     .07       0  5073.1     .05       0
Bank Sta=5062,5073.1
XS Rating Curve= 0 ,0
Exp/Cntr=0.3,0.1

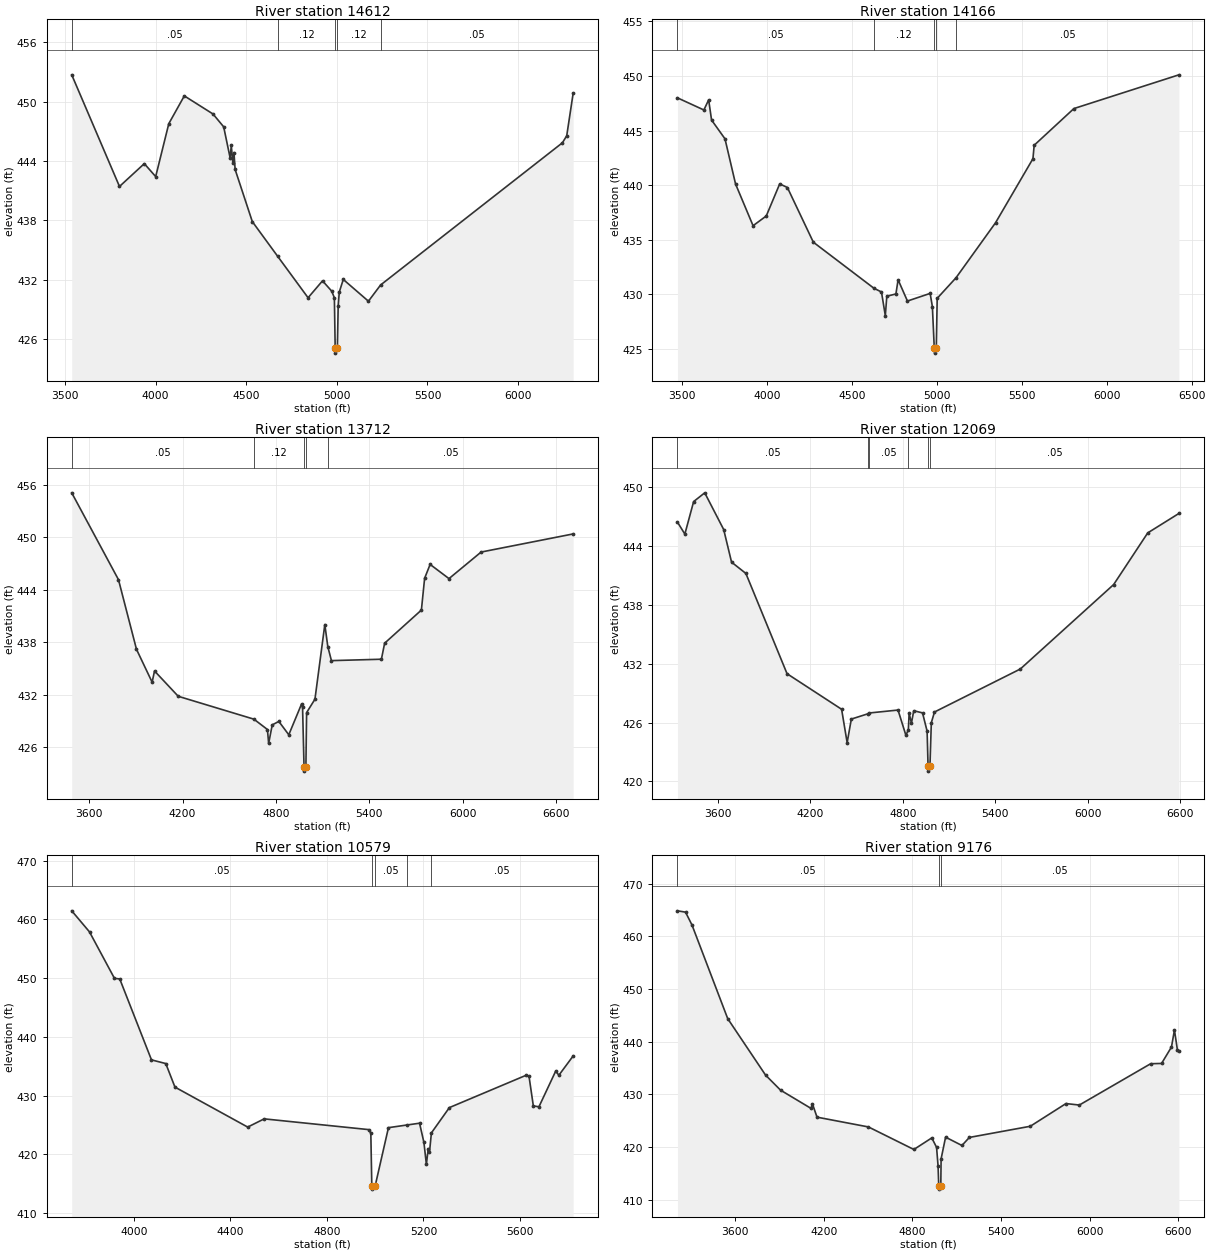
Type RM Length L Ch R = 1 ,14612   ,446,446,446
BEGIN DESCRIPTION:
Eagans Branch 26.0
END DESCRIPTION:
XS GIS Cut Line= 3
      2661574.96      6923173.86        2660376.        6924011.
      2659276.03      6924710.98
#Sta/Elev= 30
  3537.7  452.71  3801.1  441.42    3938  443.73  4000.8  442.42  4073.1  447.77
  4158.7  450.58    4317  448.75  4375.9  447.45  4411.7  444.29  4417.8  445.57
  4426.5  443.78  4432.6  444.85    4439  443.14  4533.8  437.87  4673.3  434.37
  4841.4  430.17  4921.1  431.88  4971.7  430.84  4986.5  430.17    4991  425.07
  4992.6  424.57    5003  425.07  5007.6  429.33  5013.5  430.74  5035.6  432.02
  5174.4  429.82  5241.5  431.46  6244.6  445.84  6268.3  446.55  6303.8  450.85
#Mann= 5 ,-1 , 0
  3537.7     .05       0  4673.3     .12       0    4991     .07       0
    5003     .12       0  5241.5     .05       0
Bank Sta=4991,5003
XS Rating Curve= 0 ,0
Exp/Cntr=0.3,0.1

Type RM Length L Ch R = 1 ,14166   ,454,454,454
BEGIN DESCRIPTION:
Eagans Branch 25.0
END DESCRIPTION:
XS GIS Cut Line= 3
      2661507.26      6922996.78        2660126.        6923661.
      2659026.03      6924560.98
#Sta/Elev= 30
  3471.2  447.99  3626.7  446.88  3654.8  447.81  3671.9  445.96  3750.9  444.24
  3813.3   440.1  3916.4  436.28  3994.1  437.17  4073.3  440.11  4118.6  439.78
  4271.5  434.77  4628.6  430.55  4672.9  430.21  4695.5  428.04  4704.3  429.82
  4757.9  430.03  4770.8  431.33  4825.8  429.38  4959.5  430.08  4972.7  428.88
  4983.8  425.11  4985.4  424.61  4995.8  425.11  5001.1  429.63  5111.9  431.51
  5344.8  436.55  5565.2  442.42  5572.4  443.65  5806.4  447.01  6425.1   450.1
#Mann= 5 ,-1 , 0
  3471.2     .05       0  4628.6     .12       0  4983.8     .07       0
  4995.8     .12       0  5111.9     .05       0
Bank Sta=4983.8,4995.8
XS Rating Curve= 0 ,0
Exp/Cntr=0.3,0.1

Type RM Length L Ch R = 1 ,13712   ,1643,1643,1643
BEGIN DESCRIPTION:
Eagans Branch 24.0
END DESCRIPTION:
XS GIS Cut Line= 3
      2661262.46      6922465.53        2659976.        6923261.
        2658926.        6924611.
#Sta/Elev= 30
  3487.5  455.06  3787.9  445.15  3903.7   437.2  4004.2  433.45  4019.6  434.73
    4172  431.84  4658.3  429.23  4745.3  428.05  4753.1  426.46  4776.1  428.58
  4818.6  428.97  4882.5  427.45  4964.8  430.97  4971.1  430.58  4980.5   423.8
  4982.1   423.3  4992.5   423.8  4997.1  429.98  5050.7  431.51  5114.1  440.03
  5133.3  437.51  5156.6  435.91  5477.8  436.07  5498.6   437.9  5734.8  441.68
  5755.6  445.31  5790.9  446.89  5912.2  445.27  6118.5   448.3  6710.3  450.37
#Mann= 5 ,-1 , 0
  3487.5     .05       0  4658.3     .12       0  4980.5     .07       0
  4992.5     .12       0  5133.3     .05       0
Bank Sta=4980.5,4992.5
XS Rating Curve= 0 ,0
Exp/Cntr=0.3,0.1

Type RM Length L Ch R = 1 ,12069   ,1490,1490,1490
BEGIN DESCRIPTION:
Eagans Branch 21.0
END DESCRIPTION:
XS GIS Cut Line= 3
      2660710.35      6921429.09      2659330.93      6922355.98
      2658690.27      6923812.83
#Sta/Elev= 30
  3338.1   446.4  3385.9  445.19  3442.9   448.5  3514.9  449.39  3637.9  445.65
  3688.9  442.33  3781.9  441.18  4048.9  430.97  4402.9  427.35  4438.9  423.95
    4466  426.35  4575.8   426.9  4581.8  426.97    4769  427.27    4820   424.7
  4835.9  425.25    4841  426.95    4856  425.93    4871   427.2    4928  426.98
  4957.7  425.12  4963.9  421.55  4965.6  421.05  4976.1  421.55    4985  425.98
  5005.5  427.07  5562.6  431.45  6168.1  440.05  6389.2  445.31  6591.5  447.29
#Mann= 6 ,-1 , 0
  3338.1     .05       0  4575.8     .12       0  4581.8     .05       0
  4835.9     .12       0  4963.9     .03       0  4976.1     .05       0
Bank Sta=4963.9,4976.1
XS Rating Curve= 0 ,0
Exp/Cntr=0.3,0.1

Type RM Length L Ch R = 1 ,10579   ,1403,1403,1403
BEGIN DESCRIPTION:
Eagans Branch 19.0
END DESCRIPTION:
XS GIS Cut Line= 3
      2659176.02      6920810.97        2658576.        6921911.
      2658375.99      6922711.04
#Sta/Elev= 30
  3742.8  461.46  3816.4  457.87  3919.9  449.95  3941.7  449.86  4073.2  436.07
  4132.5  435.44  4170.5  431.43  4471.9  424.62  4540.2  426.02  4973.1  424.19
  4982.1  423.58  4986.2  414.55  4988.1  414.05  4999.8  414.55  5055.1  424.52
  5132.8  424.98    5184  425.28    5202  422.02  5212.3  418.27    5220  420.95
  5225.2  420.35  5233.1  423.63  5307.6  427.94  5624.6  433.43  5637.5  433.29
  5655.5  428.22  5678.7  428.08  5748.3  434.17  5761.2  433.45  5820.5  436.74
#Mann= 5 ,-1 , 0
  3742.8     .05       0  4986.2     .05       0  4999.8     .05       0
  5132.8     .12       0  5233.1     .05       0
Bank Sta=4986.2,4999.8
XS Rating Curve= 0 ,0
Exp/Cntr=0.3,0.1

Type RM Length L Ch R = 1 ,9176    ,1389,1389,1389
BEGIN DESCRIPTION:
Eagans Branch 16.0
END DESCRIPTION:
XS GIS Cut Line= 3
      2657761.91      6919809.09        2657376.        6921561.
      2657208.52      6923151.09
#Sta/Elev= 30
  3210.3  464.84  3264.8  464.59  3308.5  462.14  3550.2  444.36  3806.2  433.64
  3907.6  430.78  4113.4  427.32  4123.6  428.16  4154.3  425.65  4502.5  423.79
  4809.7  419.51  4930.9  421.71  4963.3  419.92  4973.5  416.36  4978.1  412.48
    4980  411.98  4991.8  412.48    4994  417.73  5024.3  421.85  5134.9  420.27
  5185.2   421.8  5597.5  423.92  5838.8  428.23  5929.3  427.95    6412   435.8
  6485.7  435.85  6552.7  438.97  6572.8   442.2    6593  438.41  6603.1  438.25
#Mann= 3 ,-1 , 0
  3210.3     .05       0  4978.1     .03       0  4991.8     .05       0
Bank Sta=4978.1,4991.8
XS Rating Curve= 0 ,0
Exp/Cntr=0.3,0.1