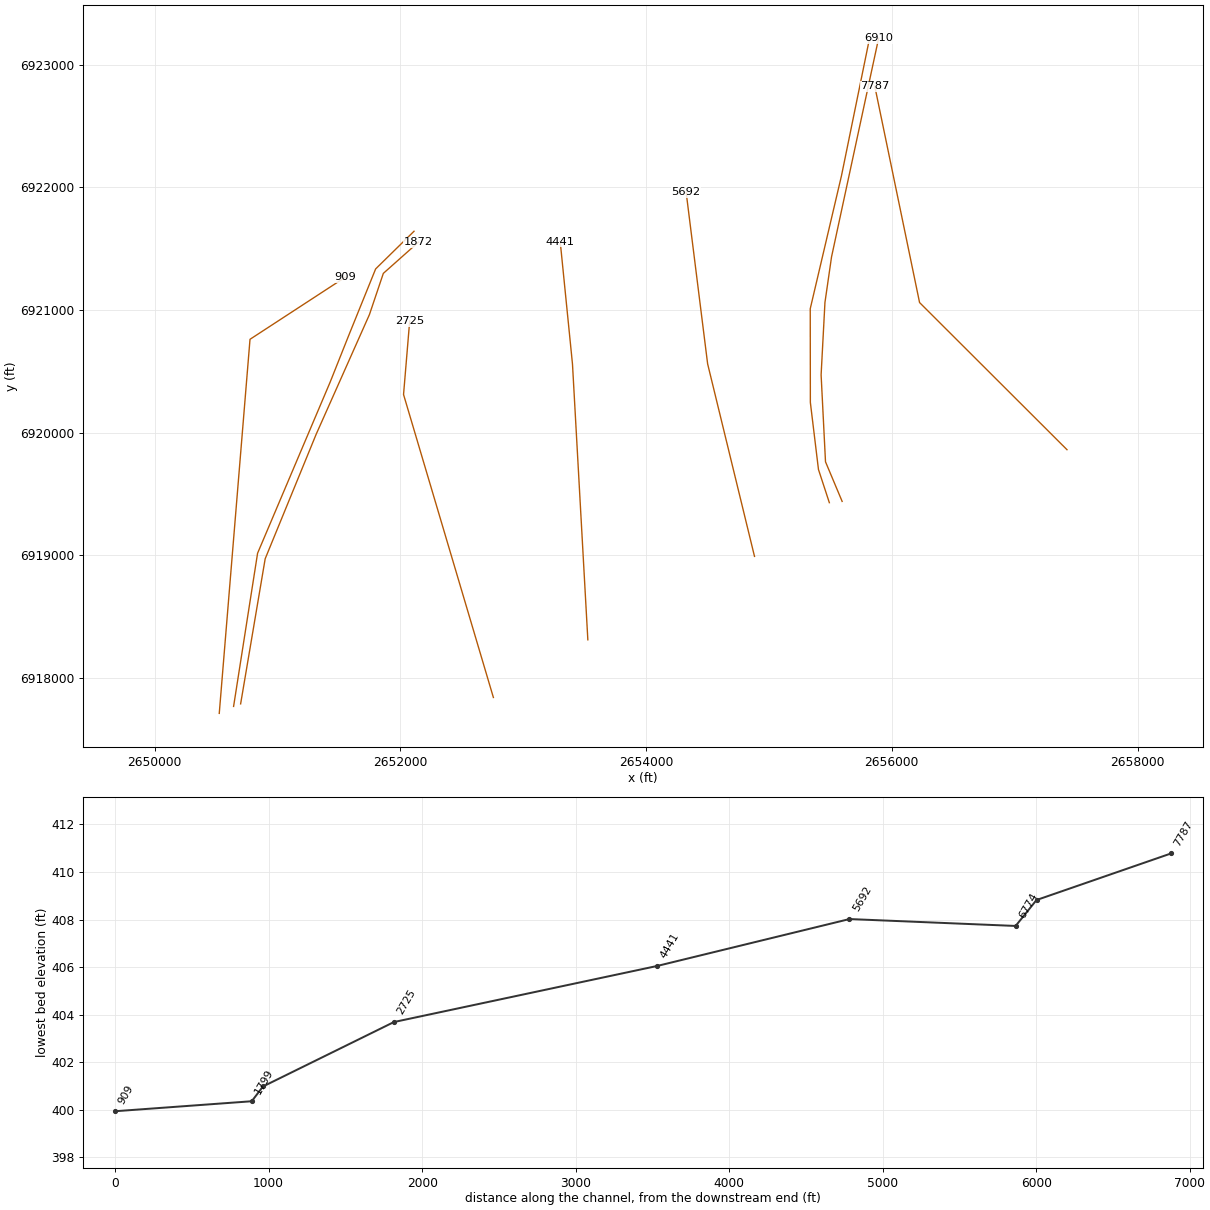
HEC-RAS study Eagans Branch.prj: Eagans Branch Base Level Engineering

--- Eagans Branch.g01 (geometry) --- (continued)

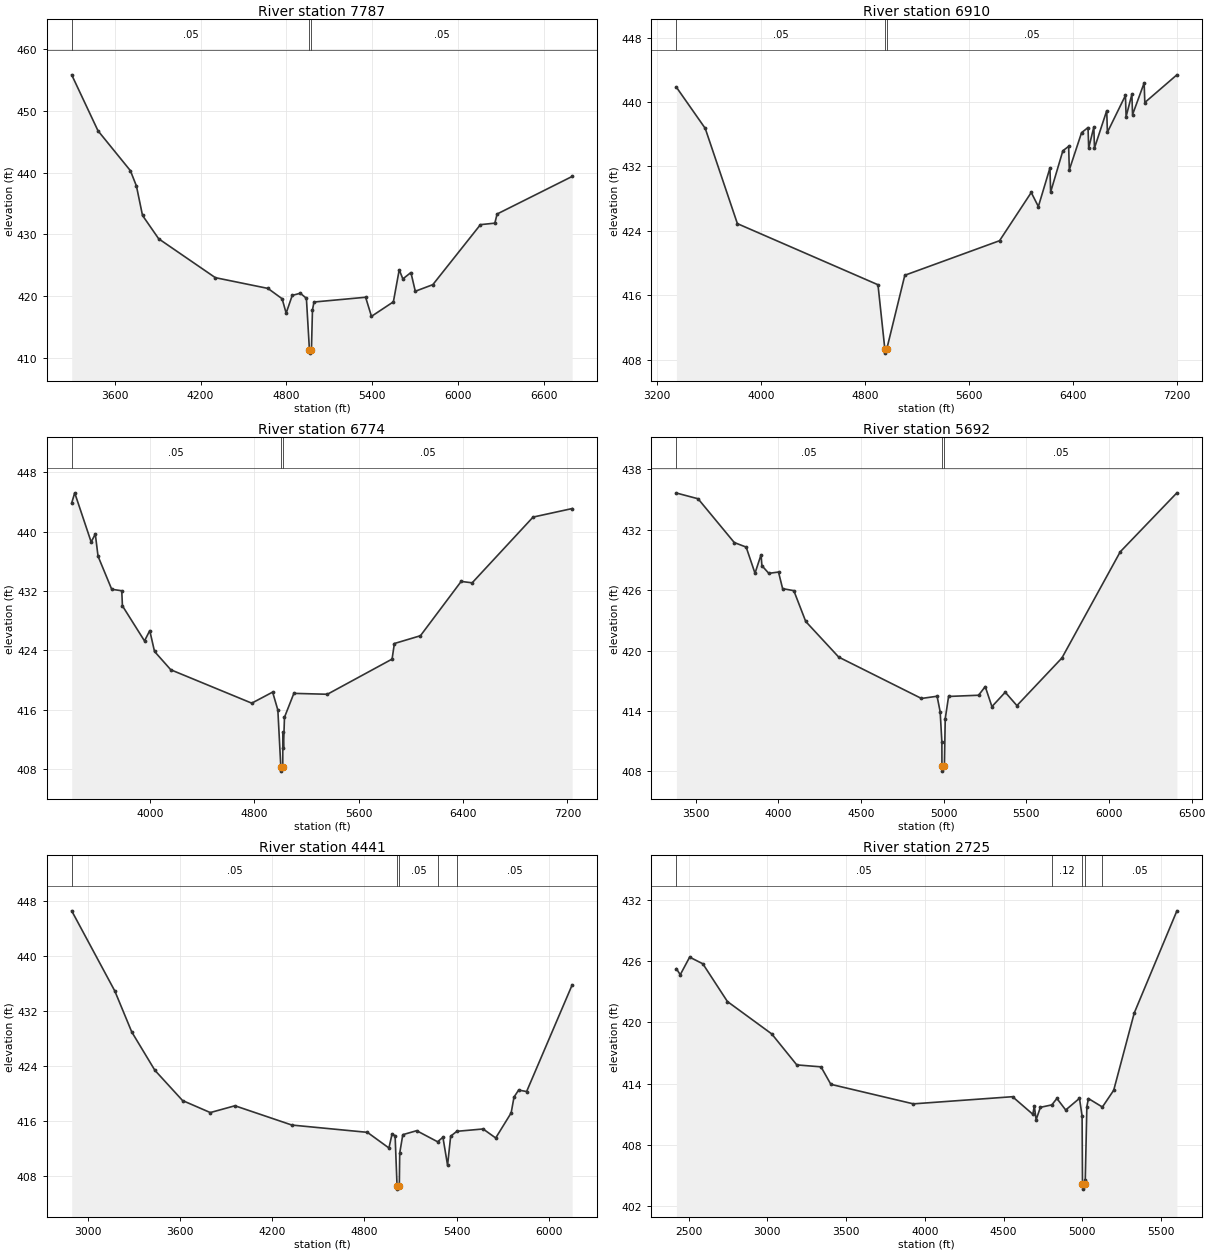
Type RM Length L Ch R = 1 ,7787    ,877,877,877
BEGIN DESCRIPTION:
Eagans Branch 13.0
END DESCRIPTION:
XS GIS Cut Line= 3
      2657425.99      6919861.01        2656226.        6921061.
      2655861.42      6922824.88
#Sta/Elev= 30
  3299.2  455.81    3483  446.76  3709.3  440.31  3751.7  437.82  3794.2  433.06
  3907.3  429.28  4303.3  422.99    4671  421.25    4770  419.58  4798.2  417.25
  4840.7  420.12  4897.2  420.47  4939.7  419.65    4961  411.28    4963  410.78
  4974.9  411.28  4982.1  417.76  4992.7  419.05  5353.6  419.82  5394.5  416.73
  5547.7  419.08  5588.5  424.26  5613.9  422.79  5670.2  423.82  5700.8  420.79
  5823.4  421.86  6156.2  431.57  6256.7  431.81  6272.7  433.29  6797.4  439.37
#Mann= 3 ,-1 , 0
  3299.2     .05       0    4961     .04       0  4974.9     .05       0
Bank Sta=4961,4974.9
XS Rating Curve= 0 ,0
Exp/Cntr=0.3,0.1

Type RM Length L Ch R = 1 ,6910    ,136,136,136
BEGIN DESCRIPTION:
Mapping XS 375aad6c
END DESCRIPTION:
XS GIS Cut Line= 6
       2655595.8      6919439.45      2655460.37      6919762.41
      2655424.61      6920471.34      2655455.85      6921061.36
       2655509.5      6921433.32      2655892.65       6923215.5
#Sta/Elev= 30
  3349.1  441.84  3570.7  436.73  3818.1   424.9  4899.5  417.31  4952.3  409.32
  4954.3  408.82  4966.9  409.32  5105.9  418.49  5834.6  422.78  6078.4  428.77
  6133.1  427.02  6222.3  431.82  6227.4  428.81  6321.6  433.95  6366.1   434.5
  6371.2  431.58  6465.5   436.2  6515.1  436.83  6520.2  434.29  6559.7  436.89
  6564.8  434.29    6659  438.93  6664.1  436.24  6802.9  440.82    6808  438.19
  6852.5  440.96  6857.6  438.44  6946.8  442.37  6951.9  439.94  7198.8  443.38
#Mann= 3 ,-1 , 0
  3349.1     .05       0  4952.3     .05       0  4966.9     .05       0
Bank Sta=4952.3,4966.9
XS Rating Curve= 0 ,0
Exp/Cntr=0.3,0.1

Type RM Length L Ch R = 1 ,6774    ,1082,1082,1082
BEGIN DESCRIPTION:
Mapping XS a7b84577
END DESCRIPTION:
XS GIS Cut Line= 6
      2655491.62      6919429.08      2655403.08      6919699.91
      2655337.11      6920246.34      2655336.16       6921010.6
      2655590.58      6922095.74      2655814.53      6923194.69
#Sta/Elev= 30
  3400.4  443.86  3423.5  445.24  3549.7  438.61  3581.3  439.69  3602.3   436.7
  3707.1  432.24  3784.1  432.04  3789.2  430.01  3958.4  425.28  3998.7  426.67
  4035.2  423.86  4159.9  421.39  4780.4  416.89  4940.4  418.38  4980.4  415.96
  5003.4  408.23  5005.4  407.73    5018  408.23  5018.5  412.98  5023.6  410.89
  5031.2  414.99  5103.1  418.21  5359.9  418.09  5855.8  422.83  5873.5  424.93
  6073.2  425.98  6385.3   433.3  6469.6  433.11  6936.4  441.97  7236.1  443.12
#Mann= 3 ,-1 , 0
  3400.4     .05       0  5003.4     .03       0    5018     .05       0
Bank Sta=5003.4,5018
XS Rating Curve= 0 ,0
Exp/Cntr=0.3,0.1

Type RM Length L Ch R = 1 ,5692    ,1251,1251,1251
BEGIN DESCRIPTION:
Eagans Branch 9.0
END DESCRIPTION:
XS GIS Cut Line= 3
      2654882.47      6918991.19        2654501.        6920561.
        2654326.      6921961.01
#Sta/Elev= 30
  3384.5  435.65  3515.4  435.08  3734.4  430.73  3806.2  430.28  3859.7  427.68
  3896.3  429.52  3901.5  428.43  3943.2  427.67  4001.8   427.8  4026.7  426.15
  4094.4  425.95  4166.4  422.89  4365.9  419.35  4866.2  415.24  4960.8  415.46
  4979.4  413.91  4989.7   410.9  4990.1  408.52  4992.1  408.02  5004.8  408.52
  5010.1  413.23  5030.2  415.44  5211.6  415.56  5251.9  416.42  5292.3  414.43
  5372.9  415.86  5443.4  414.53  5715.5  419.26  6068.2  429.81  6410.9  435.67
#Mann= 3 ,-1 , 0
  3384.5     .05       0  4990.1     .04       0  5004.8     .05       0
Bank Sta=4990.1,5004.8
XS Rating Curve= 0 ,0
Exp/Cntr=0.3,0.1

Type RM Length L Ch R = 1 ,4441    ,1716,1716,1716
BEGIN DESCRIPTION:
Eagans Branch 4.0
END DESCRIPTION:
XS GIS Cut Line= 3
        2653526.      6918310.97        2653401.      6920558.92
      2653301.15      6921557.42
#Sta/Elev= 30
  2896.5  446.58    3177   434.9  3287.1  428.94  3437.4  423.36  3617.6  418.95
  3797.9   417.2  3958.2  418.19  4328.7  415.38  4819.5  414.32  4959.7  412.04
  4979.7  414.06  4999.8  413.83  5012.4  406.55  5014.4  406.05  5027.2  406.55
  5029.8   411.3  5049.9  413.98    5140  414.56  5275.9  412.95  5310.8   413.6
    5341  409.53  5361.1  413.76  5401.3  414.47  5572.1  414.81    5654   413.5
  5754.5  417.15  5773.1  419.46  5803.3  420.48    5855  420.26  6151.4   435.8
#Mann= 5 ,-1 , 0
  2896.5     .05       0  5012.4     .03       0  5027.2     .05       0
  5275.9     .12       0  5401.3     .05       0
Bank Sta=5012.4,5027.2
XS Rating Curve= 0 ,0
Exp/Cntr=0.3,0.1

Type RM Length L Ch R = 1 ,2725    ,853,853,853
BEGIN DESCRIPTION:
Eagans Branch 3.0
END DESCRIPTION:
XS GIS Cut Line= 3
      2652757.25       6917840.5        2652026.        6920311.
        2652076.      6920910.97
#Sta/Elev= 30
  2422.7  425.25    2447  424.66  2506.7  426.38  2590.5  425.73  2746.5  422.04
  3028.1  418.87  3187.2  415.84    3341  415.65  3403.5  413.94  3927.4  412.03
  4557.3  412.73  4686.3  411.01  4695.6  411.82  4707.1  410.47  4734.1  411.69
  4806.9  411.93  4839.1  412.56  4894.9  411.43  4982.5  412.57  4999.1  410.83
  5001.6  404.19  5003.6  403.69  5016.8  404.19  5019.2  404.58  5029.3  411.76
  5039.3  412.55  5127.9  411.72  5199.8  413.36  5330.3  420.92  5601.2  430.91
#Mann= 5 ,-1 , 0
  2422.7     .05       0  4806.9     .12       0  5001.6     .07       0
  5016.8     .12       0  5127.9     .05       0
Bank Sta=5001.6,5016.8
XS Rating Curve= 0 ,0
Exp/Cntr=0.3,0.1

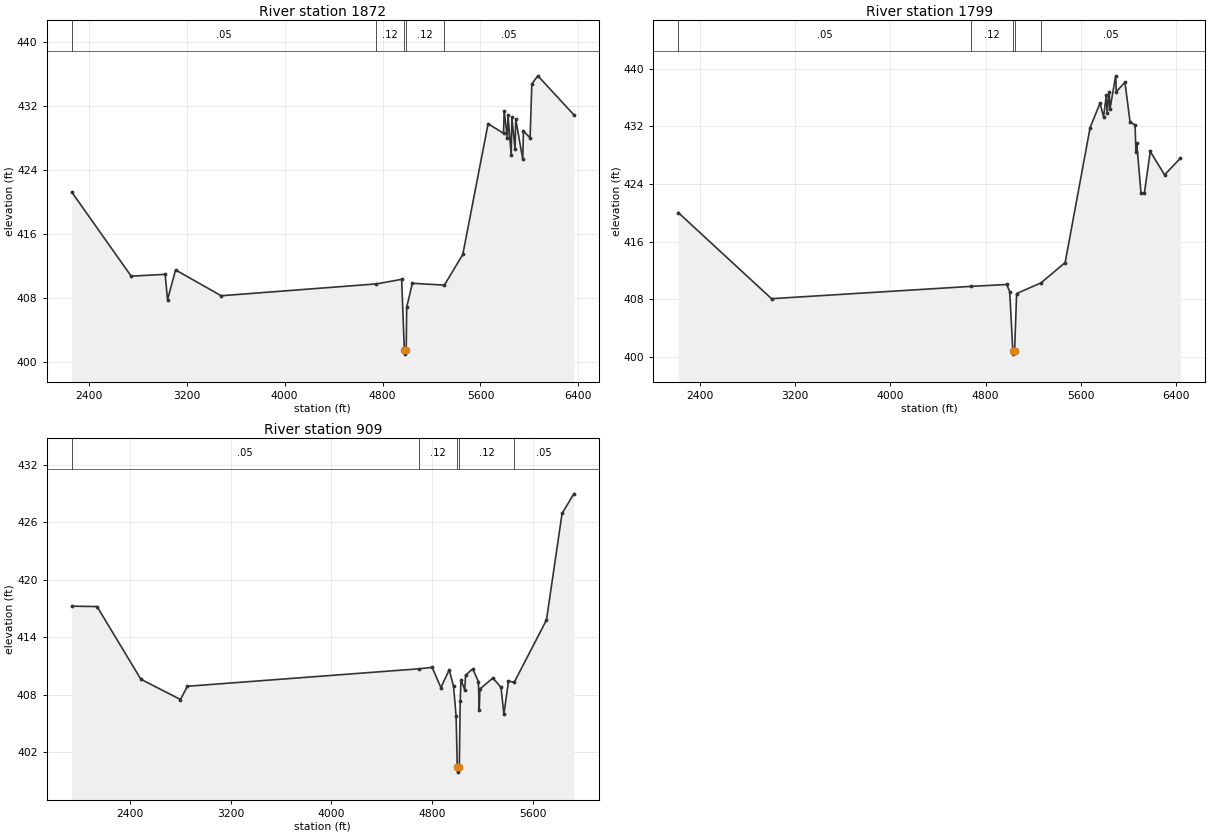
Type RM Length L Ch R = 1 ,1872    ,73,73,73
BEGIN DESCRIPTION:
Mapping XS 5253373c
END DESCRIPTION:
XS GIS Cut Line= 6
      2650699.96      6917788.48      2650899.81      6918971.76
      2651314.54      6919986.37      2651748.33      6920962.87
      2651861.41      6921298.87      2652147.85      6921554.06
#Sta/Elev= 30
  2260.5  421.24    2746  410.73  3023.7  410.96  3043.1  407.78  3108.6  411.51
  3481.3  408.28  4749.1  409.76  4956.3  410.33  4978.2  401.48  4980.2  400.98
  4993.4  401.48  4997.3  406.85  5043.8  409.84  5305.4  409.61    5456  413.45
  5662.5  429.79  5788.5  428.59  5793.8  431.39    5820  427.96  5825.3  430.86
  5851.5  425.84  5856.8  430.59    5883  426.62  5888.3  430.36    5946  425.34
  5951.3  428.87  6005.7  428.03  6019.9  434.77  6069.2  435.78  6363.3  430.91
#Mann= 5 ,-1 , 0
  2260.5     .05       0  4749.1     .12       0  4978.2     .07       0
  4993.4     .12       0  5305.4     .05       0
Bank Sta=4978.2,4993.4
XS Rating Curve= 0 ,0
Exp/Cntr=0.3,0.1

Type RM Length L Ch R = 1 ,1799    ,890,890,890
BEGIN DESCRIPTION:
Mapping XS c2ddc1b4
END DESCRIPTION:
XS GIS Cut Line= 6
      2650642.66       6917767.6      2650837.96       6919016.9
      2651429.12      6920413.45      2651580.16      6920793.66
      2651798.91      6921335.32      2652111.24      6921642.44
#Sta/Elev= 30
  2221.3  420.02  3004.1  408.06  4677.5  409.77    4977  410.03  5002.3  409.05
  5028.3  400.86  5030.3  400.36  5043.5  400.86  5060.2  408.77  5265.5  410.26
  5467.5  413.08  5676.7  431.81  5759.9  435.21  5789.5  433.33  5813.6  436.38
    5819  433.84  5837.7  436.78  5843.1  434.36  5891.4  439.01  5896.8  436.81
  5969.2  438.12  6011.7  432.64  6054.1  432.17  6061.2  428.46  6068.2  429.62
  6103.7  422.75  6131.8  422.69  6181.4  428.51  6301.5  425.26  6433.6  427.56
#Mann= 5 ,-1 , 0
  2221.3     .05       0  4677.5     .12       0  5028.3     .07       0
  5043.5     .12       0  5265.5     .05       0
Bank Sta=5028.3,5043.5
XS Rating Curve= 0 ,0
Exp/Cntr=0.3,0.1

Type RM Length L Ch R = 1 ,909     ,0,0,0
BEGIN DESCRIPTION:
Eagans Branch 1.0
END DESCRIPTION:
XS GIS Cut Line= 3
        2650526.      6917710.99      2650776.31      6920761.34
      2651550.02      6921266.64
#Sta/Elev= 30
  1939.4  417.24  2140.1   417.2  2487.9  409.62  2802.3  407.51    2857  408.89
  4693.6  410.71    4799  410.86  4869.2  408.75  4934.8  410.61  4969.6  408.87
  4989.6  405.78  4999.1  400.44  5001.1  399.94  5015.1  400.44  5022.2  407.34
  5028.2  409.59  5058.4  408.51  5064.4  410.04  5121.6  410.71  5166.8  409.37
    5173  406.44  5178.9  408.61  5281.6  409.75    5346  408.78  5369.1  405.97
  5405.3  409.44  5450.8   409.3  5706.9   415.8  5830.6   426.9  5924.1  428.95
#Mann= 5 ,-1 , 0
  1939.4     .05       0  4693.6     .12       0  4999.1     .07       0
  5015.1     .12       0  5450.8     .05       0
Bank Sta=4999.1,5015.1
XS Rating Curve= 0 ,0
Exp/Cntr=0.3,0.1

Chan Stop Cuts=-1
Use User Specified Reach Order=0
Composite Channel Slope=5