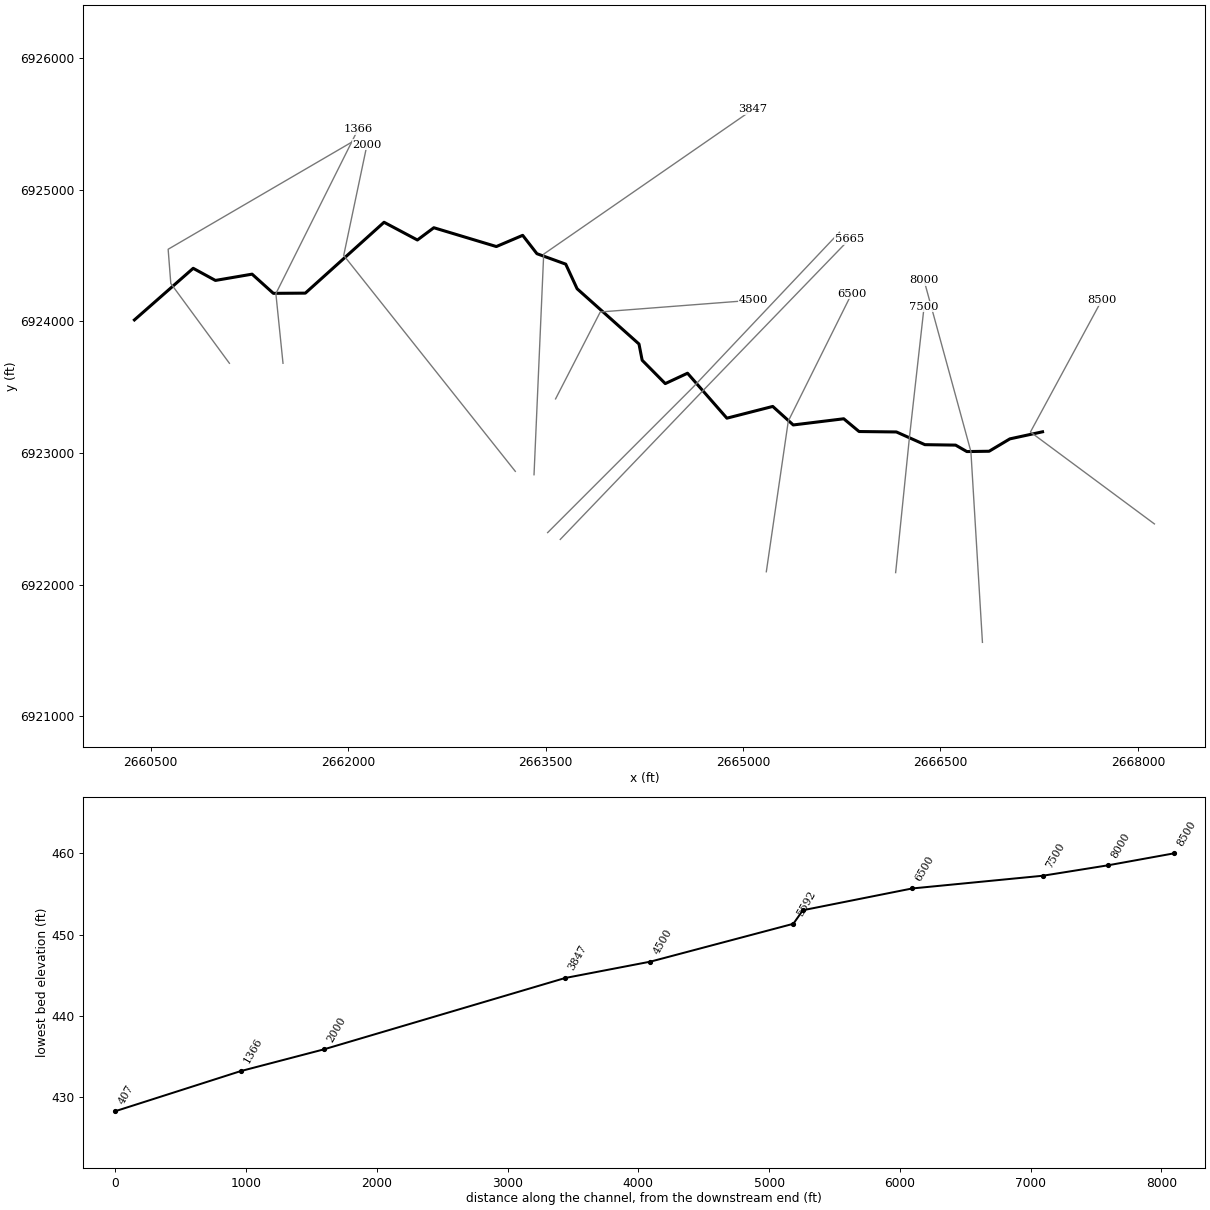
--- Eagans Branch Trib 2.prj (project) ---

Proj Title=Eagans Branch Trib 2 Base Level Engineering
Current Plan=p01
Default Exp/Contr=0.3,0.1
English Units
Geom File=g01
Flow File=f01
Plan File=p01
BEGIN DESCRIPTION:
Eagans Branch Trib 2
END DESCRIPTION:

--- Eagans Branch Trib 2.p01 (plan) ---

Plan Title=Multiple Run
Short Identifier=Multiple
Geom File=g01
Flow File=f01
Subcritical Flow
K Sum by GR= 0
Std Step Tol= 0.01
Critical Tol= 0.01
Num of Std Step Trials= 20
Max Error Tol= 0.3
Flow Tol Ratio= 0.001
Split Flow NTrial= 30
Split Flow Tol= 0.02
Split Flow Ratio= 0.02
Log Output Level= 0
Friction Slope Method= 1
Unsteady Friction Slope Method= 2
Unsteady Bridges Friction Slope Method= 1
Parabolic Critical Depth
Global Vel Dist=  1 , 1 , 1
Global Log Level= 0
CheckData=True
Encroach Param= -1, 0, 0, 0
BEGIN DESCRIPTION:
Multiple Run
END DESCRIPTION:

--- Eagans Branch Trib 2.f01 (steady flow) ---

Flow Title=Multiple
Number of Profiles=7
Profile Names=10-year,25-year,50-year,1pct_min,100-year,1pct_plu,500-year
River Rch & RM= Eagans Branch Tr,Reach-1,8500
     570     765     922     552    1101    2197    1568
River Rch & RM= Eagans Branch Tr,Reach-1,4500
     687     931    1130     680    1357    2708    1958
Boundary for River Rch & Prof#=Eagans Branch Tr,Reach-1,1
Up Type=0
Dn Type=3
Dn Slope=0.005
Boundary for River Rch & Prof#=Eagans Branch Tr,Reach-1,2
Up Type=0
Dn Type=3
Dn Slope=0.005
Boundary for River Rch & Prof#=Eagans Branch Tr,Reach-1,3
Up Type=0
Dn Type=3
Dn Slope=0.005
Boundary for River Rch & Prof#=Eagans Branch Tr,Reach-1,4
Up Type=0
Dn Type=3
Dn Slope=0.005
Boundary for River Rch & Prof#=Eagans Branch Tr,Reach-1,5
Up Type=0
Dn Type=3
Dn Slope=0.005
Boundary for River Rch & Prof#=Eagans Branch Tr,Reach-1,6
Up Type=0
Dn Type=3
Dn Slope=0.005
Boundary for River Rch & Prof#=Eagans Branch Tr,Reach-1,7
Up Type=0
Dn Type=3
Dn Slope=0.005

--- Eagans Branch Trib 2.g01 (geometry) ---

Geom Title=Existing Conditions

River Reach=Eagans Branch Tr,Reach-1
Reach XY= 30
      2667276.00      6923161.00      2667027.58      6923107.17
      2666870.07      6923013.24      2666700.92      6923010.80
      2666615.50      6923059.78      2666381.94      6923063.26
      2666165.50      6923159.78      2665881.86      6923163.07
      2665765.56      6923259.94      2665381.89      6923212.96
      2665226.10      6923353.68      2664877.56      6923264.44
      2664578.54      6923606.04      2664409.33      6923527.20
      2664233.86      6923704.83      2664209.70      6923828.13
      2663739.62      6924247.79      2663653.15      6924434.84
      2663434.34      6924514.17      2663326.11      6924653.69
      2663126.00      6924568.56      2662650.96      6924711.49
      2662526.08      6924618.30      2662272.69      6924752.98
      2661674.54      6924214.54      2661431.68      6924213.00
      2661270.10      6924358.77      2660991.39      6924311.08
      2660822.60      6924403.22      2660376.00      6924011.00

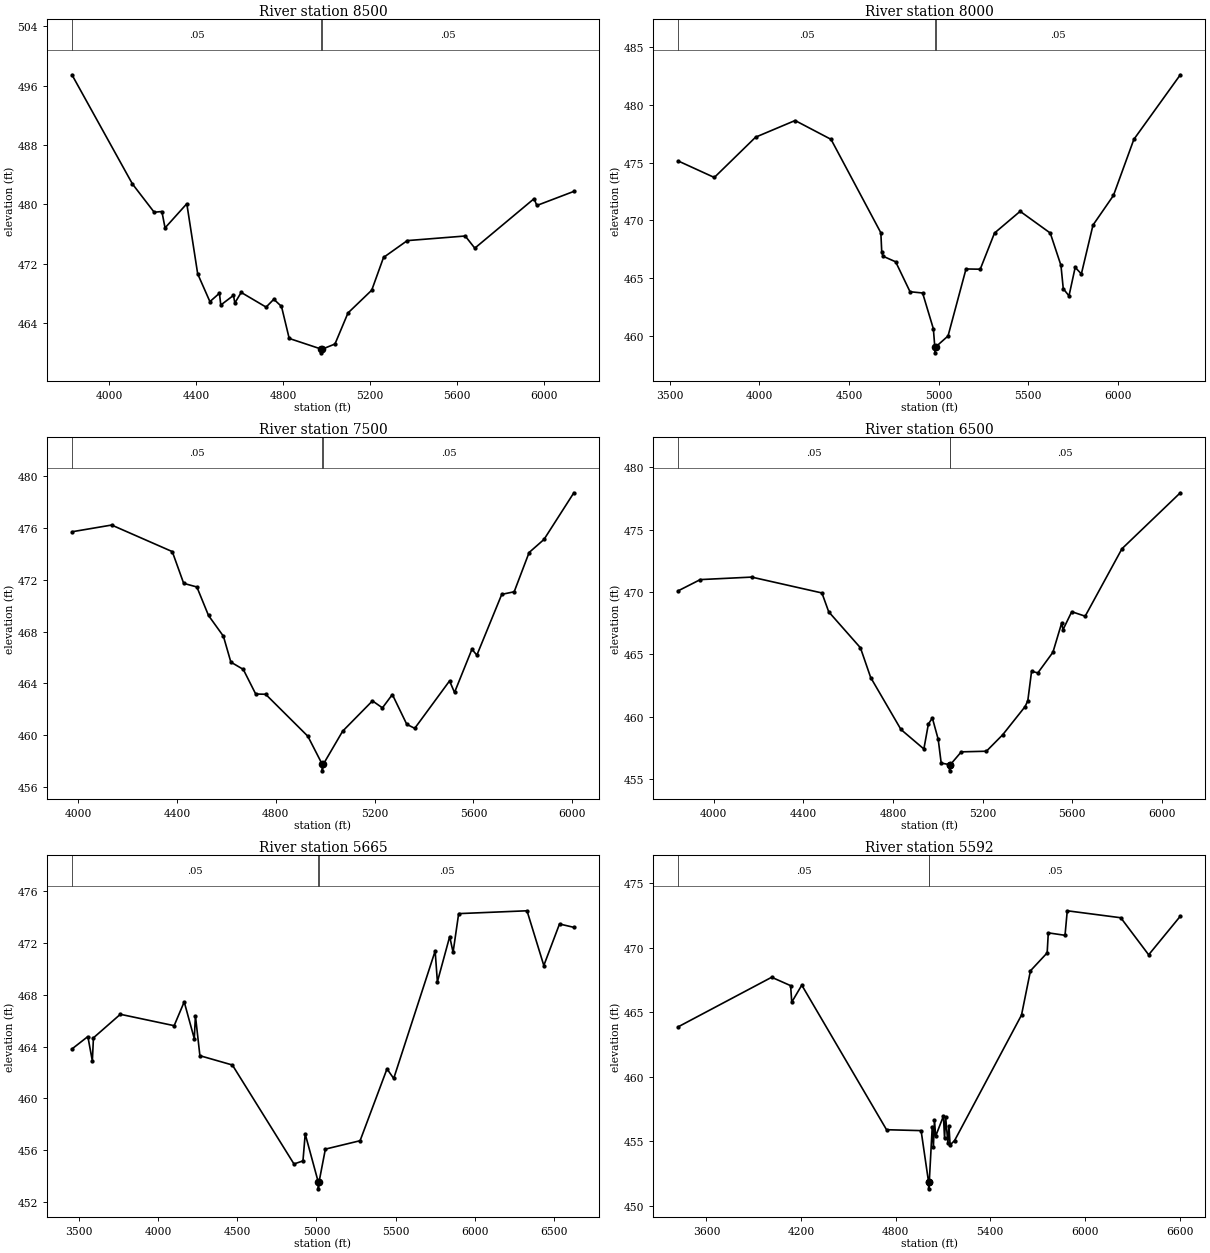
Type RM Length L Ch R = 1,8500,500,500,500
BEGIN DESCRIPTION:
Eagans Branch Trib 2 17.0
END DESCRIPTION:
XS GIS Cut Line= 3
      2668126.01      6922460.99      2667183.97      6923159.40
      2667726.02      6924161.03
#Sta/Elev= 30
  3827.3  497.46  4105.9  482.75  4206.1  478.94  4241.5  479.04  4256.1  476.83
  4356.3  480.09  4406.4  470.64  4462.7  466.90  4506.6  468.03  4512.8  466.44
  4571.3  467.74  4577.5  466.71  4606.7  468.14  4721.5  466.16  4757.0  467.22
  4792.4  466.25  4827.9  461.94  4976.2  460.50  4976.4  460.00  4980.2  460.50
  5038.7  461.19  5098.6  465.37  5208.0  468.44  5262.3  472.85  5371.7  475.12
  5638.6  475.74  5682.7  474.10  5955.8  480.77  5968.3  479.85  6138.9  481.75
#Mann=3,-1,0
  3827.3    0.05       0  4976.2    0.03       0  4980.2    0.05       0
Bank Sta=4976.2,4980.2
Exp/Cntr=0.3,0.1

Type RM Length L Ch R = 1,8000,500,500,500
BEGIN DESCRIPTION:
Eagans Branch Trib 2 16.0
END DESCRIPTION:
XS GIS Cut Line= 3
      2666819.33      6921561.09      2666731.67      6923010.65
      2666376.00      6924310.98
#Sta/Elev= 30
  3547.8  475.14  3748.1  473.72  3978.5  477.21  4198.9  478.65  4399.3  477.02
  4677.3  468.93  4682.3  467.24  4689.8  466.90  4759.9  466.42  4840.1  463.83
  4910.2  463.72  4970.3  460.62  4978.3  459.04  4978.6  458.54  4982.3  459.04
  5052.2  460.00  5152.4  465.80  5231.8  465.78  5311.4  468.91  5454.4  470.79
  5622.4  468.91  5682.1  466.11  5695.0  464.09  5727.0  463.47  5761.5  465.94
  5796.0  465.37  5860.9  469.60  5974.9  472.16  6088.9  477.02  6348.1  482.61
#Mann=3,-1,0
  3547.8    0.05       0  4978.3    0.04       0  4982.3    0.05       0
Bank Sta=4978.3,4982.3
Exp/Cntr=0.3,0.1

Type RM Length L Ch R = 1,7500,1000,1000,1000
BEGIN DESCRIPTION:
Eagans Branch Trib 2 15.0
END DESCRIPTION:
XS GIS Cut Line= 3
      2666159.89      6922091.17      2666263.88      6923110.88
      2666376.00      6924111.01
#Sta/Elev= 30
  3975.0  475.70  4135.7  476.22  4381.1  474.17  4427.2  471.72  4480.6  471.44
  4527.7  469.24  4588.0  467.64  4618.2  465.64  4668.4  465.08  4718.7  463.18
  4758.9  463.16  4929.8  459.92  4988.1  457.75  4988.3  457.25  4992.1  457.75
  5070.6  460.31  5191.3  462.65  5231.6  462.11  5271.8  463.14  5330.2  460.84
  5362.4  460.53  5503.3  464.19  5523.4  463.30  5593.8  466.63  5613.9  466.18
  5714.6  470.87  5764.9  471.07  5825.3  474.10  5885.6  475.11  6006.4  478.71
#Mann=3,-1,0
  3975.0    0.05       0  4988.1    0.03       0  4992.1    0.05       0
Bank Sta=4988.1,4992.1
Exp/Cntr=0.3,0.1

Type RM Length L Ch R = 1,6500,835,835,835
BEGIN DESCRIPTION:
Eagans Branch Trib 2 13.0
END DESCRIPTION:
XS GIS Cut Line= 3
      2665177.20      6922097.62      2665344.11      6923242.22
      2665825.99      6924210.99
#Sta/Elev= 30
  3843.3  470.10  3940.8  470.99  4170.1  471.19  4483.4  469.92  4513.7  468.41
  4655.2  465.53  4700.9  463.15  4835.9  458.99  4938.1  457.43  4958.3  459.43
  4976.0  459.91  5002.1  458.20  5015.4  456.30  5052.5  456.18  5052.7  455.68
  5056.5  456.18  5105.0  457.20  5217.0  457.25  5289.8  458.57  5389.5  460.82
  5401.7  461.29  5418.5  463.65  5446.5  463.52  5513.7  465.17  5552.9  467.52
  5558.5  466.97  5597.7  468.42  5657.6  468.06  5821.7  473.46  6082.0  477.94
#Mann=3,-1,0
  3843.3    0.05       0  5052.5    0.03       0  5056.5    0.05       0
Bank Sta=5052.5,5056.5
Exp/Cntr=0.3,0.1

Type RM Length L Ch R = 1,5665,73,73,73
BEGIN DESCRIPTION:
Mapping XS 3ac8726b
END DESCRIPTION:
XS GIS Cut Line= 3
      2663611.64      6922343.27      2664671.93      6923448.82
      2665809.75      6924625.43
#Sta/Elev= 30
  3456.9  463.81  3557.4  464.77  3585.7  462.88  3592.6  464.67  3762.4  466.49
  4102.1  465.61  4165.6  467.45  4229.4  464.60  4236.4  466.38  4264.7  463.29
  4469.7  462.57  4858.7  454.92  4915.3  455.16  4929.5  457.24  5012.4  453.50
  5012.6  453.00  5016.4  453.50  5056.8  456.07  5276.0  456.72  5445.8  462.27
  5488.2  461.53  5749.8  471.38  5764.0  469.00  5841.7  472.50  5863.0  471.28
  5898.3  474.27  6329.7  474.49  6435.9  470.26  6534.9  473.47  6625.5  473.21
#Mann=3,-1,0
  3456.9    0.05       0  5012.4    0.03       0  5016.4    0.05       0
Bank Sta=5012.4,5016.4
Exp/Cntr=0.3,0.1

Type RM Length L Ch R = 1,5592,1092,1092,1092
BEGIN DESCRIPTION:
Mapping XS 95a35217
END DESCRIPTION:
XS GIS Cut Line= 3
      2663515.70      6922395.08      2664621.20      6923500.58
      2665733.21      6924677.24
#Sta/Elev= 30
  3422.5  463.89  4013.8  467.72  4134.0  467.07  4141.1  465.79  4204.7  467.11
  4742.1  455.91  4961.3  455.84  5008.9  451.83  5009.2  451.33  5012.9  451.83
  5032.0  456.15  5039.3  454.59  5046.1  456.68  5053.4  455.40  5102.8  456.97
  5110.0  455.25  5116.9  456.90  5131.1  454.86  5138.0  456.18  5145.2  454.73
  5173.6  455.07  5597.9  464.79  5654.6  468.22  5760.6  469.61  5767.8  471.16
  5873.8  470.97  5888.0  472.87  6227.4  472.33  6404.2  469.46  6604.9  472.45
#Mann=3,-1,0
  3422.5    0.05       0  5008.9    0.04       0  5012.9    0.05       0
Bank Sta=5008.9,5012.9
Exp/Cntr=0.3,0.1

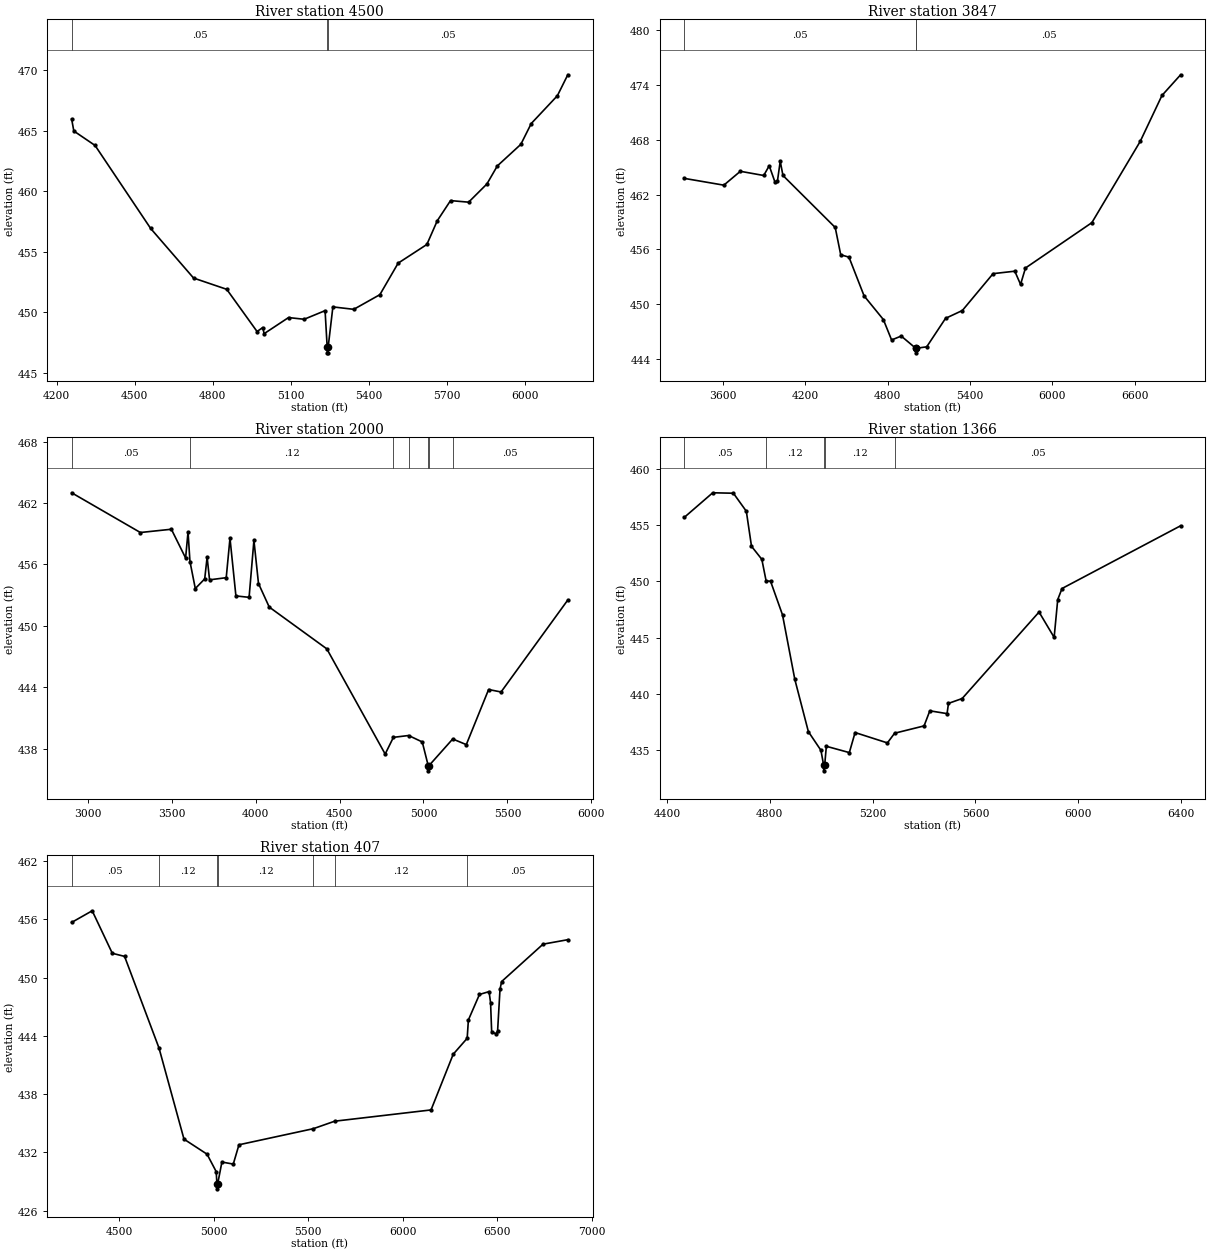
Type RM Length L Ch R = 1,4500,653,653,653
BEGIN DESCRIPTION:
Eagans Branch Trib 2 9.0
END DESCRIPTION:
XS GIS Cut Line= 3
      2663576.01      6923411.02      2663915.53      6924071.46
      2665075.98      6924161.00
#Sta/Elev= 30
  4257.4  465.95  4265.7  464.97  4347.3  463.78  4561.0  456.93  4725.8  452.84
  4853.3  451.91  4969.8  448.43  4992.0  448.76  4996.9  448.25  5090.7  449.58
  5150.9  449.44  5231.2  450.15  5239.2  447.17  5239.4  446.67  5242.9  446.67
  5243.2  447.17  5261.2  450.46  5341.5  450.26  5441.8  451.47  5512.0  454.07
  5622.3  455.61  5662.4  457.57  5713.3  459.23  5782.8  459.10  5853.0  460.60
  5893.1  462.09  5983.4  463.87  6023.5  465.59  6123.8  467.88  6163.9  469.61
#Mann=3,-1,0
  4257.4    0.05       0  5239.2    0.04       0  5243.2    0.05       0
Bank Sta=5239.2,5243.2
Exp/Cntr=0.3,0.1

Type RM Length L Ch R = 1,3847,1847,1847,1847
BEGIN DESCRIPTION:
Eagans Branch Trib 2 8.0
END DESCRIPTION:
XS GIS Cut Line= 3
      2663412.24      6922834.70      2663485.75      6924510.99
      2665075.98      6925610.99
#Sta/Elev= 30
  3322.1  463.77  3608.7  463.03  3728.8  464.55  3899.0  464.09  3939.0  465.16
  3981.3  463.35  3999.0  463.49  4019.1  465.65  4039.1  464.09  4419.5  458.39
  4459.5  455.40  4519.5  455.14  4629.7  450.89  4769.8  448.30  4829.8  446.06
  4899.9  446.49  5005.6  445.15  5005.8  444.65  5009.6  445.15  5085.4  445.31
  5222.5  448.43  5344.8  449.29  5568.5  453.33  5726.6  453.60  5768.5  452.15
  5804.4  453.95  6287.6  458.92  6639.7  467.83  6797.8  472.86  6933.6  475.13
#Mann=3,-1,0
  3322.1    0.05       0  5005.6    0.03       0  5009.6    0.05       0
Bank Sta=5005.6,5009.6
Exp/Cntr=0.3,0.1

Type RM Length L Ch R = 1,2000,634,634,634
BEGIN DESCRIPTION:
Eagans Branch Trib 2 4.0
END DESCRIPTION:
XS GIS Cut Line= 3
      2663270.03      6922860.51      2661966.33      6924501.33
      2662143.31      6925342.62
#Sta/Elev= 30
  2904.3  463.00  3313.6  459.12  3498.2  459.44  3583.1  456.63  3597.5  459.18
  3609.0  456.29  3640.8  453.65  3696.8  454.59  3711.2  456.71  3725.7  454.50
  3825.0  454.71  3847.4  458.56  3882.7  452.93  3961.2  452.79  3990.0  458.35
  4017.2  454.14  4081.3  451.84  4424.2  447.76  4771.8  437.49  4820.9  439.12
  4911.4  439.30  4992.8  438.67  5028.3  436.35  5028.6  435.85  5032.3  436.35
  5174.2  438.96  5255.1  438.41  5388.0  443.79  5462.2  443.55  5859.7  452.53
#Mann=7,-1,0
  2904.3    0.05       0  3609.0    0.12       0  4820.9    0.05       0
  4911.4    0.12       0  5028.3    0.07       0  5032.3    0.12       0
  5174.2    0.05       0
Bank Sta=5028.3,5032.3
Exp/Cntr=0.3,0.1

Type RM Length L Ch R = 1,1366,959,959,959
BEGIN DESCRIPTION:
Eagans Branch Trib 2 3.0
END DESCRIPTION:
XS GIS Cut Line= 3
      2661505.03      6923681.65      2661450.80      6924210.68
      2662075.99      6925460.98
#Sta/Elev= 30
  4468.2  455.70  4578.1  457.87  4658.5  457.83  4708.8  456.23  4728.9  453.12
  4769.1  451.96  4785.7  450.05  4803.1  450.01  4849.5  447.03  4897.4  441.30
  4950.1  436.66  4999.0  435.00  5009.5  433.68  5009.8  433.18  5013.5  433.68
  5020.0  435.36  5109.4  434.80  5131.8  436.58  5257.5  435.66  5285.5  436.52
  5400.1  437.17  5422.5  438.51  5489.5  438.26  5495.1  439.17  5548.2  439.60
  5847.3  447.28  5906.0  445.03  5920.0  448.39  5936.7  449.37  6397.9  454.94
#Mann=5,-1,0
  4468.2    0.05       0  4785.7    0.12       0  5009.5    0.07       0
  5013.5    0.12       0  5285.5    0.05       0
Bank Sta=5009.5,5013.5
Exp/Cntr=0.3,0.1

Type RM Length L Ch R = 1,407,0,0,0
BEGIN DESCRIPTION:
Eagans Branch Trib 2 2.0
END DESCRIPTION:
XS GIS Cut Line= 4
      2661097.73      6923681.61      2660652.49      6924288.00
      2660632.25      6924547.93      2662026.01      6925361.01
#Sta/Elev= 30
  4247.7  455.69  4356.4  456.89  4462.9  452.51  4527.8  452.19  4710.1  442.75
  4842.4  433.36  4964.5  431.81  5013.0  430.01  5016.6  428.74  5016.9  428.24
  5020.6  428.74  5043.1  431.00  5103.3  430.79  5133.4  432.78  5527.5  434.44
  5640.3  435.21  6150.3  436.37  6267.7  442.11  6341.6  443.75  6348.0  445.64
  6406.7  448.27  6457.5  448.56  6465.4  447.43  6471.2  444.44  6492.7  444.21
  6502.6  444.49  6515.4  448.81  6524.1  449.60  6743.2  453.45  6874.3  453.91
#Mann=7,-1,0
  4247.7    0.05       0  4710.1    0.12       0  5016.6    0.07       0
  5020.6    0.12       0  5527.5    0.05       0  5640.3    0.12       0
  6341.6    0.05       0
Bank Sta=5016.6,5020.6
Exp/Cntr=0.3,0.1

Chan Stop Cuts=-1