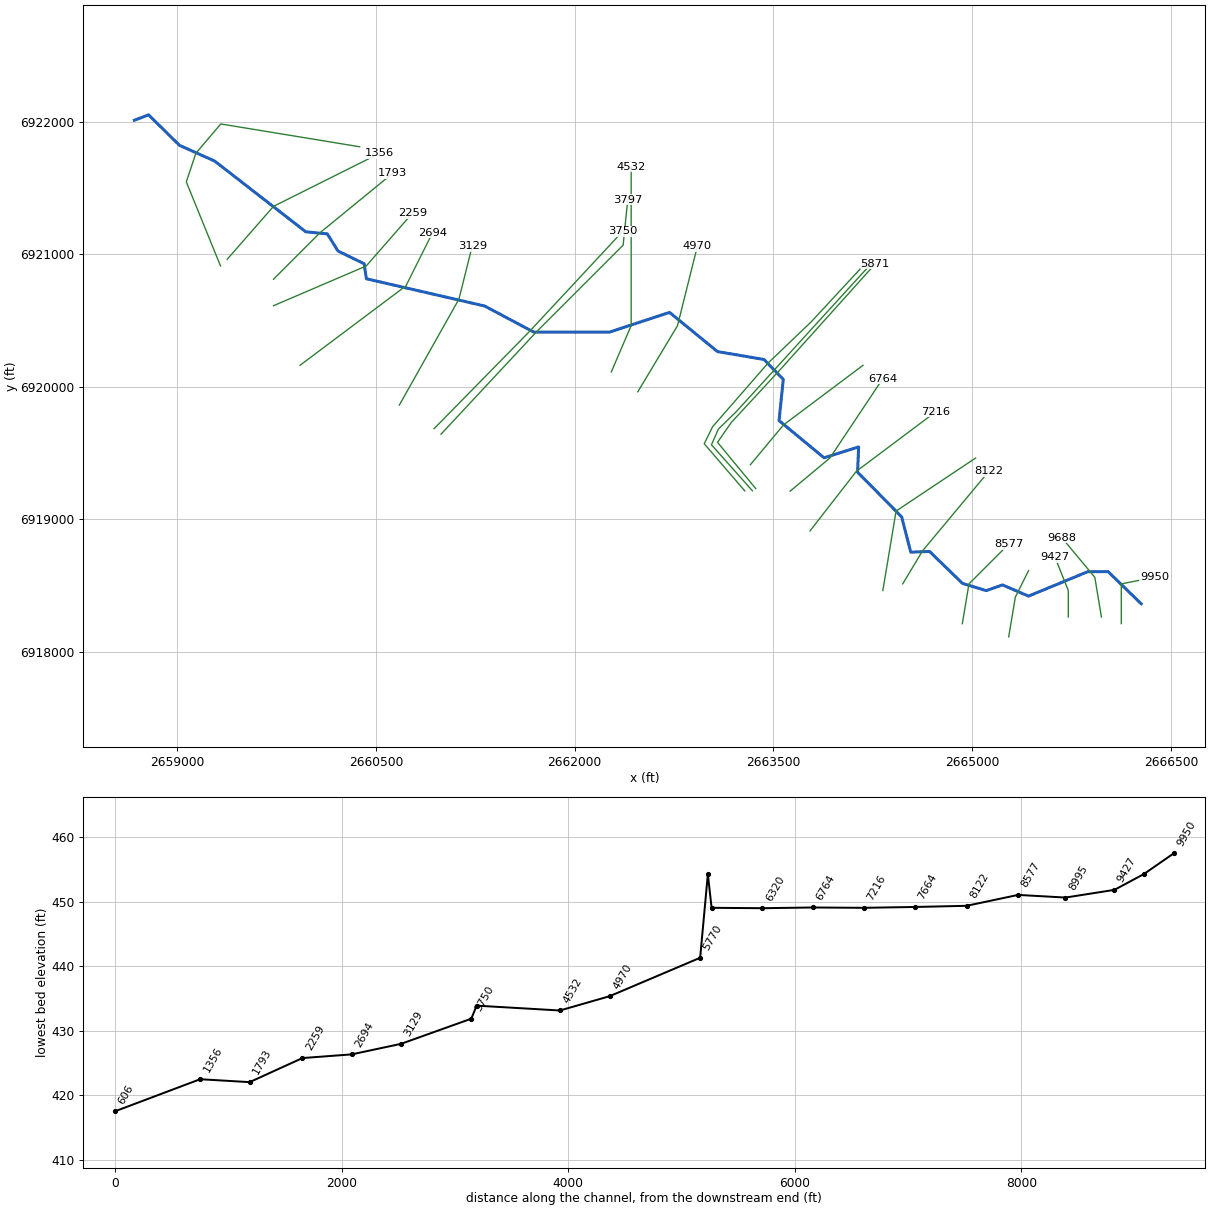
--- Eagans Branch Trib 3.prj (project) ---

Proj Title=Eagans Branch Trib 3 Base Level Engineering
Current Plan=p01
Default Exp/Contr=0.3,0.1
English Units
Geom File=g01
Flow File=f01
Plan File=p01
BEGIN DESCRIPTION:
Eagans Branch Trib 3
END DESCRIPTION:

--- Eagans Branch Trib 3.p01 (plan) ---

Plan Title=Multiple Run
Short Identifier=Multiple
Geom File=g01
Flow File=f01
Subcritical Flow
K Sum by GR= 0
Std Step Tol= 0.01
Critical Tol= 0.01
Num of Std Step Trials= 20
Max Error Tol= 0.3
Flow Tol Ratio= 0.001
Split Flow NTrial= 30
Split Flow Tol= 0.02
Split Flow Ratio= 0.02
Log Output Level= 0
Friction Slope Method= 1
Unsteady Friction Slope Method= 2
Unsteady Bridges Friction Slope Method= 1
Parabolic Critical Depth
Global Vel Dist=  1 , 1 , 1
Global Log Level= 0
CheckData=True
Encroach Param= -1, 0, 0, 0
BEGIN DESCRIPTION:
Multiple Run
END DESCRIPTION:

--- Eagans Branch Trib 3.f01 (steady flow) ---

Flow Title=Multiple
Number of Profiles=7
Profile Names=10-year,25-year,50-year,1pct_min,100-year,1pct_plu,500-year
River Rch & RM= Eagans Branch Tr,Reach-1,9950
     439     579     690     409     816    1628    1139
River Rch & RM= Eagans Branch Tr,Reach-1,7664
     716     973    1183     713    1423    2839    2059
River Rch & RM= Eagans Branch Tr,Reach-1,3797
     837    1146    1400     847    1690    3373    2466
Boundary for River Rch & Prof#=Eagans Branch Tr,Reach-1,1
Up Type=0
Dn Type=3
Dn Slope=0.005
Boundary for River Rch & Prof#=Eagans Branch Tr,Reach-1,2
Up Type=0
Dn Type=3
Dn Slope=0.005
Boundary for River Rch & Prof#=Eagans Branch Tr,Reach-1,3
Up Type=0
Dn Type=3
Dn Slope=0.005
Boundary for River Rch & Prof#=Eagans Branch Tr,Reach-1,4
Up Type=0
Dn Type=3
Dn Slope=0.005
Boundary for River Rch & Prof#=Eagans Branch Tr,Reach-1,5
Up Type=0
Dn Type=3
Dn Slope=0.005
Boundary for River Rch & Prof#=Eagans Branch Tr,Reach-1,6
Up Type=0
Dn Type=3
Dn Slope=0.005
Boundary for River Rch & Prof#=Eagans Branch Tr,Reach-1,7
Up Type=0
Dn Type=3
Dn Slope=0.005

--- Eagans Branch Trib 3.g01 (geometry) ---

Geom Title=Existing Conditions

River Reach=Eagans Branch Tr,Reach-1
Reach XY= 30
      2666276.00      6918361.00      2666026.09      6918603.65
      2665872.59      6918603.18      2665425.90      6918418.78
      2665229.42      6918503.17      2665105.96      6918460.42
      2664927.50      6918514.61      2664678.29      6918755.88
      2664536.47      6918750.47      2664467.87      6919017.07
      2664135.15      6919354.27      2664143.18      6919544.91
      2663881.89      6919462.96      2663542.27      6919743.86
      2663574.38      6920054.97      2663428.30      6920205.17
      2663077.52      6920264.74      2662715.52      6920560.45
      2662262.08      6920411.68      2661691.22      6920411.52
      2661320.07      6920608.75      2660427.00      6920814.54
      2660409.76      6920928.04      2660212.44      6921024.48
      2660132.47      6921153.30      2659969.81      6921168.83
      2659282.06      6921702.86      2659016.30      6921821.76
      2658782.71      6922052.01      2658676.00      6922011.00

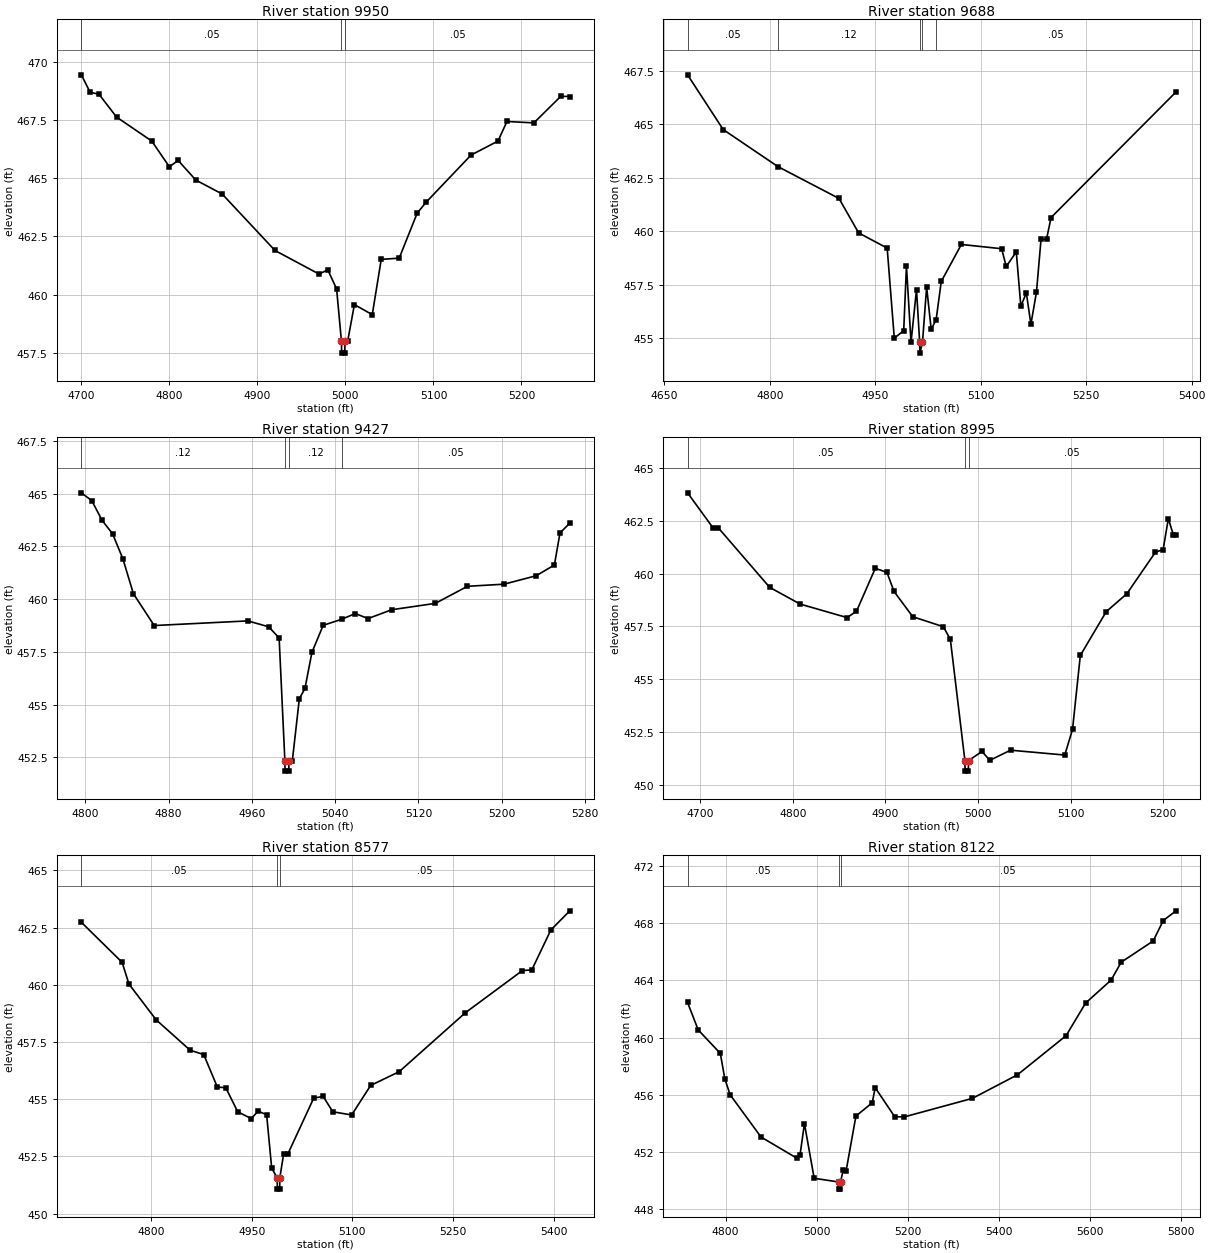
Type RM Length L Ch R = 1,9950,262,262,262
BEGIN DESCRIPTION:
Eagans Branch Trib 3 22.0
END DESCRIPTION:
XS GIS Cut Line= 3
      2666126.00      6918211.05      2666126.00      6918511.00
      2666375.99      6918561.00
#Sta/Elev= 30
  4700.0  469.43  4710.0  468.68  4720.0  468.60  4740.0  467.62  4780.0  466.59
  4800.0  465.49  4810.0  465.76  4830.0  464.92  4860.0  464.32  4920.0  461.90
  4970.0  460.89  4980.0  461.07  4990.0  460.25  4995.5  458.00  4995.7  457.50
  4999.2  457.50  4999.5  458.00  5002.5  458.00  5010.2  459.58  5030.5  459.15
  5040.7  461.52  5061.1  461.57  5081.5  463.50  5091.7  463.97  5142.7  465.99
  5173.3  466.59  5183.5  467.43  5214.1  467.37  5244.7  468.51  5254.9  468.50
#Mann=3,-1,0
  4700.0    0.05       0  4995.5    0.05       0  4999.5    0.05       0
Bank Sta=4995.5,4999.5
Exp/Cntr=0.3,0.1

Type RM Length L Ch R = 1,9688,261,261,261
BEGIN DESCRIPTION:
Eagans Branch Trib 3 21.0
END DESCRIPTION:
XS GIS Cut Line= 3
      2665976.00      6918260.98      2665926.00      6918561.00
      2665675.98      6918861.03
#Sta/Elev= 30
  4683.1  467.32  4733.8  464.76  4811.6  463.03  4898.5  461.54  4926.4  459.93
  4967.0  459.22  4977.1  455.01  4990.5  455.36  4994.4  458.38  5000.9  454.81
  5008.7  457.28  5013.2  454.81  5013.5  454.31  5017.2  454.81  5023.1  457.40
  5029.6  455.42  5036.6  455.87  5043.9  457.66  5072.5  459.39  5129.8  459.19
  5136.3  458.36  5150.6  459.04  5157.1  456.50  5164.9  457.13  5171.4  455.66
  5179.3  457.16  5185.8  459.63  5193.6  459.63  5200.1  460.65  5377.8  466.52
#Mann=5,-1,0
  4683.1    0.05       0  4811.6    0.12       0  5013.2    0.07       0
  5017.2    0.12       0  5036.6    0.05       0
Bank Sta=5013.2,5017.2
Exp/Cntr=0.3,0.1

Type RM Length L Ch R = 1,9427,432,432,432
BEGIN DESCRIPTION:
Eagans Branch Trib 3 20.0
END DESCRIPTION:
XS GIS Cut Line= 3
      2665726.00      6918261.03      2665726.00      6918461.00
      2665626.01      6918710.97
#Sta/Elev= 30
  4796.2  465.04  4806.2  464.67  4816.2  463.73  4826.2  463.10  4836.2  461.90
  4846.2  460.26  4866.2  458.75  4956.2  458.97  4976.2  458.69  4986.2  458.16
  4991.7  452.35  4991.9  451.85  4995.4  451.85  4995.7  452.35  4998.9  452.35
  5005.6  455.28  5011.0  455.77  5017.7  457.48  5028.5  458.76  5046.4  459.05
  5059.4  459.32  5071.6  459.08  5094.4  459.50  5136.2  459.80  5167.1  460.61
  5202.2  460.71  5233.1  461.11  5250.6  461.62  5256.0  463.14  5265.4  463.60
#Mann=4,-1,0
  4796.2    0.12       0  4991.7    0.07       0  4995.7    0.12       0
  5046.4    0.05       0
Bank Sta=4991.7,4995.7
Exp/Cntr=0.3,0.1

Type RM Length L Ch R = 1,8995,418,418,418
BEGIN DESCRIPTION:
Eagans Branch Trib 3 19.0
END DESCRIPTION:
XS GIS Cut Line= 3
      2665276.00      6918111.01      2665326.00      6918411.00
      2665425.98      6918610.97
#Sta/Elev= 30
  4686.3  463.82  4714.2  462.14  4719.2  462.18  4775.0  459.35  4807.9  458.56
  4858.6  457.92  4868.8  458.22  4889.1  460.25  4901.7  460.06  4909.3  459.16
  4929.6  457.96  4962.6  457.49  4970.2  456.89  4985.9  451.16  4986.1  450.66
  4989.6  450.66  4989.9  451.16  5004.4  451.59  5012.8  451.17  5035.2  451.65
  5093.8  451.42  5102.2  452.64  5110.6  456.13  5138.6  458.20  5160.9  459.05
  5191.7  461.01  5200.1  461.14  5205.7  462.60  5211.2  461.82  5214.0  461.82
#Mann=3,-1,0
  4686.3    0.05       0  4985.9    0.03       0  4989.9    0.05       0
Bank Sta=4985.9,4989.9
Exp/Cntr=0.3,0.1

Type RM Length L Ch R = 1,8577,455,455,455
BEGIN DESCRIPTION:
Eagans Branch Trib 3 18.0
END DESCRIPTION:
XS GIS Cut Line= 3
      2664926.00      6918210.99      2664976.00      6918511.00
      2665275.99      6918810.99
#Sta/Elev= 30
  4695.9  462.73  4756.7  460.98  4766.9  460.03  4807.4  458.47  4858.1  457.14
  4878.4  456.95  4898.7  455.53  4911.3  455.50  4929.1  454.45  4949.4  454.15
  4959.5  454.48  4972.2  454.32  4979.8  451.98  4987.9  451.57  4988.2  451.07
  4991.7  451.07  4991.9  451.57  4997.5  452.59  5003.6  452.59  5042.5  455.05
  5056.6  455.12  5070.8  454.45  5099.0  454.31  5127.3  455.60  5169.8  456.20
  5268.7  458.78  5353.6  460.62  5367.7  460.65  5396.0  462.39  5424.3  463.23
#Mann=3,-1,0
  4695.9    0.05       0  4987.9    0.03       0  4991.9    0.05       0
Bank Sta=4987.9,4991.9
Exp/Cntr=0.3,0.1

Type RM Length L Ch R = 1,8122,458,458,458
BEGIN DESCRIPTION:
Eagans Branch Trib 3 17.0
END DESCRIPTION:
XS GIS Cut Line= 3
      2664475.99      6918510.99      2664626.00      6918761.00
      2665126.01      6919361.01
#Sta/Elev= 30
  4716.4  462.46  4739.7  460.54  4788.3  458.89  4798.1  457.13  4809.7  456.00
  4877.7  453.03  4957.4  451.53  4963.3  451.76  4973.0  453.97  4994.4  450.14
  5048.3  449.88  5048.5  449.38  5052.0  449.38  5052.3  449.88  5058.1  450.71
  5064.6  450.67  5086.1  454.50  5121.9  455.43  5128.4  456.49  5171.3  454.45
  5192.2  454.44  5341.9  455.74  5440.8  457.39  5547.5  460.13  5590.5  462.42
  5646.5  464.03  5668.6  465.28  5738.9  466.77  5761.0  468.20  5789.0  468.88
#Mann=3,-1,0
  4716.4    0.05       0  5048.3    0.03       0  5052.3    0.05       0
Bank Sta=5048.3,5052.3
Exp/Cntr=0.3,0.1

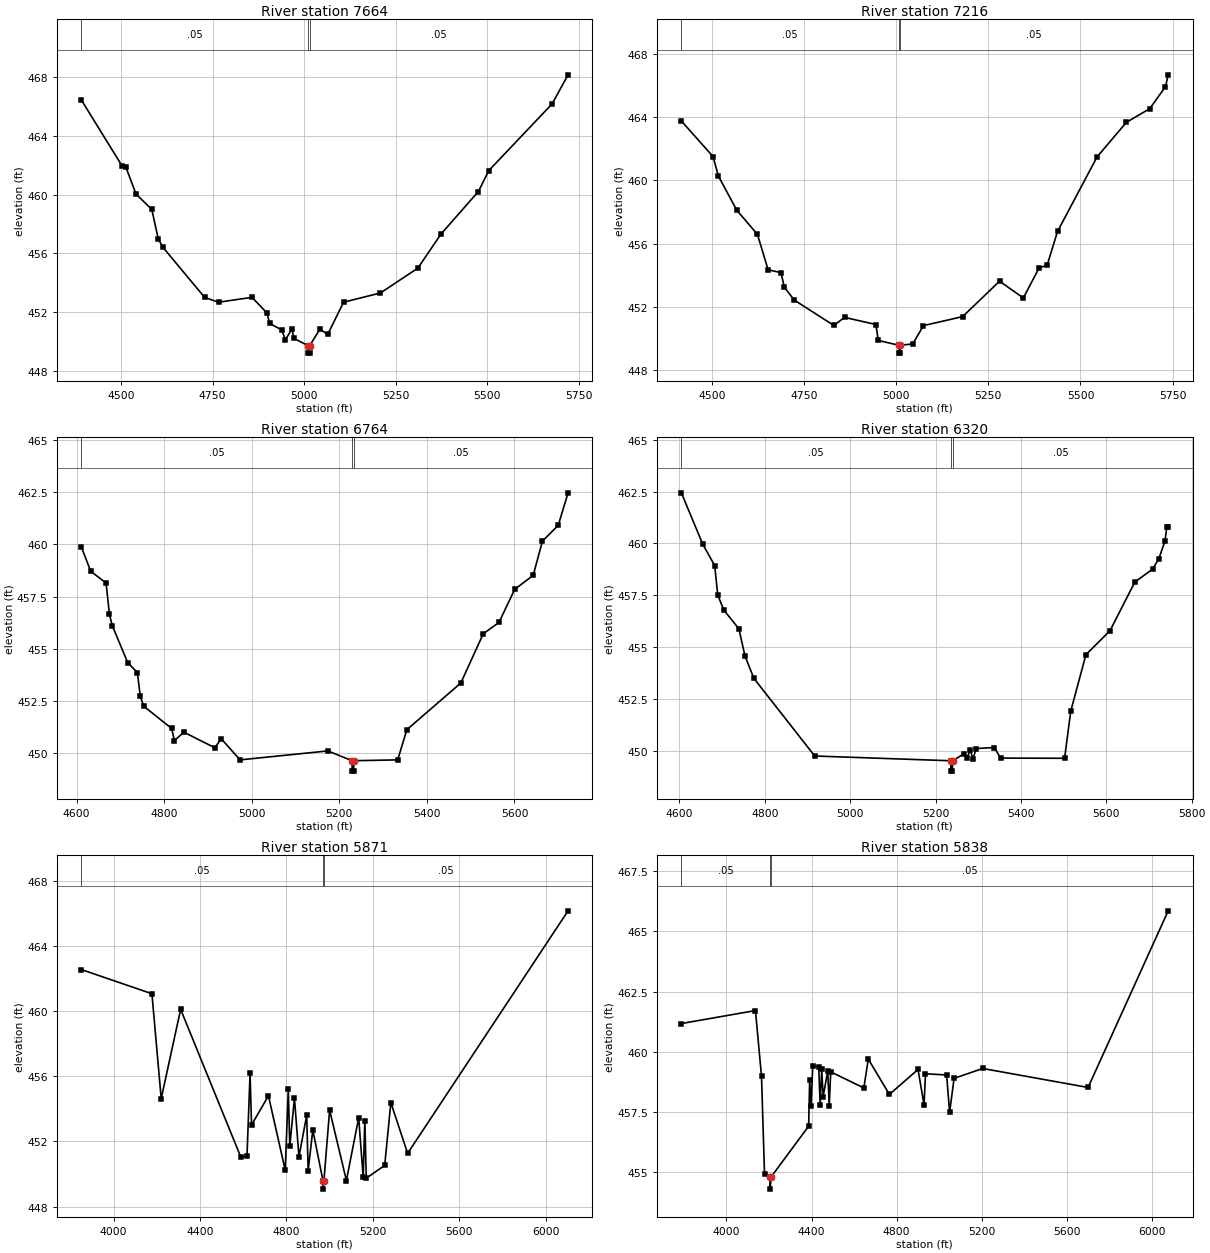
Type RM Length L Ch R = 1,7664,448,448,448
BEGIN DESCRIPTION:
Eagans Branch Trib 3 16.0
END DESCRIPTION:
XS GIS Cut Line= 3
      2664326.00      6918461.02      2664426.00      6919061.00
      2665026.03      6919461.02
#Sta/Elev= 30
  4391.3  466.46  4502.8  461.95  4512.9  461.89  4540.8  460.04  4583.9  458.99
  4601.6  456.98  4614.3  456.41  4728.4  452.99  4766.4  452.67  4857.6  453.00
  4898.2  451.94  4905.8  451.22  4938.7  450.78  4948.9  450.11  4966.6  450.85
  4971.7  450.21  5011.1  449.70  5011.3  449.20  5014.8  449.20  5015.1  449.70
  5043.1  450.84  5064.2  450.47  5107.7  452.67  5208.4  453.30  5310.5  454.99
  5373.6  457.31  5475.8  460.21  5504.3  461.64  5677.1  466.18  5720.7  468.16
#Mann=3,-1,0
  4391.3    0.05       0  5011.1    0.03       0  5015.1    0.05       0
Bank Sta=5011.1,5015.1
Exp/Cntr=0.3,0.1

Type RM Length L Ch R = 1,7216,452,452,452
BEGIN DESCRIPTION:
Eagans Branch Trib 3 15.0
END DESCRIPTION:
XS GIS Cut Line= 3
      2663776.02      6918911.03      2664126.00      6919361.00
      2664726.04      6919811.03
#Sta/Elev= 30
  4417.7  463.75  4503.6  461.50  4518.1  460.27  4567.9  458.11  4624.0  456.58
  4652.9  454.34  4688.2  454.16  4696.4  453.26  4723.5  452.43  4831.2  450.82
  4860.2  451.33  4945.2  450.88  4951.6  449.87  5007.6  449.57  5007.9  449.07
  5011.4  449.07  5011.6  449.57  5045.0  449.65  5074.2  450.81  5180.5  451.38
  5280.5  453.62  5345.0  452.56  5387.8  454.46  5409.6  454.63  5437.8  456.77
  5545.0  461.48  5624.2  463.66  5687.8  464.53  5730.5  465.92  5737.8  466.67
#Mann=3,-1,0
  4417.7    0.05       0  5007.6    0.03       0  5011.6    0.05       0
Bank Sta=5007.6,5011.6
Exp/Cntr=0.3,0.1

Type RM Length L Ch R = 1,6764,444,444,444
BEGIN DESCRIPTION:
Eagans Branch Trib 3 14.0
END DESCRIPTION:
XS GIS Cut Line= 3
      2663626.02      6919211.02      2663926.00      6919461.00
      2664326.01      6920061.01
#Sta/Elev= 30
  4610.8  459.90  4632.2  458.72  4667.4  458.15  4675.2  456.64  4681.7  456.10
  4716.9  454.33  4739.0  453.85  4745.5  452.72  4753.3  452.24  4817.1  451.17
  4823.6  450.59  4845.1  450.99  4916.0  450.24  4930.3  450.68  4973.3  449.66
  5174.0  450.09  5229.1  449.62  5229.4  449.12  5232.9  449.12  5233.1  449.62
  5333.3  449.66  5354.3  451.11  5477.5  453.35  5528.6  455.71  5564.6  456.26
  5600.7  457.85  5642.8  458.52  5663.8  460.16  5699.9  460.92  5722.4  462.48
#Mann=3,-1,0
  4610.8    0.05       0  5229.1    0.03       0  5233.1    0.05       0
Bank Sta=5229.1,5233.1
Exp/Cntr=0.3,0.1

Type RM Length L Ch R = 1,6320,449,449,449
BEGIN DESCRIPTION:
Eagans Branch Trib 3 13.0
END DESCRIPTION:
XS GIS Cut Line= 3
      2663326.03      6919411.03      2663576.00      6919711.00
      2664176.02      6920161.02
#Sta/Elev= 30
  4604.5  462.44  4654.6  459.96  4682.6  458.93  4689.7  457.51  4704.0  456.78
  4739.2  455.88  4753.5  454.57  4774.3  453.49  4916.9  449.74  5235.7  449.51
  5235.9  449.01  5239.4  449.01  5239.7  449.51  5266.8  449.85  5273.1  449.63
  5281.4  450.02  5287.7  449.59  5295.0  450.10  5337.7  450.15  5352.3  449.64
  5502.3  449.63  5516.8  451.91  5552.3  454.63  5608.5  455.78  5666.8  458.13
  5708.5  458.76  5723.1  459.26  5737.7  460.13  5741.8  460.80  5745.0  460.80
#Mann=3,-1,0
  4604.5    0.05       0  5235.7    0.03       0  5239.7    0.05       0
Bank Sta=5235.7,5239.7
Exp/Cntr=0.3,0.1

Type RM Length L Ch R = 1,5871,33,33,33
BEGIN DESCRIPTION:
Mapping XS 1513565b
END DESCRIPTION:
XS GIS Cut Line= 6
      2663366.30      6919230.53      2663077.68      6919579.91
      2663181.85      6919729.65      2663535.58      6920111.60
      2663999.99      6920628.09      2664268.38      6920926.78
#Sta/Elev= 30
  3850.7  462.58  4177.6  461.09  4220.6  454.64  4310.5  460.13  4589.2  451.03
  4617.5  451.11  4631.7  456.19  4638.5  453.02  4716.8  454.81  4794.4  450.23
  4808.6  455.20  4815.4  451.70  4837.0  454.67  4857.9  451.06  4893.7  453.61
  4900.5  450.21  4922.0  452.71  4969.3  449.57  4969.6  449.07  4973.3  449.57
  4999.7  453.93  5077.4  449.60  5134.2  453.46  5155.1  449.81  5162.6  453.29
  5169.3  449.74  5254.6  450.53  5283.0  454.39  5360.7  451.27  6103.0  466.19
#Mann=3,-1,0
  3850.7    0.05       0  4969.3    0.03       0  4973.3    0.05       0
Bank Sta=4969.3,4973.3
Exp/Cntr=0.3,0.1

Type RM Length L Ch R = 1,5838,68,68,68
BEGIN DESCRIPTION:
Mapping XS 2b61d6dd
END DESCRIPTION:
XS GIS Cut Line= 6
      2663341.13      6919214.03      2663032.11      6919561.25
      2663084.19      6919679.30      2663219.61      6919811.25
      2664184.88      6920870.28      2664236.95      6920922.35
#Sta/Elev= 30
  3787.8  461.17  4136.2  461.71  4164.7  458.98  4178.9  454.89  4205.3  454.78
  4205.5  454.28  4209.3  454.78  4386.4  456.90  4391.2  458.83  4398.2  457.73
  4405.4  459.39  4433.6  459.38  4440.6  457.78  4447.8  459.26  4454.8  458.13
  4476.1  459.20  4483.1  457.73  4490.2  459.16  4645.9  458.49  4666.9  459.69
  4766.2  458.22  4900.7  459.26  4929.1  457.79  4935.9  459.08  5035.2  459.03
  5049.4  457.48  5070.4  458.89  5205.2  459.30  5700.6  458.51  6077.3  465.86
#Mann=3,-1,0
  3787.8    0.05       0  4205.3    0.03       0  4209.3    0.05       0
Bank Sta=4205.3,4209.3
Exp/Cntr=0.3,0.1

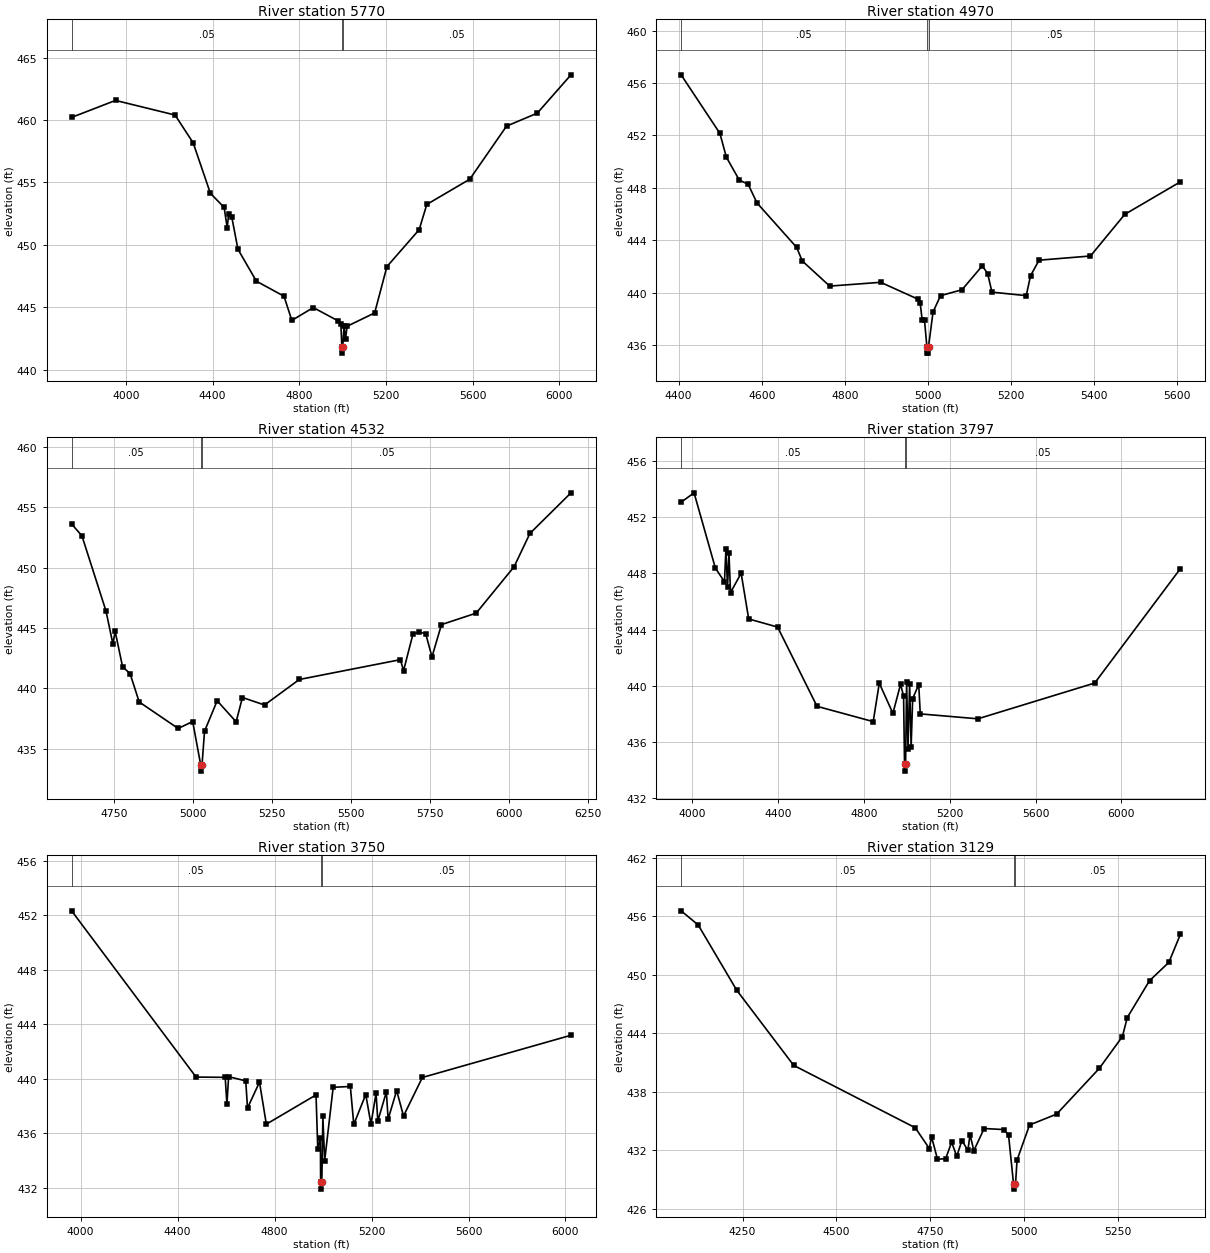
Type RM Length L Ch R = 1,5770,800,800,800
BEGIN DESCRIPTION:
Mapping XS 6b39ae41
END DESCRIPTION:
XS GIS Cut Line= 6
      2663283.58      6919213.13      2662977.61      6919569.01
      2663040.54      6919697.04      2663459.49      6920178.05
      2663784.90      6920489.15      2664195.06      6920931.86
#Sta/Elev= 30
  3750.1  460.21  3952.6  461.57  4227.2  460.40  4310.8  458.17  4390.2  454.13
  4453.7  453.00  4467.9  451.36  4474.6  452.49  4488.8  452.24  4517.3  449.65
  4602.5  447.09  4729.7  445.89  4766.0  443.95  4864.8  444.98  4977.8  443.93
  4992.1  443.67  4996.7  441.83  4996.9  441.33  5000.7  441.83  5006.8  443.52
  5013.7  442.46  5020.9  443.48  5148.0  444.55  5204.6  448.26  5353.4  451.22
  5388.6  453.24  5586.9  455.26  5756.4  459.51  5898.2  460.55  6053.7  463.62
#Mann=3,-1,0
  3750.1    0.05       0  4996.7    0.03       0  5000.7    0.05       0
Bank Sta=4996.7,5000.7
Exp/Cntr=0.3,0.1

Type RM Length L Ch R = 1,4970,438,438,438
BEGIN DESCRIPTION:
Eagans Branch Trib 3 10.0
END DESCRIPTION:
XS GIS Cut Line= 3
      2662475.99      6919960.99      2662776.00      6920461.00
      2662926.01      6921061.02
#Sta/Elev= 30
  4405.9  456.63  4499.2  452.16  4514.8  450.34  4545.9  448.59  4567.2  448.27
  4588.6  446.84  4683.9  443.45  4697.5  442.41  4763.5  440.49  4886.0  440.78
  4975.4  439.50  4981.2  439.18  4986.1  437.89  4991.6  437.89  4997.3  435.87
  4997.6  435.37  5001.1  435.37  5001.3  435.87  5012.2  438.52  5030.2  439.76
  5081.8  440.21  5130.7  442.04  5143.6  441.44  5153.9  440.03  5236.4  439.76
  5246.7  441.28  5267.3  442.47  5391.0  442.79  5473.5  445.97  5607.5  448.46
#Mann=3,-1,0
  4405.9    0.05       0  4997.3    0.05       0  5001.3    0.05       0
Bank Sta=4997.3,5001.3
Exp/Cntr=0.3,0.1

Type RM Length L Ch R = 1,4532,735,735,735
BEGIN DESCRIPTION:
Eagans Branch Trib 3 9.0
END DESCRIPTION:
XS GIS Cut Line= 3
      2662276.02      6920111.04      2662426.00      6920461.00
      2662426.00      6921660.95
#Sta/Elev= 30
  4614.6  453.60  4647.2  452.62  4723.4  446.40  4745.1  443.69  4752.4  444.71
  4775.9  441.79  4799.5  441.23  4828.5  438.88  4951.8  436.69  4997.8  437.26
  5023.3  433.66  5023.6  433.16  5027.3  433.66  5035.3  436.46  5075.3  438.98
  5135.3  437.24  5155.3  439.25  5225.3  438.63  5335.3  440.74  5655.3  442.38
  5665.3  441.47  5695.3  444.52  5715.3  444.65  5735.3  444.54  5755.3  442.61
  5785.3  445.28  5895.3  446.23  6015.3  450.07  6065.3  452.82  6195.3  456.18
#Mann=3,-1,0
  4614.6    0.05       0  5023.3    0.05       0  5027.3    0.05       0
Bank Sta=5023.3,5027.3
Exp/Cntr=0.3,0.1

Type RM Length L Ch R = 1,3797,47,47,47
BEGIN DESCRIPTION:
Mapping XS b4fe13e2
END DESCRIPTION:
XS GIS Cut Line= 4
      2660990.43      6919641.10      2661712.66      6920415.41
      2662365.44      6921068.19      2662400.16      6921411.92
#Sta/Elev= 30
  3947.7  453.08  4008.1  453.75  4107.3  448.39  4149.8  447.41  4156.7  449.78
  4164.0  447.01  4170.8  449.44  4178.1  446.64  4227.5  448.02  4262.7  444.76
  4397.5  444.18  4581.2  438.53  4843.1  437.44  4871.4  440.18  4934.9  438.03
  4970.6  440.10  4984.7  439.26  4989.1  434.41  4989.7  433.91  4994.0  434.41
  4998.9  440.24  5005.3  435.52  5012.9  440.13  5019.9  435.65  5027.0  439.08
  5055.3  440.08  5062.4  437.99  5331.1  437.64  5875.5  440.19  6275.2  448.35
#Mann=3,-1,0
  3947.7    0.05       0  4989.1    0.04       0  4994.0    0.05       0
Bank Sta=4989.1,4994
Exp/Cntr=0.3,0.1

Type RM Length L Ch R = 1,3750,621,621,621
BEGIN DESCRIPTION:
Mapping XS 546b4c7f
END DESCRIPTION:
XS GIS Cut Line= 3
      2660938.37      6919682.79      2661657.11      6920415.41
      2662361.48      6921171.83
#Sta/Elev= 30
  3962.8  452.33  4476.1  440.12  4596.3  440.10  4603.4  438.12  4610.4  440.15
  4681.1  439.84  4688.3  437.84  4737.7  439.75  4766.0  436.66  4971.0  438.81
  4978.2  434.82  4989.1  435.67  4989.9  432.39  4990.5  431.89  4994.8  432.39
  4999.2  437.23  5006.5  433.97  5041.7  439.37  5112.6  439.43  5126.7  436.64
  5176.1  438.84  5197.6  436.67  5218.6  438.93  5225.9  436.89  5261.1  439.03
  5268.4  437.03  5303.6  439.13  5331.9  437.26  5409.6  440.09  6022.7  443.19
#Mann=3,-1,0
  3962.8    0.05       0  4989.9    0.04       0  4994.8    0.05       0
Bank Sta=4989.9,4994.8
Exp/Cntr=0.3,0.1

Type RM Length L Ch R = 1,3129,435,435,435
BEGIN DESCRIPTION:
Eagans Branch Trib 3 6.0
END DESCRIPTION:
XS GIS Cut Line= 3
      2660676.02      6919861.04      2661126.00      6920661.00
      2661225.99      6921060.95
#Sta/Elev= 30
  4086.4  456.55  4131.9  455.10  4234.6  448.40  4386.3  440.69  4710.1  434.29
  4747.7  432.15  4753.4  433.38  4769.3  431.06  4791.0  431.11  4807.0  432.80
  4820.7  431.36  4834.4  432.98  4850.3  431.97  4856.0  433.58  4866.2  431.94
  4893.6  434.21  4946.9  434.10  4958.7  433.50  4972.0  428.49  4972.7  427.99
  4977.1  428.49  4981.3  430.98  5014.5  434.57  5086.7  435.69  5200.1  440.37
  5261.9  443.65  5274.8  445.59  5334.1  449.38  5385.6  451.26  5416.5  454.15
#Mann=3,-1,0
  4086.4    0.05       0  4972.0    0.04       0  4977.1    0.05       0
Bank Sta=4972,4977.1
Exp/Cntr=0.3,0.1

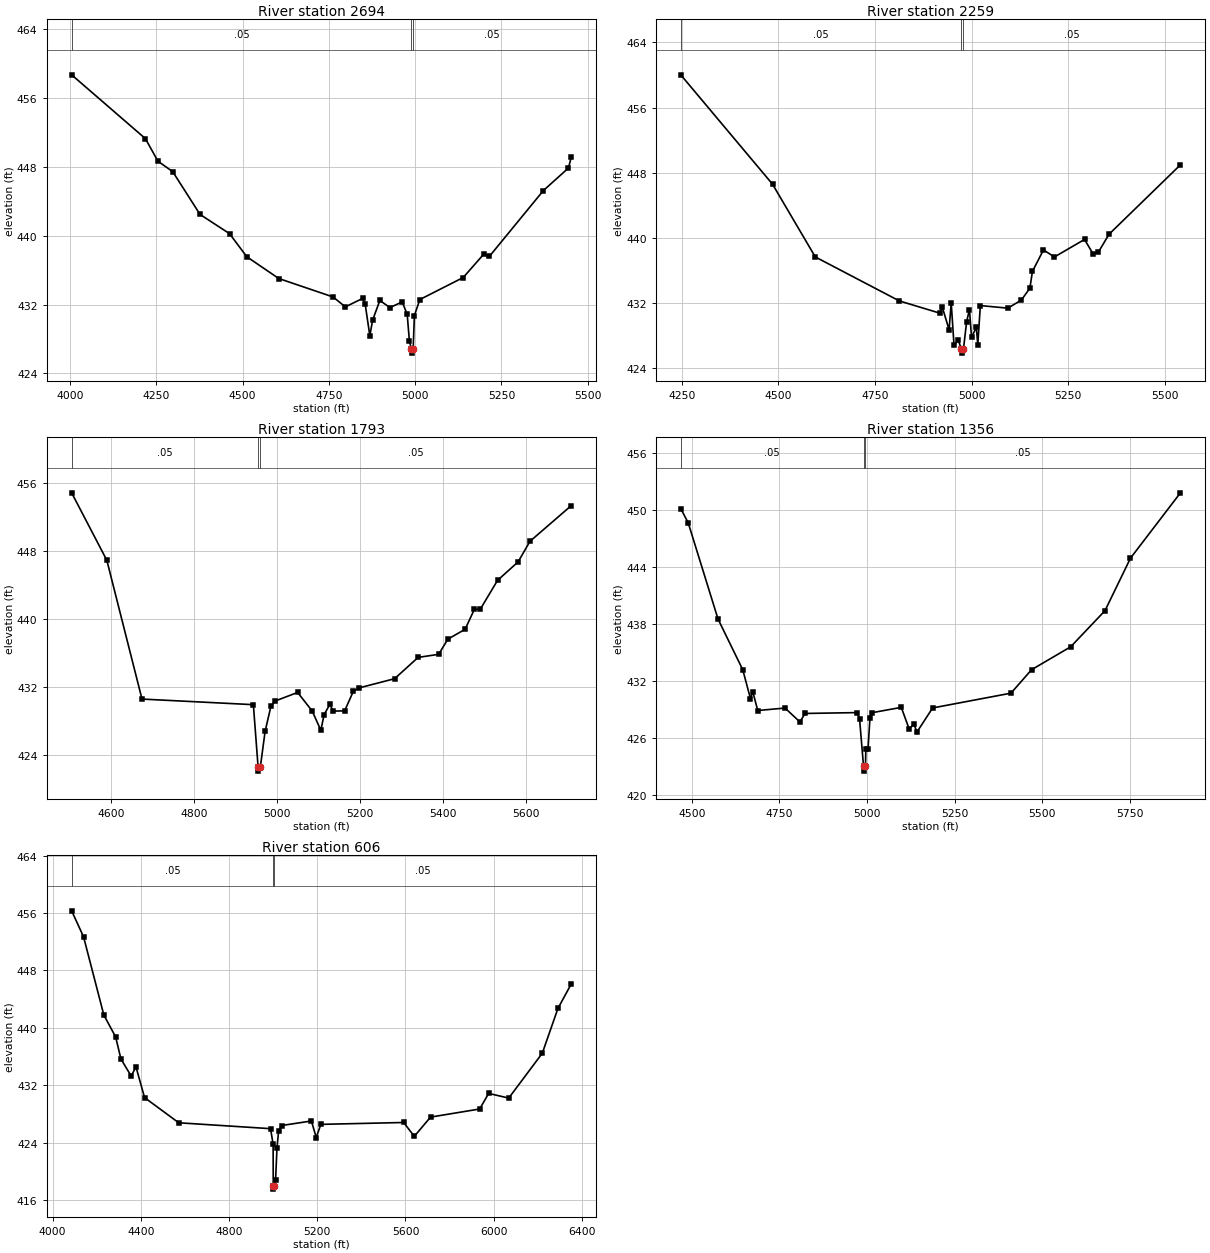
Type RM Length L Ch R = 1,2694,435,435,435
BEGIN DESCRIPTION:
Eagans Branch Trib 3 5.0
END DESCRIPTION:
XS GIS Cut Line= 3
      2659925.97      6920160.98      2660726.00      6920761.00
      2660926.02      6921161.04
#Sta/Elev= 30
  4005.0  458.67  4218.6  451.26  4255.0  448.64  4297.7  447.43  4376.9  442.46
  4462.3  440.23  4512.3  437.55  4605.0  435.02  4762.3  432.88  4797.7  431.73
  4847.7  432.71  4855.0  432.10  4868.6  428.39  4876.9  430.21  4897.7  432.47
  4926.9  431.65  4962.3  432.31  4976.9  430.87  4983.2  427.77  4988.8  426.86
  4989.6  426.36  4994.2  426.86  4997.7  430.72  5013.4  432.58  5139.2  435.14
  5197.9  437.82  5214.7  437.58  5371.2  445.23  5443.9  447.85  5452.3  449.14
#Mann=3,-1,0
  4005.0    0.05       0  4988.8    0.04       0  4994.2    0.05       0
Bank Sta=4988.8,4994.2
Exp/Cntr=0.3,0.1

Type RM Length L Ch R = 1,2259,466,466,466
BEGIN DESCRIPTION:
Eagans Branch Trib 3 4.0
END DESCRIPTION:
XS GIS Cut Line= 3
      2659726.00      6920611.00      2660426.00      6920911.00
      2660776.01      6921311.01
#Sta/Elev= 30
  4247.4  460.02  4484.9  446.57  4595.6  437.62  4813.1  432.21  4918.3  430.70
  4923.8  431.51  4941.9  428.66  4947.3  432.00  4954.6  426.73  4965.5  427.39
  4973.6  426.29  4974.4  425.79  4979.0  426.29  4987.2  429.65  4994.5  431.15
  4999.9  427.74  5012.3  428.96  5016.1  426.84  5022.7  431.64  5093.9  431.32
  5129.0  432.32  5150.9  433.78  5157.5  435.84  5186.0  438.48  5214.5  437.62
  5292.3  439.77  5314.1  438.03  5327.9  438.19  5355.9  440.42  5540.5  448.95
#Mann=3,-1,0
  4247.4    0.05       0  4973.6    0.04       0  4979.0    0.05       0
Bank Sta=4973.6,4979
Exp/Cntr=0.3,0.1

Type RM Length L Ch R = 1,1793,437,437,437
BEGIN DESCRIPTION:
Eagans Branch Trib 3 3.0
END DESCRIPTION:
XS GIS Cut Line= 3
      2659726.00      6920811.00      2660076.00      6921161.00
      2660625.99      6921611.00
#Sta/Elev= 30
  4504.5  454.85  4589.4  446.90  4674.2  430.55  4942.9  429.89  4954.3  422.56
  4955.1  422.06  4959.8  422.56  4971.2  426.73  4985.3  429.71  4995.9  430.33
  5049.7  431.33  5084.9  429.14  5105.7  426.87  5113.6  428.72  5128.0  429.97
  5134.4  429.13  5163.1  429.16  5184.0  431.45  5198.3  431.87  5283.7  432.95
  5340.4  435.46  5390.0  435.82  5412.2  437.61  5453.8  438.77  5476.1  441.12
  5490.5  441.14  5532.1  444.54  5581.6  446.71  5610.3  449.14  5710.1  453.35
#Mann=3,-1,0
  4504.5    0.05       0  4954.3    0.04       0  4959.8    0.05       0
Bank Sta=4954.3,4959.8
Exp/Cntr=0.3,0.1

Type RM Length L Ch R = 1,1356,750,750,750
BEGIN DESCRIPTION:
Eagans Branch Trib 3 2.0
END DESCRIPTION:
XS GIS Cut Line= 3
      2659375.97      6920960.96      2659726.00      6921361.00
      2660526.02      6921761.01
#Sta/Elev= 30
  4468.4  450.19  4489.8  448.68  4574.8  438.54  4645.5  433.19  4667.3  430.16
  4673.9  430.88  4688.2  428.90  4766.0  429.16  4808.7  427.69  4822.9  428.59
  4972.0  428.68  4978.6  428.05  4990.1  423.01  4990.9  422.51  4995.6  423.01
  4996.6  424.80  5002.8  424.80  5008.3  428.07  5013.9  428.67  5097.8  429.23
  5120.1  426.97  5134.1  427.44  5142.5  426.63  5187.2  429.17  5410.8  430.73
  5469.5  433.20  5581.3  435.62  5679.2  439.43  5751.8  444.96  5894.4  451.85
#Mann=3,-1,0
  4468.4    0.05       0  4990.1    0.04       0  4995.6    0.05       0
Bank Sta=4990.1,4995.6
Exp/Cntr=0.3,0.1

Type RM Length L Ch R = 1,606,0,0,0
BEGIN DESCRIPTION:
Eagans Branch Trib 3 1.0
END DESCRIPTION:
XS GIS Cut Line= 5
      2659326.02      6920910.95      2659067.70      6921545.62
      2659140.10      6921762.11      2659328.11      6921983.12
      2660376.01      6921811.00
#Sta/Elev= 30
  4086.5  456.31  4140.5  452.69  4232.4  441.80  4285.9  438.75  4309.9  435.68
  4356.5  433.29  4378.1  434.59  4417.0  430.30  4572.1  426.79  4988.3  425.97
  5000.0  423.78  5000.5  418.05  5001.3  417.55  5006.0  418.05  5011.0  418.77
  5017.5  423.32  5024.8  425.62  5038.4  426.41  5173.5  427.04  5195.5  424.74
  5216.3  426.57  5592.0  426.83  5640.1  424.90  5713.7  427.58  5936.6  428.71
  5977.1  430.88  6068.3  430.23  6220.4  436.48  6291.3  442.71  6352.1  446.15
#Mann=3,-1,0
  4086.5    0.05       0  5000.5    0.04       0  5006.0    0.05       0
Bank Sta=5000.5,5006
Exp/Cntr=0.3,0.1

Chan Stop Cuts=-1