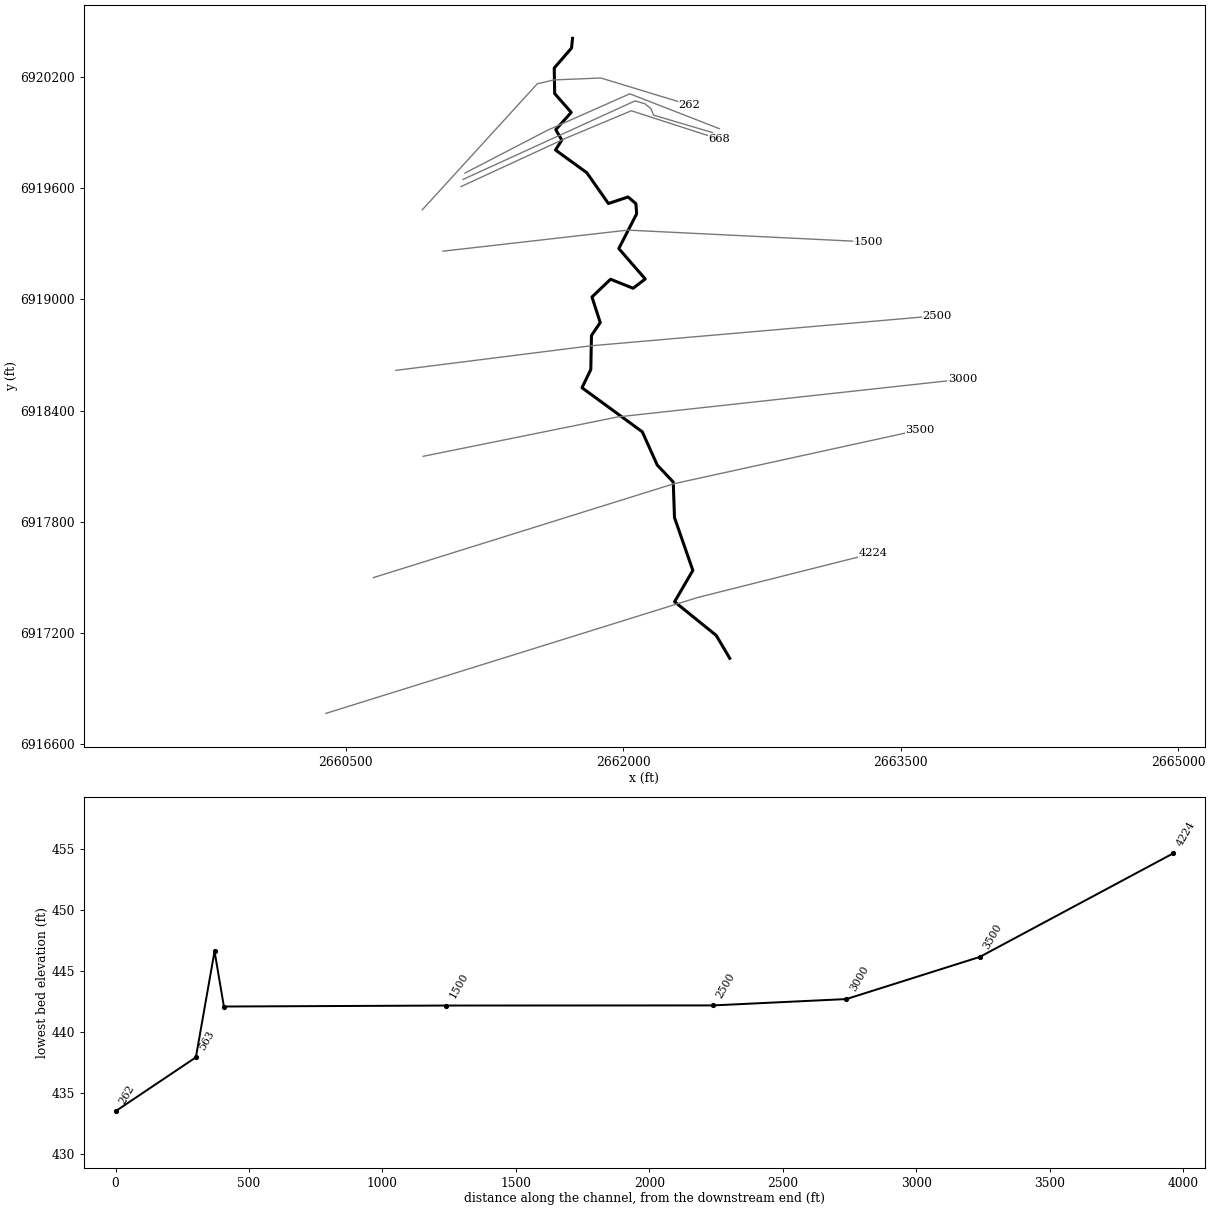
--- Eagans Branch Trib 3_1.prj (project) ---

Proj Title=Eagans Branch Trib 3_1 Base Level Engineering
Current Plan=p01
Default Exp/Contr=0.3,0.1
English Units
Geom File=g01
Flow File=f01
Plan File=p01
BEGIN DESCRIPTION:
Eagans Branch Trib 3_1
END DESCRIPTION:

--- Eagans Branch Trib 3_1.p01 (plan) ---

Plan Title=Multiple Run
Short Identifier=Multiple
Geom File=g01
Flow File=f01
Subcritical Flow
K Sum by GR= 0
Std Step Tol= 0.01
Critical Tol= 0.01
Num of Std Step Trials= 20
Max Error Tol= 0.3
Flow Tol Ratio= 0.001
Split Flow NTrial= 30
Split Flow Tol= 0.02
Split Flow Ratio= 0.02
Log Output Level= 0
Friction Slope Method= 1
Unsteady Friction Slope Method= 2
Unsteady Bridges Friction Slope Method= 1
Parabolic Critical Depth
Global Vel Dist=  1 , 1 , 1
Global Log Level= 0
CheckData=True
Encroach Param= -1, 0, 0, 0
BEGIN DESCRIPTION:
Multiple Run
END DESCRIPTION:

--- Eagans Branch Trib 3_1.f01 (steady flow) ---

Flow Title=Multiple
Number of Profiles=7
Profile Names=10-year,25-year,50-year,1pct_min,100-year,1pct_plu,500-year
River Rch & RM= Eagans Branch Tr,Reach-1,4224
     314     405     475     277     553    1104     749
Boundary for River Rch & Prof#=Eagans Branch Tr,Reach-1,1
Up Type=0
Dn Type=3
Dn Slope=0.005
Boundary for River Rch & Prof#=Eagans Branch Tr,Reach-1,2
Up Type=0
Dn Type=3
Dn Slope=0.005
Boundary for River Rch & Prof#=Eagans Branch Tr,Reach-1,3
Up Type=0
Dn Type=3
Dn Slope=0.005
Boundary for River Rch & Prof#=Eagans Branch Tr,Reach-1,4
Up Type=0
Dn Type=3
Dn Slope=0.005
Boundary for River Rch & Prof#=Eagans Branch Tr,Reach-1,5
Up Type=0
Dn Type=3
Dn Slope=0.005
Boundary for River Rch & Prof#=Eagans Branch Tr,Reach-1,6
Up Type=0
Dn Type=3
Dn Slope=0.005
Boundary for River Rch & Prof#=Eagans Branch Tr,Reach-1,7
Up Type=0
Dn Type=3
Dn Slope=0.005

--- Eagans Branch Trib 3_1.g01 (geometry) ---

Geom Title=Existing Conditions

River Reach=Eagans Branch Tr,Reach-1
Reach XY= 30
      2662576.00      6917061.00      2662503.03      6917184.52
      2662277.69      6917366.63      2662376.49      6917535.96
      2662277.22      6917821.51      2662270.53      6918013.45
      2662184.16      6918104.95      2662103.14      6918284.84
      2661777.17      6918523.01      2661824.75      6918621.48
      2661828.40      6918805.48      2661875.75      6918875.10
      2661831.09      6919013.31      2661931.62      6919109.27
      2662053.44      6919060.53      2662119.02      6919110.72
      2661976.09      6919275.04      2662072.69      6919462.80
      2662068.53      6919517.70      2662026.36      6919553.74
      2661919.94      6919518.50      2661803.14      6919684.84
      2661633.98      6919807.65      2661667.95      6919861.00
      2661635.33      6919917.67      2661718.89      6920010.99
      2661629.55      6920112.47      2661627.04      6920250.56
      2661720.67      6920358.49      2661726.00      6920411.00

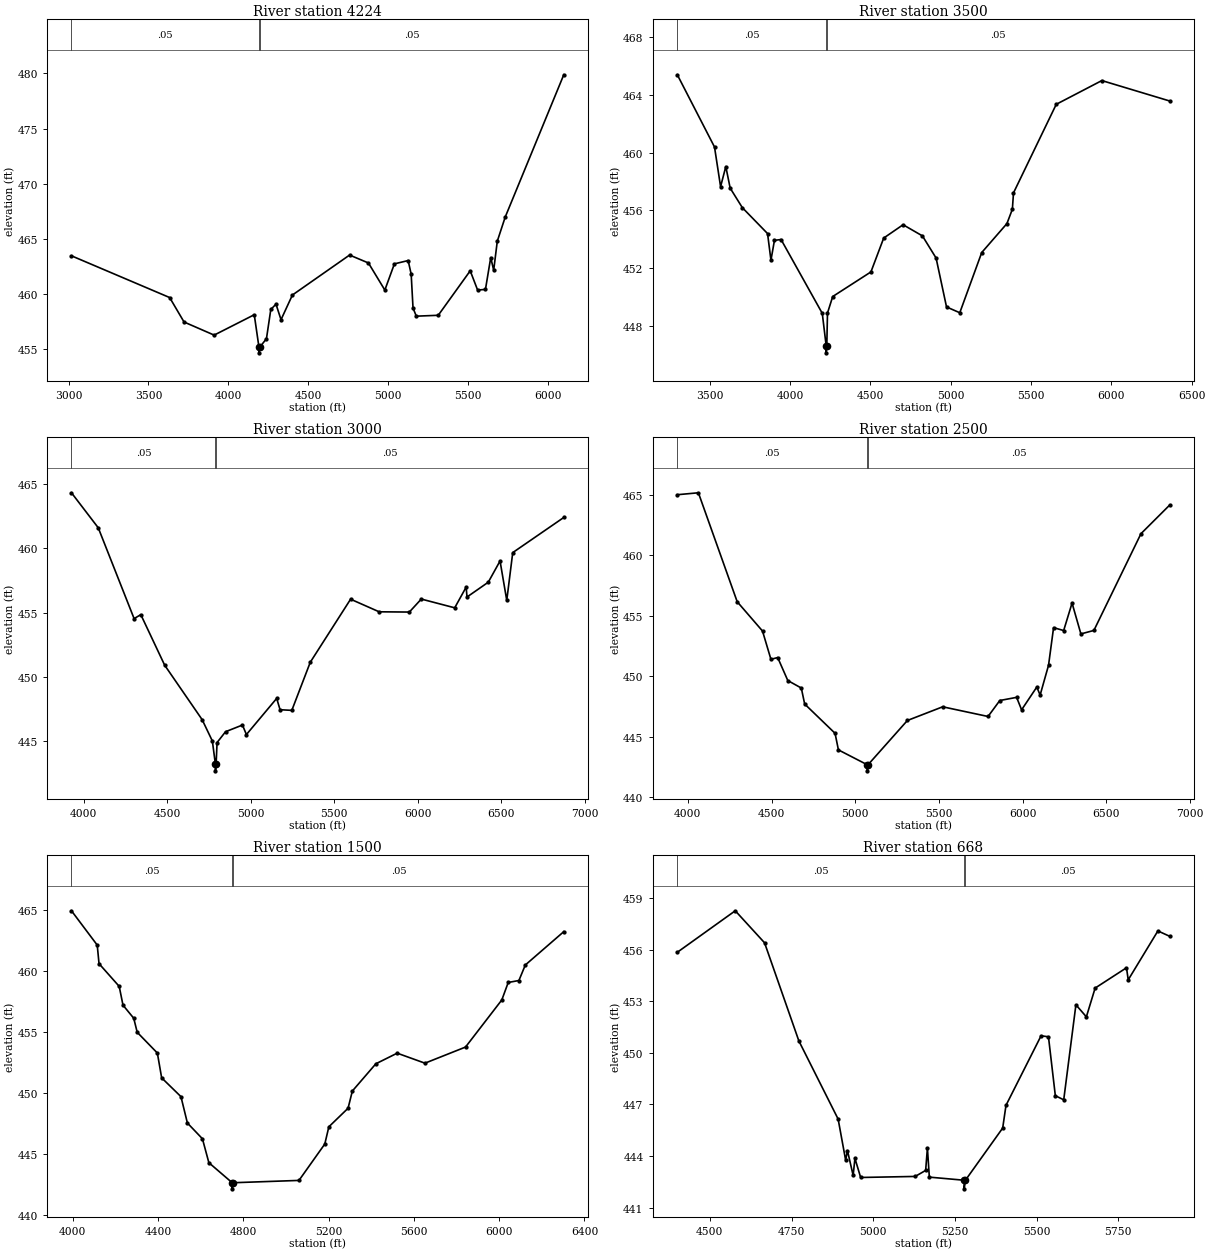
Type RM Length L Ch R = 1,4224,724,724,724
BEGIN DESCRIPTION:
Eagans Branch Trib 3_1 7.0
END DESCRIPTION:
XS GIS Cut Line= 3
      2660392.67      6916763.43      2662401.86      6917389.27
      2663351.70      6917628.46
#Sta/Elev= 30
  3018.0  463.44  3633.1  459.65  3723.2  457.43  3911.8  456.24  4163.1  458.09
  4192.6  455.13  4192.8  454.63  4196.6  455.13  4239.4  455.91  4266.7  458.57
  4299.2  459.05  4330.7  457.64  4402.0  459.88  4760.2  463.51  4878.3  462.79
  4981.1  460.33  5040.9  462.71  5127.1  463.01  5146.0  461.78  5157.6  458.70
  5178.2  457.96  5315.6  458.04  5515.9  462.08  5562.2  460.33  5611.3  460.39
  5644.4  463.28  5662.9  462.13  5685.5  464.77  5735.1  466.96  6101.9  479.88
#Mann=3,-1,0
  3018.0    0.05       0  4192.6   0.035       0  4196.6    0.05       0
Bank Sta=4192.6,4196.6
Exp/Cntr=0.3,0.1

Type RM Length L Ch R = 1,3500,500,500,500
BEGIN DESCRIPTION:
Eagans Branch Trib 3_1 6.0
END DESCRIPTION:
XS GIS Cut Line= 3
      2660649.66      6917497.09      2662274.11      6918004.31
      2663605.39      6918295.70
#Sta/Elev= 30
  3298.2  465.37  3529.7  460.38  3567.5  457.64  3600.0  459.03  3627.2  457.54
  3702.9  456.19  3859.9  454.40  3881.0  452.56  3902.8  453.93  3943.9  453.99
  4200.5  448.89  4224.7  446.66  4225.0  446.16  4228.7  446.66  4233.0  448.91
  4265.5  450.05  4503.4  451.75  4582.9  454.09  4703.6  455.01  4823.9  454.24
  4909.0  452.71  4974.0  449.33  5056.5  448.93  5193.2  453.09  5350.0  455.09
  5383.9  456.08  5390.9  457.21  5657.1  463.33  5940.9  464.97  6362.8  463.56
#Mann=3,-1,0
  3298.2    0.05       0  4224.7    0.03       0  4228.7    0.05       0
Bank Sta=4224.7,4228.7
Exp/Cntr=0.3,0.1

Type RM Length L Ch R = 1,3000,500,500,500
BEGIN DESCRIPTION:
Eagans Branch Trib 3_1 5.0
END DESCRIPTION:
XS GIS Cut Line= 3
      2660918.81      6918152.49      2661971.28      6918365.44
      2663835.48      6918569.15
#Sta/Elev= 30
  3926.2  464.32  4086.6  461.60  4301.4  454.54  4341.6  454.85  4484.5  450.92
  4708.9  446.69  4770.2  445.03  4788.6  443.21  4788.8  442.71  4792.6  443.21
  4798.4  444.91  4849.1  445.75  4950.5  446.27  4974.2  445.53  5155.6  448.34
  5175.8  447.46  5246.2  447.41  5356.8  451.15  5598.3  456.05  5769.3  455.07
  5950.3  455.05  6021.8  456.06  6222.0  455.38  6290.6  456.99  6295.7  456.22
  6423.1  457.37  6493.6  459.02  6533.8  455.96  6569.6  459.67  6875.3  462.40
#Mann=3,-1,0
  3926.2    0.05       0  4788.6    0.05       0  4792.6    0.05       0
Bank Sta=4788.6,4792.6
Exp/Cntr=0.3,0.1

Type RM Length L Ch R = 1,2500,1000,1000,1000
BEGIN DESCRIPTION:
Eagans Branch Trib 3_1 4.0
END DESCRIPTION:
XS GIS Cut Line= 3
      2660771.23      6918616.89      2661825.70      6918749.70
      2663696.57      6918912.03
#Sta/Elev= 30
  3937.2  465.00  4063.0  465.16  4294.8  456.16  4446.0  453.74  4496.4  451.40
  4536.7  451.55  4597.1  449.65  4677.8  449.03  4697.9  447.71  4879.4  445.29
  4899.5  443.92  5072.2  442.69  5072.5  442.19  5076.2  442.69  5311.5  446.35
  5522.3  447.48  5793.3  446.68  5863.5  448.00  5963.9  448.26  5993.7  447.23
  6084.4  449.11  6104.4  448.45  6154.6  450.91  6184.7  454.02  6245.0  453.78
  6295.1  456.05  6347.9  453.50  6425.6  453.79  6706.7  461.78  6877.9  464.14
#Mann=3,-1,0
  3937.2    0.05       0  5072.2    0.03       0  5076.2    0.05       0
Bank Sta=5072.2,5076.2
Exp/Cntr=0.3,0.1

Type RM Length L Ch R = 1,1500,832,832,832
BEGIN DESCRIPTION:
Eagans Branch Trib 3_1 3.0
END DESCRIPTION:
XS GIS Cut Line= 3
      2661025.96      6919261.00      2662024.80      6919374.73
      2663326.04      6919311.00
#Sta/Elev= 30
  3994.7  464.95  4115.5  462.14  4123.9  460.62  4218.5  458.76  4236.3  457.22
  4286.6  456.15  4302.9  455.00  4397.4  453.30  4417.5  451.27  4508.0  449.73
  4538.2  447.57  4608.7  446.28  4638.9  444.32  4748.3  442.68  4748.6  442.18
  4752.3  442.68  5061.3  442.87  5182.4  445.85  5201.4  447.26  5291.5  448.78
  5311.6  450.19  5421.7  452.42  5521.8  453.29  5652.0  452.47  5842.2  453.79
  6012.4  457.65  6042.4  459.08  6092.5  459.24  6122.5  460.51  6302.8  463.24
#Mann=3,-1,0
  3994.7    0.05       0  4748.3    0.03       0  4752.3    0.05       0
Bank Sta=4748.3,4752.3
Exp/Cntr=0.3,0.1

Type RM Length L Ch R = 1,668,35,35,35
BEGIN DESCRIPTION:
Eagans Branch Trib 3_1 2.0
END DESCRIPTION:
XS GIS Cut Line= 4
      2661123.52      6919610.10      2661694.80      6919873.56
      2662043.84      6920019.66      2662518.87      6919866.18
#Sta/Elev= 30
  4400.5  455.84  4577.8  458.25  4667.5  456.39  4772.5  450.69  4892.7  446.15
  4915.7  443.76  4921.2  444.32  4938.6  442.88  4944.1  443.87  4961.6  442.76
  5128.5  442.82  5160.5  443.17  5165.9  444.47  5171.8  442.78  5278.2  442.60
  5278.5  442.10  5282.2  442.60  5396.3  445.63  5406.4  446.95  5513.8  450.99
  5536.4  450.93  5557.4  447.51  5583.1  447.27  5620.4  452.79  5652.4  452.09
  5679.2  453.76  5775.2  454.94  5780.5  454.24  5871.3  457.08  5907.2  456.77
#Mann=3,-1,0
  4400.5    0.05       0  5278.2    0.03       0  5282.2    0.05       0
Bank Sta=5278.2,5282.2
Exp/Cntr=0.3,0.1

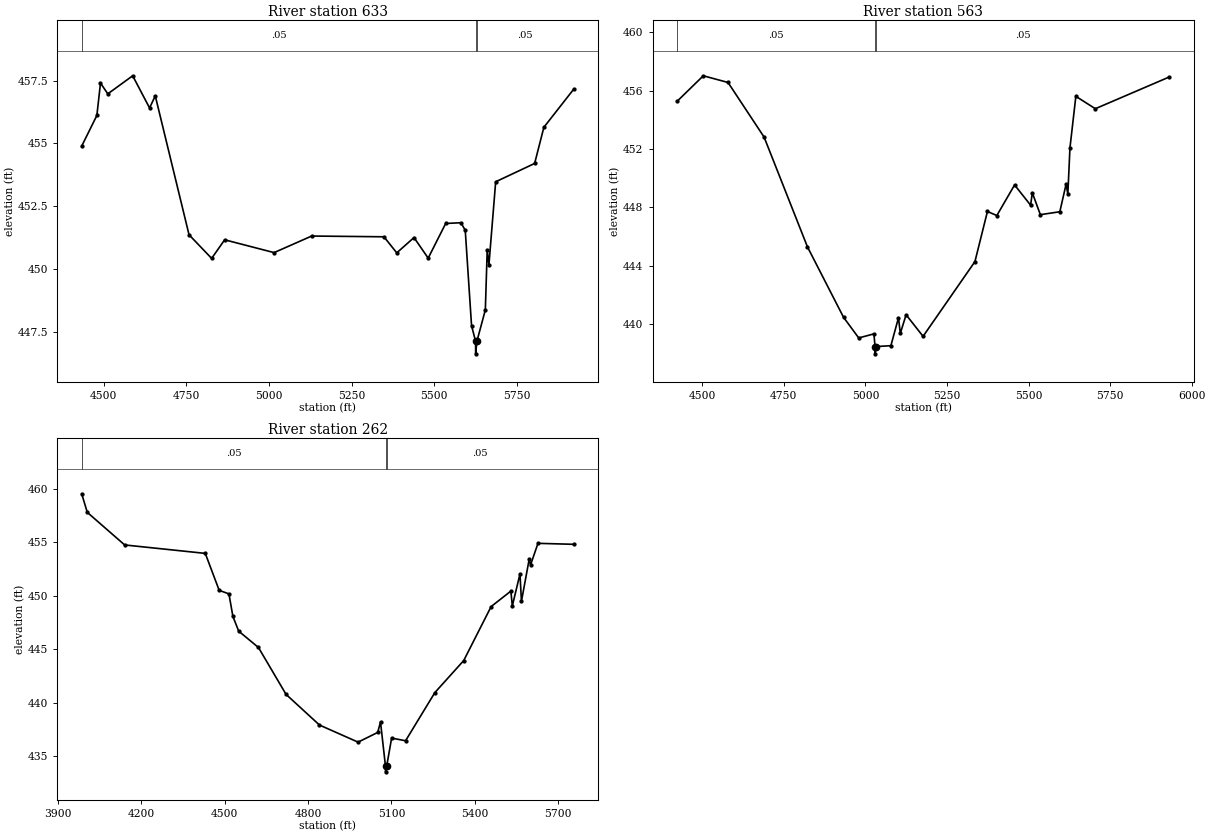
Type RM Length L Ch R = 1,633,70,70,70
BEGIN DESCRIPTION:
Mapping XS 2bf2a55b
END DESCRIPTION:
XS GIS Cut Line= 6
      2661134.51      6919648.78      2662064.44      6920073.25
      2662117.57      6920057.10      2662150.12      6920030.72
      2662163.92      6919996.17      2662482.11      6919901.93
#Sta/Elev= 30
  4433.2  454.89  4479.1  456.11  4490.1  457.40  4512.2  456.97  4587.5  457.69
  4638.6  456.41  4655.9  456.89  4758.1  451.36  4826.5  450.42  4865.9  451.16
  5015.5  450.65  5129.3  451.31  5348.0  451.28  5386.8  450.64  5439.0  451.25
  5481.9  450.43  5534.9  451.81  5580.9  451.84  5594.1  451.54  5613.2  447.74
  5625.4  447.12  5625.6  446.62  5629.4  447.12  5654.9  448.37  5660.6  450.76
  5665.8  450.17  5686.2  453.47  5804.1  454.20  5832.1  455.64  5922.0  457.15
#Mann=3,-1,0
  4433.2    0.05       0  5625.4    0.03       0  5629.4    0.05       0
Bank Sta=5625.4,5629.4
Exp/Cntr=0.3,0.1

Type RM Length L Ch R = 1,563,301,301,301
BEGIN DESCRIPTION:
Eagans Branch Trib 3_1 1.0
END DESCRIPTION:
XS GIS Cut Line= 4
      2661144.77      6919683.01      2661591.79      6919914.90
      2662035.58      6920111.29      2662519.07      6919923.15
#Sta/Elev= 30
  4422.9  455.27  4503.1  457.02  4578.9  456.56  4689.5  452.81  4822.3  445.28
  4932.9  440.45  4979.5  439.03  5026.1  439.31  5029.5  438.44  5029.8  437.94
  5033.5  438.44  5078.1  438.50  5101.4  440.42  5106.9  439.34  5124.7  440.62
  5176.7  439.14  5335.7  444.27  5374.0  447.71  5402.8  447.43  5457.2  449.53
  5506.3  448.14  5511.6  448.99  5536.2  447.49  5595.9  447.69  5615.1  449.58
  5620.5  448.90  5626.9  452.07  5645.0  455.61  5704.7  454.76  5930.6  456.93
#Mann=3,-1,0
  4422.9    0.05       0  5029.5    0.03       0  5033.5    0.05       0
Bank Sta=5029.5,5033.5
Exp/Cntr=0.3,0.1

Type RM Length L Ch R = 1,262,0,0,0
BEGIN DESCRIPTION:
Mapping XS e571b0d9
END DESCRIPTION:
XS GIS Cut Line= 5
      2660914.06      6919484.87      2661535.58      6920165.41
      2661625.86      6920186.25      2661879.33      6920196.66
      2662358.45      6920050.85
#Sta/Elev= 30
  3986.0  459.56  4006.1  457.82  4140.5  454.77  4430.4  453.98  4480.4  450.52
  4515.5  450.19  4529.7  448.08  4550.6  446.70  4621.6  445.17  4720.9  440.78
  4841.1  437.91  4979.9  436.31  5050.5  437.22  5060.5  438.20  5078.5  434.03
  5078.8  433.53  5082.5  434.03  5100.5  436.69  5150.6  436.44  5256.0  440.95
  5359.8  443.95  5458.3  449.00  5529.3  450.45  5534.5  449.06  5562.1  452.06
  5567.3  449.49  5595.0  453.41  5600.2  452.91  5626.8  454.92  5754.8  454.83
#Mann=3,-1,0
  3986.0    0.05       0  5078.5    0.05       0  5082.5    0.05       0
Bank Sta=5078.5,5082.5
Exp/Cntr=0.3,0.1

Chan Stop Cuts=-1