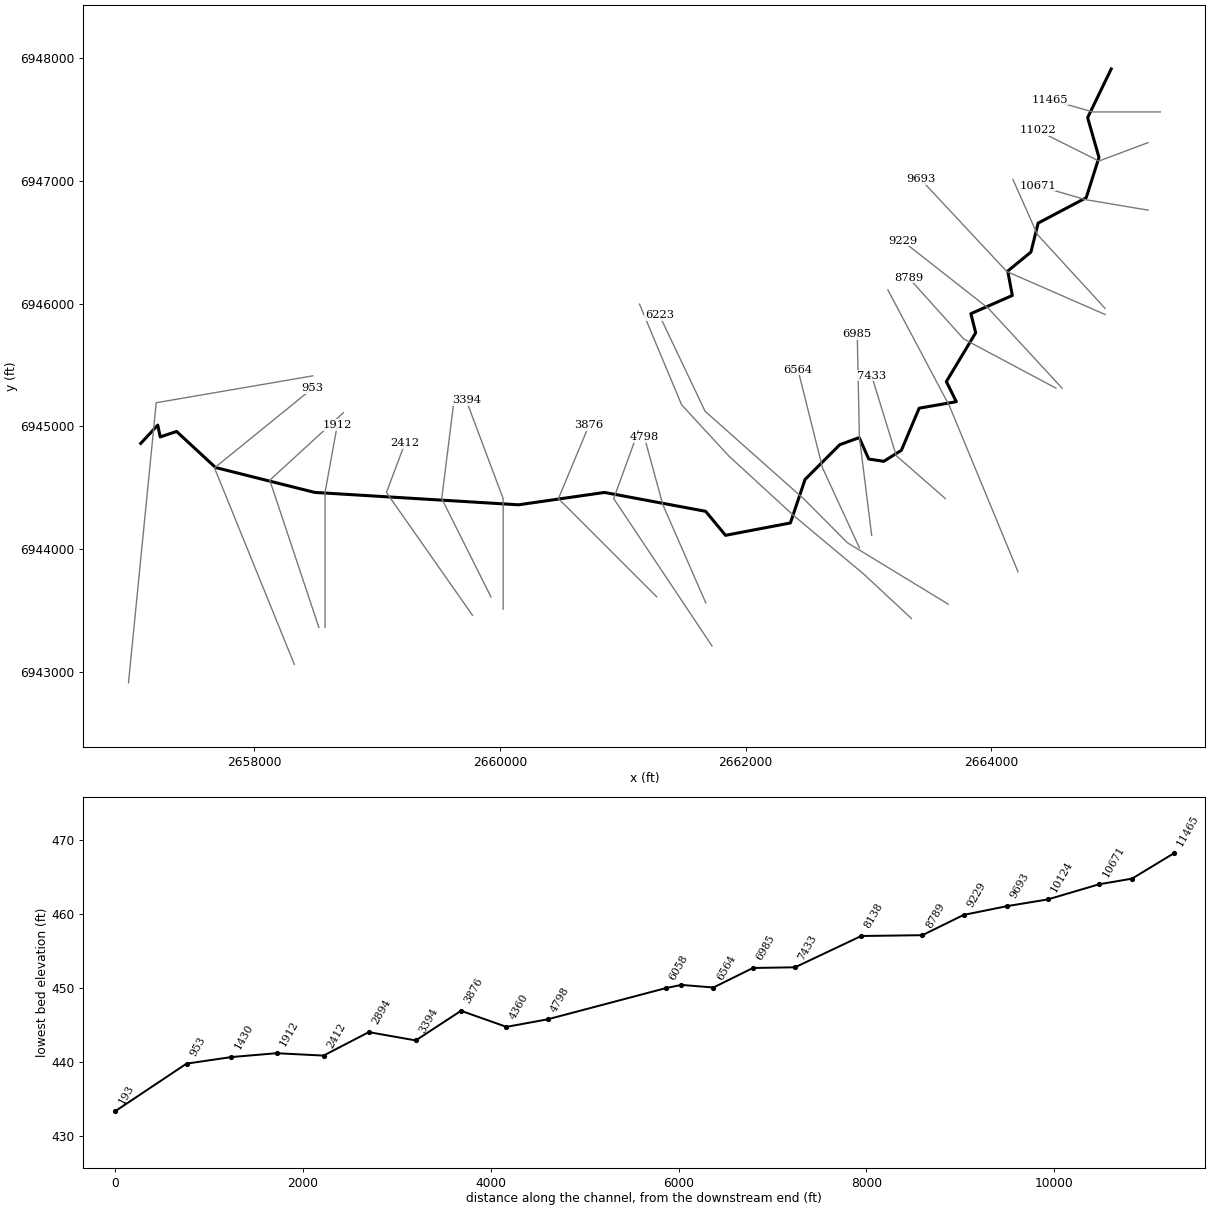
--- Eagans Creek.prj (project) ---

Proj Title=Eagans Creek Base Level Engineering
Current Plan=p01
Default Exp/Contr=0.3,0.1
English Units
Geom File=g01
Flow File=f01
Plan File=p01
BEGIN DESCRIPTION:
Eagans Creek
END DESCRIPTION:

--- Eagans Creek.p01 (plan) ---

Plan Title=Multiple Run
Short Identifier=Multiple
Geom File=g01
Flow File=f01
Subcritical Flow
K Sum by GR= 0
Std Step Tol= 0.01
Critical Tol= 0.01
Num of Std Step Trials= 20
Max Error Tol= 0.3
Flow Tol Ratio= 0.001
Split Flow NTrial= 30
Split Flow Tol= 0.02
Split Flow Ratio= 0.02
Log Output Level= 0
Friction Slope Method= 1
Unsteady Friction Slope Method= 2
Unsteady Bridges Friction Slope Method= 1
Parabolic Critical Depth
Global Vel Dist=  1 , 1 , 1
Global Log Level= 0
CheckData=True
Encroach Param= -1, 0, 0, 0
BEGIN DESCRIPTION:
Multiple Run
END DESCRIPTION:

--- Eagans Creek.f01 (steady flow) ---

Flow Title=Multiple
Number of Profiles=7
Profile Names=10-year,25-year,50-year,1pct_min,100-year,1pct_plu,500-year
River Rch & RM= Eagans Creek,Reach-1,11465
     509     675     808     480     958    1912    1346
River Rch & RM= Eagans Creek,Reach-1,10124
     817    1117    1363     825    1646    3284    2399
River Rch & RM= Eagans Creek,Reach-1,9693
     959    1318    1614     980    1955    3900    2866
River Rch & RM= Eagans Creek,Reach-1,6223
    1086    1499    1842    1120    2234    4457    3288
River Rch & RM= Eagans Creek,Reach-1,2412
    1170    1620    1995    1215    2425    4839    3585
Boundary for River Rch & Prof#=Eagans Creek,Reach-1,1
Up Type=0
Dn Type=3
Dn Slope=0.005
Boundary for River Rch & Prof#=Eagans Creek,Reach-1,2
Up Type=0
Dn Type=3
Dn Slope=0.005
Boundary for River Rch & Prof#=Eagans Creek,Reach-1,3
Up Type=0
Dn Type=3
Dn Slope=0.005
Boundary for River Rch & Prof#=Eagans Creek,Reach-1,4
Up Type=0
Dn Type=3
Dn Slope=0.005
Boundary for River Rch & Prof#=Eagans Creek,Reach-1,5
Up Type=0
Dn Type=3
Dn Slope=0.005
Boundary for River Rch & Prof#=Eagans Creek,Reach-1,6
Up Type=0
Dn Type=3
Dn Slope=0.005
Boundary for River Rch & Prof#=Eagans Creek,Reach-1,7
Up Type=0
Dn Type=3
Dn Slope=0.005

--- Eagans Creek.g01 (geometry) ---

Geom Title=Existing Conditions

River Reach=Eagans Creek,Reach-1
Reach XY= 30
      2664976.00      6947911.00      2664784.06      6947514.29
      2664876.36      6947190.85      2664772.49      6946862.25
      2664381.19      6946655.56      2664322.47      6946419.49
      2664133.73      6946264.65      2664171.00      6946066.01
      2663833.35      6945917.38      2663872.93      6945762.43
      2663634.05      6945364.29      2663715.07      6945200.57
      2663412.65      6945147.64      2663267.98      6944804.66
      2663124.41      6944714.67      2663001.99      6944733.64
      2662924.61      6944907.98      2662766.30      6944850.25
      2662483.80      6944567.21      2662364.17      6944212.63
      2661836.29      6944111.97      2661674.54      6944307.46
      2660851.04      6944461.32      2660151.00      6944360.60
      2658491.22      6944461.52      2657684.44      6944664.41
      2657367.37      6944958.03      2657234.18      6944913.57
      2657214.20      6945009.96      2657076.00      6944861.00

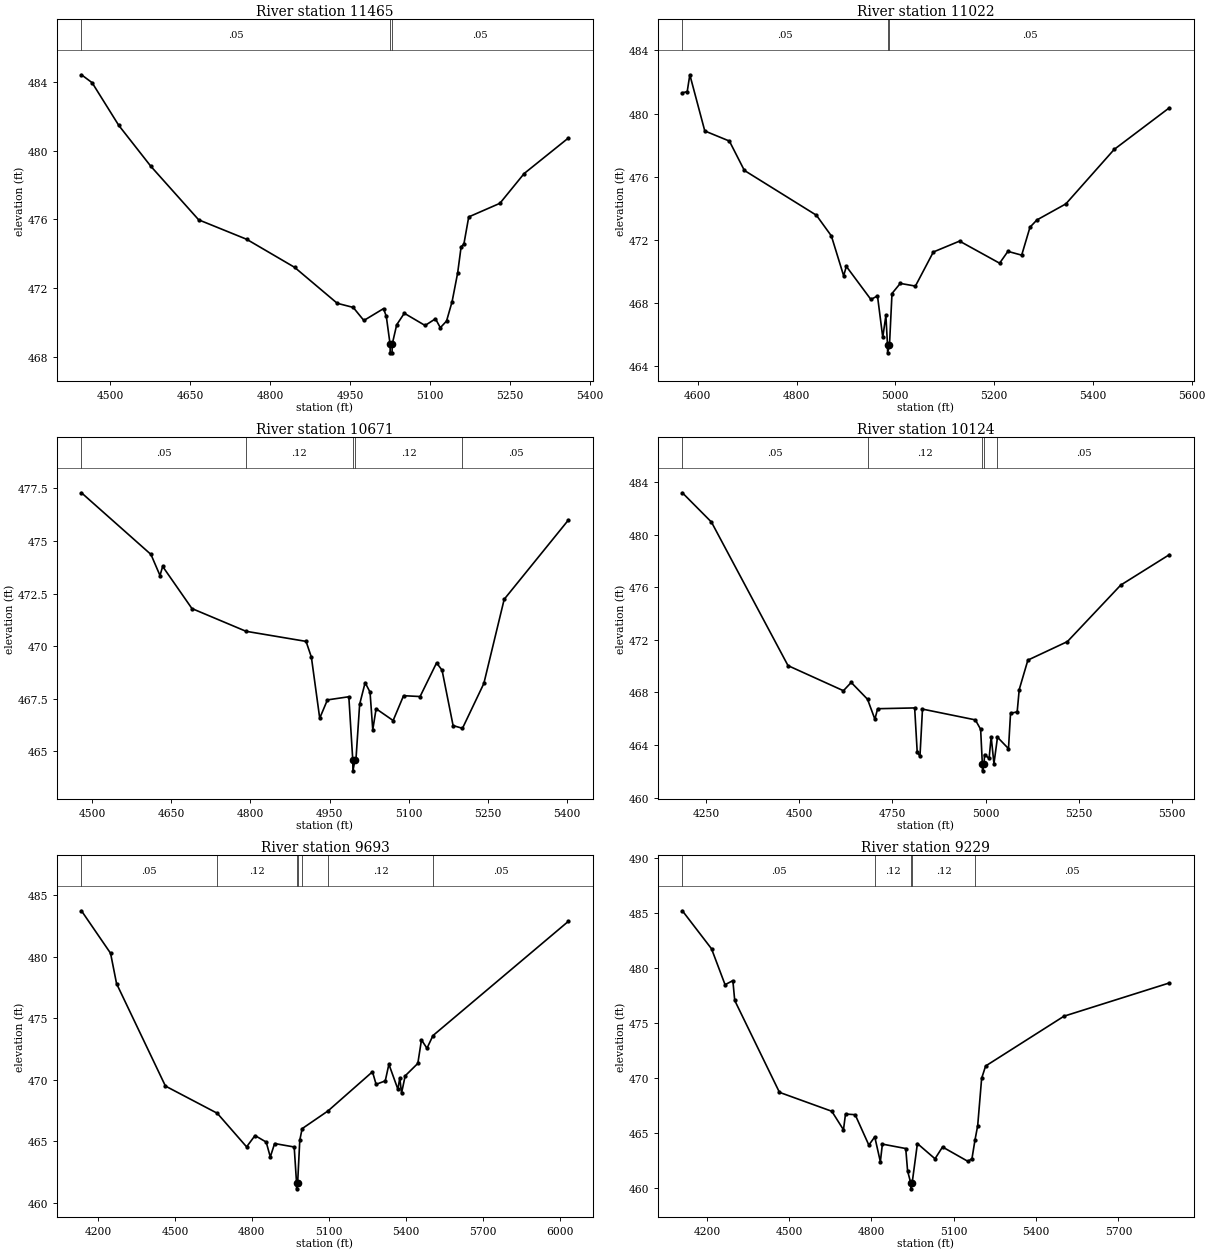
Type RM Length L Ch R = 1,11465,443,443,443
BEGIN DESCRIPTION:
Eagans Creek 25.0
END DESCRIPTION:
XS GIS Cut Line= 3
      2665375.97      6947561.00      2664826.00      6947561.00
      2664475.97      6947661.01
#Sta/Elev= 30
  4445.7  484.41  4465.7  483.95  4515.7  481.47  4575.7  479.10  4665.7  475.98
  4755.7  474.85  4845.7  473.22  4925.7  471.13  4955.7  470.89  4975.7  470.13
  5012.6  470.82  5017.8  470.37  5024.9  468.75  5025.1  468.25  5028.6  468.25
  5028.9  468.75  5037.3  469.88  5051.6  470.55  5090.6  469.84  5110.1  470.23
  5119.2  469.71  5130.9  470.10  5141.3  471.23  5151.7  472.89  5158.2  474.41
  5163.4  474.57  5172.5  476.15  5231.0  476.94  5276.5  478.67  5359.7  480.74
#Mann=3,-1,0
  4445.7    0.05       0  5024.9    0.05       0  5028.9    0.05       0
Bank Sta=5024.9,5028.9
Exp/Cntr=0.3,0.1

Type RM Length L Ch R = 1,11022,351,351,351
BEGIN DESCRIPTION:
Eagans Creek 24.0
END DESCRIPTION:
XS GIS Cut Line= 3
      2665275.98      6947310.99      2664876.00      6947161.00
      2664376.00      6947411.00
#Sta/Elev= 30
  4568.7  481.32  4578.5  481.39  4583.8  482.46  4614.1  478.90  4663.9  478.26
  4694.2  476.40  4840.1  473.56  4870.4  472.25  4895.3  469.72  4900.7  470.32
  4950.5  468.22  4963.8  468.45  4974.5  465.82  4980.8  467.21  4984.1  465.34
  4984.3  464.84  4988.1  465.34  4993.2  468.60  5009.9  469.24  5040.6  469.07
  5076.9  471.23  5130.0  471.92  5211.1  470.52  5227.9  471.27  5255.8  471.03
  5272.6  472.80  5286.6  473.26  5345.3  474.28  5443.1  477.73  5554.9  480.37
#Mann=3,-1,0
  4568.7    0.05       0  4984.1    0.03       0  4988.1    0.05       0
Bank Sta=4984.1,4988.1
Exp/Cntr=0.3,0.1

Type RM Length L Ch R = 1,10671,547,547,547
BEGIN DESCRIPTION:
Eagans Creek 23.0
END DESCRIPTION:
XS GIS Cut Line= 3
      2665275.97      6946761.01      2664762.77      6946847.28
      2664376.04      6946960.99
#Sta/Elev= 30
  4479.6  477.29  4611.4  474.36  4628.5  473.36  4633.6  473.79  4689.1  471.79
  4791.6  470.71  4905.5  470.23  4915.6  469.48  4931.4  466.58  4946.0  467.45
  4986.6  467.60  4994.1  464.58  4994.4  464.08  4998.1  464.58  5000.0  464.58
  5007.1  467.24  5017.5  468.27  5026.8  467.82  5032.0  466.03  5038.3  467.03
  5070.6  466.47  5090.4  467.65  5121.7  467.61  5153.0  469.21  5163.4  468.86
  5184.3  466.23  5202.1  466.10  5242.6  468.23  5281.2  472.23  5403.1  476.00
#Mann=5,-1,0
  4479.6    0.05       0  4791.6    0.12       0  4994.1    0.07       0
  4998.1    0.12       0  5202.1    0.05       0
Bank Sta=4994.1,4998.1
Exp/Cntr=0.3,0.1

Type RM Length L Ch R = 1,10124,431,431,431
BEGIN DESCRIPTION:
Eagans Creek 22.0
END DESCRIPTION:
XS GIS Cut Line= 3
      2664926.01      6945960.99      2664376.00      6946561.00
      2664176.00      6947011.00
#Sta/Elev= 30
  4186.5  483.20  4264.5  480.97  4469.9  470.04  4618.5  468.13  4639.4  468.76
  4683.2  467.48  4702.9  465.96  4710.3  466.76  4809.6  466.82  4816.4  463.48
  4823.8  463.13  4830.6  466.73  4972.4  465.91  4986.6  465.19  4991.2  462.53
  4991.6  462.03  4995.6  462.53  4997.1  463.27  5009.3  462.97  5014.8  464.63
  5022.3  462.58  5031.8  464.59  5061.3  463.72  5066.8  466.41  5084.6  466.52
  5090.1  468.22  5113.3  470.46  5219.3  471.87  5362.3  476.17  5492.9  478.49
#Mann=5,-1,0
  4186.5    0.05       0  4683.2    0.12       0  4991.2    0.07       0
  4995.6    0.12       0  5031.8    0.05       0
Bank Sta=4991.2,4995.6
Exp/Cntr=0.3,0.1

Type RM Length L Ch R = 1,9693,464,464,464
BEGIN DESCRIPTION:
Eagans Creek 21.0
END DESCRIPTION:
XS GIS Cut Line= 3
      2664926.04      6945910.98      2664126.00      6946261.00
      2663425.98      6947011.02
#Sta/Elev= 30
  4135.5  483.72  4249.0  480.27  4272.4  477.80  4463.0  469.48  4665.1  467.27
  4779.5  464.54  4812.3  465.46  4855.9  464.93  4871.9  463.72  4888.7  464.81
  4965.1  464.53  4974.2  461.63  4974.6  461.13  4978.6  461.63  4986.9  465.08
  4996.1  466.02  5097.0  467.46  5270.4  470.64  5284.5  469.62  5320.2  469.90
  5334.4  471.25  5369.5  469.22  5376.9  470.15  5383.7  468.90  5397.9  470.31
  5447.2  471.32  5461.4  473.23  5482.9  472.55  5506.2  473.58  6034.7  482.87
#Mann=7,-1,0
  4135.5    0.05       0  4665.1    0.12       0  4974.2    0.03       0
  4978.6    0.12       0  4996.1    0.05       0  5097.0    0.12       0
  5506.2    0.05       0
Bank Sta=4974.2,4978.6
Exp/Cntr=0.3,0.1

Type RM Length L Ch R = 1,9229,440,440,440
BEGIN DESCRIPTION:
Eagans Creek 20.0
END DESCRIPTION:
XS GIS Cut Line= 3
      2664575.97      6945311.03      2663976.00      6945961.00
      2663275.98      6946511.02
#Sta/Elev= 30
  4110.9  485.18  4217.2  481.73  4266.5  478.47  4294.9  478.84  4301.7  477.04
  4464.7  468.70  4655.5  466.98  4698.0  465.30  4705.4  466.73  4740.6  466.67
  4790.5  463.91  4812.0  464.66  4832.4  462.40  4839.8  464.00  4924.9  463.60
  4931.7  461.56  4943.5  460.44  4944.0  459.94  4948.1  460.44  4967.4  464.05
  5031.6  462.67  5059.0  463.74  5151.8  462.43  5166.3  462.69  5177.5  464.41
  5187.1  465.67  5201.5  469.97  5216.0  471.09  5501.5  475.61  5885.7  478.63
#Mann=5,-1,0
  4110.9    0.05       0  4812.0    0.12       0  4943.5    0.07       0
  4948.1    0.12       0  5177.5    0.05       0
Bank Sta=4943.5,4948.1
Exp/Cntr=0.3,0.1

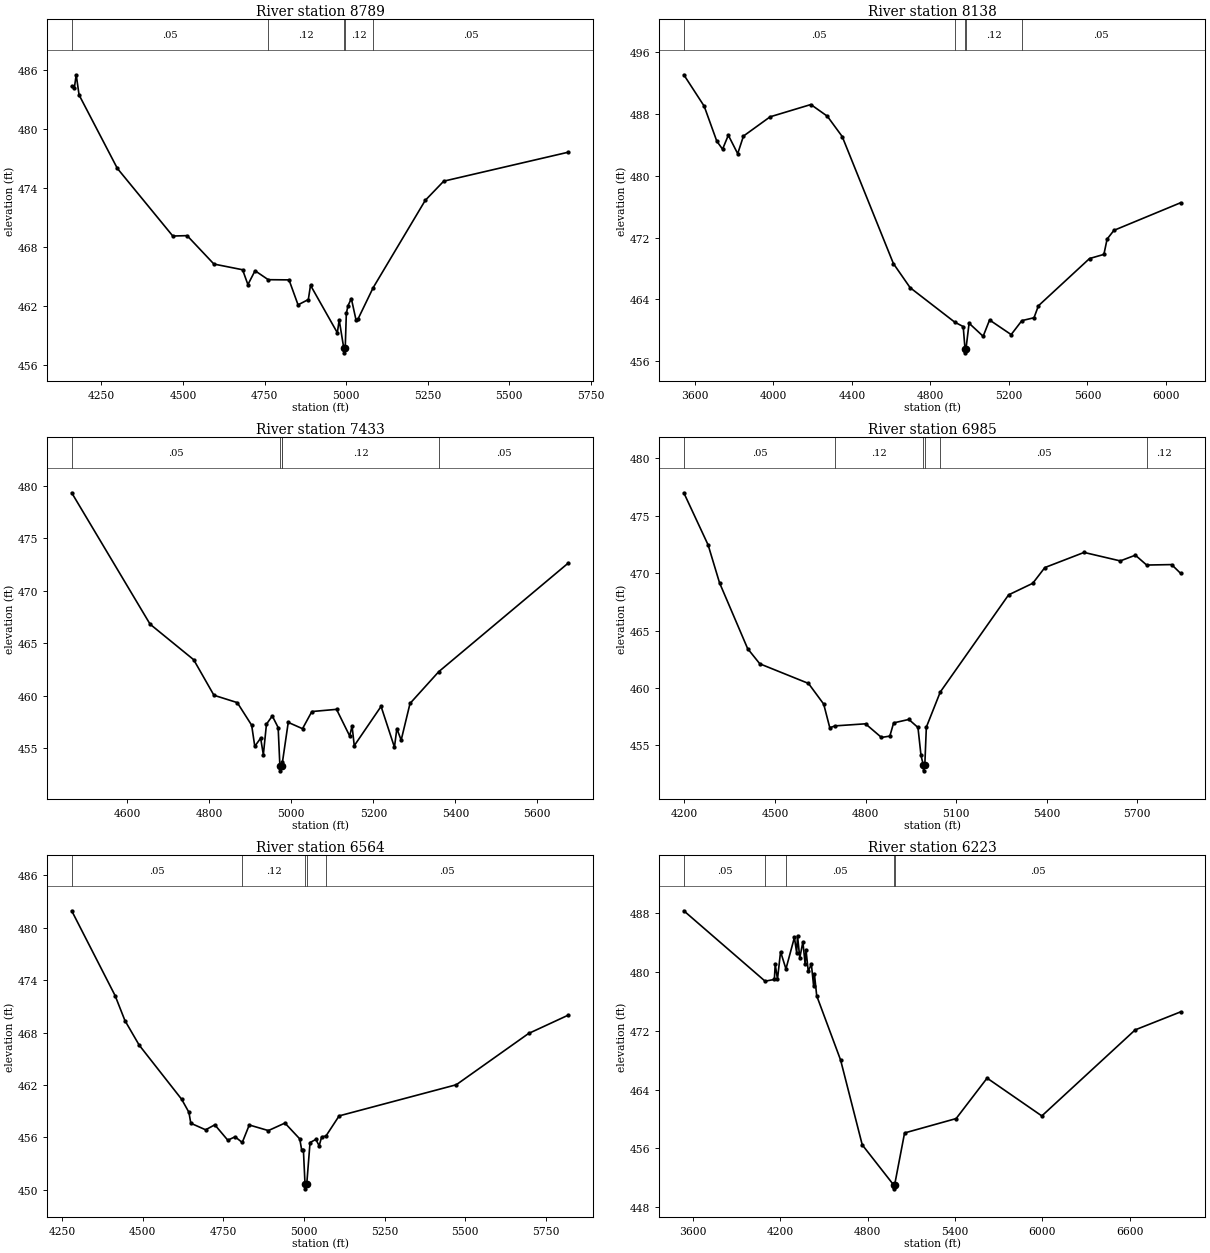
Type RM Length L Ch R = 1,8789,651,651,651
BEGIN DESCRIPTION:
Eagans Creek 19.0
END DESCRIPTION:
XS GIS Cut Line= 3
      2664525.96      6945311.02      2663776.00      6945711.00
      2663326.03      6946210.97
#Sta/Elev= 30
  4158.8  484.32  4166.9  484.13  4172.6  485.48  4181.4  483.43  4298.7  475.96
  4468.7  469.08  4512.6  469.12  4594.7  466.23  4682.6  465.65  4698.9  464.14
  4720.8  465.55  4761.2  464.64  4824.9  464.62  4852.6  462.08  4884.1  462.62
  4890.8  464.07  4973.0  459.24  4978.7  460.55  4992.6  457.70  4993.1  457.20
  4997.2  457.70  5000.6  461.22  5005.9  462.01  5015.9  462.72  5030.1  460.57
  5036.8  460.67  5082.7  463.82  5242.3  472.70  5299.1  474.66  5681.4  477.61
#Mann=5,-1,0
  4158.8    0.05       0  4761.2    0.12       0  4992.6    0.07       0
  4997.2    0.12       0  5082.7    0.05       0
Bank Sta=4992.6,4997.2
Exp/Cntr=0.3,0.1

Type RM Length L Ch R = 1,8138,705,705,705
BEGIN DESCRIPTION:
Eagans Creek 17.0
END DESCRIPTION:
XS GIS Cut Line= 3
      2664217.00      6943815.02      2663661.12      6945161.38
      2663157.97      6946111.02
#Sta/Elev= 30
  3543.4  493.07  3647.2  489.01  3711.5  484.48  3740.9  483.44  3770.2  485.25
  3818.0  482.86  3847.4  485.14  3983.2  487.63  4190.8  489.22  4274.7  487.71
  4350.5  485.08  4611.4  468.64  4696.7  465.52  4924.5  461.05  4967.1  460.49
  4976.3  457.59  4976.9  457.09  4981.1  457.59  4997.1  460.92  5068.7  459.23
  5101.4  461.34  5211.4  459.45  5266.1  461.26  5327.8  461.63  5350.4  463.18
  5610.7  469.29  5684.0  469.83  5700.3  471.81  5735.2  472.94  6074.7  476.51
#Mann=5,-1,0
  3543.4    0.05       0  4924.5    0.12       0  4976.3    0.07       0
  4981.1    0.12       0  5266.1    0.05       0
Bank Sta=4976.3,4981.1
Exp/Cntr=0.3,0.1

Type RM Length L Ch R = 1,7433,448,448,448
BEGIN DESCRIPTION:
Eagans Creek 16.0
END DESCRIPTION:
XS GIS Cut Line= 3
      2663625.97      6944411.03      2663226.00      6944761.00
      2663026.01      6945410.96
#Sta/Elev= 30
  4464.4  479.31  4655.6  466.81  4761.9  463.43  4811.3  460.05  4868.2  459.35
  4903.3  457.20  4910.9  455.19  4925.2  455.97  4931.8  454.39  4939.4  457.30
  4953.6  458.08  4967.9  456.98  4972.1  453.36  4972.7  452.86  4977.0  453.36
  4978.4  453.69  4992.5  457.47  5027.3  456.87  5050.1  458.50  5110.3  458.71
  5142.3  456.18  5148.2  457.12  5153.5  455.25  5218.9  458.99  5251.5  455.11
  5257.4  456.87  5267.9  455.78  5289.5  459.27  5359.5  462.29  5675.9  472.64
#Mann=5,-1,0
  4464.4    0.05       0  4972.1    0.07       0  4977.0    0.05       0
  4978.4    0.12       0  5359.5    0.05       0
Bank Sta=4972.1,4977
Exp/Cntr=0.3,0.1

Type RM Length L Ch R = 1,6985,421,421,421
BEGIN DESCRIPTION:
Eagans Creek 15.0
END DESCRIPTION:
XS GIS Cut Line= 3
      2663025.99      6944111.05      2662926.00      6944911.00
      2662908.41      6945750.74
#Sta/Elev= 30
  4197.8  477.01  4278.4  472.46  4316.2  469.16  4409.4  463.42  4449.7  462.10
  4610.9  460.39  4661.3  458.59  4681.5  456.53  4699.4  456.69  4799.9  456.87
  4852.8  455.68  4880.5  455.80  4893.1  456.95  4943.5  457.25  4973.7  456.55
  4983.8  454.11  4991.5  453.27  4992.1  452.77  4996.4  453.27  5001.5  456.58
  5047.6  459.64  5274.0  468.11  5354.1  469.12  5394.1  470.49  5524.1  471.81
  5644.1  471.07  5694.1  471.57  5731.5  470.71  5814.2  470.75  5843.9  469.99
#Mann=6,-1,0
  4197.8    0.05       0  4699.4    0.12       0  4991.5    0.07       0
  4996.4    0.12       0  5047.6    0.05       0  5731.5    0.12       0
Bank Sta=4991.5,4996.4
Exp/Cntr=0.3,0.1

Type RM Length L Ch R = 1,6564,341,341,341
BEGIN DESCRIPTION:
Eagans Creek 14.0
END DESCRIPTION:
XS GIS Cut Line= 3
      2662926.00      6944011.00      2662626.00      6944661.00
      2662426.00      6945460.99
#Sta/Elev= 30
  4279.9  481.92  4414.4  472.23  4445.1  469.36  4489.2  466.56  4620.9  460.37
  4643.4  458.88  4649.3  457.63  4695.2  456.88  4723.7  457.45  4764.0  455.69
  4786.5  456.08  4808.8  455.43  4830.6  457.43  4889.8  456.79  4941.2  457.65
  4987.1  455.84  4993.0  454.60  4998.4  454.60  5003.5  450.63  5004.2  450.13
  5008.7  450.63  5019.0  455.42  5037.0  455.78  5047.3  455.05  5055.1  456.07
  5068.4  456.17  5109.2  458.47  5472.5  462.03  5696.7  467.89  5820.4  470.00
#Mann=5,-1,0
  4279.9    0.05       0  4808.8    0.12       0  5003.5    0.07       0
  5008.7    0.12       0  5068.4    0.05       0
Bank Sta=5003.5,5008.7
Exp/Cntr=0.3,0.1

Type RM Length L Ch R = 1,6223,165,165,165
BEGIN DESCRIPTION:
Mapping XS cd8dc57c
END DESCRIPTION:
XS GIS Cut Line= 5
      2663649.18      6943551.30      2662828.12      6944051.55
      2662476.47      6944405.80      2661669.97      6945122.51
      2661297.22      6945907.02
#Sta/Elev= 30
  3539.4  488.35  4097.2  478.76  4160.7  479.00  4166.5  481.05  4182.0  479.04
  4203.3  482.77  4240.1  480.43  4298.2  484.72  4313.7  482.62  4319.5  484.97
  4335.0  481.92  4356.3  484.12  4371.8  481.09  4377.6  483.05  4393.1  480.11
  4414.4  481.09  4429.9  478.13  4435.7  479.69  4451.2  476.77  4615.1  468.02
  4763.6  456.47  4980.1  450.98  4980.9  450.48  4985.4  450.98  5054.0  458.09
  5407.7  460.05  5620.1  465.56  5995.6  460.41  6636.1  472.13  6947.5  474.58
#Mann=5,-1,0
  3539.4    0.05       0  4097.2   0.075       0  4240.1    0.05       0
  4980.1    0.05       0  4985.4    0.05       0
Bank Sta=4980.1,4985.4
Exp/Cntr=0.3,0.1

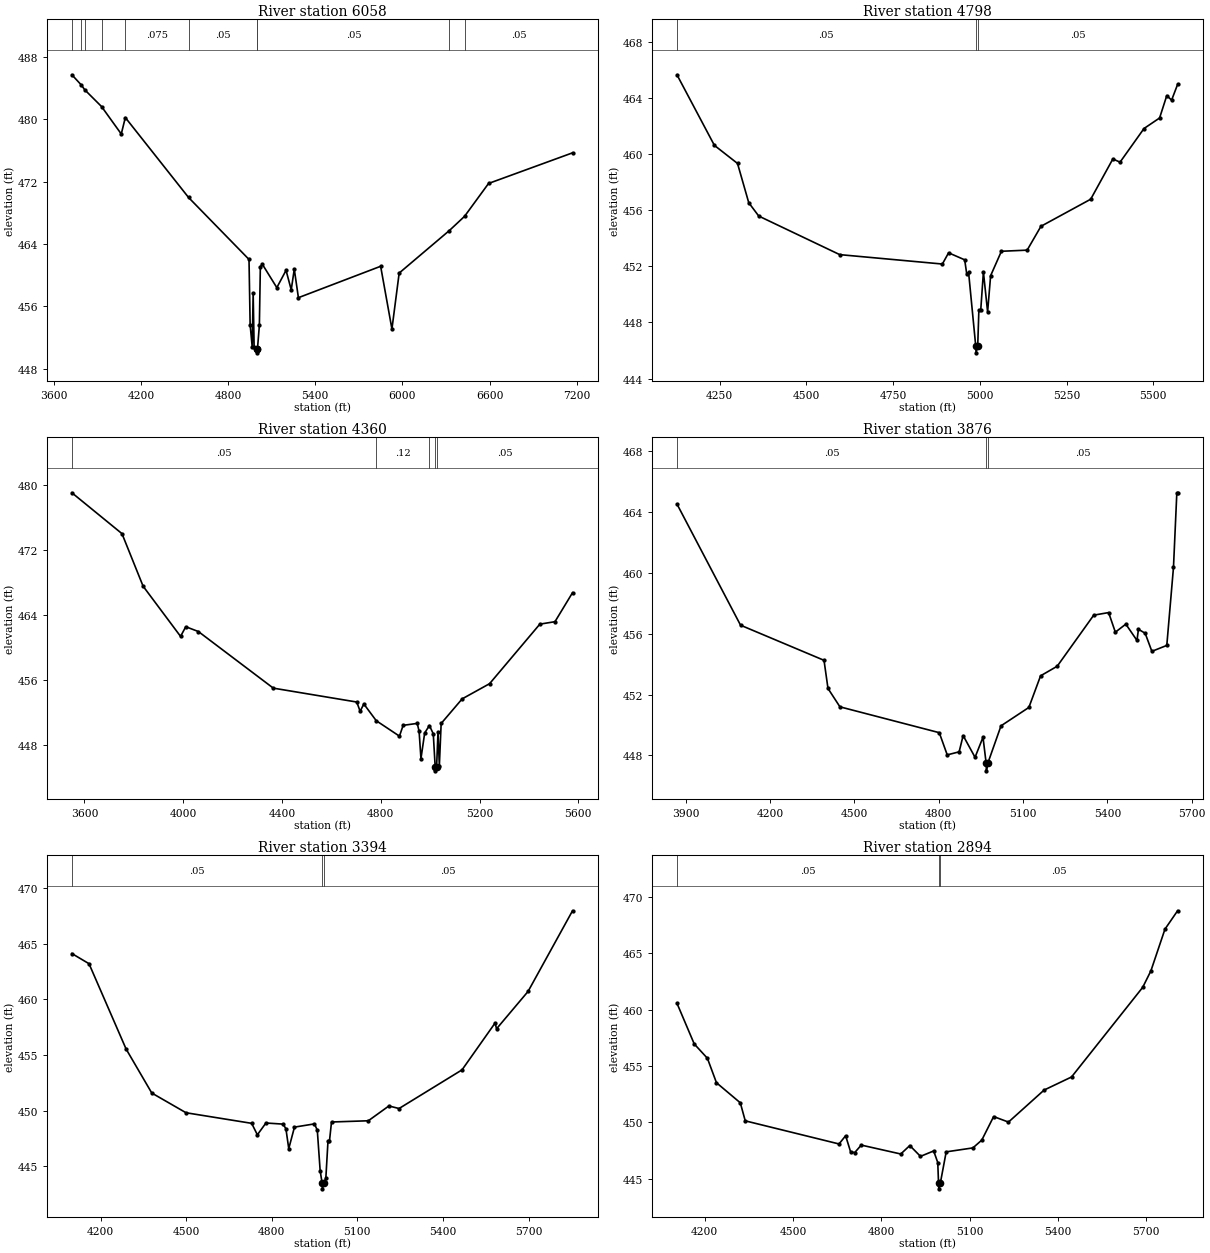
Type RM Length L Ch R = 1,6058,1260,1260,1260
BEGIN DESCRIPTION:
Mapping XS 065fc0fd
END DESCRIPTION:
XS GIS Cut Line= 6
      2663349.69      6943434.11      2662963.37      6943794.38
      2662389.77      6944273.94      2661862.40      6944759.02
      2661479.00      6945174.59      2661136.13      6945994.86
#Sta/Elev= 30
  3724.1  485.74  3789.9  484.41  3812.2  483.82  3928.4  481.66  4064.1  478.14
  4092.0  480.25  4527.4  469.99  4943.6  462.04  4951.4  453.66  4965.7  450.80
  4972.2  457.72  4978.8  450.81  4996.5  450.55  4997.3  450.05  5001.8  450.55
  5014.9  453.56  5021.7  461.11  5035.8  461.41  5135.1  458.42  5198.6  460.64
  5234.3  458.14  5255.3  460.79  5283.7  457.13  5849.9  461.16  5927.6  453.11
  5977.5  460.29  6322.6  465.74  6427.6  467.57  6592.9  471.79  7171.0  475.72
#Mann=10,-1,0
  3724.1   0.075       0  3789.9    0.05       0  3812.2   0.075       0
  3928.4    0.05       0  4092.0   0.075       0  4527.4    0.05       0
  4996.5    0.05       0  5001.8    0.05       0  6322.6   0.075       0
  6427.6    0.05       0
Bank Sta=4996.5,5001.8
Exp/Cntr=0.3,0.1

Type RM Length L Ch R = 1,4798,438,438,438
BEGIN DESCRIPTION:
Eagans Creek 10.0
END DESCRIPTION:
XS GIS Cut Line= 3
      2661675.98      6943561.04      2661326.00      6944361.00
      2661175.99      6944911.04
#Sta/Elev= 30
  4126.8  465.65  4234.7  460.62  4301.4  459.33  4333.8  456.53  4362.6  455.58
  4596.1  452.83  4892.0  452.16  4909.9  452.96  4956.3  452.46  4962.2  451.46
  4967.6  451.56  4988.1  446.33  4989.1  445.83  4993.9  446.33  4997.2  448.88
  5002.6  448.88  5010.3  451.59  5022.4  448.75  5031.1  451.33  5062.2  453.07
  5136.4  453.15  5176.2  454.85  5319.6  456.78  5383.5  459.65  5404.2  459.42
  5473.3  461.82  5518.2  462.57  5539.0  464.17  5552.8  463.84  5570.1  464.96
#Mann=3,-1,0
  4126.8    0.05       0  4988.1    0.03       0  4993.9    0.05       0
Bank Sta=4988.1,4993.9
Exp/Cntr=0.3,0.1

Type RM Length L Ch R = 1,4360,484,484,484
BEGIN DESCRIPTION:
Eagans Creek 9.0
END DESCRIPTION:
XS GIS Cut Line= 3
      2661725.98      6943211.03      2660926.00      6944411.00
      2661125.99      6944960.99
#Sta/Elev= 30
  3549.0  479.04  3751.8  474.01  3837.4  467.54  3989.1  461.36  4010.2  462.55
  4061.2  461.96  4364.7  454.99  4702.7  453.28  4716.3  452.14  4731.3  453.04
  4781.6  450.98  4875.5  449.08  4890.5  450.41  4947.6  450.65  4955.1  449.68
  4962.6  446.31  4977.7  449.47  4996.8  450.39  5012.5  449.37  5020.2  445.31
  5021.1  444.81  5026.0  445.31  5031.7  449.63  5037.1  445.43  5044.4  450.64
  5129.5  453.67  5240.6  455.54  5444.1  462.87  5505.3  463.17  5576.4  466.74
#Mann=5,-1,0
  3549.0    0.05       0  4781.6    0.12       0  4996.8    0.05       0
  5020.2    0.03       0  5026.0    0.05       0
Bank Sta=5020.2,5026
Exp/Cntr=0.3,0.1

Type RM Length L Ch R = 1,3876,482,482,482
BEGIN DESCRIPTION:
Eagans Creek 8.0
END DESCRIPTION:
XS GIS Cut Line= 3
      2661276.03      6943610.97      2660476.00      6944411.00
      2660726.00      6945010.99
#Sta/Elev= 30
  3868.6  464.53  4094.9  456.56  4391.9  454.25  4406.0  452.40  4448.5  451.19
  4802.0  449.49  4830.3  448.03  4872.7  448.23  4886.9  449.30  4929.3  447.87
  4957.6  449.19  4968.8  447.48  4969.7  446.98  4974.7  447.48  5021.7  449.94
  5120.8  451.15  5162.5  453.23  5221.6  453.86  5351.6  457.22  5404.6  457.39
  5428.5  456.10  5465.8  456.63  5505.4  455.56  5510.8  456.29  5534.6  456.03
  5558.5  454.84  5611.6  455.23  5635.4  460.37  5647.3  465.27  5650.0  465.27
#Mann=3,-1,0
  3868.6    0.05       0  4968.8    0.03       0  4974.7    0.05       0
Bank Sta=4968.8,4974.7
Exp/Cntr=0.3,0.1

Type RM Length L Ch R = 1,3394,500,500,500
BEGIN DESCRIPTION:
Eagans Creek 7.0
END DESCRIPTION:
XS GIS Cut Line= 3
      2660026.00      6943511.00      2660026.00      6944411.00
      2659726.00      6945211.00
#Sta/Elev= 30
  4099.6  464.10  4159.6  463.19  4289.6  455.53  4379.6  451.58  4499.6  449.81
  4729.6  448.86  4749.6  447.83  4779.6  448.89  4839.6  448.79  4849.6  448.38
  4859.6  446.59  4879.6  448.52  4949.6  448.81  4959.6  448.25  4969.6  444.62
  4976.5  443.48  4977.6  442.98  4982.6  443.48  4989.6  443.95  4997.1  447.28
  5002.3  447.28  5009.4  448.98  5138.4  449.09  5210.5  450.42  5246.1  450.19
  5466.8  453.66  5582.5  457.86  5587.9  457.35  5698.2  460.70  5854.0  467.94
#Mann=3,-1,0
  4099.6    0.05       0  4976.5    0.03       0  4982.6    0.05       0
Bank Sta=4976.5,4982.6
Exp/Cntr=0.3,0.1

Type RM Length L Ch R = 1,2894,482,482,482
BEGIN DESCRIPTION:
Eagans Creek 6.0
END DESCRIPTION:
XS GIS Cut Line= 3
      2659926.00      6943611.00      2659526.00      6944411.00
      2659626.01      6945211.04
#Sta/Elev= 30
  4105.6  460.56  4164.3  456.95  4209.0  455.68  4239.8  453.51  4320.8  451.73
  4337.6  450.13  4656.2  448.08  4678.6  448.81  4695.4  447.39  4709.3  447.31
  4731.7  447.98  4865.9  447.19  4896.6  447.94  4932.9  446.98  4977.7  447.46
  4991.6  446.43  4994.2  444.60  4995.2  444.10  5000.3  444.60  5020.2  447.38
  5110.9  447.73  5141.1  448.42  5181.4  450.51  5231.8  450.02  5352.8  452.86
  5446.0  454.02  5687.8  461.97  5715.6  463.43  5763.4  467.13  5806.3  468.76
#Mann=3,-1,0
  4105.6    0.05       0  4994.2    0.03       0  5000.3    0.05       0
Bank Sta=4994.2,5000.3
Exp/Cntr=0.3,0.1

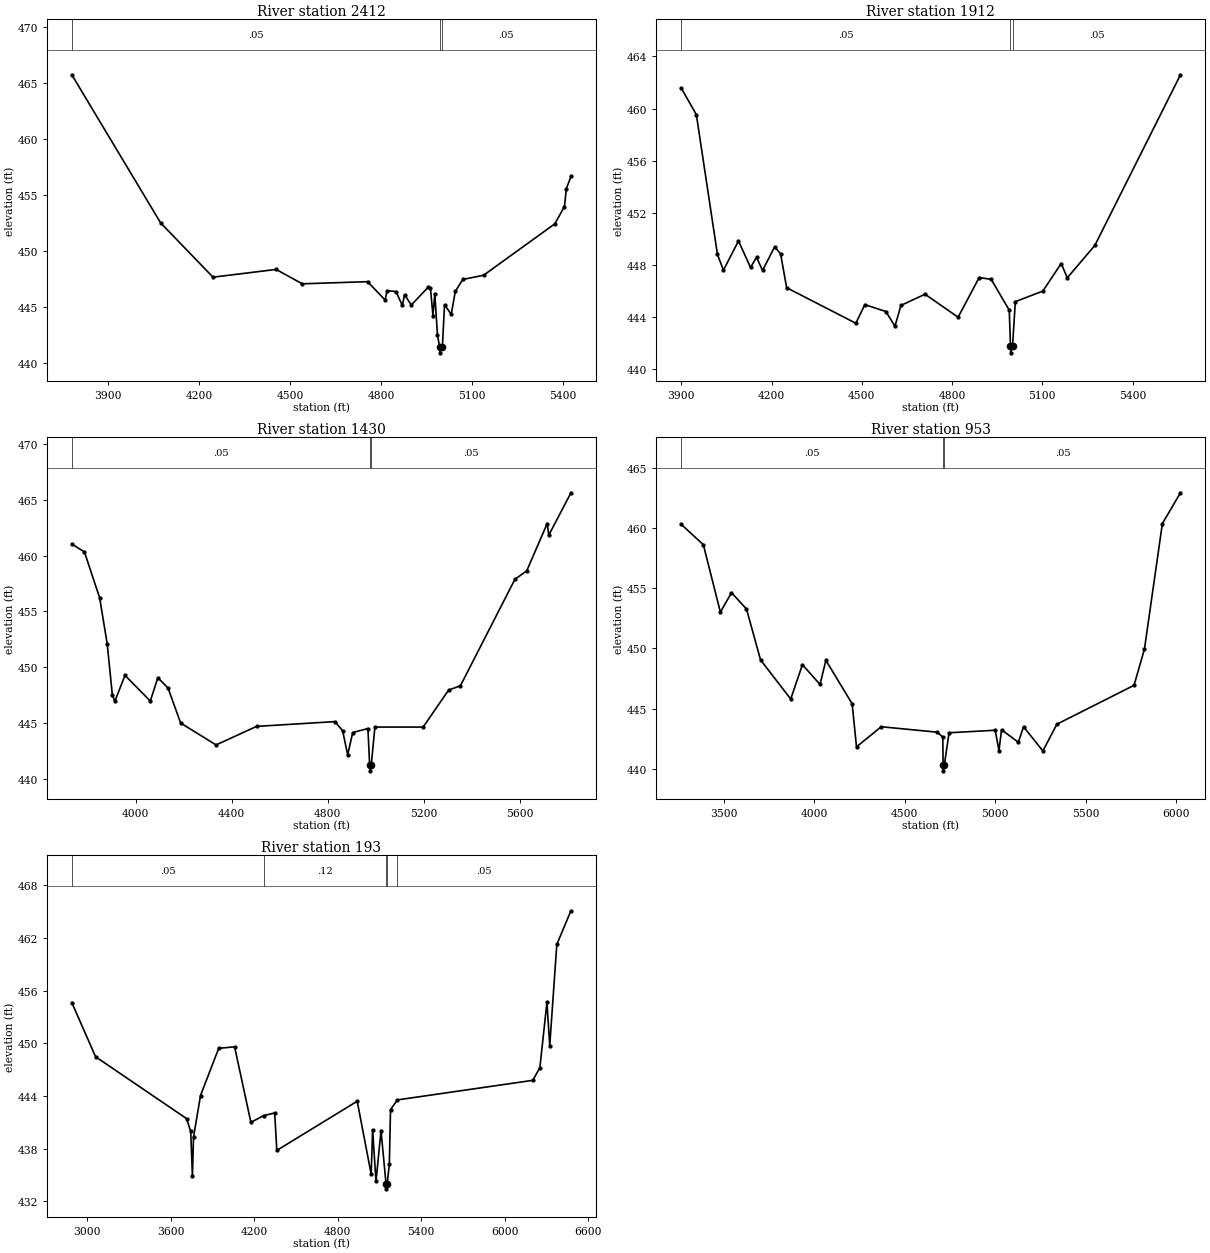
Type RM Length L Ch R = 1,2412,500,500,500
BEGIN DESCRIPTION:
Eagans Creek 5.0
END DESCRIPTION:
XS GIS Cut Line= 3
      2659776.01      6943460.98      2659076.00      6944461.00
      2659226.01      6944861.02
#Sta/Elev= 30
  3779.3  465.70  4072.7  452.50  4245.4  447.67  4453.7  448.36  4540.1  447.08
  4755.8  447.27  4813.8  445.63  4819.9  446.47  4849.6  446.39  4870.5  445.15
  4877.9  446.11  4900.1  445.19  4956.8  446.80  4963.4  446.67  4971.6  444.25
  4977.7  446.18  4986.5  442.54  4993.6  441.43  4994.7  440.93  5000.2  441.43
  5002.7  441.43  5009.8  445.22  5032.0  444.36  5045.4  446.41  5070.3  447.47
  5138.8  447.84  5373.8  452.42  5405.8  453.96  5412.1  455.56  5427.2  456.64
#Mann=3,-1,0
  3779.3    0.05       0  4993.6    0.03       0  5000.2    0.05       0
Bank Sta=4993.6,5000.2
Exp/Cntr=0.3,0.1

Type RM Length L Ch R = 1,1912,482,482,482
BEGIN DESCRIPTION:
Eagans Creek 4.0
END DESCRIPTION:
XS GIS Cut Line= 3
      2658576.00      6943361.01      2658576.00      6944461.00
      2658676.00      6945010.99
#Sta/Elev= 30
  3900.1  461.56  3950.1  459.53  4020.1  448.81  4040.1  447.59  4090.1  449.84
  4130.1  447.80  4150.1  448.58  4170.1  447.57  4210.1  449.38  4230.1  448.85
  4250.1  446.25  4480.1  443.52  4510.1  444.95  4580.1  444.42  4610.1  443.29
  4630.1  444.89  4710.1  445.75  4820.1  443.98  4890.1  447.03  4930.1  446.89
  4990.1  444.52  4994.2  441.75  4995.3  441.25  5000.9  441.75  5010.3  445.18
  5101.7  445.99  5162.7  448.10  5183.0  447.01  5274.5  449.49  5559.1  462.59
#Mann=3,-1,0
  3900.1    0.05       0  4994.2    0.03       0  5000.9    0.05       0
Bank Sta=4994.2,5000.9
Exp/Cntr=0.3,0.1

Type RM Length L Ch R = 1,1430,477,477,477
BEGIN DESCRIPTION:
Eagans Creek 3.0
END DESCRIPTION:
XS GIS Cut Line= 3
      2658526.01      6943360.96      2658126.00      6944561.00
      2658726.01      6945111.00
#Sta/Elev= 30
  3734.5  461.04  3787.2  460.33  3850.5  456.22  3882.1  452.07  3903.2  447.55
  3913.7  446.95  3955.9  449.28  4061.3  446.98  4092.9  449.07  4135.1  448.15
  4187.8  445.01  4335.4  443.05  4504.0  444.71  4830.8  445.14  4862.4  444.32
  4883.5  442.17  4904.6  444.16  4967.8  444.52  4975.0  441.23  4976.1  440.73
  4981.7  441.23  4996.8  444.65  5197.7  444.65  5303.8  447.96  5353.1  448.35
  5580.0  457.88  5629.3  458.64  5714.4  462.87  5721.2  461.84  5813.4  465.63
#Mann=3,-1,0
  3734.5    0.05       0  4975.0    0.03       0  4981.7    0.05       0
Bank Sta=4975,4981.7
Exp/Cntr=0.3,0.1

Type RM Length L Ch R = 1,953,760,760,760
BEGIN DESCRIPTION:
Eagans Creek 2.0
END DESCRIPTION:
XS GIS Cut Line= 3
      2658325.99      6943061.02      2657676.00      6944661.00
      2658475.97      6945310.97
#Sta/Elev= 30
  3265.0  460.29  3386.8  458.61  3480.8  453.01  3542.1  454.63  3625.1  453.27
  3702.7  449.05  3869.4  445.80  3934.2  448.65  4031.3  447.01  4063.7  449.01
  4208.8  445.41  4232.9  441.83  4369.5  443.50  4678.9  443.05  4709.5  442.64
  4711.5  440.34  4712.6  439.84  4718.2  440.34  4744.3  443.00  4999.2  443.21
  5020.0  441.52  5034.3  443.25  5127.0  442.21  5155.8  443.50  5262.5  441.49
  5339.9  443.71  5766.3  446.94  5823.8  449.95  5922.9  460.37  6022.7  462.92
#Mann=3,-1,0
  3265.0    0.05       0  4711.5    0.03       0  4718.2    0.05       0
Bank Sta=4711.5,4718.2
Exp/Cntr=0.3,0.1

Type RM Length L Ch R = 1,193,0,0,0
BEGIN DESCRIPTION:
Eagans Creek 1.0
END DESCRIPTION:
XS GIS Cut Line= 3
      2656976.00      6942911.03      2657201.65      6945191.95
      2658476.00      6945411.00
#Sta/Elev= 30
  2890.8  454.64  3061.6  448.47  3714.8  441.42  3744.9  439.95  3757.1  434.88
  3765.0  439.31  3815.3  444.05  3945.9  449.43  4060.2  449.60  4177.0  440.99
  4269.1  441.76  4347.9  442.06  4363.3  437.79  4940.7  443.40  5041.2  435.07
  5051.3  440.16  5075.5  434.25  5111.6  440.04  5148.2  433.91  5149.4  433.41
  5155.3  433.91  5171.5  436.24  5179.9  442.44  5229.5  443.55  6201.9  445.78
  6252.7  447.23  6303.4  454.67  6323.5  449.74  6374.4  461.28  6475.9  465.11
#Mann=5,-1,0
  2890.8    0.05       0  4269.1    0.12       0  5148.2    0.07       0
  5155.3    0.12       0  5229.5    0.05       0
Bank Sta=5148.2,5155.3
Exp/Cntr=0.3,0.1

Chan Stop Cuts=-1