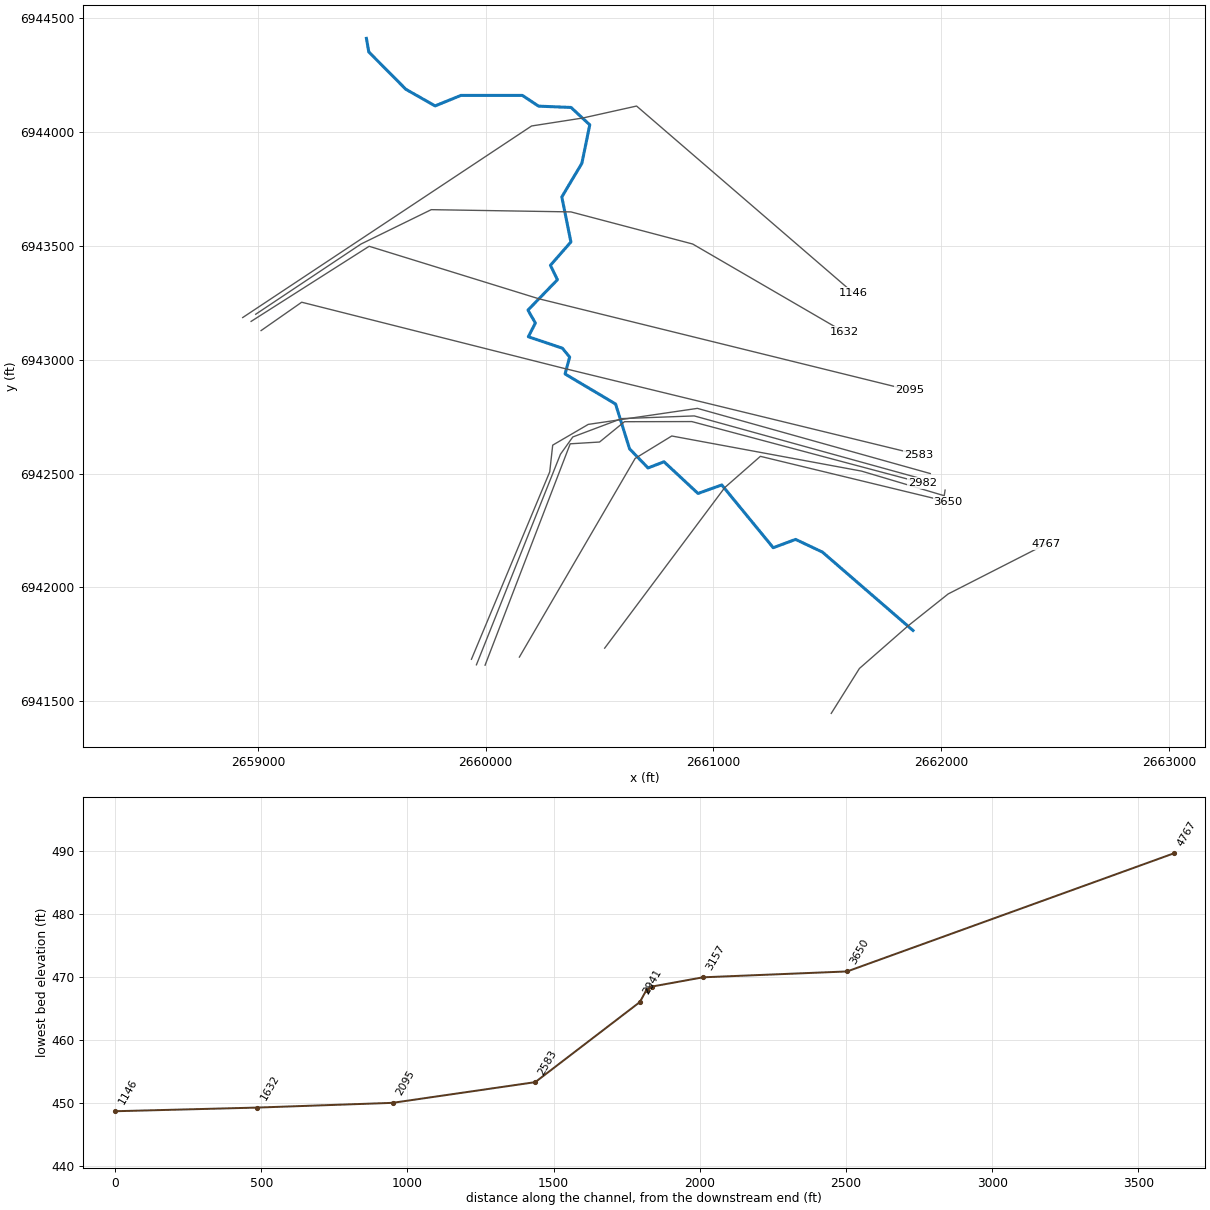
--- Eagans Creek Trib 2.prj (project) ---

Proj Title=Eagans Creek Trib 2 Base Level Engineering
Current Plan=p01
Default Exp/Contr=0.3,0.1
English Units
Geom File=g01
Flow File=f01
Plan File=p01
BEGIN DESCRIPTION:
Eagans Creek Trib 2
END DESCRIPTION:

--- Eagans Creek Trib 2.p01 (plan) ---

Plan Title=Multiple Run
Short Identifier=Multiple
Geom File=g01
Flow File=f01
Subcritical Flow
K Sum by GR= 0
Std Step Tol= 0.01
Critical Tol= 0.01
Num of Std Step Trials= 20
Max Error Tol= 0.3
Flow Tol Ratio= 0.001
Split Flow NTrial= 30
Split Flow Tol= 0.02
Split Flow Ratio= 0.02
Log Output Level= 0
Friction Slope Method= 1
Unsteady Friction Slope Method= 2
Unsteady Bridges Friction Slope Method= 1
Parabolic Critical Depth
Global Vel Dist=  1 , 1 , 1
Global Log Level= 0
CheckData=True
Encroach Param= -1, 0, 0, 0
BEGIN DESCRIPTION:
Multiple Run
END DESCRIPTION:

--- Eagans Creek Trib 2.f01 (steady flow) ---

Flow Title=Multiple
Number of Profiles=7
Profile Names=10-year,25-year,50-year,1pct_min,100-year,1pct_plu,500-year
River Rch & RM= Eagans Creek Tri,Reach-1,4767
     158     192     218     123     246     490     310
Boundary for River Rch & Prof#=Eagans Creek Tri,Reach-1,1
Up Type=0
Dn Type=3
Dn Slope=0.005
Boundary for River Rch & Prof#=Eagans Creek Tri,Reach-1,2
Up Type=0
Dn Type=3
Dn Slope=0.005
Boundary for River Rch & Prof#=Eagans Creek Tri,Reach-1,3
Up Type=0
Dn Type=3
Dn Slope=0.005
Boundary for River Rch & Prof#=Eagans Creek Tri,Reach-1,4
Up Type=0
Dn Type=3
Dn Slope=0.005
Boundary for River Rch & Prof#=Eagans Creek Tri,Reach-1,5
Up Type=0
Dn Type=3
Dn Slope=0.005
Boundary for River Rch & Prof#=Eagans Creek Tri,Reach-1,6
Up Type=0
Dn Type=3
Dn Slope=0.005
Boundary for River Rch & Prof#=Eagans Creek Tri,Reach-1,7
Up Type=0
Dn Type=3
Dn Slope=0.005

--- Eagans Creek Trib 2.g01 (geometry) ---

Geom Title=Existing Conditions

River Reach=Eagans Creek Tri,Reach-1
Reach XY= 30
      2661876.00      6941811.00      2661478.30      6942155.17
      2661360.58      6942210.86      2661262.27      6942174.40
      2661036.35      6942449.96      2660932.05      6942412.66
      2660782.67      6942551.70      2660712.64      6942524.64
      2660631.52      6942608.54      2660570.08      6942805.31
      2660348.36      6942937.29      2660368.53      6943011.23
      2660336.49      6943050.48      2660187.08      6943100.63
      2660217.94      6943160.99      2660185.29      6943217.67
      2660314.76      6943351.00      2660284.02      6943414.33
      2660373.93      6943516.86      2660334.04      6943714.32
      2660422.18      6943862.59      2660456.73      6944031.08
      2660374.56      6944107.46      2660231.94      6944113.27
      2660160.78      6944160.48      2659891.21      6944160.46
      2659777.72      6944114.34      2659649.18      6944187.29
      2659486.51      6944351.21      2659476.00      6944411.00

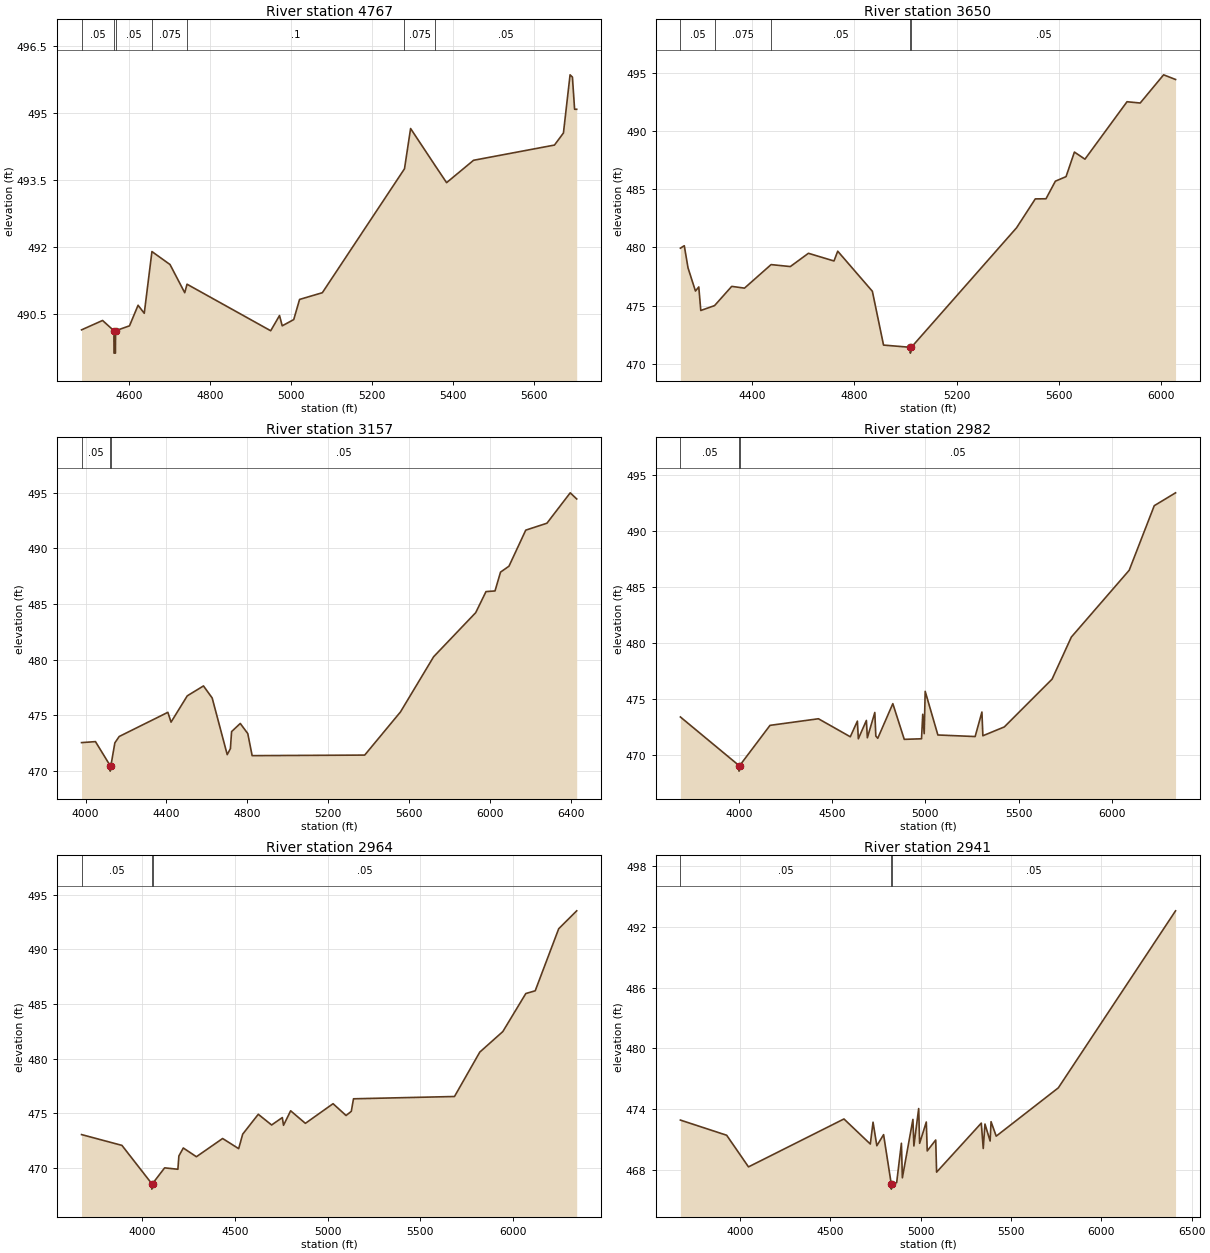
Type RM Length L Ch R = 1,4767,1117,1117,1117
BEGIN DESCRIPTION:
Eagans Creek Trib 2 1.0
END DESCRIPTION:
XS GIS Cut Line= 5
      2661517.07      6941446.97      2661640.81      6941644.23
      2661855.61      6941832.22      2662030.55      6941971.46
      2662460.58      6942190.73
#Sta/Elev= 30
  4481.7  490.15  4533.7  490.36  4561.8  490.13  4562.0  489.63  4565.5  489.63
  4565.8  490.13  4600.3  490.24  4621.5  490.70  4636.8  490.52  4655.8  491.90
  4700.5  491.61  4736.9  490.98  4742.6  491.17  4949.5  490.13  4971.3  490.47
  4978.0  490.24  5006.5  490.38  5020.9  490.83  5077.2  490.98  5280.4  493.75
  5295.5  494.65  5355.6  493.83  5384.5  493.44  5451.2  493.94  5651.3  494.28
  5673.5  494.55  5689.9  495.85  5695.7  495.80  5701.1  495.08  5706.3  495.08
#Mann=7,-1,0
  4481.7    0.05       0  4561.8    0.07       0  4565.8    0.05       0
  4655.8   0.075       0  4742.6     0.1       0  5280.4   0.075       0
  5355.6    0.05       0
Bank Sta=4561.8,4565.8
Exp/Cntr=0.3,0.1

Type RM Length L Ch R = 1,3650,493,493,493
BEGIN DESCRIPTION:
Eagans Creek Trib 2 2.0
END DESCRIPTION:
XS GIS Cut Line= 4
      2660522.26      6941733.40      2661049.68      6942438.58
      2661205.89      6942575.63      2662030.46      6942375.99
#Sta/Elev= 30
  4119.4  479.93  4134.6  480.14  4149.2  478.24  4178.3  476.25  4191.3  476.60
  4199.2  474.58  4253.1  475.00  4320.1  476.65  4370.1  476.50  4474.2  478.52
  4549.3  478.35  4620.2  479.49  4720.2  478.83  4734.8  479.67  4870.3  476.23
  4914.0  471.61  5018.7  471.42  5019.0  470.92  5022.7  471.42  5434.3  481.68
  5507.6  484.16  5549.4  484.17  5586.1  485.68  5627.9  486.07  5660.6  488.18
  5701.8  487.57  5866.4  492.50  5917.9  492.39  6009.5  494.81  6056.2  494.41
#Mann=5,-1,0
  4119.4    0.05       0  4253.1   0.075       0  4474.2    0.05       0
  5018.7    0.03       0  5022.7    0.05       0
Bank Sta=5018.7,5022.7
Exp/Cntr=0.3,0.1

Type RM Length L Ch R = 1,3157,175,175,175
BEGIN DESCRIPTION:
Mapping XS 0bf1a0b2
END DESCRIPTION:
XS GIS Cut Line= 6
      2660147.70      6941694.12      2660656.07      6942566.55
      2660816.78      6942664.94      2661649.86      6942510.79
      2662013.14      6942402.67      2662016.98      6942427.44
#Sta/Elev= 30
  3980.4  472.55  4049.3  472.64  4121.7  470.49  4122.0  469.99  4125.7  470.49
  4145.2  472.53  4166.7  473.10  4407.4  475.27  4423.2  474.39  4503.4  476.75
  4583.6  477.64  4626.6  476.56  4701.1  471.47  4716.8  472.01  4722.6  473.54
  4765.6  474.27  4802.8  473.36  4824.3  471.38  5381.2  471.43  5558.3  475.31
  5722.1  480.26  5930.3  484.22  5981.2  486.11  6025.8  486.17  6053.1  487.86
  6094.8  488.39  6177.9  491.63  6282.6  492.25  6397.9  494.98  6429.9  494.43
#Mann=3,-1,0
  3980.4    0.05       0  4121.7    0.03       0  4125.7    0.05       0
Bank Sta=4121.7,4125.7
Exp/Cntr=0.3,0.1

Type RM Length L Ch R = 1,2982,18,18,18
BEGIN DESCRIPTION:
Eagans Creek Trib 2 4.0
END DESCRIPTION:
XS GIS Cut Line= 6
      2659997.13      6941658.60      2660370.82      6942630.61
      2660499.73      6942638.42      2660609.19      6942727.68
      2660904.68      6942728.26      2661916.40      6942458.73
#Sta/Elev= 30
  3684.8  473.36  3999.3  469.02  3999.5  468.52  4003.3  469.02  4165.8  472.61
  4425.7  473.20  4596.7  471.59  4634.8  472.99  4639.9  471.41  4683.1  473.05
  4688.3  471.50  4728.3  473.76  4733.7  471.66  4744.0  471.45  4825.0  474.55
  4886.4  471.36  4979.0  471.41  4985.5  473.60  4993.4  471.87  4998.7  475.65
  5066.8  471.75  5266.8  471.61  5303.2  473.80  5308.3  471.68  5423.5  472.47
  5679.8  476.74  5783.2  480.50  6093.7  486.47  6228.2  492.24  6342.5  493.39
#Mann=3,-1,0
  3684.8    0.05       0  3999.3    0.04       0  4003.3    0.05       0
Bank Sta=3999.3,4003.3
Exp/Cntr=0.3,0.1

Type RM Length L Ch R = 1,2964,23,23,23
BEGIN DESCRIPTION:
Eagans Creek Trib 2 5.0
END DESCRIPTION:
XS GIS Cut Line= 6
      2659959.13      6941660.30      2660328.03      6942584.73
      2660382.28      6942660.69      2660596.32      6942741.27
      2660915.53      6942753.05      2661901.19      6942480.62
#Sta/Elev= 30
  3674.7  473.03  3892.3  472.04  4053.0  468.53  4053.2  468.03  4057.0  468.53
  4122.3  469.98  4193.7  469.85  4199.1  471.07  4222.9  471.80  4293.5  471.00
  4434.7  472.67  4521.2  471.74  4542.9  473.07  4626.8  474.89  4698.7  473.91
  4756.4  474.59  4762.8  473.88  4801.2  475.21  4880.6  474.06  5029.7  475.86
  5099.7  474.78  5128.0  475.16  5139.8  476.31  5683.9  476.52  5820.2  480.59
  5944.2  482.47  6068.2  485.96  6118.8  486.21  6245.4  491.90  6342.3  493.54
#Mann=3,-1,0
  3674.7    0.05       0  4053.0    0.04       0  4057.0    0.05       0
Bank Sta=4053,4057
Exp/Cntr=0.3,0.1

Type RM Length L Ch R = 1,2941,358,358,358
BEGIN DESCRIPTION:
Eagans Creek Trib 2 3.0
END DESCRIPTION:
XS GIS Cut Line= 6
      2659937.23      6941684.65      2660280.98      6942507.56
      2660294.00      6942624.75      2660450.25      6942715.90
      2660929.42      6942786.21      2661951.89      6942500.02
#Sta/Elev= 30
  3670.2  472.90  3926.3  471.40  4047.1  468.27  4575.5  473.01  4721.4  470.53
  4736.5  472.69  4757.5  470.36  4794.8  471.46  4837.4  466.57  4837.6  466.07
  4841.4  466.57  4867.2  466.71  4893.5  470.61  4898.8  467.19  4957.2  472.97
  4962.5  470.34  4989.1  474.04  4994.3  470.60  5031.3  472.71  5036.4  469.85
  5083.4  470.93  5088.3  467.75  5335.7  472.60  5346.5  470.09  5356.0  472.51
  5384.5  470.83  5389.7  472.74  5418.3  471.31  5762.1  476.09  6410.9  493.60
#Mann=3,-1,0
  3670.2    0.05       0  4837.4    0.03       0  4841.4    0.05       0
Bank Sta=4837.4,4841.4
Exp/Cntr=0.3,0.1

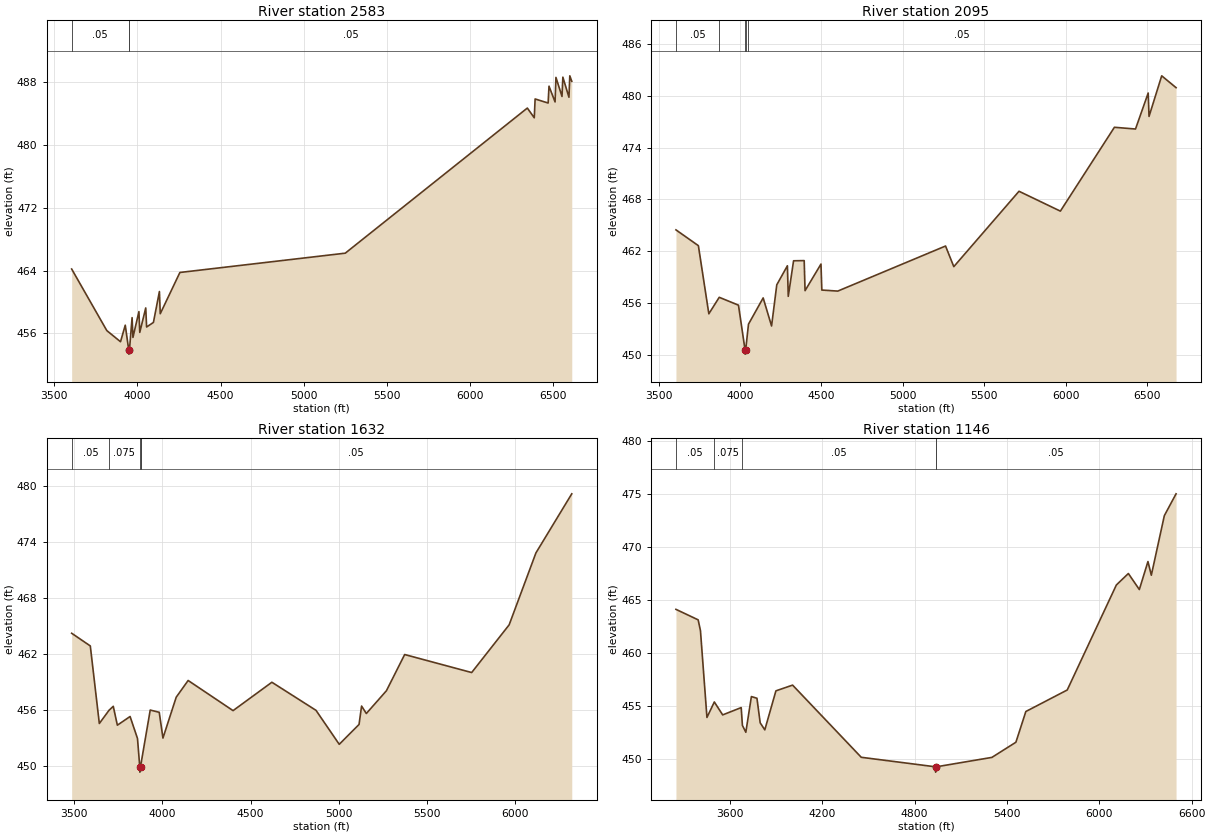
Type RM Length L Ch R = 1,2583,488,488,488
BEGIN DESCRIPTION:
Eagans Creek Trib 2 6.0
END DESCRIPTION:
XS GIS Cut Line= 4
      2659013.63      6943127.85      2659191.91      6943252.32
      2660334.09      6942964.17      2661900.52      6942582.74
#Sta/Elev= 30
  3604.6  464.22  3816.0  456.37  3898.4  454.95  3926.9  457.06  3948.0  453.87
  3948.3  453.37  3952.0  453.87  3968.0  458.02  3973.1  455.50  4009.1  458.79
  4014.2  456.14  4050.1  459.26  4055.3  456.83  4096.3  457.41  4132.3  461.35
  4137.4  458.52  4255.5  463.78  5250.0  466.24  6345.0  484.74  6386.7  483.50
  6391.8  485.90  6470.1  485.38  6475.3  487.53  6511.8  485.52  6517.0  488.65
  6553.5  486.22  6558.7  488.68  6595.3  486.12  6600.4  488.85  6612.2  488.15
#Mann=3,-1,0
  3604.6    0.05       0  3948.0    0.05       0  3952.0    0.05       0
Bank Sta=3948,3952
Exp/Cntr=0.3,0.1

Type RM Length L Ch R = 1,2095,463,463,463
BEGIN DESCRIPTION:
Eagans Creek Trib 2 7.0
END DESCRIPTION:
XS GIS Cut Line= 4
      2658969.80      6943168.17      2659488.01      6943497.94
      2660232.37      6943267.67      2661860.97      6942866.00
#Sta/Elev= 30
  3606.6  464.48  3744.3  462.65  3808.5  454.76  3872.4  456.67  3990.5  455.76
  4030.8  450.59  4031.1  450.09  4034.8  450.59  4052.0  453.56  4142.1  456.60
  4193.7  453.35  4225.7  458.12  4290.9  460.32  4296.2  456.78  4328.8  460.90
  4394.0  460.92  4399.3  457.44  4497.1  460.52  4502.3  457.51  4600.2  457.39
  5262.0  462.61  5312.7  460.22  5713.1  468.95  5967.1  466.65  6298.9  476.36
  6428.5  476.16  6506.3  480.33  6511.5  477.62  6589.3  482.32  6677.4  480.95
#Mann=5,-1,0
  3606.6    0.05       0  3872.4   0.075       0  4030.8    0.05       0
  4034.8   0.075       0  4052.0    0.05       0
Bank Sta=4030.8,4034.8
Exp/Cntr=0.3,0.1

Type RM Length L Ch R = 1,1632,486,486,486
BEGIN DESCRIPTION:
Mapping XS f8bbd8eb
END DESCRIPTION:
XS GIS Cut Line= 6
      2658989.92      6943199.55      2659452.38      6943507.86
      2659760.68      6943658.73      2660374.01      6943648.89
      2660908.62      6943507.86      2661572.72      6943121.83
#Sta/Elev= 30
  3486.6  464.22  3592.2  462.86  3643.3  454.55  3698.4  455.97  3722.3  456.39
  3745.5  454.37  3817.6  455.30  3859.6  452.94  3872.7  449.84  3872.9  449.34
  3876.7  449.84  3877.9  450.06  3931.7  455.99  3982.8  455.75  4003.8  452.99
  4079.0  457.37  4146.5  459.16  4401.0  455.93  4621.0  458.97  4871.0  455.96
  5002.7  452.32  5114.9  454.45  5129.2  456.42  5156.2  455.62  5270.0  458.06
  5373.4  461.94  5753.0  460.01  5965.3  465.12  6117.1  472.83  6320.1  479.16
#Mann=5,-1,0
  3486.6    0.05       0  3698.4   0.075       0  3872.7    0.03       0
  3876.7   0.075       0  3877.9    0.05       0
Bank Sta=3872.7,3876.7
Exp/Cntr=0.3,0.1

Type RM Length L Ch R = 1,1146,0,0,0
BEGIN DESCRIPTION:
Eagans Creek Trib 2 8.0
END DESCRIPTION:
XS GIS Cut Line= 5
      2658932.85      6943185.03      2660201.33      6944026.20
      2660426.58      6944061.25      2660662.29      6944113.68
      2661614.47      6943292.72
#Sta/Elev= 30
  3250.0  464.12  3394.1  463.13  3409.2  462.11  3451.3  453.92  3499.2  455.38
  3553.6  454.16  3673.8  454.85  3681.7  453.17  3703.9  452.52  3740.0  455.89
  3776.1  455.73  3797.2  453.41  3827.2  452.75  3899.4  456.43  4007.7  456.97
  4453.7  450.16  4936.7  449.26  4936.9  448.76  4940.7  449.26  5302.5  450.15
  5458.3  451.58  5523.0  454.48  5791.8  456.51  6111.0  466.42  6188.9  467.50
  6260.2  465.99  6316.2  468.63  6338.1  467.34  6422.6  472.96  6498.7  475.02
#Mann=5,-1,0
  3250.0    0.05       0  3499.2   0.075       0  3681.7    0.05       0
  4936.7    0.03       0  4940.7    0.05       0
Bank Sta=4936.7,4940.7
Exp/Cntr=0.3,0.1

Chan Stop Cuts=-1