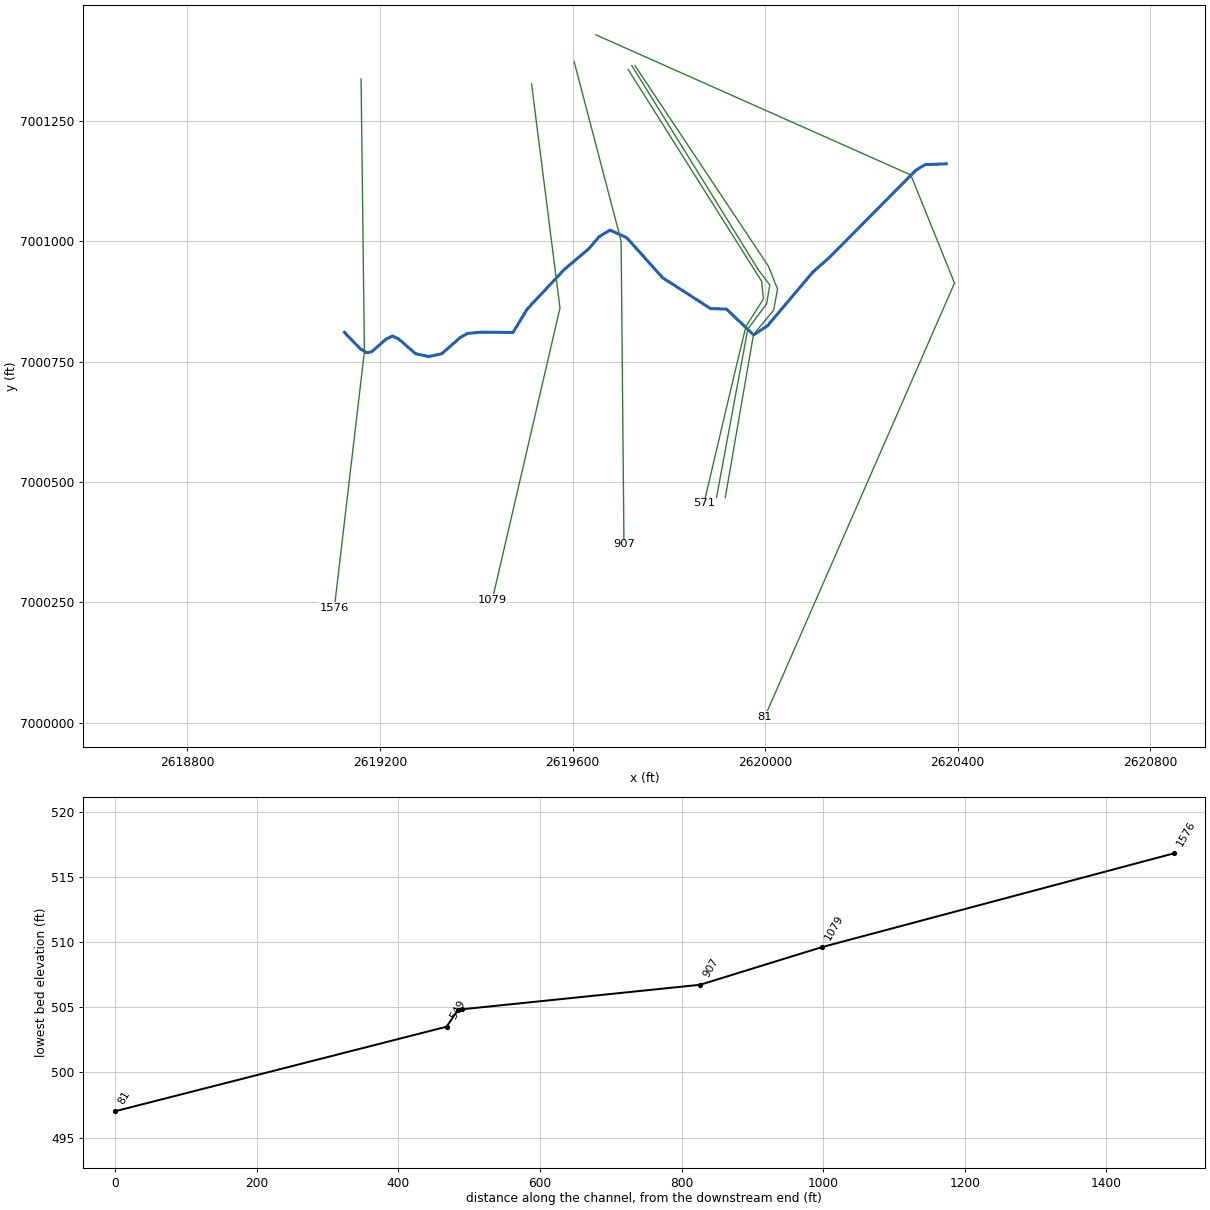
--- Hackberry Creek Tributary 1.prj (project) ---

Proj Title=Hackberry Creek Tributary 1 Base Level Engineering
Current Plan=p01
Default Exp/Contr=0.3,0.1
English Units
Geom File=g01
Flow File=f01
Plan File=p01
BEGIN DESCRIPTION:
Hackberry Creek Tributary 1
END DESCRIPTION:

--- Hackberry Creek Tributary 1.p01 (plan) ---

Plan Title=Multiple Run
Short Identifier=Multiple
Geom File=g01
Flow File=f01
Subcritical Flow
K Sum by GR= 0
Std Step Tol= 0.01
Critical Tol= 0.01
Num of Std Step Trials= 20
Max Error Tol= 0.3
Flow Tol Ratio= 0.001
Split Flow NTrial= 30
Split Flow Tol= 0.02
Split Flow Ratio= 0.02
Log Output Level= 0
Friction Slope Method= 1
Unsteady Friction Slope Method= 2
Unsteady Bridges Friction Slope Method= 1
Parabolic Critical Depth
Global Vel Dist=  1 , 1 , 1
Global Log Level= 0
CheckData=True
Encroach Param= -1, 0, 0, 0
BEGIN DESCRIPTION:
Multiple Run
END DESCRIPTION:

--- Hackberry Creek Tributary 1.f01 (steady flow) ---

Flow Title=Multiple
Number of Profiles=7
Profile Names=10-year,25-year,50-year,1pct_min,100-year,1pct_plu,500-year
River Rch & RM= Hackberry Creek ,Reach-1,1576
      80      93     102      56     111     222     132
River Rch & RM= Hackberry Creek ,Reach-1,81
    1992    2802    3486    2140    4271    8521    6415
Boundary for River Rch & Prof#=Hackberry Creek ,Reach-1,1
Up Type=0
Dn Type=3
Dn Slope=0.005
Boundary for River Rch & Prof#=Hackberry Creek ,Reach-1,2
Up Type=0
Dn Type=3
Dn Slope=0.005
Boundary for River Rch & Prof#=Hackberry Creek ,Reach-1,3
Up Type=0
Dn Type=3
Dn Slope=0.005
Boundary for River Rch & Prof#=Hackberry Creek ,Reach-1,4
Up Type=0
Dn Type=3
Dn Slope=0.005
Boundary for River Rch & Prof#=Hackberry Creek ,Reach-1,5
Up Type=0
Dn Type=3
Dn Slope=0.005
Boundary for River Rch & Prof#=Hackberry Creek ,Reach-1,6
Up Type=0
Dn Type=3
Dn Slope=0.005
Boundary for River Rch & Prof#=Hackberry Creek ,Reach-1,7
Up Type=0
Dn Type=3
Dn Slope=0.005

--- Hackberry Creek Tributary 1.g01 (geometry) ---

Geom Title=Existing Conditions

River Reach=Hackberry Creek ,Reach-1
Reach XY= 30
      2619126.00      7000811.00      2619159.22      7000776.69
      2619172.66      7000768.51      2619182.66      7000770.60
      2619212.62      7000796.93      2619225.91      7000803.33
      2619239.18      7000796.90      2619273.70      7000766.63
      2619300.96      7000760.68      2619328.17      7000766.40
      2619366.33      7000800.09      2619381.93      7000808.70
      2619410.84      7000811.39      2619476.15      7000810.70
      2619505.74      7000859.33      2619582.99      7000941.80
      2619633.34      7000984.33      2619655.04      7001009.50
      2619677.61      7001023.39      2619712.33      7001007.77
      2619786.99      7000924.44      2619886.63      7000860.39
      2619919.88      7000859.19      2619976.22      7000805.51
      2620004.87      7000824.61      2620099.49      7000936.59
      2620134.16      7000967.05      2620312.73      7001147.53
      2620332.14      7001159.32      2620376.00      7001161.00

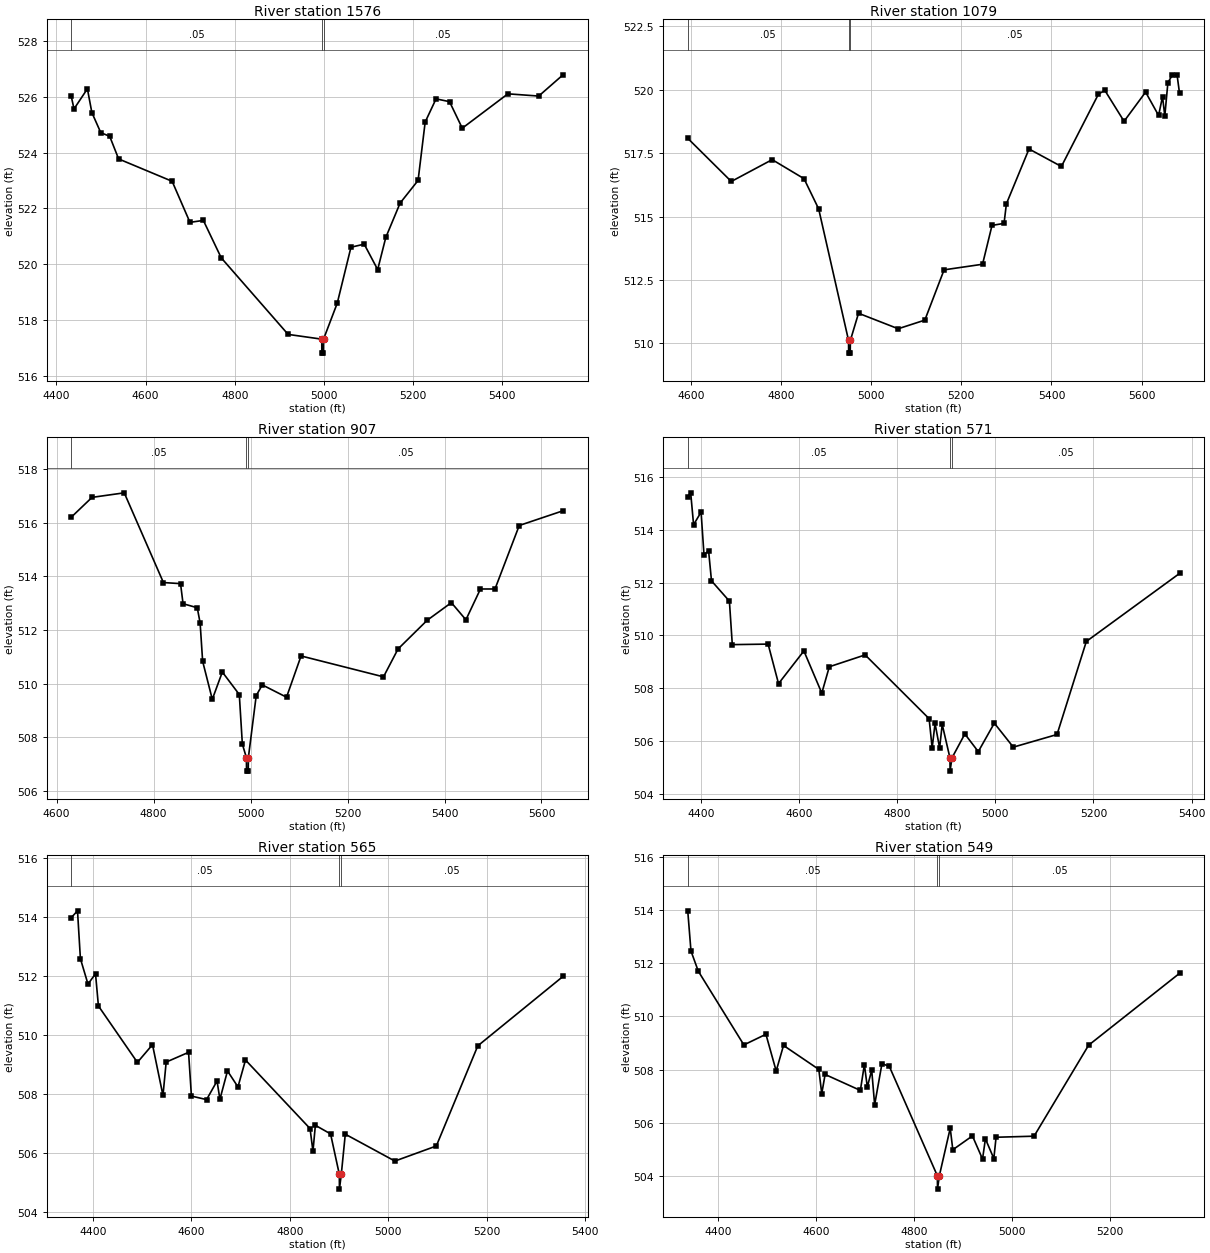
Type RM Length L Ch R = 1,1576,497,497,497
BEGIN DESCRIPTION:
Mapping XS d235c78c
END DESCRIPTION:
XS GIS Cut Line= 3
      2619160.64      7001337.23      2619167.59      7000771.22
      2619105.09      7000238.22
#Sta/Elev= 30
  4433.4  526.01  4439.6  525.56  4469.6  526.28  4479.6  525.43  4499.6  524.71
  4519.6  524.58  4539.6  523.77  4659.6  522.97  4699.6  521.50  4729.6  521.57
  4769.7  520.23  4919.7  517.49  4995.1  517.32  4995.3  516.82  4998.8  516.82
  4999.1  517.32  5029.9  518.61  5060.6  520.61  5090.3  520.72  5120.5  519.81
  5138.7  520.96  5170.8  522.19  5211.1  523.00  5227.0  525.09  5251.4  525.92
  5281.6  525.82  5310.2  524.87  5412.5  526.10  5481.6  526.02  5536.1  526.78
#Mann=3,-1,0
  4433.4    0.05       0  4995.1    0.04       0  4999.1    0.05       0
Bank Sta=4995.1,4999.1
Exp/Cntr=0.3,0.1

Type RM Length L Ch R = 1,1079,172,172,172
BEGIN DESCRIPTION:
Mapping XS f25eabf2
END DESCRIPTION:
XS GIS Cut Line= 3
      2619514.81      7001326.80      2619573.84      7000861.50
      2619433.27      7000255.83
#Sta/Elev= 30
  4593.2  518.08  4689.8  516.38  4780.5  517.24  4851.1  516.49  4883.6  515.30
  4949.9  510.12  4950.1  509.62  4953.6  509.62  4953.9  510.12  4972.0  511.19
  5060.0  510.58  5119.1  510.92  5161.8  512.90  5247.1  513.12  5268.1  514.65
  5294.8  514.73  5300.0  515.50  5350.2  517.66  5422.0  516.97  5504.2  519.82
  5518.3  519.97  5561.0  518.75  5608.8  519.90  5637.6  518.98  5646.3  519.72
  5651.4  518.96  5658.2  520.27  5668.4  520.58  5678.7  520.56  5684.0  519.86
#Mann=3,-1,0
  4593.2    0.05       0  4949.9    0.05       0  4953.9    0.05       0
Bank Sta=4949.9,4953.9
Exp/Cntr=0.3,0.1

Type RM Length L Ch R = 1,907,336,336,336
BEGIN DESCRIPTION:
Mapping XS 1b9b0cf7
END DESCRIPTION:
XS GIS Cut Line= 3
      2619603.47      7001372.41      2619700.84      7001000.65
      2619706.74      7000370.68
#Sta/Elev= 30
  4630.1  516.21  4672.9  516.95  4739.4  517.12  4820.2  513.77  4855.5  513.73
  4860.7  512.98  4890.0  512.83  4895.9  512.26  4901.1  510.83  4921.0  509.41
  4941.7  510.43  4976.7  509.59  4983.0  507.74  4991.4  507.23  4991.6  506.73
  4995.1  506.73  4995.4  507.23  5011.6  509.55  5024.1  509.95  5074.1  509.49
  5104.1  511.03  5274.1  510.25  5304.1  511.29  5364.1  512.36  5414.1  513.02
  5444.1  512.38  5474.1  513.53  5504.1  513.53  5554.1  515.90  5644.4  516.45
#Mann=3,-1,0
  4630.1    0.05       0  4991.4    0.03       0  4995.4    0.05       0
Bank Sta=4991.4,4995.4
Exp/Cntr=0.3,0.1

Type RM Length L Ch R = 1,571,6,6,6
BEGIN DESCRIPTION:
Mapping XS 63eb6483
END DESCRIPTION:
XS GIS Cut Line= 6
      2619715.35      7001357.19      2619992.71      7000917.06
      2619996.62      7000880.60      2619960.16      7000823.31
      2619939.33      7000737.37      2619872.93      7000456.14
#Sta/Elev= 30
  4373.1  515.27  4379.1  515.41  4385.0  514.20  4400.3  514.68  4406.2  513.06
  4415.6  513.21  4421.5  512.07  4458.0  511.30  4463.9  509.65  4536.9  509.67
  4558.1  508.17  4609.8  509.41  4646.3  507.81  4661.6  508.81  4734.6  509.26
  4865.0  506.84  4871.2  505.73  4877.1  506.66  4886.4  505.73  4891.7  506.62
  4907.5  505.35  4907.7  504.85  4911.5  505.35  4937.8  506.26  4965.2  505.59
  4997.9  506.67  5036.6  505.76  5125.7  506.24  5185.4  509.77  5375.3  512.35
#Mann=3,-1,0
  4373.1    0.05       0  4907.5    0.03       0  4911.5    0.05       0
Bank Sta=4907.5,4911.5
Exp/Cntr=0.3,0.1

Type RM Length L Ch R = 1,565,16,16,16
BEGIN DESCRIPTION:
Mapping XS 2f2035ea
END DESCRIPTION:
XS GIS Cut Line= 6
      2619723.19      7001364.97      2619986.20      7000940.49
      2620009.64      7000909.24      2620003.13      7000870.18
      2619964.07      7000818.10      2619898.96      7000467.83
#Sta/Elev= 30
  4356.0  513.97  4368.7  514.20  4374.6  512.58  4390.0  511.72  4405.3  512.07
  4411.2  510.98  4490.4  509.07  4521.1  509.67  4542.4  507.95  4548.9  509.08
  4594.4  509.41  4600.2  507.93  4631.0  507.81  4652.3  508.44  4658.1  507.82
  4673.5  508.78  4694.8  508.24  4710.1  509.15  4841.3  506.83  4847.2  506.06
  4852.1  506.94  4883.0  506.65  4900.8  505.28  4901.0  504.78  4904.8  505.28
  4912.9  506.64  5013.7  505.73  5097.9  506.24  5182.2  509.63  5355.4  511.98
#Mann=3,-1,0
  4356.0    0.05       0  4900.8    0.03       0  4904.8    0.05       0
Bank Sta=4900.8,4904.8
Exp/Cntr=0.3,0.1

Type RM Length L Ch R = 1,549,468,468,468
BEGIN DESCRIPTION:
Mapping XS 3b3bd05e
END DESCRIPTION:
XS GIS Cut Line= 6
      2619729.69      7001364.98      2620006.78      7000948.46
      2620025.79      7000901.07      2620017.71      7000857.32
      2619975.79      7000806.38      2619917.19      7000467.82
#Sta/Elev= 30
  4337.3  513.97  4343.9  512.46  4358.9  511.70  4452.1  508.93  4497.2  509.33
  4518.2  507.95  4533.2  508.91  4605.4  508.01  4611.4  507.10  4618.3  507.82
  4690.4  507.22  4698.6  508.19  4704.6  507.35  4713.6  507.98  4719.6  506.68
  4734.6  508.23  4749.7  508.12  4847.9  504.01  4848.2  503.51  4851.9  504.01
  4874.2  505.80  4879.5  504.99  4919.6  505.51  4940.3  504.64  4946.2  505.40
  4963.4  504.66  4968.0  505.46  5045.7  505.50  5157.3  508.92  5343.2  511.62
#Mann=3,-1,0
  4337.3    0.05       0  4847.9    0.03       0  4851.9    0.05       0
Bank Sta=4847.9,4851.9
Exp/Cntr=0.3,0.1

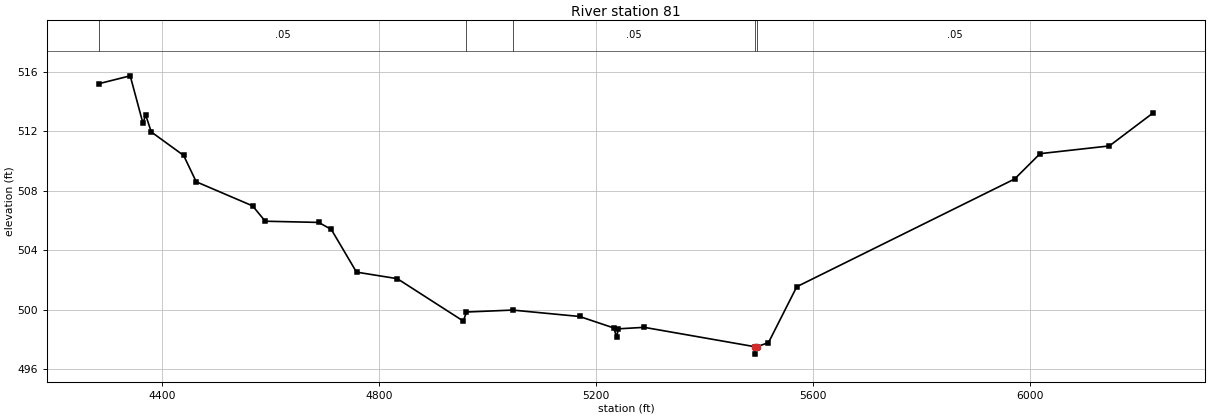
Type RM Length L Ch R = 1,81,0,0,0
BEGIN DESCRIPTION:
Hackberry Creek Tributary 1 1.0
END DESCRIPTION:
XS GIS Cut Line= 4
      2619648.56      7001428.95      2620302.55      7001137.96
      2620393.37      7000913.32      2619999.26      7000012.24
#Sta/Elev= 30
  4284.2  515.20  4341.1  515.72  4364.4  512.56  4369.8  513.07  4379.9  511.95
  4439.6  510.37  4462.8  508.60  4566.7  506.98  4590.0  505.95  4688.4  505.87
  4711.7  505.40  4758.2  502.53  4833.4  502.09  4955.1  499.24  4960.9  499.85
  5045.9  499.98  5169.3  499.55  5232.3  498.78  5237.7  498.18  5240.9  498.72
  5288.5  498.82  5492.1  497.52  5492.3  497.02  5496.1  497.52  5517.5  497.79
  5569.7  501.55  5971.3  508.79  6018.1  510.49  6145.9  511.01  6225.8  513.21
#Mann=5,-1,0
  4284.2    0.05       0  4960.9    0.12       0  5045.9    0.05       0
  5492.1    0.07       0  5496.1    0.05       0
Bank Sta=5492.1,5496.1
Exp/Cntr=0.3,0.1

Chan Stop Cuts=-1