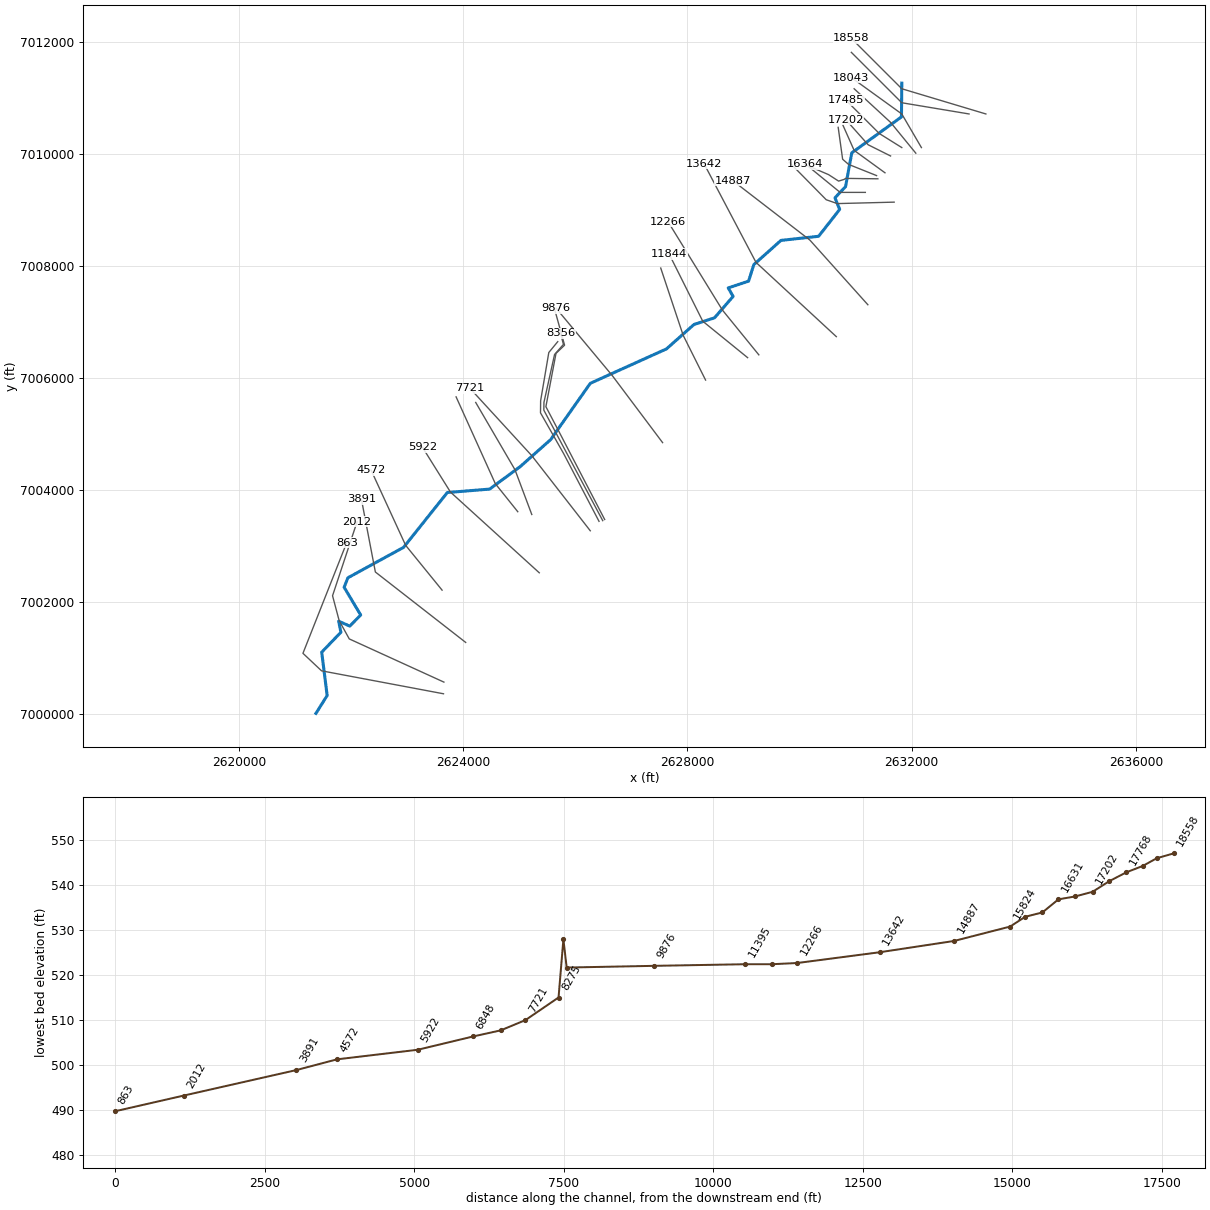
--- Hackberry Creek Tributary 10.prj (project) ---

Proj Title=Hackberry Creek Tributary 10 Base Level Engineering
Current Plan=p01
Default Exp/Contr=0.3,0.1
English Units
Geom File=g01
Flow File=f01
Plan File=p01
BEGIN DESCRIPTION:
Hackberry Creek Tributary 10
END DESCRIPTION:

--- Hackberry Creek Tributary 10.p01 (plan) ---

Plan Title=Multiple Run
Short Identifier=Multiple
Geom File=g01
Flow File=f01
Subcritical Flow
K Sum by GR= 0
Std Step Tol= 0.01
Critical Tol= 0.01
Num of Std Step Trials= 20
Max Error Tol= 0.3
Flow Tol Ratio= 0.001
Split Flow NTrial= 30
Split Flow Tol= 0.02
Split Flow Ratio= 0.02
Log Output Level= 0
Friction Slope Method= 1
Unsteady Friction Slope Method= 2
Unsteady Bridges Friction Slope Method= 1
Parabolic Critical Depth
Global Vel Dist=  1 , 1 , 1
Global Log Level= 0
CheckData=True
Encroach Param= -1, 0, 0, 0
BEGIN DESCRIPTION:
Multiple Run
END DESCRIPTION:

--- Hackberry Creek Tributary 10.f01 (steady flow) ---

Flow Title=Multiple
Number of Profiles=7
Profile Names=10-year,25-year,50-year,1pct_min,100-year,1pct_plu,500-year
River Rch & RM= Hackberry Creek ,Reach-1,18558
     196     243     278     158     316     630     406
River Rch & RM= Hackberry Creek ,Reach-1,16364
     236     298     344     199     396     791     523
River Rch & RM= Hackberry Creek ,Reach-1,14887
     355     456     533     310     619    1235     831
River Rch & RM= Hackberry Creek ,Reach-1,13642
     627     832     994     589    1175    2344    1639
River Rch & RM= Hackberry Creek ,Reach-1,7721
     742     995    1198     714    1425    2843    2017
River Rch & RM= Hackberry Creek ,Reach-1,5922
     922    1249    1515     909    1814    3620    2602
Boundary for River Rch & Prof#=Hackberry Creek ,Reach-1,1
Up Type=0
Dn Type=3
Dn Slope=0.005
Boundary for River Rch & Prof#=Hackberry Creek ,Reach-1,2
Up Type=0
Dn Type=3
Dn Slope=0.005
Boundary for River Rch & Prof#=Hackberry Creek ,Reach-1,3
Up Type=0
Dn Type=3
Dn Slope=0.005
Boundary for River Rch & Prof#=Hackberry Creek ,Reach-1,4
Up Type=0
Dn Type=3
Dn Slope=0.005
Boundary for River Rch & Prof#=Hackberry Creek ,Reach-1,5
Up Type=0
Dn Type=3
Dn Slope=0.005
Boundary for River Rch & Prof#=Hackberry Creek ,Reach-1,6
Up Type=0
Dn Type=3
Dn Slope=0.005
Boundary for River Rch & Prof#=Hackberry Creek ,Reach-1,7
Up Type=0
Dn Type=3
Dn Slope=0.005

--- Hackberry Creek Tributary 10.g01 (geometry) ---

Geom Title=Existing Conditions

River Reach=Hackberry Creek ,Reach-1
Reach XY= 30
      2631826.00      7011261.00      2631820.27      7010658.45
      2630933.86      7010017.17      2630822.46      7009412.46
      2630633.79      7009214.42      2630718.19      7009007.59
      2630342.73      7008527.47      2629670.19      7008453.61
      2629186.61      7008021.06      2629093.14      7007727.04
      2628730.56      7007605.82      2628817.02      7007454.34
      2628485.68      7007071.76      2628119.83      7006953.14
      2627628.30      7006516.83      2626269.94      7005902.86
      2625562.45      7004897.65      2625020.38      7004416.62
      2624474.50      7004014.61      2623719.53      7003953.30
      2622939.21      7002974.63      2621945.78      7002431.09
      2621879.12      7002262.63      2622174.50      7001766.87
      2621979.66      7001568.67      2621781.09      7001656.38
      2621821.01      7001458.45      2621478.94      7001103.03
      2621576.06      7000329.29      2621376.00      7000011.00

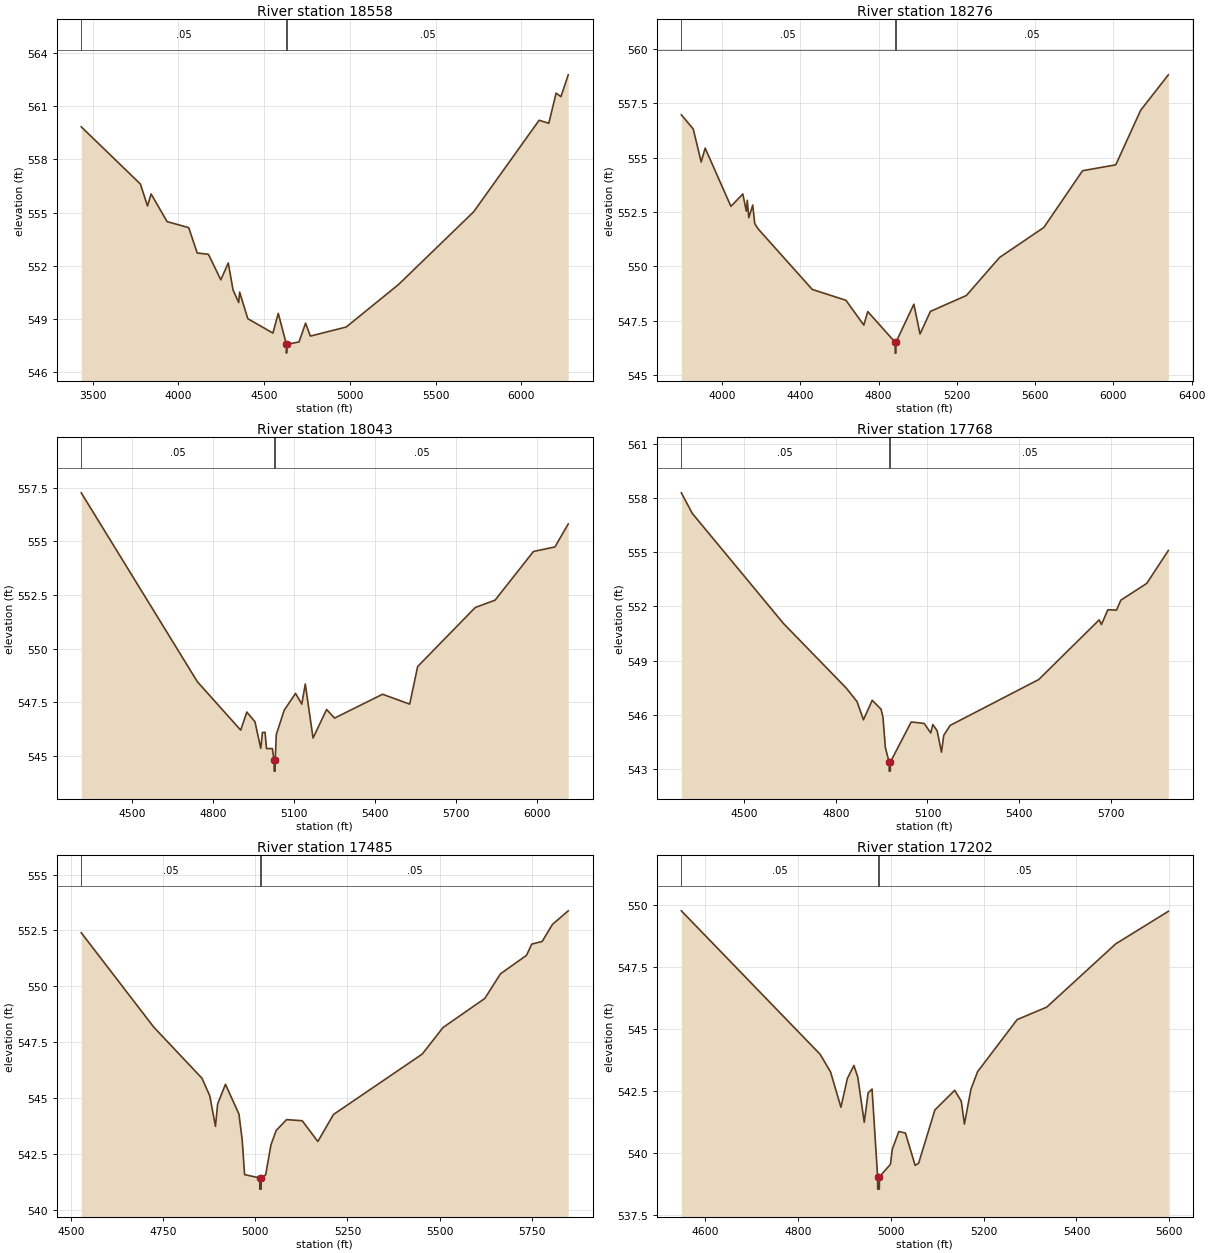
Type RM Length L Ch R = 1,18558,282,282,282
BEGIN DESCRIPTION:
Hackberry Creek Tributary 10 38.0
END DESCRIPTION:
XS GIS Cut Line= 3
      2633326.01      7010711.00      2631826.00      7011161.00
      2630926.03      7012060.97
#Sta/Elev= 30
  3433.8  559.83  3778.3  556.61  3820.1  555.37  3841.0  556.05  3934.1  554.49
  4060.2  554.15  4109.8  552.72  4175.1  552.65  4247.3  551.21  4290.8  552.16
  4318.6  550.64  4351.7  549.93  4356.9  550.52  4404.8  549.02  4550.9  548.21
  4582.2  549.32  4629.8  547.58  4630.1  547.08  4633.8  547.58  4703.2  547.71
  4741.5  548.77  4769.3  548.04  4978.1  548.55  5282.7  550.94  5721.1  555.04
  6102.9  560.20  6159.5  560.03  6201.9  561.73  6230.2  561.53  6272.6  562.76
#Mann=3,-1,0
  3433.8    0.05       0  4629.8   0.035       0  4633.8    0.05       0
Bank Sta=4629.8,4633.8
Exp/Cntr=0.3,0.1

Type RM Length L Ch R = 1,18276,233,233,233
BEGIN DESCRIPTION:
Hackberry Creek Tributary 10 37.0
END DESCRIPTION:
XS GIS Cut Line= 3
      2633025.96      7010711.01      2631826.00      7010911.00
      2630926.00      7011811.00
#Sta/Elev= 30
  3791.4  556.97  3852.2  556.32  3892.7  554.80  3913.0  555.44  4044.8  552.76
  4105.6  553.33  4123.4  552.54  4128.4  553.04  4136.0  552.24  4156.3  552.82
  4166.5  551.97  4184.2  551.72  4460.5  548.94  4632.8  548.44  4724.0  547.30
  4744.3  547.92  4884.3  546.51  4884.5  546.01  4888.0  546.01  4888.3  546.51
  4980.0  548.26  5011.4  546.89  5064.5  547.93  5248.3  548.66  5418.0  550.41
  5644.3  551.79  5842.3  554.40  6012.0  554.67  6139.3  557.18  6280.7  558.81
#Mann=3,-1,0
  3791.4    0.05       0  4884.3   0.035       0  4888.3    0.05       0
Bank Sta=4884.3,4888.3
Exp/Cntr=0.3,0.1

Type RM Length L Ch R = 1,18043,275,275,275
BEGIN DESCRIPTION:
Hackberry Creek Tributary 10 36.0
END DESCRIPTION:
XS GIS Cut Line= 3
      2632176.02      7010110.97      2631826.00      7010711.00
      2630926.03      7011360.98
#Sta/Elev= 30
  4311.4  557.26  4741.9  548.46  4902.3  546.21  4925.0  547.05  4955.2  546.60
  4976.7  545.36  4982.9  546.10  4992.4  546.11  4998.2  545.35  5019.6  545.35
  5026.1  544.80  5026.4  544.30  5029.9  544.30  5030.1  544.80  5034.3  546.01
  5063.7  547.14  5105.5  547.92  5128.7  547.42  5141.7  548.36  5170.4  545.84
  5220.7  547.17  5250.2  546.77  5428.1  547.88  5528.6  547.42  5558.1  549.17
  5771.6  551.92  5844.9  552.26  5987.4  554.53  6066.9  554.74  6116.2  555.81
#Mann=3,-1,0
  4311.4    0.05       0  5026.1    0.03       0  5030.1    0.05       0
Bank Sta=5026.1,5030.1
Exp/Cntr=0.3,0.1

Type RM Length L Ch R = 1,17768,283,283,283
BEGIN DESCRIPTION:
Hackberry Creek Tributary 10 35.0
END DESCRIPTION:
XS GIS Cut Line= 3
      2632076.02      7010010.98      2631626.00      7010561.00
      2630976.04      7011160.97
#Sta/Elev= 30
  4293.9  558.28  4329.8  557.14  4628.4  551.05  4834.4  547.47  4869.6  546.72
  4890.4  545.72  4919.1  546.80  4947.9  546.31  4954.3  545.87  4962.2  544.18
  4974.6  543.38  4974.8  542.88  4978.3  542.88  4978.6  543.38  5046.8  545.60
  5089.3  545.52  5110.9  544.99  5117.7  545.46  5131.9  545.11  5146.0  543.93
  5153.4  544.86  5174.4  545.41  5464.7  547.95  5662.6  551.25  5670.0  550.99
  5691.0  551.81  5719.3  551.79  5733.5  552.34  5818.6  553.27  5889.1  555.09
#Mann=3,-1,0
  4293.9    0.05       0  4974.6    0.03       0  4978.6    0.05       0
Bank Sta=4974.6,4978.6
Exp/Cntr=0.3,0.1

Type RM Length L Ch R = 1,17485,283,283,283
BEGIN DESCRIPTION:
Hackberry Creek Tributary 10 34.0
END DESCRIPTION:
XS GIS Cut Line= 3
      2631826.01      7010110.99      2631426.00      7010361.00
      2630826.03      7010960.97
#Sta/Elev= 30
  4528.3  552.40  4724.7  548.18  4855.6  545.89  4876.8  545.10  4892.1  543.74
  4898.0  544.74  4919.2  545.62  4955.8  544.29  4964.6  543.13  4971.1  541.58
  5012.2  541.43  5012.4  540.93  5015.9  540.93  5016.2  541.43  5028.3  541.57
  5042.4  542.90  5056.6  543.55  5084.9  544.04  5127.3  543.99  5169.7  543.06
  5212.1  544.27  5452.6  546.97  5509.1  548.16  5622.3  549.46  5664.7  550.56
  5735.4  551.39  5749.5  551.89  5777.8  552.01  5806.1  552.78  5848.5  553.38
#Mann=3,-1,0
  4528.3    0.05       0  5012.2    0.03       0  5016.2    0.05       0
Bank Sta=5012.2,5016.2
Exp/Cntr=0.3,0.1

Type RM Length L Ch R = 1,17202,287,287,287
BEGIN DESCRIPTION:
Hackberry Creek Tributary 10 33.0
END DESCRIPTION:
XS GIS Cut Line= 3
      2631626.03      7009960.98      2631226.00      7010161.00
      2630826.02      7010610.98
#Sta/Elev= 30
  4548.6  549.75  4847.7  543.97  4870.1  543.26  4892.4  541.84  4906.4  543.00
  4920.4  543.52  4928.8  543.05  4942.7  541.23  4951.1  542.42  4959.5  542.57
  4971.5  539.04  4971.7  538.54  4975.2  538.54  4975.5  539.04  4999.2  539.54
  5003.0  540.14  5017.2  540.86  5031.4  540.80  5052.3  539.50  5059.8  539.58
  5094.9  541.73  5137.6  542.52  5151.8  542.08  5158.5  541.16  5172.7  542.57
  5186.9  543.27  5272.2  545.37  5335.8  545.87  5484.6  548.42  5597.9  549.73
#Mann=3,-1,0
  4548.6    0.05       0  4971.5    0.03       0  4975.5    0.05       0
Bank Sta=4971.5,4975.5
Exp/Cntr=0.3,0.1

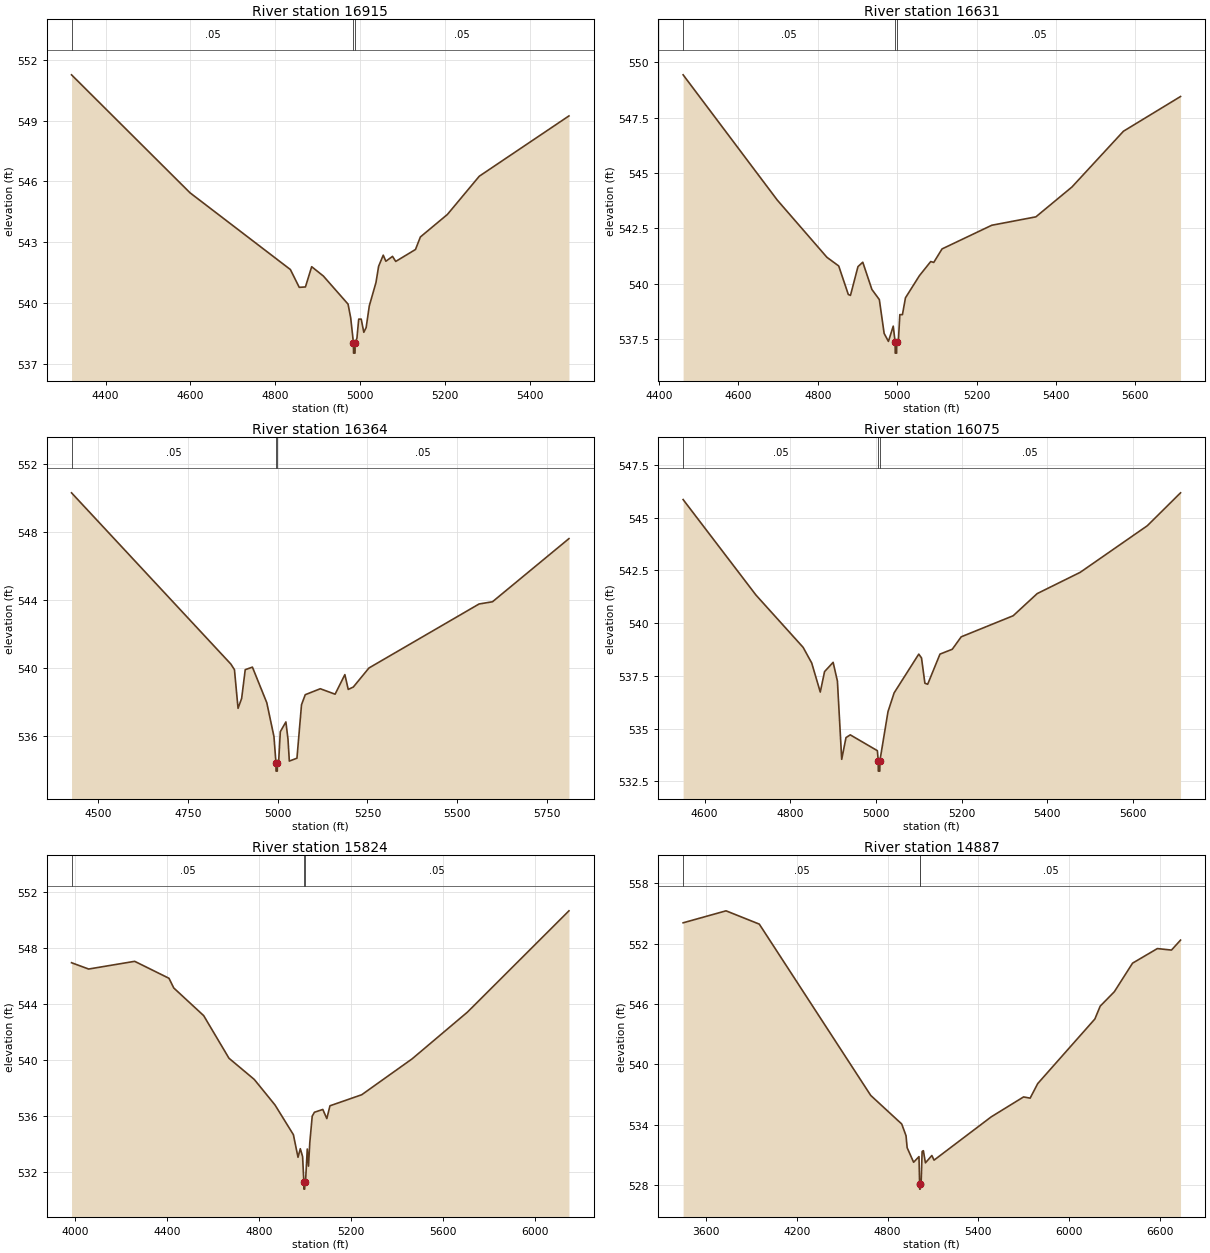
Type RM Length L Ch R = 1,16915,284,284,284
BEGIN DESCRIPTION:
Hackberry Creek Tributary 10 32.0
END DESCRIPTION:
XS GIS Cut Line= 3
      2631526.04      7009660.97      2630976.00      7010061.00
      2630775.98      7010511.04
#Sta/Elev= 30
  4319.6  551.27  4599.0  545.44  4835.5  541.65  4856.4  540.77  4871.0  540.79
  4885.7  541.79  4913.2  541.33  4971.5  539.94  4977.7  539.26  4984.2  538.02
  4984.4  537.52  4987.9  537.52  4988.2  538.02  4992.4  538.26  4996.6  539.20
  5002.5  539.20  5008.6  538.55  5014.1  538.78  5021.6  539.86  5037.3  541.01
  5043.5  541.81  5054.4  542.36  5060.6  542.06  5076.3  542.30  5083.8  542.05
  5130.4  542.64  5142.0  543.26  5205.6  544.37  5280.8  546.26  5492.2  549.24
#Mann=3,-1,0
  4319.6    0.05       0  4984.2    0.03       0  4988.2    0.05       0
Bank Sta=4984.2,4988.2
Exp/Cntr=0.3,0.1

Type RM Length L Ch R = 1,16631,267,267,267
BEGIN DESCRIPTION:
Hackberry Creek Tributary 10 31.0
END DESCRIPTION:
XS GIS Cut Line= 4
      2631376.04      7009610.98      2630876.00      7009811.00
      2630770.79      7009903.06      2630691.67      7010471.82
#Sta/Elev= 30
  4461.0  549.44  4698.0  543.78  4823.2  541.19  4852.8  540.80  4877.0  539.51
  4882.4  539.47  4901.3  540.77  4913.4  540.97  4936.3  539.74  4955.1  539.28
  4967.2  537.75  4978.0  537.39  4990.1  538.08  4994.9  537.36  4995.1  536.86
  4998.6  536.86  4998.9  537.36  5002.9  537.36  5006.7  538.60  5013.3  538.60
  5020.9  539.36  5056.0  540.36  5084.5  541.00  5092.1  540.96  5113.0  541.57
  5238.2  542.64  5349.3  543.02  5440.2  544.37  5569.8  546.89  5713.6  548.46
#Mann=3,-1,0
  4461.0    0.05       0  4994.9    0.03       0  4998.9    0.05       0
Bank Sta=4994.9,4998.9
Exp/Cntr=0.3,0.1

Type RM Length L Ch R = 1,16364,289,289,289
BEGIN DESCRIPTION:
Hackberry Creek Tributary 10 30.0
END DESCRIPTION:
XS GIS Cut Line= 6
      2631399.56      7009553.61      2630826.00      7009561.00
      2630795.15      7009542.07      2630698.70      7009512.55
      2630519.79      7009628.12      2630096.15      7009810.43
#Sta/Elev= 30
  4426.3  550.31  4869.9  540.25  4879.9  539.92  4889.9  537.65  4899.9  538.23
  4909.9  539.92  4929.9  540.07  4969.9  537.98  4989.9  535.99  4995.4  534.46
  4995.7  533.96  4999.2  533.96  4999.4  534.46  5002.8  534.46  5007.6  536.28
  5023.1  536.85  5028.9  535.85  5032.7  534.55  5053.9  534.72  5066.6  537.86
  5077.0  538.45  5118.9  538.80  5160.1  538.48  5187.3  539.63  5196.7  538.76
  5210.8  538.90  5254.4  540.02  5561.0  543.78  5598.3  543.91  5811.2  547.62
#Mann=3,-1,0
  4426.3    0.05       0  4995.4    0.03       0  4999.4    0.05       0
Bank Sta=4995.4,4999.4
Exp/Cntr=0.3,0.1

Type RM Length L Ch R = 1,16075,251,251,251
BEGIN DESCRIPTION:
Hackberry Creek Tributary 10 29.0
END DESCRIPTION:
XS GIS Cut Line= 3
      2631175.99      7009311.00      2630726.00      7009311.00
      2630176.02      7009760.99
#Sta/Elev= 30
  4550.0  545.86  4720.0  541.33  4830.0  538.85  4850.0  538.11  4870.0  536.73
  4880.0  537.70  4900.0  538.14  4910.0  537.25  4920.0  533.54  4930.0  534.57
  4940.0  534.70  5003.2  533.95  5005.2  533.48  5005.4  532.98  5008.9  532.98
  5009.2  533.48  5028.0  535.80  5042.3  536.69  5099.8  538.53  5106.2  538.35
  5114.1  537.15  5120.6  537.10  5149.3  538.53  5178.0  538.76  5198.8  539.35
  5320.1  540.35  5376.1  541.40  5476.6  542.41  5633.1  544.62  5710.6  546.18
#Mann=3,-1,0
  4550.0    0.05       0  5005.2   0.035       0  5009.2    0.05       0
Bank Sta=5005.2,5009.2
Exp/Cntr=0.3,0.1

Type RM Length L Ch R = 1,15824,937,937,937
BEGIN DESCRIPTION:
Hackberry Creek Tributary 10 28.0
END DESCRIPTION:
XS GIS Cut Line= 4
      2631690.36      7009136.94      2630676.00      7009111.00
      2630478.21      7009179.71      2629819.72      7009848.73
#Sta/Elev= 30
  3985.3  546.95  4059.7  546.50  4259.8  547.05  4409.1  545.84  4429.8  545.15
  4559.8  543.18  4669.9  540.14  4779.9  538.63  4870.0  536.81  4950.0  534.69
  4970.0  533.08  4980.0  533.69  4990.0  533.13  4995.5  531.31  4995.7  530.81
  4999.2  530.81  4999.5  531.31  5002.6  531.31  5010.3  533.67  5015.6  532.45
  5021.2  534.11  5031.8  536.01  5041.4  536.29  5077.8  536.49  5095.3  535.84
  5108.9  536.75  5247.2  537.54  5466.4  540.10  5706.8  543.43  6148.1  550.65
#Mann=3,-1,0
  3985.3    0.05       0  4995.5   0.035       0  4999.5    0.05       0
Bank Sta=4995.5,4999.5
Exp/Cntr=0.3,0.1

Type RM Length L Ch R = 1,14887,1245,1245,1245
BEGIN DESCRIPTION:
Hackberry Creek Tributary 10 26.0
END DESCRIPTION:
XS GIS Cut Line= 3
      2631220.72      7007305.38      2630185.63      7008460.46
      2628811.06      7009520.60
#Sta/Elev= 30
  3449.0  554.07  3732.5  555.26  3952.3  553.94  4688.7  536.92  4893.5  534.08
  4922.0  532.91  4929.4  531.72  4972.1  530.28  5007.5  530.84  5011.8  528.11
  5012.0  527.61  5015.5  527.61  5015.8  528.11  5022.0  528.37  5028.3  531.35
  5036.5  531.43  5050.1  530.22  5092.6  530.95  5107.1  530.49  5484.8  534.79
  5698.6  536.77  5742.1  536.65  5791.9  538.09  6169.7  544.51  6205.0  545.79
  6298.3  547.22  6418.8  550.06  6582.7  551.51  6676.0  551.36  6735.9  552.35
#Mann=3,-1,0
  3449.0    0.05       0  5011.8    0.03       0  5015.8    0.05       0
Bank Sta=5011.8,5015.8
Exp/Cntr=0.3,0.1

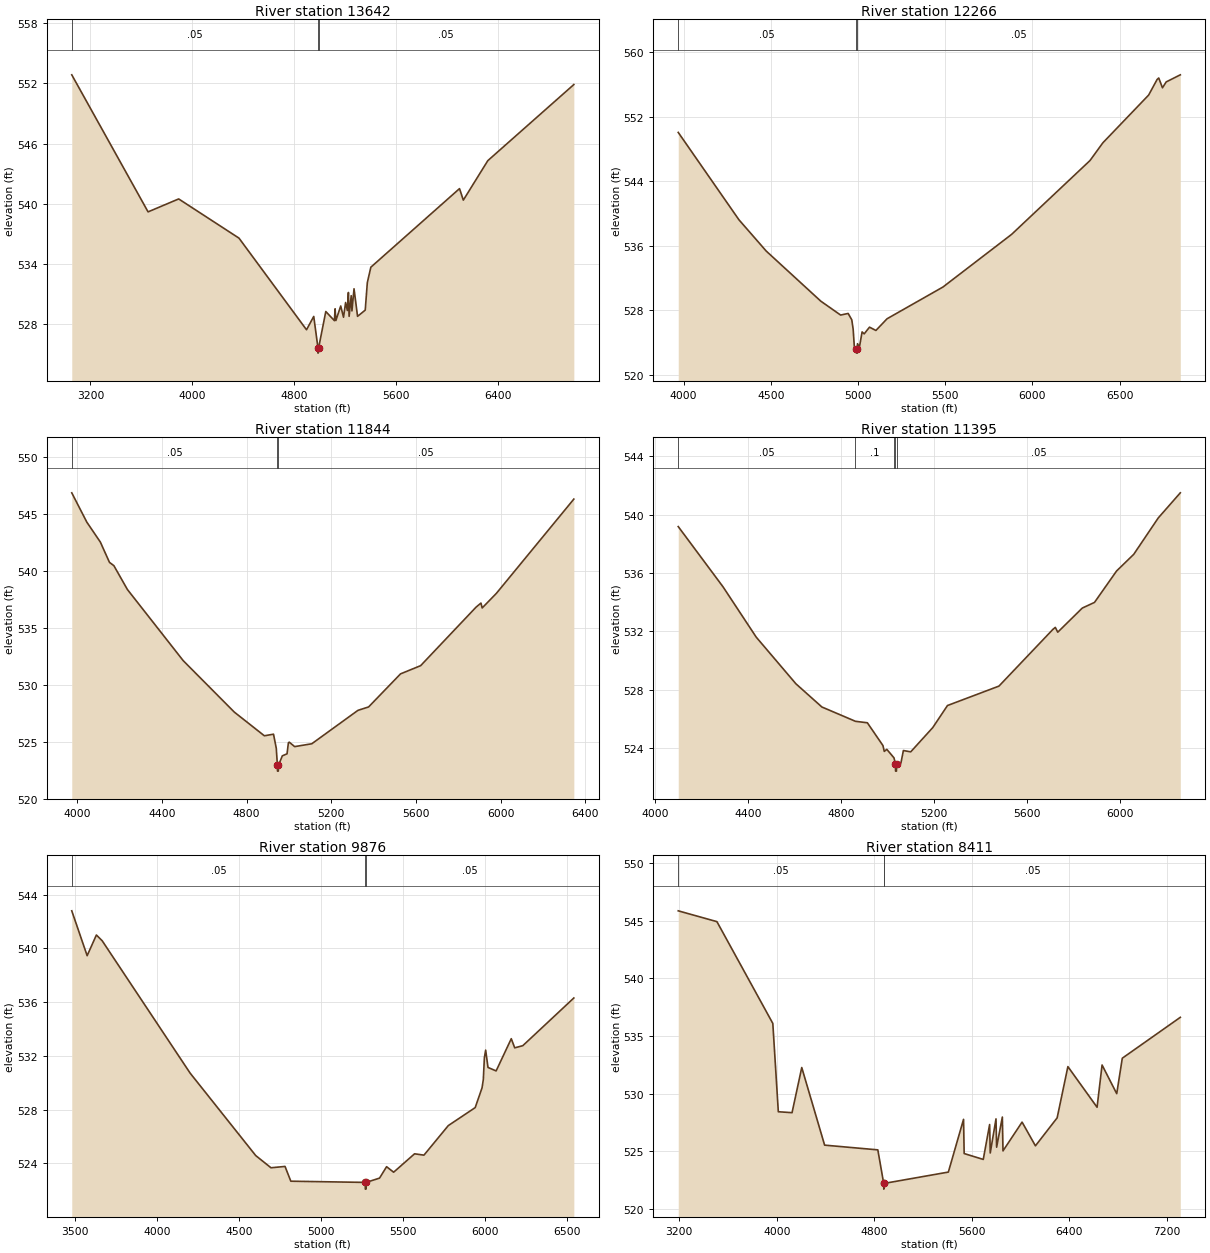
Type RM Length L Ch R = 1,13642,1376,1376,1376
BEGIN DESCRIPTION:
Hackberry Creek Tributary 10 23.0
END DESCRIPTION:
XS GIS Cut Line= 3
      2630658.23      7006735.92      2629226.00      7008061.00
      2628297.20      7009826.06
#Sta/Elev= 30
  3053.1  552.86  3652.8  539.19  3893.3  540.48  4367.3  536.57  4898.0  527.43
  4954.7  528.76  4988.2  525.60  4988.6  525.10  4992.6  525.60  5049.5  529.25
  5117.0  528.34  5122.7  529.52  5128.6  528.35  5166.7  529.80  5188.8  528.68
  5205.2  530.15  5219.0  529.35  5227.2  531.15  5232.8  528.77  5249.2  530.83
  5254.9  529.31  5271.3  531.52  5299.0  528.77  5359.4  529.39  5375.8  532.13
  5403.5  533.67  6100.4  541.51  6130.2  540.36  6322.8  544.30  6998.8  551.89
#Mann=3,-1,0
  3053.1    0.05       0  4988.2    0.03       0  4992.6    0.05       0
Bank Sta=4988.2,4992.6
Exp/Cntr=0.3,0.1

Type RM Length L Ch R = 1,12266,422,422,422
BEGIN DESCRIPTION:
Hackberry Creek Tributary 10 20.0
END DESCRIPTION:
XS GIS Cut Line= 3
      2629275.97      7006411.03      2628626.00      7007211.00
      2627658.26      7008784.49
#Sta/Elev= 30
  3969.3  550.08  4317.1  539.25  4473.5  535.37  4786.7  529.15  4900.2  527.43
  4943.3  527.63  4964.1  526.84  4972.0  525.68  4978.5  523.55  4990.4  523.21
  4991.0  522.71  4994.7  522.71  4995.2  523.21  4996.8  523.88  5007.7  523.43
  5023.2  525.34  5035.3  525.10  5065.7  525.93  5102.4  525.52  5166.3  526.97
  5487.0  530.91  5880.5  537.44  6329.6  546.59  6403.0  548.78  6665.8  554.71
  6714.2  556.64  6723.7  556.83  6745.0  555.61  6766.3  556.34  6847.3  557.22
#Mann=3,-1,0
  3969.3    0.05       0  4990.4   0.035       0  4995.2    0.05       0
Bank Sta=4990.4,4995.2
Exp/Cntr=0.3,0.1

Type RM Length L Ch R = 1,11844,449,449,449
BEGIN DESCRIPTION:
Hackberry Creek Tributary 10 19.0
END DESCRIPTION:
XS GIS Cut Line= 3
      2629076.03      7006360.98      2628276.00      7007011.00
      2627676.02      7008210.96
#Sta/Elev= 30
  3974.1  546.85  4045.2  544.28  4109.2  542.53  4152.3  540.75  4173.1  540.46
  4237.0  538.37  4500.7  532.13  4742.0  527.62  4884.2  525.54  4927.4  525.68
  4940.5  524.44  4945.8  522.94  4946.3  522.44  4950.0  522.44  4950.6  522.94
  4969.0  523.78  4991.3  523.96  4997.7  524.92  5001.7  524.98  5027.3  524.59
  5108.3  524.84  5326.3  527.77  5376.7  528.07  5527.6  530.97  5622.6  531.69
  5885.4  536.84  5907.7  537.18  5913.3  536.75  5980.4  538.03  6346.5  546.30
#Mann=3,-1,0
  3974.1    0.05       0  4945.8   0.035       0  4950.6    0.05       0
Bank Sta=4945.8,4950.6
Exp/Cntr=0.3,0.1

Type RM Length L Ch R = 1,11395,1519,1519,1519
BEGIN DESCRIPTION:
Hackberry Creek Tributary 10 18.0
END DESCRIPTION:
XS GIS Cut Line= 3
      2628326.02      7005960.96      2627926.00      7006761.00
      2627525.99      7007961.02
#Sta/Elev= 30
  4101.2  539.18  4294.1  535.05  4436.7  531.61  4607.2  528.42  4719.0  526.83
  4863.5  525.85  4914.6  525.75  4981.7  524.19  4987.3  523.79  4998.3  523.93
  5029.1  523.35  5035.3  522.94  5036.0  522.44  5039.7  522.44  5040.3  522.94
  5058.9  522.99  5069.5  523.85  5101.1  523.76  5195.9  525.42  5259.2  526.93
  5480.6  528.26  5712.5  532.14  5723.0  532.28  5733.5  531.95  5838.9  533.60
  5891.6  533.99  5986.5  536.14  6060.3  537.28  6165.7  539.77  6260.6  541.49
#Mann=5,-1,0
  4101.2    0.05       0  4863.5     0.1       0  5029.1    0.05       0
  5035.3    0.07       0  5040.3    0.05       0
Bank Sta=5035.3,5040.3
Exp/Cntr=0.3,0.1

Type RM Length L Ch R = 1,9876,1465,1465,1465
BEGIN DESCRIPTION:
Hackberry Creek Tributary 10 14.0
END DESCRIPTION:
XS GIS Cut Line= 3
      2627559.51      7004843.91      2626659.51      7006043.90
      2625660.24      7007243.03
#Sta/Elev= 30
  3478.4  542.80  3572.2  539.46  3628.5  541.00  3663.9  540.57  4199.8  530.72
  4599.8  524.58  4693.0  523.67  4778.5  523.77  4813.9  522.67  5267.4  522.58
  5268.2  522.08  5272.1  522.08  5272.9  522.58  5354.8  522.90  5397.7  523.75
  5440.7  523.34  5568.3  524.71  5625.5  524.61  5773.9  526.81  5937.9  528.15
  5979.6  529.62  5987.4  530.23  5993.9  531.86  6001.7  532.43  6016.0  531.14
  6065.5  530.88  6157.9  533.28  6178.8  532.60  6228.2  532.76  6539.3  536.31
#Mann=3,-1,0
  3478.4    0.05       0  5267.4    0.03       0  5272.9    0.05       0
Bank Sta=5267.4,5272.9
Exp/Cntr=0.3,0.1

Type RM Length L Ch R = 1,8411,55,55,55
BEGIN DESCRIPTION:
Mapping XS 56d70831
END DESCRIPTION:
XS GIS Cut Line= 6
      2626526.29      7003472.04      2625699.91      7005062.29
      2625477.69      7005485.90      2625658.25      7006437.29
      2625811.03      7006583.12      2625632.06      7007229.94
#Sta/Elev= 30
  3191.0  545.87  3508.5  544.93  3967.4  536.09  4012.5  528.42  4125.2  528.34
  4204.9  532.26  4392.6  525.52  4829.3  525.11  4877.4  522.20  4878.3  521.70
  4883.2  522.20  5408.2  523.18  5532.9  527.76  5538.0  524.79  5694.7  524.28
  5747.0  527.31  5752.1  524.84  5799.3  527.80  5804.4  525.34  5851.5  527.96
  5856.6  525.02  6013.4  527.52  6123.0  525.46  6301.3  527.89  6389.4  532.34
  6629.0  528.81  6670.0  532.48  6790.3  529.99  6836.0  533.07  7312.2  536.62
#Mann=3,-1,0
  3191.0    0.05       0  4877.4   0.035       0  4883.2    0.05       0
Bank Sta=4877.4,4883.2
Exp/Cntr=0.3,0.1

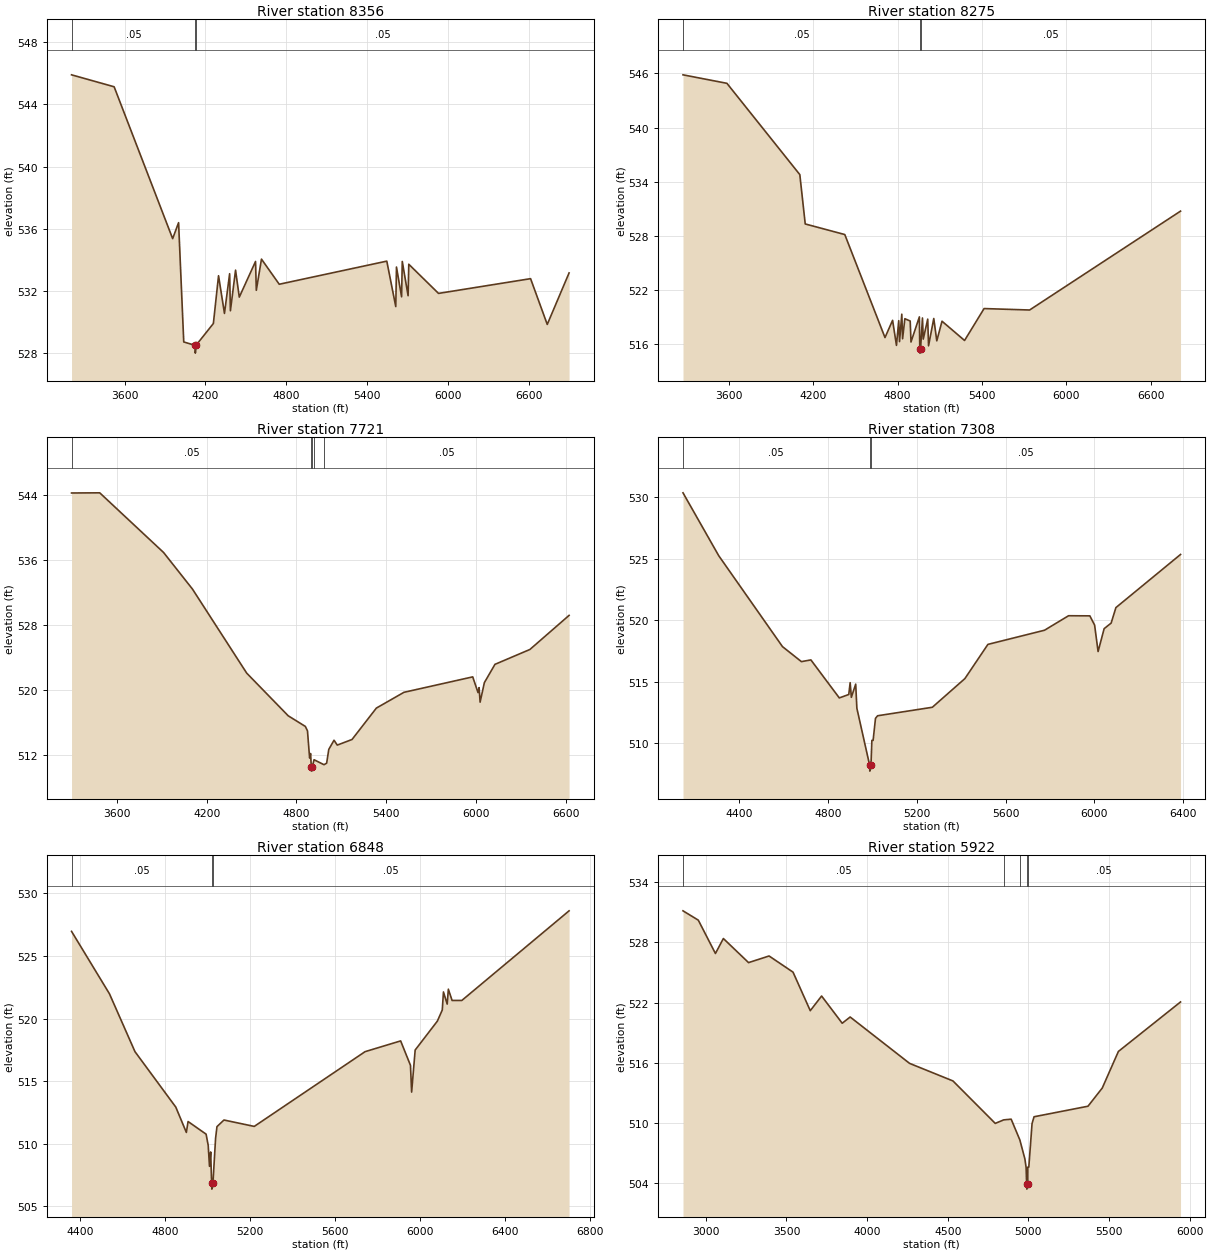
Type RM Length L Ch R = 1,8356,81,81,81
BEGIN DESCRIPTION:
Mapping XS 69b31086
END DESCRIPTION:
XS GIS Cut Line= 6
      2626491.58      7003451.18      2625440.96      7005423.62
      2625442.97      7005562.29      2625632.54      7006417.98
      2625790.96      7006597.23      2625737.68      7006797.64
#Sta/Elev= 30
  3204.8  545.91  3521.2  545.14  3956.1  535.35  4000.1  536.38  4038.5  528.69
  4123.6  528.47  4124.5  527.97  4129.4  528.47  4258.6  529.88  4297.0  532.96
  4341.0  530.53  4379.4  533.09  4385.1  530.70  4423.4  533.32  4451.1  531.58
  4571.9  533.88  4577.6  532.02  4615.9  534.03  4748.0  532.41  5547.1  533.90
  5613.8  530.97  5619.0  533.52  5657.0  531.60  5662.1  533.88  5705.3  531.67
  5710.4  533.70  5931.4  531.82  6615.4  532.77  6739.3  529.82  6901.4  533.14
#Mann=3,-1,0
  3204.8    0.05       0  4123.6   0.035       0  4129.4    0.05       0
Bank Sta=4123.6,4129.4
Exp/Cntr=0.3,0.1

Type RM Length L Ch R = 1,8275,554,554,554
BEGIN DESCRIPTION:
Mapping XS 12b7a72a
END DESCRIPTION:
XS GIS Cut Line= 6
      2626425.62      7003438.79      2625793.87      7004648.92
      2625381.54      7005375.92      2625383.94      7005591.59
      2625529.78      7006452.70      2625689.01      7006646.55
#Sta/Elev= 30
  3272.6  545.83  3585.2  544.89  4104.0  534.79  4142.5  529.33  4424.0  528.16
  4710.2  516.76  4764.2  518.67  4791.8  515.90  4807.9  518.63  4813.6  516.31
  4829.7  519.35  4835.4  516.63  4851.5  518.85  4889.5  518.59  4895.2  516.27
  4954.9  519.05  4957.7  515.54  4958.6  515.04  4963.5  515.54  4976.7  518.93
  4982.4  516.59  5014.3  518.80  5020.1  515.85  5057.3  518.87  5078.8  516.40
  5116.0  518.57  5276.5  516.44  5415.4  519.97  5739.4  519.81  6813.5  530.75
#Mann=3,-1,0
  3272.6    0.05       0  4957.7   0.035       0  4963.5    0.05       0
Bank Sta=4957.7,4963.5
Exp/Cntr=0.3,0.1

Type RM Length L Ch R = 1,7721,413,413,413
BEGIN DESCRIPTION:
Hackberry Creek Tributary 10 10.0
END DESCRIPTION:
XS GIS Cut Line= 3
      2626269.37      7003270.62      2625226.00      7004611.00
      2624125.99      7005811.01
#Sta/Elev= 30
  3296.7  544.21  3485.2  544.23  3912.2  536.89  4105.0  532.40  4467.8  522.06
  4745.6  516.81  4859.6  515.51  4874.1  514.97  4888.5  511.61  4894.9  512.17
  4899.9  510.51  4901.0  510.01  4906.1  510.51  4918.2  511.41  4984.7  510.80
  5002.4  510.99  5016.6  512.68  5051.7  513.81  5073.3  513.21  5172.0  513.90
  5334.7  517.76  5519.1  519.70  5979.1  521.60  6014.3  519.67  6021.7  520.28
  6028.4  518.49  6056.8  520.89  6127.7  523.14  6361.4  524.97  6623.2  529.16
#Mann=5,-1,0
  3296.7    0.05       0  4899.9   0.035       0  4906.1    0.05       0
  4918.2    0.12       0  4984.7    0.05       0
Bank Sta=4899.9,4906.1
Exp/Cntr=0.3,0.1

Type RM Length L Ch R = 1,7308,460,460,460
BEGIN DESCRIPTION:
Hackberry Creek Tributary 10 9.0
END DESCRIPTION:
XS GIS Cut Line= 3
      2625226.00      7003560.99      2624926.00      7004361.00
      2624225.97      7005561.04
#Sta/Elev= 30
  4145.4  530.35  4306.5  525.24  4594.0  517.85  4679.4  516.63  4722.1  516.77
  4850.3  513.68  4893.0  513.96  4899.2  514.92  4904.6  513.73  4924.2  514.80
  4929.5  512.84  4986.9  508.23  4987.9  507.73  4993.2  508.23  4997.1  510.23
  5002.7  510.23  5013.5  512.02  5023.0  512.23  5269.8  512.92  5416.6  515.25
  5520.4  518.03  5775.5  519.18  5884.2  520.36  5980.1  520.35  6001.6  519.60
  6017.3  517.45  6044.6  519.31  6076.1  519.76  6097.6  521.02  6389.1  525.34
#Mann=3,-1,0
  4145.4    0.05       0  4986.9   0.035       0  4993.2    0.05       0
Bank Sta=4986.9,4993.2
Exp/Cntr=0.3,0.1

Type RM Length L Ch R = 1,6848,926,926,926
BEGIN DESCRIPTION:
Hackberry Creek Tributary 10 8.0
END DESCRIPTION:
XS GIS Cut Line= 3
      2624975.99      7003611.01      2624576.00      7004111.00
      2623876.01      7005660.97
#Sta/Elev= 30
  4359.7  526.97  4538.2  521.98  4658.2  517.36  4850.3  512.93  4899.9  510.91
  4908.0  511.78  4992.8  510.77  5002.7  509.88  5008.8  508.20  5014.3  509.35
  5018.8  506.88  5019.8  506.38  5025.1  506.88  5037.4  510.43  5043.9  511.37
  5076.8  511.90  5219.4  511.39  5740.8  517.36  5908.2  518.22  5954.4  516.27
  5959.9  514.13  5976.5  517.49  6081.0  519.80  6104.1  520.69  6109.6  522.13
  6127.2  521.16  6132.7  522.35  6150.3  521.45  6196.0  521.45  6700.7  528.61
#Mann=3,-1,0
  4359.7    0.05       0  5018.8   0.035       0  5025.1    0.05       0
Bank Sta=5018.8,5025.1
Exp/Cntr=0.3,0.1

Type RM Length L Ch R = 1,5922,1350,1350,1350
BEGIN DESCRIPTION:
Hackberry Creek Tributary 10 6.0
END DESCRIPTION:
XS GIS Cut Line= 3
      2625359.61      7002520.65      2623776.00      7003961.00
      2623275.98      7004761.04
#Sta/Elev= 30
  2858.9  531.15  2953.8  530.22  3059.9  526.90  3109.2  528.39  3265.3  525.99
  3392.4  526.65  3541.0  525.04  3647.8  521.20  3718.1  522.66  3845.8  519.95
  3895.1  520.57  4263.4  515.95  4532.3  514.20  4794.5  509.97  4847.0  510.32
  4893.1  510.39  4947.0  508.32  4978.3  506.42  4985.7  505.59  4989.1  503.92
  4990.2  503.42  4995.8  503.92  4996.2  505.61  5002.5  505.61  5022.6  509.95
  5034.9  510.63  5369.3  511.68  5457.7  513.49  5557.9  517.14  5943.0  522.07
#Mann=5,-1,0
  2858.9    0.05       0  4847.0    0.12       0  4947.0    0.05       0
  4989.1   0.035       0  4995.8    0.05       0
Bank Sta=4989.1,4995.8
Exp/Cntr=0.3,0.1

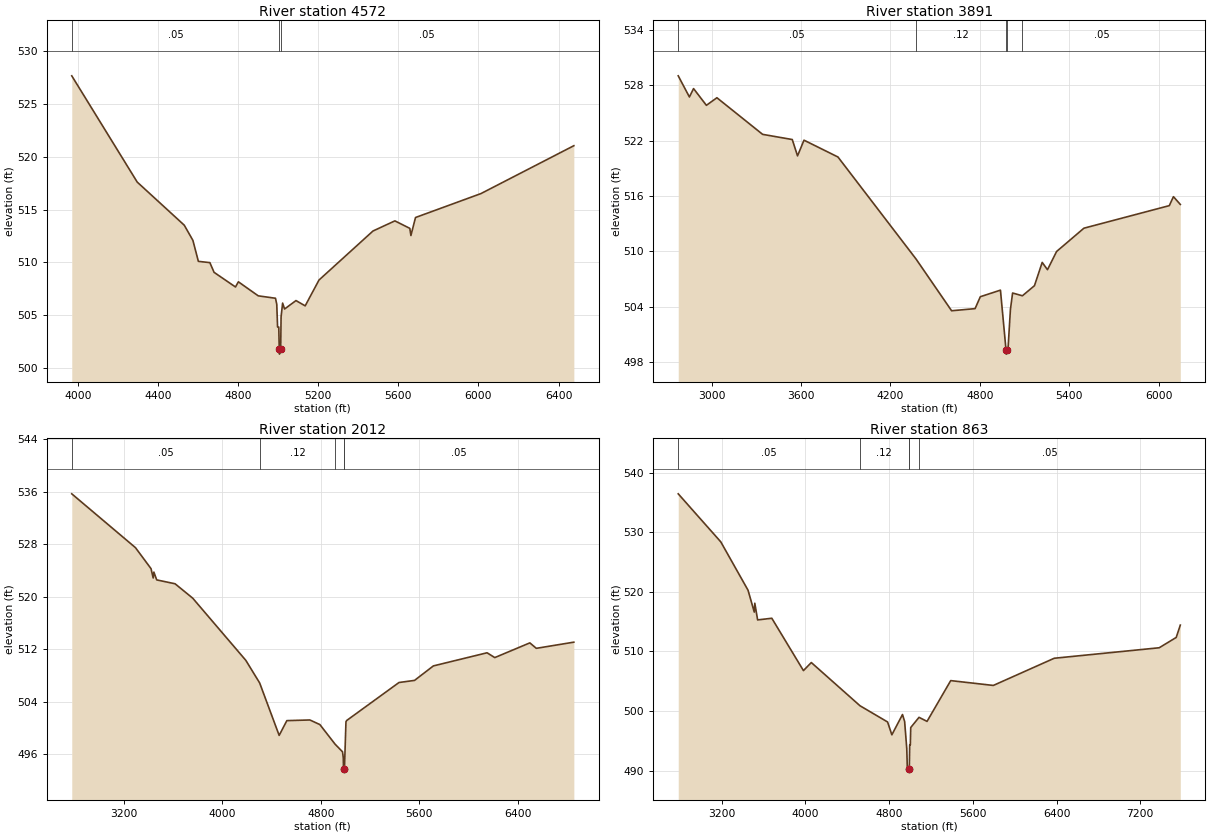
Type RM Length L Ch R = 1,4572,681,681,681
BEGIN DESCRIPTION:
Hackberry Creek Tributary 10 3.0
END DESCRIPTION:
XS GIS Cut Line= 3
      2623625.97      7002211.03      2622976.00      7003011.00
      2622360.34      7004352.43
#Sta/Elev= 30
  3969.5  527.69  4296.3  517.61  4531.2  513.52  4574.3  512.08  4601.6  510.09
  4659.0  509.97  4679.9  509.05  4786.9  507.66  4801.3  508.15  4900.4  506.82
  4986.6  506.59  4993.0  506.02  4997.0  503.86  5003.0  503.86  5005.4  501.79
  5006.5  501.29  5012.6  501.79  5014.5  504.82  5022.2  506.13  5032.0  505.57
  5088.9  506.37  5134.9  505.87  5203.9  508.32  5473.4  512.97  5582.7  513.93
  5657.2  513.22  5662.7  512.54  5685.7  514.25  6012.5  516.52  6476.2  521.06
#Mann=3,-1,0
  3969.5    0.05       0  5005.4    0.03       0  5012.6    0.05       0
Bank Sta=5005.4,5012.6
Exp/Cntr=0.3,0.1

Type RM Length L Ch R = 1,3891,1879,1879,1879
BEGIN DESCRIPTION:
Hackberry Creek Tributary 10 2.0
END DESCRIPTION:
XS GIS Cut Line= 3
      2624047.13      7001277.58      2622436.03      7002534.51
      2622186.71      7003836.24
#Sta/Elev= 30
  2776.7  529.00  2851.7  526.71  2879.6  527.62  2965.6  525.81  3036.2  526.63
  3342.8  522.67  3541.8  522.11  3577.2  520.34  3620.5  522.04  3848.5  520.22
  4372.2  509.19  4611.0  503.59  4768.4  503.82  4803.7  505.11  4938.7  505.82
  4975.8  499.40  4976.9  498.90  4983.0  499.40  4989.6  499.49  5005.6  503.73
  5020.2  505.51  5086.0  505.21  5166.8  506.30  5218.8  508.82  5254.3  508.03
  5315.4  510.00  5498.7  512.52  6071.7  514.96  6099.4  515.93  6145.5  515.09
#Mann=5,-1,0
  2776.7    0.05       0  4372.2    0.12       0  4975.8    0.07       0
  4983.0    0.12       0  5086.0    0.05       0
Bank Sta=4975.8,4983
Exp/Cntr=0.3,0.1

Type RM Length L Ch R = 1,2012,1149,1149,1149
BEGIN DESCRIPTION:
Mapping XS ab747260
END DESCRIPTION:
XS GIS Cut Line= 5
      2623658.28      7000569.22      2621970.75      7001340.07
      2621790.19      7001666.46      2621672.14      7002110.90
      2622109.64      7003430.34
#Sta/Elev= 30
  2777.9  535.66  3295.6  527.45  3421.8  524.25  3439.3  522.83  3444.8  523.73
  3467.8  522.54  3617.0  521.95  3760.6  519.75  4191.6  510.28  4304.2  506.83
  4462.5  498.84  4525.0  501.09  4711.9  501.19  4793.2  500.49  4917.3  497.49
  4977.1  496.34  4983.3  495.45  4985.2  493.74  4986.4  493.24  4992.8  493.74
  5005.1  500.92  5011.1  501.11  5435.9  506.90  5562.0  507.22  5715.1  509.43
  6150.9  511.43  6214.1  510.70  6498.6  512.94  6551.3  512.11  6856.1  513.05
#Mann=5,-1,0
  2777.9    0.05       0  4304.2    0.12       0  4917.3    0.05       0
  4985.2    0.03       0  4992.8    0.05       0
Bank Sta=4985.2,4992.8
Exp/Cntr=0.3,0.1

Type RM Length L Ch R = 1,863,0,0,0
BEGIN DESCRIPTION:
Hackberry Creek Tributary 10 1.0
END DESCRIPTION:
XS GIS Cut Line= 4
      2623651.33      7000360.90      2621475.98      7000770.63
      2621144.36      7001083.12      2621926.01      7003061.01
#Sta/Elev= 30
  2786.4  536.43  3193.0  528.37  3453.3  520.26  3512.8  516.59  3517.8  518.08
  3544.8  515.28  3680.3  515.56  3982.4  506.78  4057.6  508.13  4522.9  500.88
  4786.3  498.16  4827.0  496.01  4928.7  499.41  4949.1  498.24  4969.5  493.66
  4974.8  490.38  4986.0  490.25  4987.2  489.75  4993.6  490.25  4997.4  494.33
  5003.4  494.33  5007.3  497.23  5086.5  498.94  5163.1  498.26  5389.3  505.10
  5796.2  504.29  6378.1  508.85  7380.9  510.61  7543.2  512.34  7582.4  514.41
#Mann=5,-1,0
  2786.4    0.05       0  4522.9    0.12       0  4986.0    0.07       0
  4993.6    0.12       0  5086.5    0.05       0
Bank Sta=4986,4993.6
Exp/Cntr=0.3,0.1

Chan Stop Cuts=-1