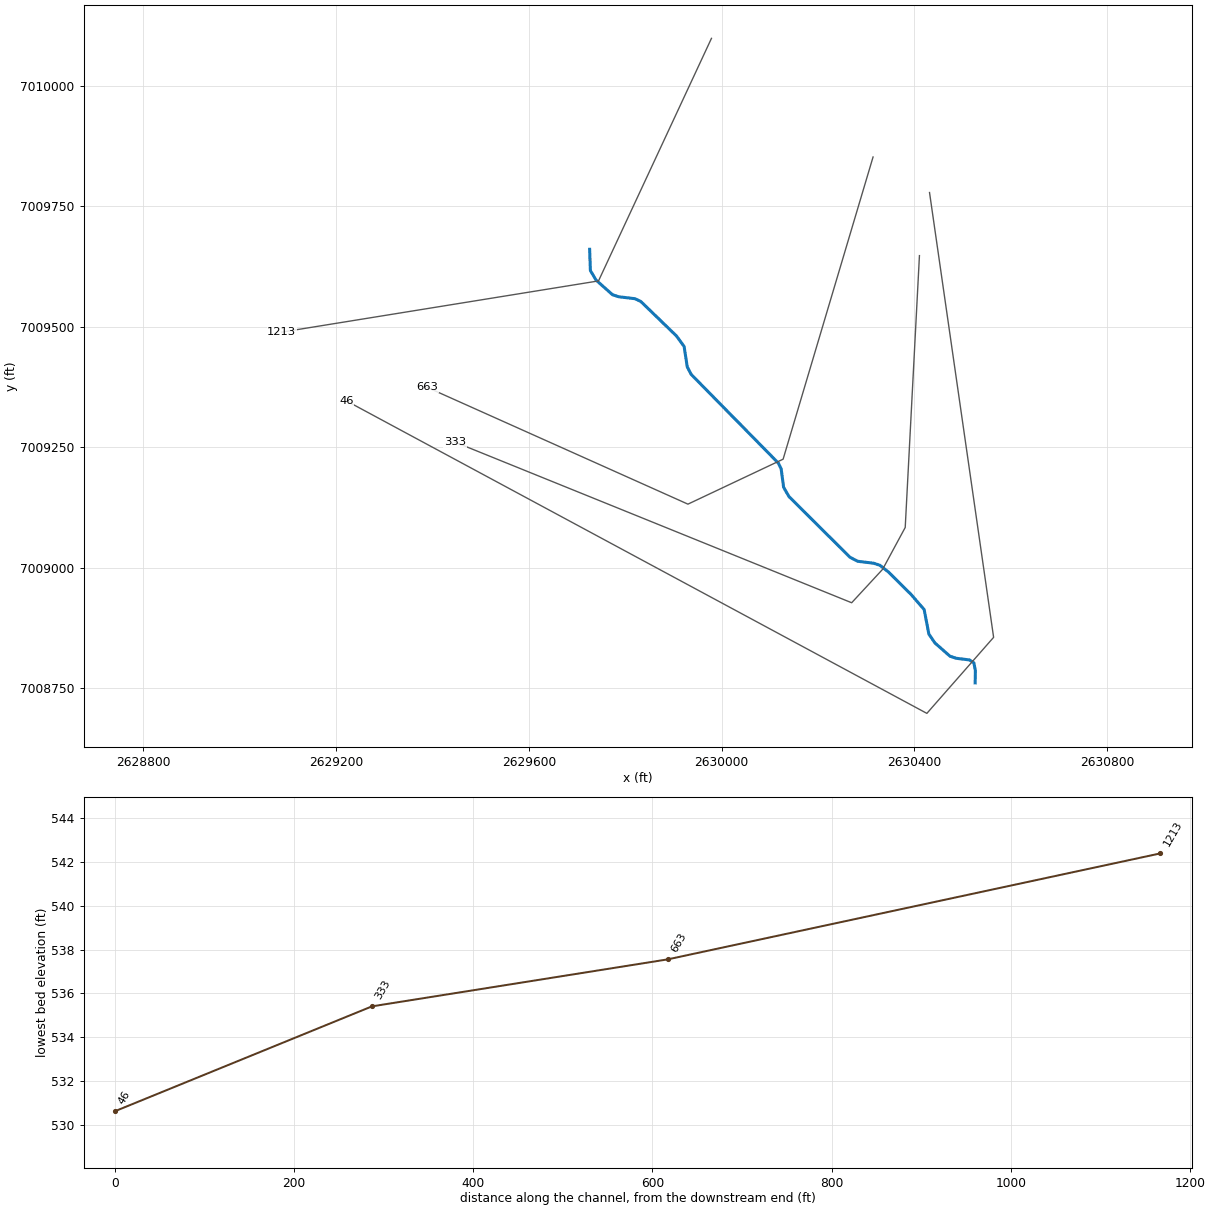
--- Hackberry Creek Tributary 10_1.prj (project) ---

Proj Title=Hackberry Creek Tributary 10_1 Base Level Engineering
Current Plan=p01
Default Exp/Contr=0.3,0.1
English Units
Geom File=g01
Flow File=f01
Plan File=p01
BEGIN DESCRIPTION:
Hackberry Creek Tributary 10_1
END DESCRIPTION:

--- Hackberry Creek Tributary 10_1.p01 (plan) ---

Plan Title=Multiple Run
Short Identifier=Multiple
Geom File=g01
Flow File=f01
Subcritical Flow
K Sum by GR= 0
Std Step Tol= 0.01
Critical Tol= 0.01
Num of Std Step Trials= 20
Max Error Tol= 0.3
Flow Tol Ratio= 0.001
Split Flow NTrial= 30
Split Flow Tol= 0.02
Split Flow Ratio= 0.02
Log Output Level= 0
Friction Slope Method= 1
Unsteady Friction Slope Method= 2
Unsteady Bridges Friction Slope Method= 1
Parabolic Critical Depth
Global Vel Dist=  1 , 1 , 1
Global Log Level= 0
CheckData=True
Encroach Param= -1, 0, 0, 0
BEGIN DESCRIPTION:
Multiple Run
END DESCRIPTION:

--- Hackberry Creek Tributary 10_1.f01 (steady flow) ---

Flow Title=Multiple
Number of Profiles=7
Profile Names=10-year,25-year,50-year,1pct_min,100-year,1pct_plu,500-year
River Rch & RM= Hackberry Creek ,Reach-1,1213
      70      81      88      48      95     190     111
River Rch & RM= Hackberry Creek ,Reach-1,46
     355     456     533     310     619    1235     831
Boundary for River Rch & Prof#=Hackberry Creek ,Reach-1,1
Up Type=0
Dn Type=3
Dn Slope=0.005
Boundary for River Rch & Prof#=Hackberry Creek ,Reach-1,2
Up Type=0
Dn Type=3
Dn Slope=0.005
Boundary for River Rch & Prof#=Hackberry Creek ,Reach-1,3
Up Type=0
Dn Type=3
Dn Slope=0.005
Boundary for River Rch & Prof#=Hackberry Creek ,Reach-1,4
Up Type=0
Dn Type=3
Dn Slope=0.005
Boundary for River Rch & Prof#=Hackberry Creek ,Reach-1,5
Up Type=0
Dn Type=3
Dn Slope=0.005
Boundary for River Rch & Prof#=Hackberry Creek ,Reach-1,6
Up Type=0
Dn Type=3
Dn Slope=0.005
Boundary for River Rch & Prof#=Hackberry Creek ,Reach-1,7
Up Type=0
Dn Type=3
Dn Slope=0.005

--- Hackberry Creek Tributary 10_1.g01 (geometry) ---

Geom Title=Existing Conditions

River Reach=Hackberry Creek ,Reach-1
Reach XY= 30
      2629726.00      7009661.00      2629727.56      7009616.87
      2629739.27      7009597.22      2629773.49      7009566.71
      2629786.53      7009562.50      2629819.95      7009558.49
      2629832.06      7009552.86      2629906.23      7009481.13
      2629922.03      7009459.36      2629928.54      7009417.05
      2629936.78      7009401.32      2630117.84      7009217.05
      2630123.47      7009204.95      2630128.53      7009167.05
      2630139.63      7009147.79      2630266.32      7009021.78
      2630282.05      7009013.54      2630315.37      7009009.45
      2630328.30      7009005.15      2630346.13      7008991.23
      2630393.08      7008944.58      2630420.15      7008913.28
      2630429.90      7008862.44      2630442.52      7008843.96
      2630473.58      7008816.60      2630486.61      7008812.19
      2630514.18      7008808.75      2630523.34      7008802.55
      2630526.44      7008786.46      2630526.00      7008761.00

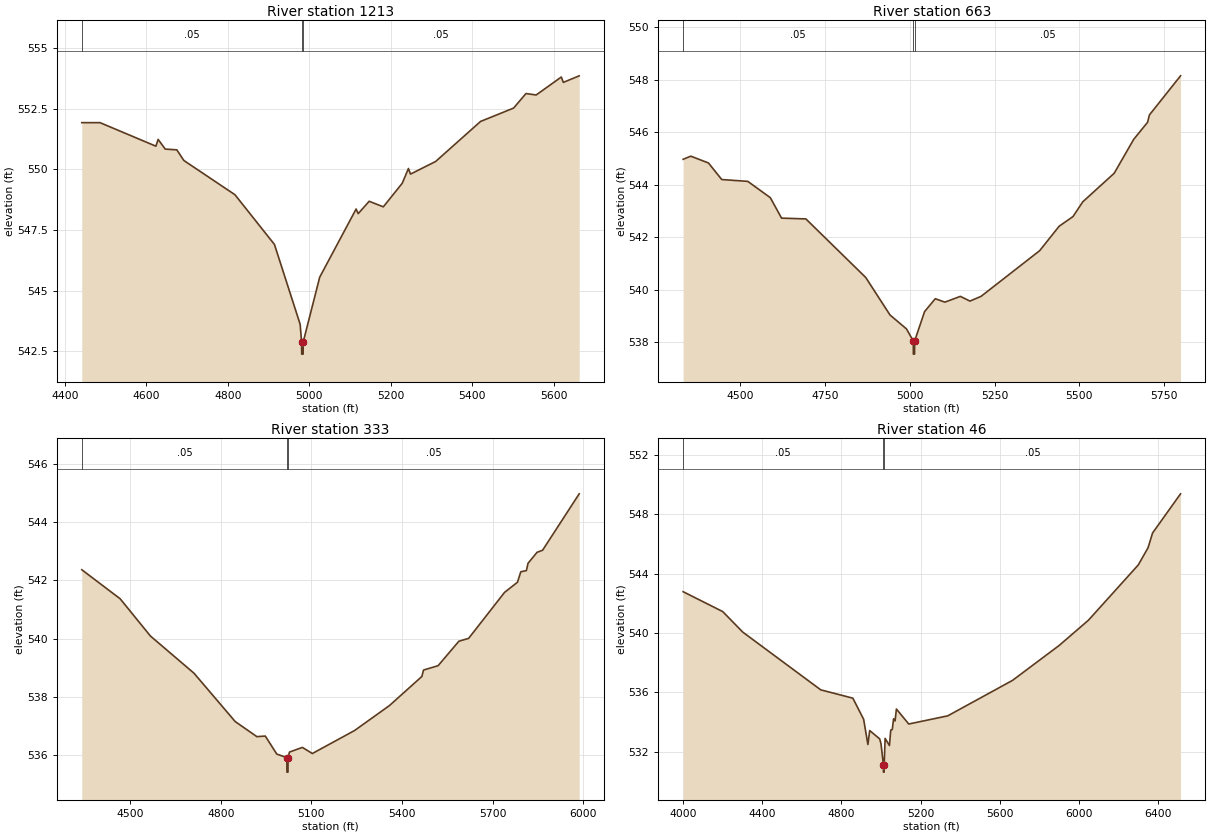
Type RM Length L Ch R = 1,1213,550,550,550
BEGIN DESCRIPTION:
Mapping XS 5294a293
END DESCRIPTION:
XS GIS Cut Line= 3
      2629978.82      7010098.88      2629744.45      7009595.42
      2629086.93      7009489.09
#Sta/Elev= 30
  4441.5  551.92  4486.3  551.92  4623.5  550.95  4629.0  551.23  4646.4  550.83
  4674.8  550.80  4692.2  550.36  4817.6  548.95  4914.6  546.90  4977.7  543.61
  4981.2  542.88  4981.5  542.38  4985.0  542.38  4985.2  542.88  5025.7  545.55
  5115.1  548.36  5120.2  548.17  5147.2  548.68  5181.9  548.45  5228.3  549.42
  5243.6  550.03  5248.7  549.80  5310.4  550.32  5420.7  551.97  5501.8  552.52
  5532.2  553.12  5557.2  553.06  5618.9  553.80  5624.0  553.58  5662.9  553.85
#Mann=3,-1,0
  4441.5    0.05       0  4981.2   0.035       0  4985.2    0.05       0
Bank Sta=4981.2,4985.2
Exp/Cntr=0.3,0.1

Type RM Length L Ch R = 1,663,330,330,330
BEGIN DESCRIPTION:
Mapping XS a84c5956
END DESCRIPTION:
XS GIS Cut Line= 4
      2630314.12      7009852.60      2630127.48      7009225.41
      2629930.00      7009132.09      2629389.27      7009374.34
#Sta/Elev= 30
  4332.7  544.97  4355.2  545.09  4407.4  544.83  4446.4  544.20  4523.2  544.13
  4589.5  543.51  4622.7  542.73  4694.3  542.70  4870.6  540.47  4942.2  539.04
  4990.7  538.51  5010.7  538.05  5011.0  537.55  5014.5  537.55  5014.7  538.05
  5044.0  539.17  5075.5  539.66  5103.8  539.53  5149.3  539.75  5177.6  539.57
  5210.3  539.75  5383.0  541.49  5440.3  542.42  5481.2  542.79  5509.9  543.35
  5602.6  544.44  5660.0  545.73  5700.9  546.38  5706.3  546.66  5798.0  548.15
#Mann=3,-1,0
  4332.7    0.05       0  5010.7   0.035       0  5014.7    0.05       0
Bank Sta=5010.7,5014.7
Exp/Cntr=0.3,0.1

Type RM Length L Ch R = 1,333,287,287,287
BEGIN DESCRIPTION:
Mapping XS 9ae7b99c
END DESCRIPTION:
XS GIS Cut Line= 5
      2630410.36      7009647.91      2630380.85      7009083.68
      2630333.97      7008996.87      2630269.73      7008927.43
      2629446.84      7009260.75
#Sta/Elev= 30
  4340.1  542.37  4467.2  541.37  4567.3  540.09  4711.6  538.81  4847.7  537.15
  4919.5  536.63  4947.4  536.65  4985.5  536.03  5018.7  535.91  5019.0  535.41
  5022.5  535.41  5022.7  535.91  5027.5  536.10  5070.1  536.26  5103.1  536.05
  5242.7  536.84  5358.4  537.70  5465.6  538.70  5471.0  538.92  5519.3  539.07
  5587.9  539.91  5620.3  540.01  5739.1  541.59  5781.9  541.94  5792.9  542.30
  5811.4  542.34  5816.8  542.59  5846.8  542.97  5865.0  543.04  5986.2  544.98
#Mann=3,-1,0
  4340.1    0.05       0  5018.7   0.035       0  5022.7    0.05       0
Bank Sta=5018.7,5022.7
Exp/Cntr=0.3,0.1

Type RM Length L Ch R = 1,46,0,0,0
BEGIN DESCRIPTION:
Hackberry Creek Tributary 10_1 1.0
END DESCRIPTION:
XS GIS Cut Line= 4
      2630431.29      7009778.84      2630564.27      7008855.64
      2630425.76      7008697.83      2629221.56      7009346.29
#Sta/Elev= 30
  4001.1  542.78  4201.0  541.44  4302.0  540.06  4695.7  536.17  4857.7  535.61
  4912.1  534.19  4933.6  532.49  4942.7  533.43  4993.0  532.87  4999.7  532.55
  5011.9  531.13  5012.1  530.63  5015.6  530.63  5015.9  531.13  5020.5  532.90
  5042.3  532.42  5049.0  533.46  5056.6  533.50  5063.2  534.22  5070.8  534.08
  5077.5  534.88  5139.8  533.87  5336.6  534.42  5663.8  536.81  5899.0  539.16
  6046.7  540.86  6298.1  544.58  6347.6  545.74  6370.2  546.73  6511.5  549.37
#Mann=3,-1,0
  4001.1    0.05       0  5011.9   0.035       0  5015.9    0.05       0
Bank Sta=5011.9,5015.9
Exp/Cntr=0.3,0.1

Chan Stop Cuts=-1