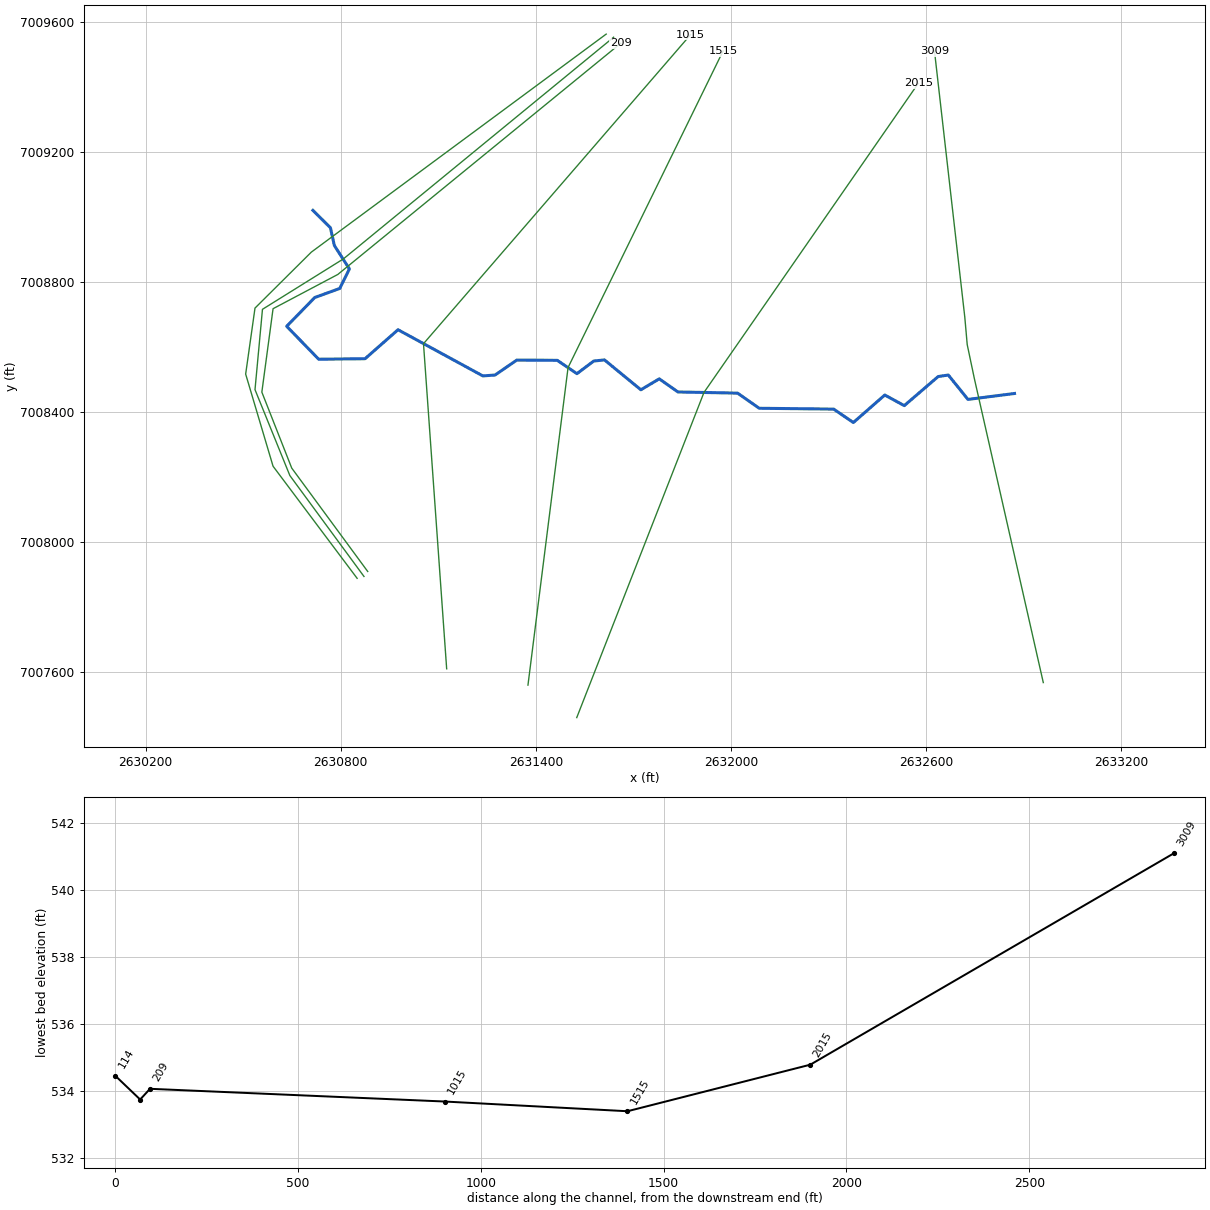
--- Hackberry Creek Tributary 10_2.prj (project) ---

Proj Title=Hackberry Creek Tributary 10_2 Base Level Engineering
Current Plan=p01
Default Exp/Contr=0.3,0.1
English Units
Geom File=g01
Flow File=f01
Plan File=p01
Y Axis Title=Elevation
X Axis Title(PF)=Main Channel Distance
X Axis Title(XS)=Station
BEGIN DESCRIPTION:
Hackberry Creek Tributary 10_2
END DESCRIPTION:
DSS Export Rating Curves= 0
DSS Export Rating Curve Sorted= 0
DSS Export Volume Flow Curves= 0
DXF OffsetX= 0
DXF OffsetY= 0
DXF ScaleX= 1
DXF ScaleY= 10

--- Hackberry Creek Tributary 10_2.p01 (plan) ---

Plan Title=Multiple Run
Short Identifier=Multiple
Geom File=g01
Flow File=f01
Subcritical Flow
K Sum by GR= 0
Std Step Tol= 0.01
Critical Tol= 0.01
Num of Std Step Trials= 20
Max Error Tol= 0.3
Flow Tol Ratio= 0.001
Split Flow NTrial= 30
Split Flow Tol= 0.02
Split Flow Ratio= 0.02
Log Output Level= 0
Friction Slope Method= 1
Unsteady Friction Slope Method= 2
Unsteady Bridges Friction Slope Method= 1
Parabolic Critical Depth
Global Vel Dist=  1 , 1 , 1
Global Log Level= 0
CheckData=True
Encroach Param= -1, 0, 0, 0
BEGIN DESCRIPTION:
Multiple Run
END DESCRIPTION:

--- Hackberry Creek Tributary 10_2.f01 (steady flow) ---

Flow Title=Multiple
Program Version=4.10
Number of Profiles= 7
Profile Names=10-year,25-year,50-year,1pct_min,100-year,1pct_plu,500-year
River Rch & RM=Hackberry Creek,Reach-1         ,3009
     290     367     426     245     489     976     644
Boundary for River Rch & Prof#=Hackberry Creek,Reach-1         , 1
Up Type= 0
Dn Type= 3
Dn Slope=0.00047
Boundary for River Rch & Prof#=Hackberry Creek,Reach-1         , 2
Up Type= 0
Dn Type= 3
Dn Slope=0.00047
Boundary for River Rch & Prof#=Hackberry Creek,Reach-1         , 3
Up Type= 0
Dn Type= 3
Dn Slope=0.00047
Boundary for River Rch & Prof#=Hackberry Creek,Reach-1         , 4
Up Type= 0
Dn Type= 3
Dn Slope=0.00047
Boundary for River Rch & Prof#=Hackberry Creek,Reach-1         , 5
Up Type= 0
Dn Type= 3
Dn Slope=0.00047
Boundary for River Rch & Prof#=Hackberry Creek,Reach-1         , 6
Up Type= 0
Dn Type= 3
Dn Slope=0.00047
Boundary for River Rch & Prof#=Hackberry Creek,Reach-1         , 7
Up Type= 0
Dn Type= 3
Dn Slope=0.00047
DSS Import GetInterval= 0
DSS Import GetPeak= 0
DSS Import FillOption= 0

--- Hackberry Creek Tributary 10_2.g01 (geometry) ---

Geom Title=Existing Conditions

River Reach=Hackberry Creek ,Reach-1
Reach XY= 30
      2632872.13      7008457.65      2632728.90      7008439.42
      2632668.51      7008514.45      2632637.31      7008509.72
      2632533.18      7008420.32      2632473.19      7008452.97
      2632376.62      7008368.34      2632316.09      7008409.61
      2632087.03      7008412.22      2632020.58      7008458.74
      2631836.96      7008462.38      2631779.74      7008502.71
      2631723.19      7008469.01      2631611.16      7008560.98
      2631578.17      7008557.42      2631526.53      7008518.59
      2631466.08      7008559.63      2631341.74      7008560.48
      2631274.78      7008514.37      2631237.20      7008511.75
      2630976.44      7008653.70      2630875.05      7008564.55
      2630732.36      7008563.05      2630634.10      7008664.34
      2630720.46      7008752.83      2630797.20      7008780.63
      2630826.93      7008840.73      2630780.63      7008912.67
      2630768.61      7008967.15      2630714.67      7009020.85

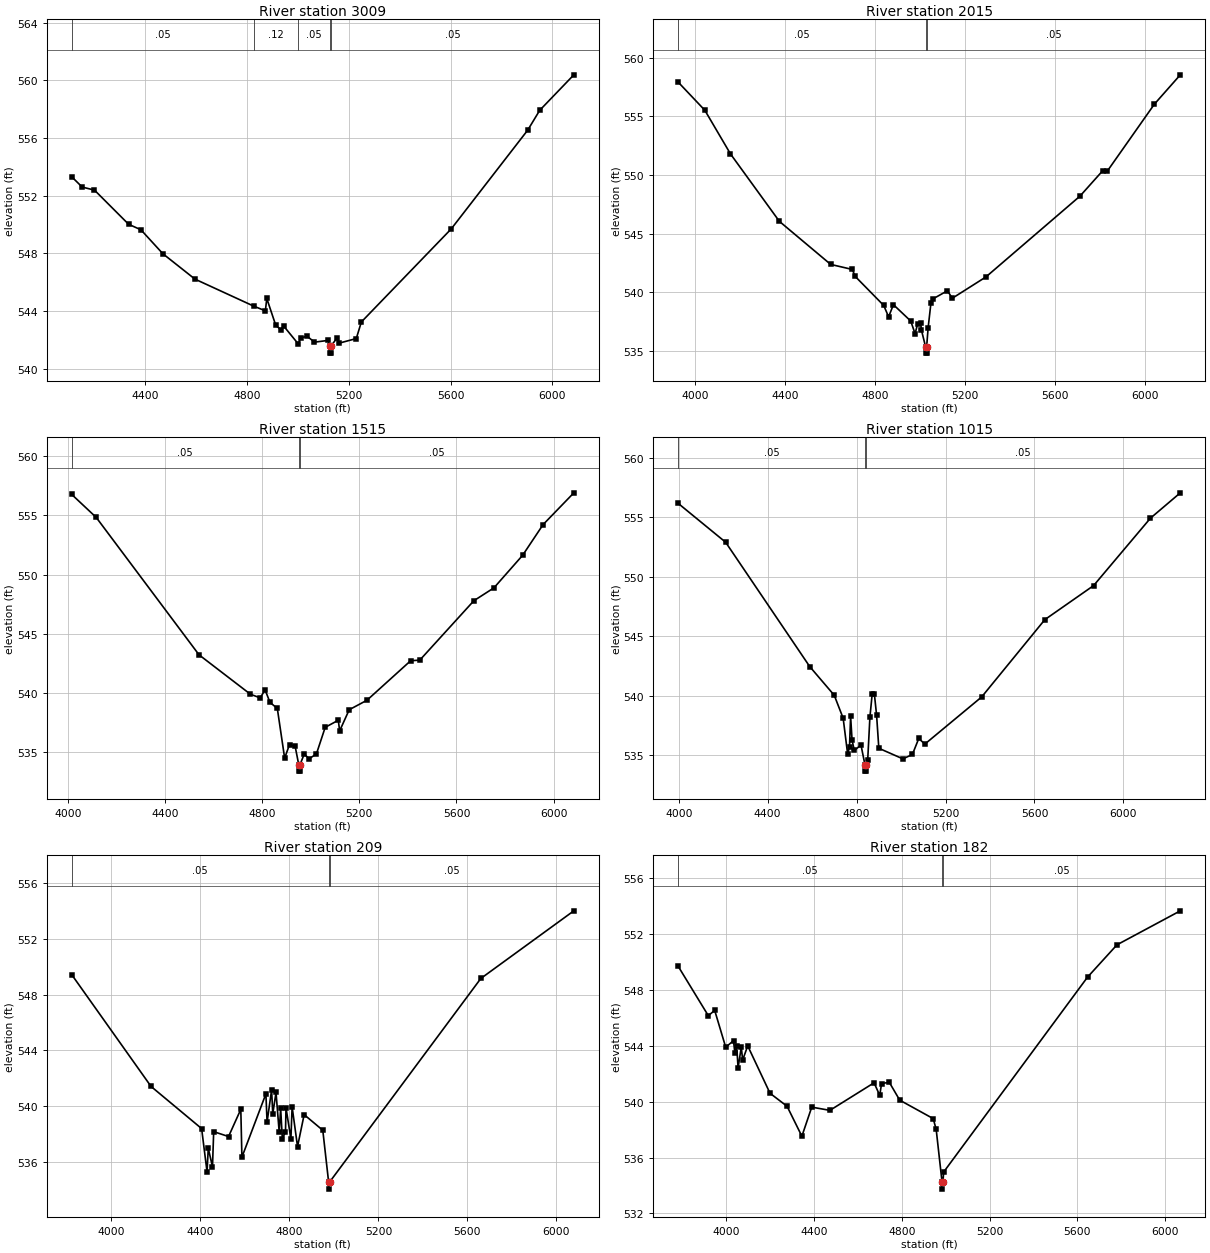
Type RM Length L Ch R = 1,3009,994,994,994
BEGIN DESCRIPTION:
Hackberry Creek Tributary 10_2 5.0
END DESCRIPTION:
XS GIS Cut Line= 5
      2632960.63      7007568.66      2632748.83      7008502.64
      2632726.68      7008608.00      2632719.26      7008692.14
      2632626.00      7009511.02
#Sta/Elev= 30
  4110.9  553.31  4151.8  552.60  4200.1  552.39  4334.5  550.02  4382.8  549.64
  4469.0  547.98  4595.2  546.22  4826.0  544.35  4872.1  544.02  4877.6  544.88
  4913.1  543.01  4933.6  542.71  4943.9  542.97  5000.8  541.74  5012.0  542.15
  5036.2  542.26  5065.2  541.85  5118.0  541.97  5126.2  541.59  5126.5  541.09
  5130.0  541.09  5130.2  541.59  5154.5  542.15  5159.6  541.77  5229.5  542.10
  5249.5  543.25  5602.8  549.70  5903.7  556.55  5950.7  557.92  6084.9  560.38
#Mann=5,-1,0
  4110.9    0.05       0  4826.0    0.12       0  5000.8    0.05       0
  5126.2    0.07       0  5130.2    0.05       0
Bank Sta=5126.2,5130.2
Exp/Cntr=0.3,0.1

Type RM Length L Ch R = 1,2015,500,500,500
BEGIN DESCRIPTION:
Hackberry Creek Tributary 10_2 4.0
END DESCRIPTION:
XS GIS Cut Line= 3
      2631525.99      7007460.97      2631917.28      7008460.95
      2632576.01      7009411.02
#Sta/Elev= 30
  3926.2  557.93  4044.4  555.53  4158.3  551.80  4375.4  546.04  4603.3  542.36
  4699.4  541.93  4711.9  541.34  4839.0  538.85  4860.5  537.88  4881.9  538.92
  4958.9  537.52  4978.0  536.44  4989.3  537.26  5003.1  537.35  5006.3  536.75
  5025.3  535.28  5025.5  534.78  5029.0  534.78  5029.3  535.28  5036.1  536.95
  5048.7  539.09  5057.0  539.41  5121.8  540.11  5143.5  539.47  5292.8  541.29
  5710.2  548.19  5811.6  550.37  5832.5  550.35  6041.2  556.06  6156.1  558.56
#Mann=3,-1,0
  3926.2    0.05       0  5025.3    0.03       0  5029.3    0.05       0
Bank Sta=5025.3,5029.3
Exp/Cntr=0.3,0.1

Type RM Length L Ch R = 1,1515,500,500,500
BEGIN DESCRIPTION:
Hackberry Creek Tributary 10_2 3.0
END DESCRIPTION:
XS GIS Cut Line= 3
      2631376.00      7007560.96      2631499.29      7008537.43
      2631975.98      7009510.97
#Sta/Elev= 30
  4015.4  556.77  4116.2  554.83  4539.6  543.22  4751.2  539.89  4791.6  539.58
  4811.7  540.26  4831.9  539.20  4862.1  538.69  4892.3  534.49  4912.5  535.64
  4935.6  535.48  4950.8  533.89  4951.1  533.39  4954.6  533.39  4954.8  533.89
  4973.0  534.84  4993.1  534.43  5023.3  534.85  5059.3  537.09  5113.3  537.69
  5118.9  536.79  5158.3  538.58  5231.4  539.38  5411.4  542.72  5449.0  542.77
  5671.7  547.79  5754.5  548.88  5872.6  551.63  5957.1  554.23  6083.6  556.91
#Mann=3,-1,0
  4015.4    0.05       0  4950.8    0.03       0  4954.8    0.05       0
Bank Sta=4950.8,4954.8
Exp/Cntr=0.3,0.1

Type RM Length L Ch R = 1,1015,806,806,806
BEGIN DESCRIPTION:
Hackberry Creek Tributary 10_2 2.0
END DESCRIPTION:
XS GIS Cut Line= 3
      2631126.00      7007611.05      2631054.76      7008610.76
      2631876.01      7009561.01
#Sta/Elev= 30
  3997.7  556.16  4210.9  552.90  4589.1  542.46  4699.4  540.05  4739.5  538.12
  4759.6  535.12  4768.0  535.71  4773.0  538.28  4779.6  536.26  4789.7  535.42
  4819.7  535.87  4837.8  534.18  4838.0  533.68  4841.5  533.68  4841.8  534.18
  4849.8  534.59  4859.8  538.22  4869.9  540.12  4879.9  540.15  4889.9  538.37
  4899.9  535.60  5008.2  534.71  5050.9  535.08  5079.5  536.42  5106.9  535.95
  5362.5  539.91  5646.5  546.40  5865.9  549.26  6121.5  554.92  6255.9  557.05
#Mann=3,-1,0
  3997.7    0.05       0  4837.8    0.03       0  4841.8    0.05       0
Bank Sta=4837.8,4841.8
Exp/Cntr=0.3,0.1

Type RM Length L Ch R = 1,209,27,27,27
BEGIN DESCRIPTION:
Mapping XS 6e6e6dfc
END DESCRIPTION:
XS GIS Cut Line= 6
      2630883.21      7007910.35      2630649.60      7008228.22
      2630557.69      7008461.81      2630592.16      7008718.39
      2630791.29      7008823.70      2631660.57      7009534.06
#Sta/Elev= 30
  3821.6  549.43  4178.0  541.42  4405.3  538.40  4429.7  535.29  4435.1  536.99
  4454.1  535.66  4459.5  538.18  4526.3  537.83  4581.4  539.78  4586.4  536.35
  4694.2  540.89  4699.5  538.86  4719.8  541.17  4725.1  539.46  4739.7  540.99
  4753.9  538.16  4760.6  539.84  4768.1  537.65  4782.3  538.18  4784.5  539.89
  4806.6  537.66  4812.0  539.96  4836.4  537.11  4866.1  539.40  4949.9  538.28
  4976.2  534.56  4976.5  534.06  4980.2  534.56  5660.2  549.16  6078.4  554.01
#Mann=3,-1,0
  3821.6    0.05       0  4976.2   0.035       0  4980.2    0.05       0
Bank Sta=4976.2,4980.2
Exp/Cntr=0.3,0.1

Type RM Length L Ch R = 1,182,68,68,68
BEGIN DESCRIPTION:
Mapping XS 07067285
END DESCRIPTION:
XS GIS Cut Line= 6
      2630871.74      7007895.01      2630643.85      7008205.24
      2630536.63      7008469.47      2630559.60      7008716.48
      2630808.52      7008871.57      2631639.49      7009553.19
#Sta/Elev= 30
  3780.3  549.66  3917.3  546.14  3946.6  546.51  3996.8  543.88  4032.3  544.35
  4038.5  543.46  4047.0  543.94  4053.2  542.40  4067.8  543.90  4074.0  542.96
  4097.1  543.98  4198.9  540.59  4276.6  539.66  4344.1  537.52  4389.1  539.60
  4471.9  539.37  4673.3  541.34  4699.1  540.44  4707.4  541.28  4742.5  541.38
  4790.2  540.10  4942.9  538.78  4956.5  538.01  4983.3  534.24  4983.5  533.74
  4987.3  534.24  4990.5  534.96  5646.6  548.89  5780.8  551.20  6069.7  553.63
#Mann=3,-1,0
  3780.3    0.05       0  4983.3   0.035       0  4987.3    0.05       0
Bank Sta=4983.3,4987.3
Exp/Cntr=0.3,0.1

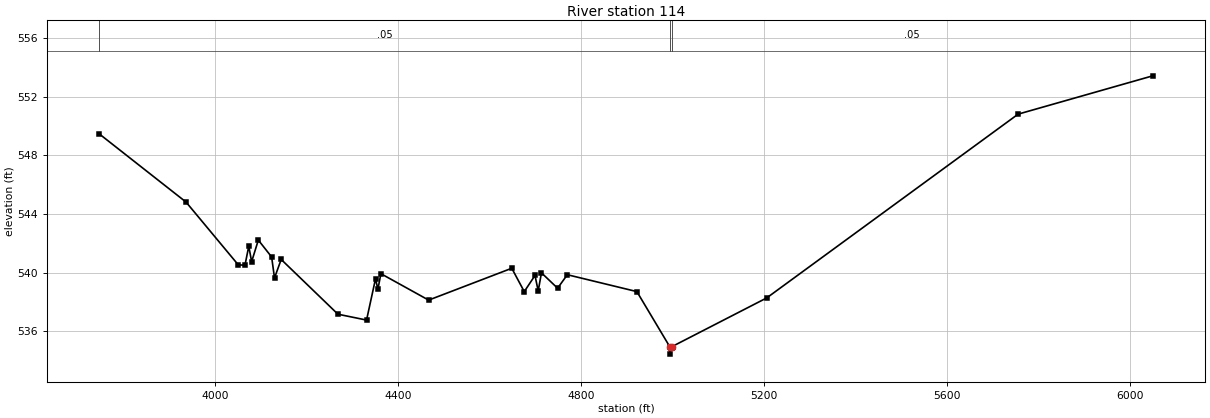
Type RM Length L Ch R = 1,114,0,0,0
BEGIN DESCRIPTION:
Mapping XS 282c1f58
END DESCRIPTION:
XS GIS Cut Line= 6
      2630850.66      7007889.29      2630592.16      7008233.96
      2630507.91      7008517.34      2630536.63      7008720.31
      2630709.81      7008892.31      2631616.55      7009562.79
#Sta/Elev= 30
  3747.0  549.45  3936.6  544.81  4050.9  540.53  4065.5  540.51  4073.8  541.80
  4080.1  540.75  4094.7  542.22  4123.8  541.07  4130.1  539.64  4144.7  540.90
  4268.8  537.17  4331.4  536.77  4351.0  539.58  4356.2  538.87  4362.8  539.93
  4467.2  538.13  4649.0  540.30  4676.3  538.71  4699.8  539.81  4706.8  538.75
  4713.9  539.99  4749.2  538.94  4770.5  539.86  4922.6  538.71  4994.6  534.95
  4994.9  534.45  4998.6  534.95  5206.6  538.28  5756.4  550.80  6050.8  553.41
#Mann=3,-1,0
  3747.0    0.05       0  4994.6   0.035       0  4998.6    0.05       0
Bank Sta=4994.6,4998.6
Exp/Cntr=0.3,0.1

Chan Stop Cuts=-1