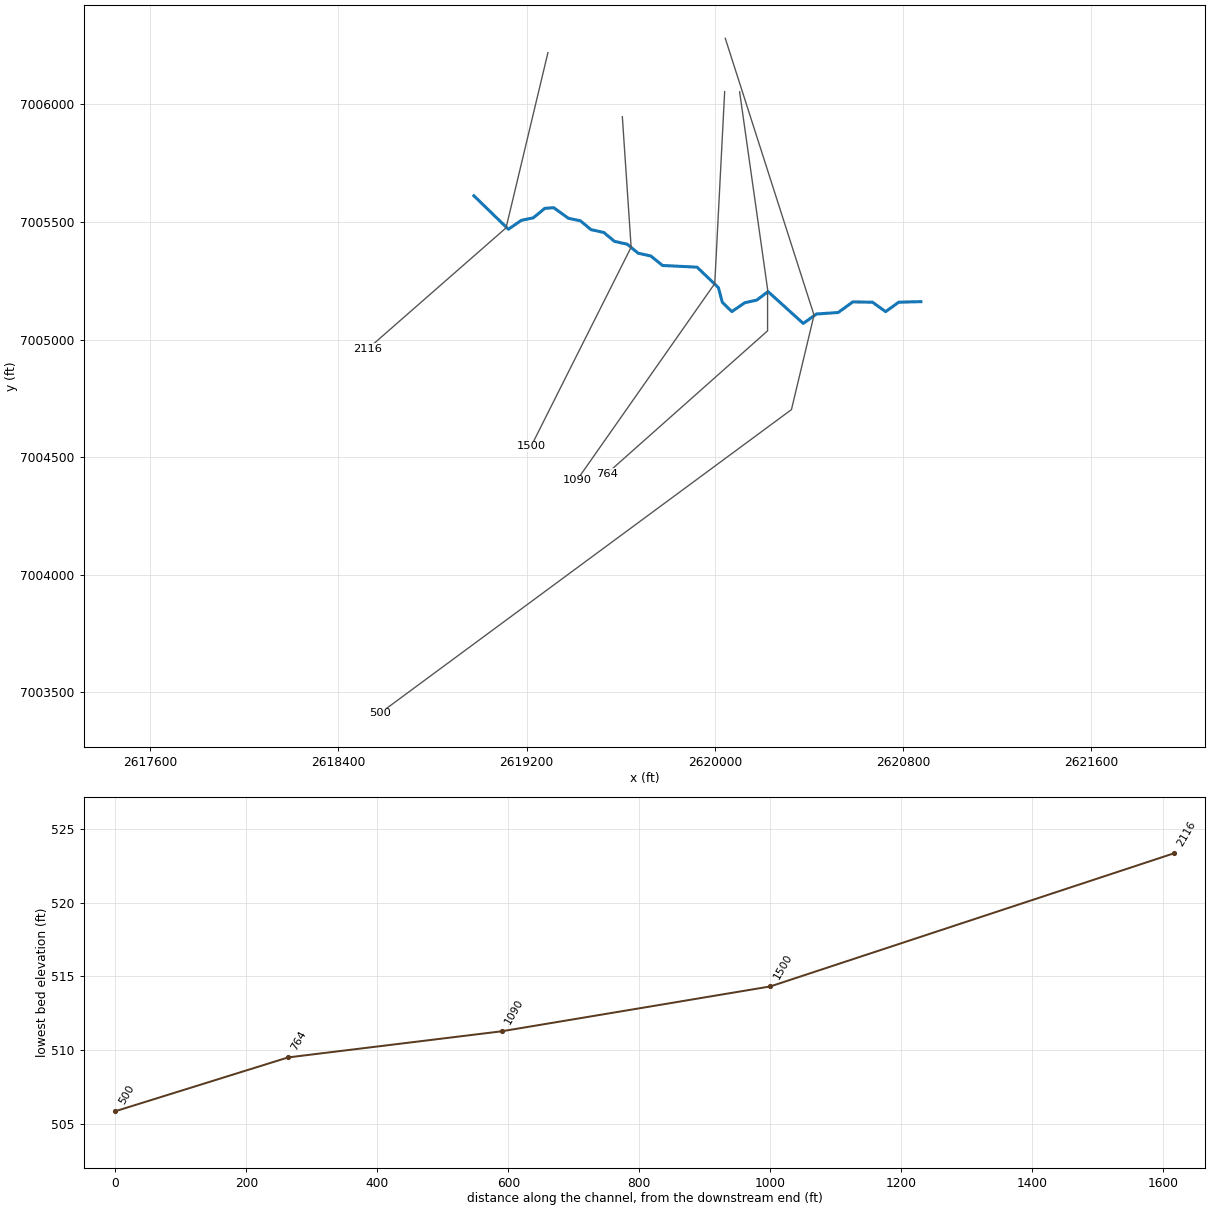
--- Hackberry Creek Tributary 2.prj (project) ---

Proj Title=Hackberry Creek Tributary 2 Base Level Engineering
Current Plan=p01
Default Exp/Contr=0.3,0.1
English Units
Geom File=g01
Flow File=f01
Plan File=p01
BEGIN DESCRIPTION:
Hackberry Creek Tributary 2
END DESCRIPTION:

--- Hackberry Creek Tributary 2.p01 (plan) ---

Plan Title=Multiple Run
Short Identifier=Multiple
Geom File=g01
Flow File=f01
Subcritical Flow
K Sum by GR= 0
Std Step Tol= 0.01
Critical Tol= 0.01
Num of Std Step Trials= 20
Max Error Tol= 0.3
Flow Tol Ratio= 0.001
Split Flow NTrial= 30
Split Flow Tol= 0.02
Split Flow Ratio= 0.02
Log Output Level= 0
Friction Slope Method= 1
Unsteady Friction Slope Method= 2
Unsteady Bridges Friction Slope Method= 1
Parabolic Critical Depth
Global Vel Dist=  1 , 1 , 1
Global Log Level= 0
CheckData=True
Encroach Param= -1, 0, 0, 0
BEGIN DESCRIPTION:
Multiple Run
END DESCRIPTION:

--- Hackberry Creek Tributary 2.f01 (steady flow) ---

Flow Title=Multiple
Number of Profiles=7
Profile Names=10-year,25-year,50-year,1pct_min,100-year,1pct_plu,500-year
River Rch & RM= Hackberry Creek ,Reach-1,2116
     150     184     209     119     237     474     303
Boundary for River Rch & Prof#=Hackberry Creek ,Reach-1,1
Up Type=0
Dn Type=3
Dn Slope=0.005
Boundary for River Rch & Prof#=Hackberry Creek ,Reach-1,2
Up Type=0
Dn Type=3
Dn Slope=0.005
Boundary for River Rch & Prof#=Hackberry Creek ,Reach-1,3
Up Type=0
Dn Type=3
Dn Slope=0.005
Boundary for River Rch & Prof#=Hackberry Creek ,Reach-1,4
Up Type=0
Dn Type=3
Dn Slope=0.005
Boundary for River Rch & Prof#=Hackberry Creek ,Reach-1,5
Up Type=0
Dn Type=3
Dn Slope=0.005
Boundary for River Rch & Prof#=Hackberry Creek ,Reach-1,6
Up Type=0
Dn Type=3
Dn Slope=0.005
Boundary for River Rch & Prof#=Hackberry Creek ,Reach-1,7
Up Type=0
Dn Type=3
Dn Slope=0.005

--- Hackberry Creek Tributary 2.g01 (geometry) ---

Geom Title=Existing Conditions

River Reach=Hackberry Creek ,Reach-1
Reach XY= 30
      2618976.00      7005611.00      2619122.59      7005468.76
      2619177.63      7005506.57      2619228.19      7005517.13
      2619277.72      7005557.66      2619315.31      7005560.26
      2619377.72      7005515.22      2619428.20      7005504.92
      2619473.80      7005467.08      2619528.20      7005454.92
      2619573.80      7005417.08      2619628.20      7005404.92
      2619673.80      7005367.08      2619728.18      7005354.88
      2619777.56      7005314.76      2619924.54      7005307.46
      2620015.23      7005220.67      2620031.85      7005158.15
      2620072.34      7005118.67      2620127.64      7005156.59
      2620178.29      7005167.38      2620226.09      7005203.71
      2620375.90      7005068.31      2620431.89      7005108.44
      2620524.40      7005114.86      2620586.55      7005159.89
      2620670.11      7005158.64      2620726.01      7005118.52
      2620781.77      7005158.66      2620876.00      7005161.00

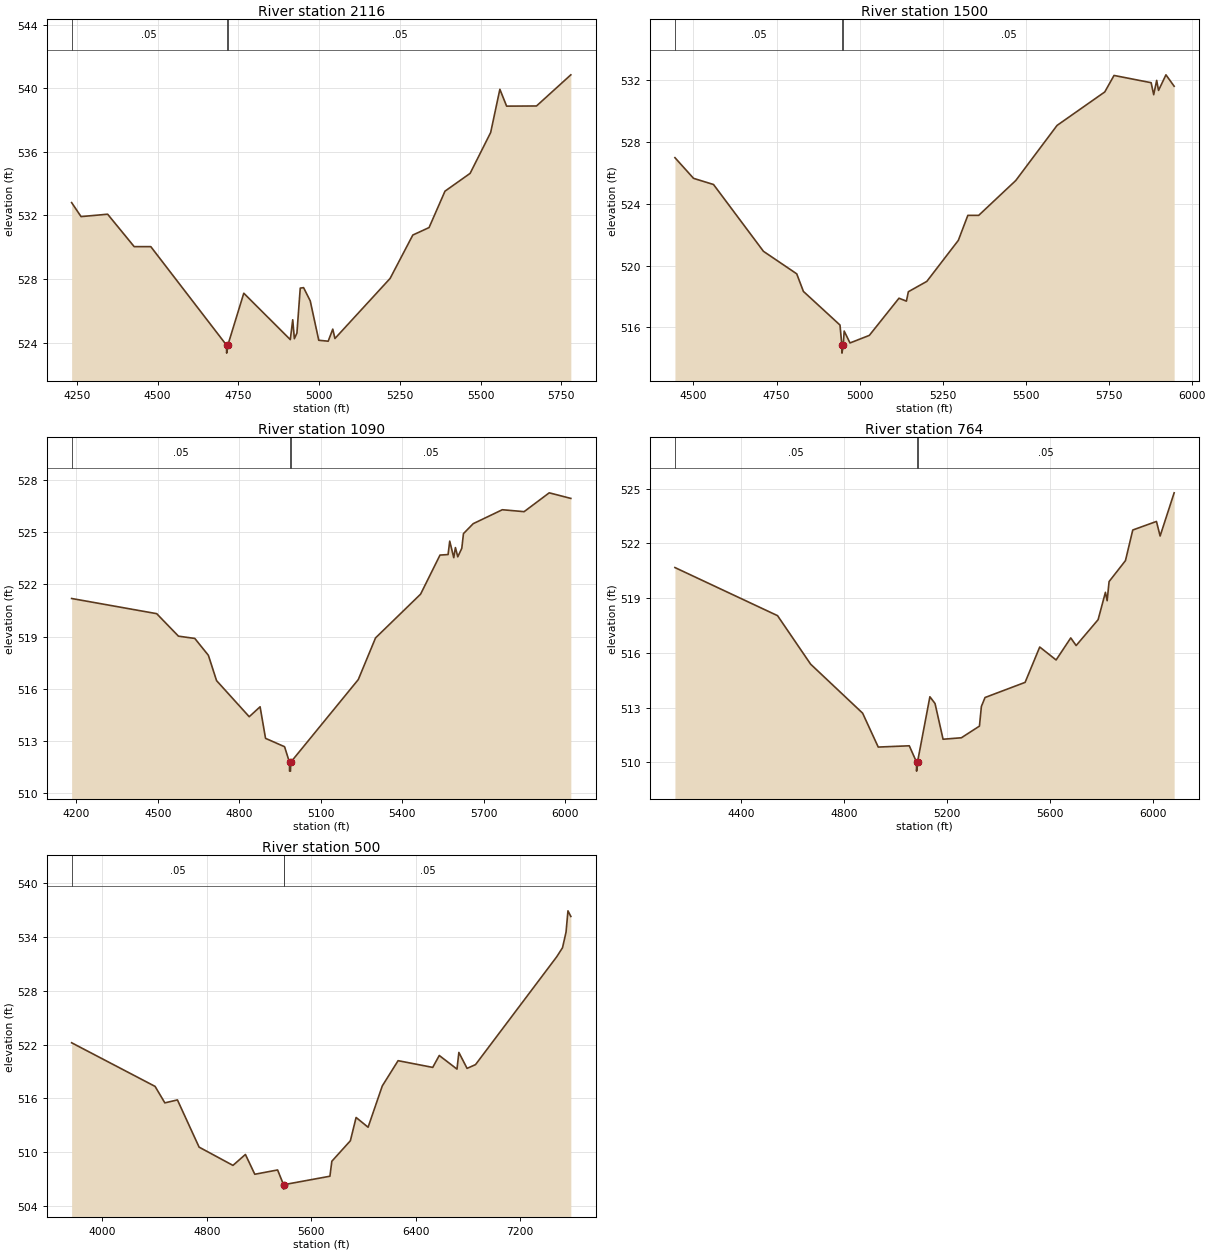
Type RM Length L Ch R = 1,2116,616,616,616
BEGIN DESCRIPTION:
Hackberry Creek Tributary 2 4.0
END DESCRIPTION:
XS GIS Cut Line= 3
      2619290.67      7006219.42      2619112.62      7005474.50
      2618526.02      7004961.01
#Sta/Elev= 30
  4234.1  532.81  4263.3  531.93  4345.6  532.08  4427.8  530.04  4479.2  530.04
  4713.7  523.84  4714.0  523.34  4717.7  523.84  4767.1  527.11  4911.1  524.19
  4918.6  525.44  4923.7  524.25  4931.6  524.60  4941.9  527.43  4952.2  527.46
  4972.8  526.63  4999.2  524.15  5028.4  524.09  5042.6  524.85  5049.3  524.26
  5220.1  528.04  5290.4  530.77  5340.7  531.24  5390.0  533.53  5467.8  534.65
  5531.4  537.22  5559.9  539.94  5580.8  538.88  5673.3  538.89  5779.6  540.85
#Mann=3,-1,0
  4234.1    0.05       0  4713.7   0.035       0  4717.7    0.05       0
Bank Sta=4713.7,4717.7
Exp/Cntr=0.3,0.1

Type RM Length L Ch R = 1,1500,410,410,410
BEGIN DESCRIPTION:
Hackberry Creek Tributary 2 3.0
END DESCRIPTION:
XS GIS Cut Line= 3
      2619606.90      7005946.91      2619644.27      7005392.37
      2619218.94      7004545.92
#Sta/Elev= 30
  4444.2  526.99  4500.2  525.65  4560.4  525.25  4710.7  520.92  4810.9  519.46
  4831.0  518.32  4941.2  516.14  4946.8  514.82  4947.1  514.32  4950.8  514.82
  4953.8  515.75  4971.3  514.98  5029.5  515.47  5118.8  517.88  5141.2  517.69
  5147.0  518.30  5202.6  518.97  5297.5  521.63  5326.1  523.25  5358.8  523.25
  5470.5  525.51  5594.7  529.08  5738.4  531.25  5766.3  532.32  5878.0  531.85
  5885.7  531.07  5894.7  532.00  5900.3  531.35  5922.6  532.36  5947.3  531.62
#Mann=3,-1,0
  4444.2    0.05       0  4946.8   0.035       0  4950.8    0.05       0
Bank Sta=4946.8,4950.8
Exp/Cntr=0.3,0.1

Type RM Length L Ch R = 1,1090,326,326,326
BEGIN DESCRIPTION:
Hackberry Creek Tributary 2 2.0
END DESCRIPTION:
XS GIS Cut Line= 3
      2620041.80      7006053.59      2619999.73      7005237.88
      2619414.18      7004402.57
#Sta/Elev= 30
  4183.2  521.18  4496.2  520.31  4576.3  519.02  4636.4  518.89  4686.5  517.92
  4716.5  516.47  4836.7  514.40  4876.7  514.97  4896.7  513.16  4966.8  512.68
  4984.9  511.78  4985.1  511.28  4988.6  511.28  4988.9  511.78  5238.0  516.53
  5301.5  518.92  5467.3  521.43  5538.7  523.67  5568.4  523.70  5574.5  524.47
  5589.3  523.52  5595.4  524.10  5604.1  523.57  5618.9  524.06  5625.0  524.90
  5660.8  525.47  5768.0  526.27  5848.2  526.16  5940.6  527.24  6020.1  526.92
#Mann=3,-1,0
  4183.2    0.05       0  4984.9    0.03       0  4988.9    0.05       0
Bank Sta=4984.9,4988.9
Exp/Cntr=0.3,0.1

Type RM Length L Ch R = 1,764,264,264,264
BEGIN DESCRIPTION:
Mapping XS d48be7ad
END DESCRIPTION:
XS GIS Cut Line= 4
      2620105.40      7006052.73      2620224.25      7005214.08
      2620224.25      7005036.92      2619540.61      7004429.49
#Sta/Elev= 30
  4142.3  520.68  4540.8  518.04  4669.2  515.38  4871.2  512.69  4931.8  510.83
  5052.4  510.90  5080.4  510.01  5080.7  509.51  5084.4  510.01  5132.4  513.59
  5152.4  513.22  5183.6  511.26  5254.7  511.34  5324.9  511.98  5332.4  513.06
  5346.6  513.55  5502.2  514.38  5559.0  516.32  5622.6  515.61  5679.5  516.82
  5700.4  516.40  5785.7  517.82  5814.1  519.32  5820.8  518.86  5828.3  519.91
  5891.9  521.06  5920.3  522.74  6012.3  523.21  6026.5  522.41  6081.0  524.78
#Mann=3,-1,0
  4142.3    0.05       0  5080.4    0.03       0  5084.4    0.05       0
Bank Sta=5080.4,5084.4
Exp/Cntr=0.3,0.1

Type RM Length L Ch R = 1,500,0,0,0
BEGIN DESCRIPTION:
Hackberry Creek Tributary 2 1.0
END DESCRIPTION:
XS GIS Cut Line= 4
      2620044.41      7006280.17      2620421.69      7005103.69
      2620325.66      7004702.07      2618575.98      7003410.98
#Sta/Elev= 30
  3764.5  522.20  4403.6  517.33  4478.4  515.49  4574.8  515.82  4740.6  510.55
  5000.0  508.51  5095.3  509.73  5167.3  507.52  5341.9  508.00  5387.1  506.36
  5387.4  505.86  5391.1  506.36  5742.5  507.30  5757.1  508.97  5899.1  511.26
  5943.0  513.86  6034.8  512.77  6143.5  517.38  6264.5  520.20  6529.8  519.45
  6579.9  520.78  6715.6  519.26  6729.9  521.12  6792.8  519.34  6857.5  519.76
  7479.8  531.81  7523.7  532.81  7550.8  534.56  7565.4  536.93  7587.4  536.30
#Mann=3,-1,0
  3764.5    0.05       0  5387.1    0.03       0  5391.1    0.05       0
Bank Sta=5387.1,5391.1
Exp/Cntr=0.3,0.1

Chan Stop Cuts=-1