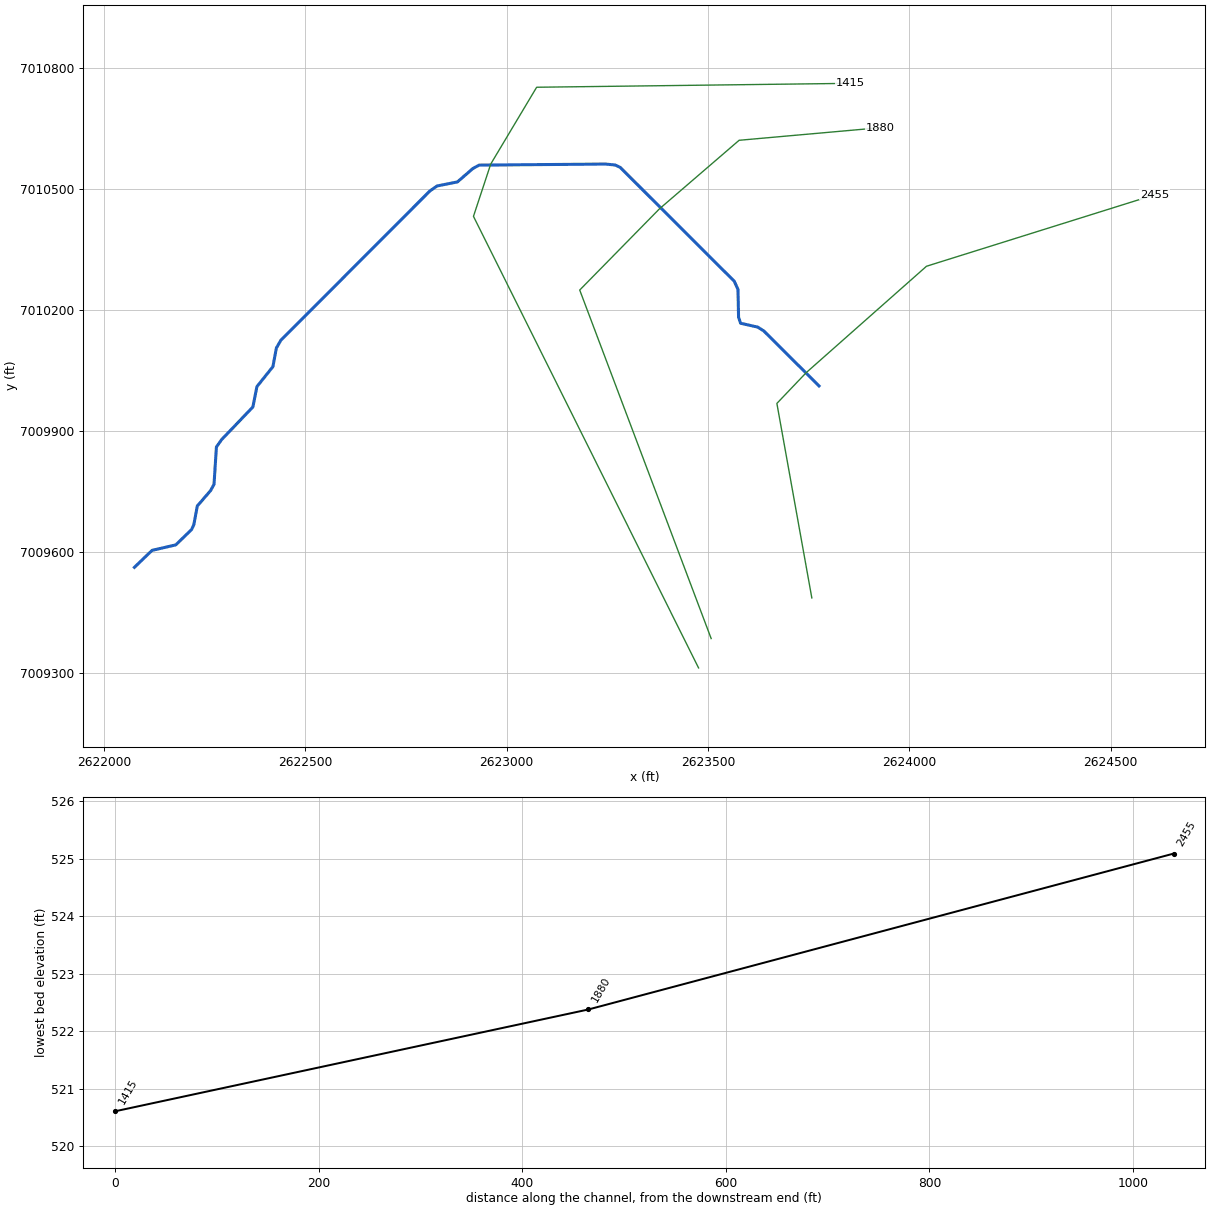
--- Hackberry Creek Tributary 3.prj (project) ---

Proj Title=Hackberry Creek Tributary 3 Base Level Engineering
Current Plan=p01
Default Exp/Contr=0.3,0.1
English Units
Geom File=g01
Flow File=f01
Plan File=p01
BEGIN DESCRIPTION:
Hackberry Creek Tributary 3
END DESCRIPTION:

--- Hackberry Creek Tributary 3.p01 (plan) ---

Plan Title=Multiple Run
Short Identifier=Multiple
Geom File=g01
Flow File=f01
Subcritical Flow
K Sum by GR= 0
Std Step Tol= 0.01
Critical Tol= 0.01
Num of Std Step Trials= 20
Max Error Tol= 0.3
Flow Tol Ratio= 0.001
Split Flow NTrial= 30
Split Flow Tol= 0.02
Split Flow Ratio= 0.02
Log Output Level= 0
Friction Slope Method= 1
Unsteady Friction Slope Method= 2
Unsteady Bridges Friction Slope Method= 1
Parabolic Critical Depth
Global Vel Dist=  1 , 1 , 1
Global Log Level= 0
CheckData=True
Encroach Param= -1, 0, 0, 0
BEGIN DESCRIPTION:
Multiple Run
END DESCRIPTION:

--- Hackberry Creek Tributary 3.f01 (steady flow) ---

Flow Title=Multiple
Number of Profiles=7
Profile Names=10-year,25-year,50-year,1pct_min,100-year,1pct_plu,500-year
River Rch & RM= Hackberry Creek ,Reach-1,2455
     176     218     249     142     283     566     365
Boundary for River Rch & Prof#=Hackberry Creek ,Reach-1,1
Up Type=0
Dn Type=3
Dn Slope=0.005
Boundary for River Rch & Prof#=Hackberry Creek ,Reach-1,2
Up Type=0
Dn Type=3
Dn Slope=0.005
Boundary for River Rch & Prof#=Hackberry Creek ,Reach-1,3
Up Type=0
Dn Type=3
Dn Slope=0.005
Boundary for River Rch & Prof#=Hackberry Creek ,Reach-1,4
Up Type=0
Dn Type=3
Dn Slope=0.005
Boundary for River Rch & Prof#=Hackberry Creek ,Reach-1,5
Up Type=0
Dn Type=3
Dn Slope=0.005
Boundary for River Rch & Prof#=Hackberry Creek ,Reach-1,6
Up Type=0
Dn Type=3
Dn Slope=0.005
Boundary for River Rch & Prof#=Hackberry Creek ,Reach-1,7
Up Type=0
Dn Type=3
Dn Slope=0.005

--- Hackberry Creek Tributary 3.g01 (geometry) ---

Geom Title=Existing Conditions

River Reach=Hackberry Creek ,Reach-1
Reach XY= 30
      2623776.00      7010011.00      2623638.95      7010147.27
      2623623.92      7010156.85      2623581.26      7010166.47
      2623576.22      7010181.26      2623574.79      7010250.41
      2623565.47      7010270.75      2623282.19      7010553.19
      2623270.15      7010558.94      2623246.18      7010561.43
      2622931.93      7010558.76      2622916.33      7010550.21
      2622878.17      7010517.14      2622827.63      7010507.06
      2622809.32      7010494.36      2622439.62      7010124.21
      2622428.50      7010104.96      2622419.90      7010058.81
      2622380.19      7010009.27      2622370.15      7009958.71
      2622292.49      7009877.74      2622279.62      7009859.50
      2622273.67      7009766.97      2622265.16      7009751.34
      2622232.15      7009713.15      2622223.58      7009666.85
      2622217.99      7009654.66      2622178.61      7009616.61
      2622119.89      7009603.05      2622076.00      7009561.00

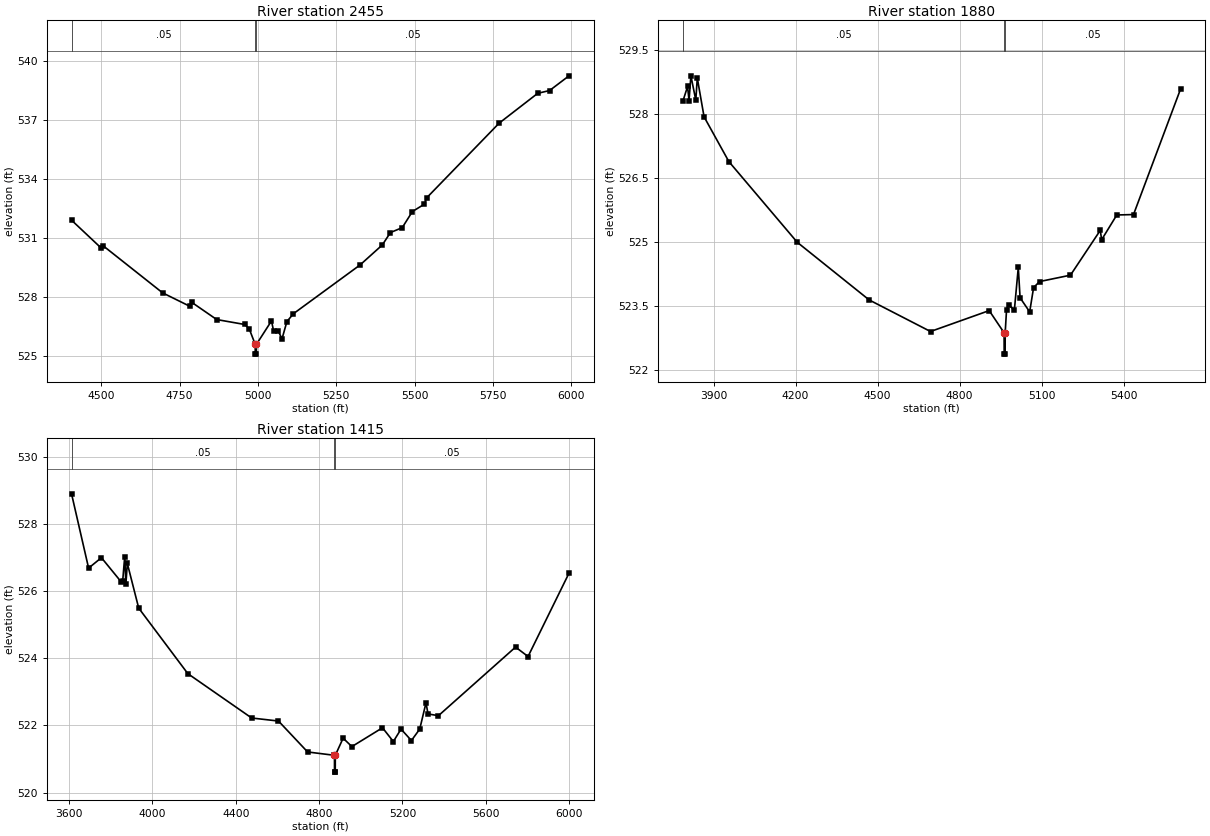
Type RM Length L Ch R = 1,2455,575,575,575
BEGIN DESCRIPTION:
Mapping XS 0ab8cf02
END DESCRIPTION:
XS GIS Cut Line= 5
      2623758.15      7009484.98      2623671.35      7009967.60
      2623744.27      7010043.99      2624042.88      7010307.88
      2624608.85      7010484.96
#Sta/Elev= 30
  4404.9  531.91  4499.6  530.49  4504.7  530.62  4695.5  528.21  4783.1  527.52
  4788.2  527.73  4868.2  526.85  4957.4  526.60  4971.6  526.39  4991.0  525.59
  4991.2  525.09  4994.7  525.09  4995.0  525.59  5042.9  526.78  5049.5  526.29
  5063.8  526.29  5076.6  525.87  5092.2  526.75  5113.1  527.15  5325.6  529.63
  5396.7  530.65  5422.5  531.28  5460.2  531.53  5492.6  532.35  5530.3  532.72
  5538.9  533.06  5769.4  536.85  5892.6  538.37  5930.3  538.51  5992.4  539.26
#Mann=3,-1,0
  4404.9    0.05       0  4991.0   0.035       0  4995.0    0.05       0
Bank Sta=4991,4995
Exp/Cntr=0.3,0.1

Type RM Length L Ch R = 1,1880,465,465,465
BEGIN DESCRIPTION:
Mapping XS caee1cec
END DESCRIPTION:
XS GIS Cut Line= 5
      2623508.17      7009384.22      2623181.77      7010248.85
      2623379.68      7010450.24      2623577.60      7010620.38
      2623928.27      7010651.63
#Sta/Elev= 30
  3788.4  528.32  3804.9  528.65  3810.2  528.32  3817.0  528.90  3835.0  528.33
  3840.4  528.85  3865.2  527.94  3956.0  526.89  4206.1  525.00  4469.0  523.65
  4693.5  522.91  4908.1  523.40  4962.6  522.88  4962.9  522.38  4966.4  522.38
  4966.6  522.88  4971.6  523.42  4978.8  523.54  5000.2  523.41  5014.5  524.41
  5021.1  523.70  5056.2  523.37  5070.5  523.94  5092.4  524.08  5205.4  524.23
  5314.4  525.28  5319.4  525.06  5374.8  525.64  5436.0  525.65  5608.0  528.59
#Mann=3,-1,0
  3788.4    0.05       0  4962.6   0.035       0  4966.6    0.05       0
Bank Sta=4962.6,4966.6
Exp/Cntr=0.3,0.1

Type RM Length L Ch R = 1,1415,0,0,0
BEGIN DESCRIPTION:
Hackberry Creek Tributary 3 4.0
END DESCRIPTION:
XS GIS Cut Line= 5
      2623476.90      7009311.36      2622917.91      7010431.68
      2622960.82      7010561.44      2623074.82      7010751.97
      2623852.72      7010761.66
#Sta/Elev= 30
  3611.3  528.89  3693.2  526.68  3754.8  526.99  3849.8  526.27  3856.8  526.29
  3866.6  527.02  3872.2  526.20  3879.1  526.82  3933.8  525.49  4169.7  523.54
  4476.3  522.22  4605.0  522.13  4744.8  521.21  4873.8  521.11  4874.0  520.61
  4877.5  520.61  4877.8  521.11  4915.3  521.62  4957.4  521.37  5104.4  521.93
  5156.5  521.52  5193.4  521.89  5243.2  521.55  5283.2  521.89  5313.2  522.67
  5323.2  522.34  5373.2  522.29  5743.3  524.33  5803.3  524.05  6000.0  526.53
#Mann=3,-1,0
  3611.3    0.05       0  4873.8   0.035       0  4877.8    0.05       0
Bank Sta=4873.8,4877.8
Exp/Cntr=0.3,0.1

Chan Stop Cuts=-1