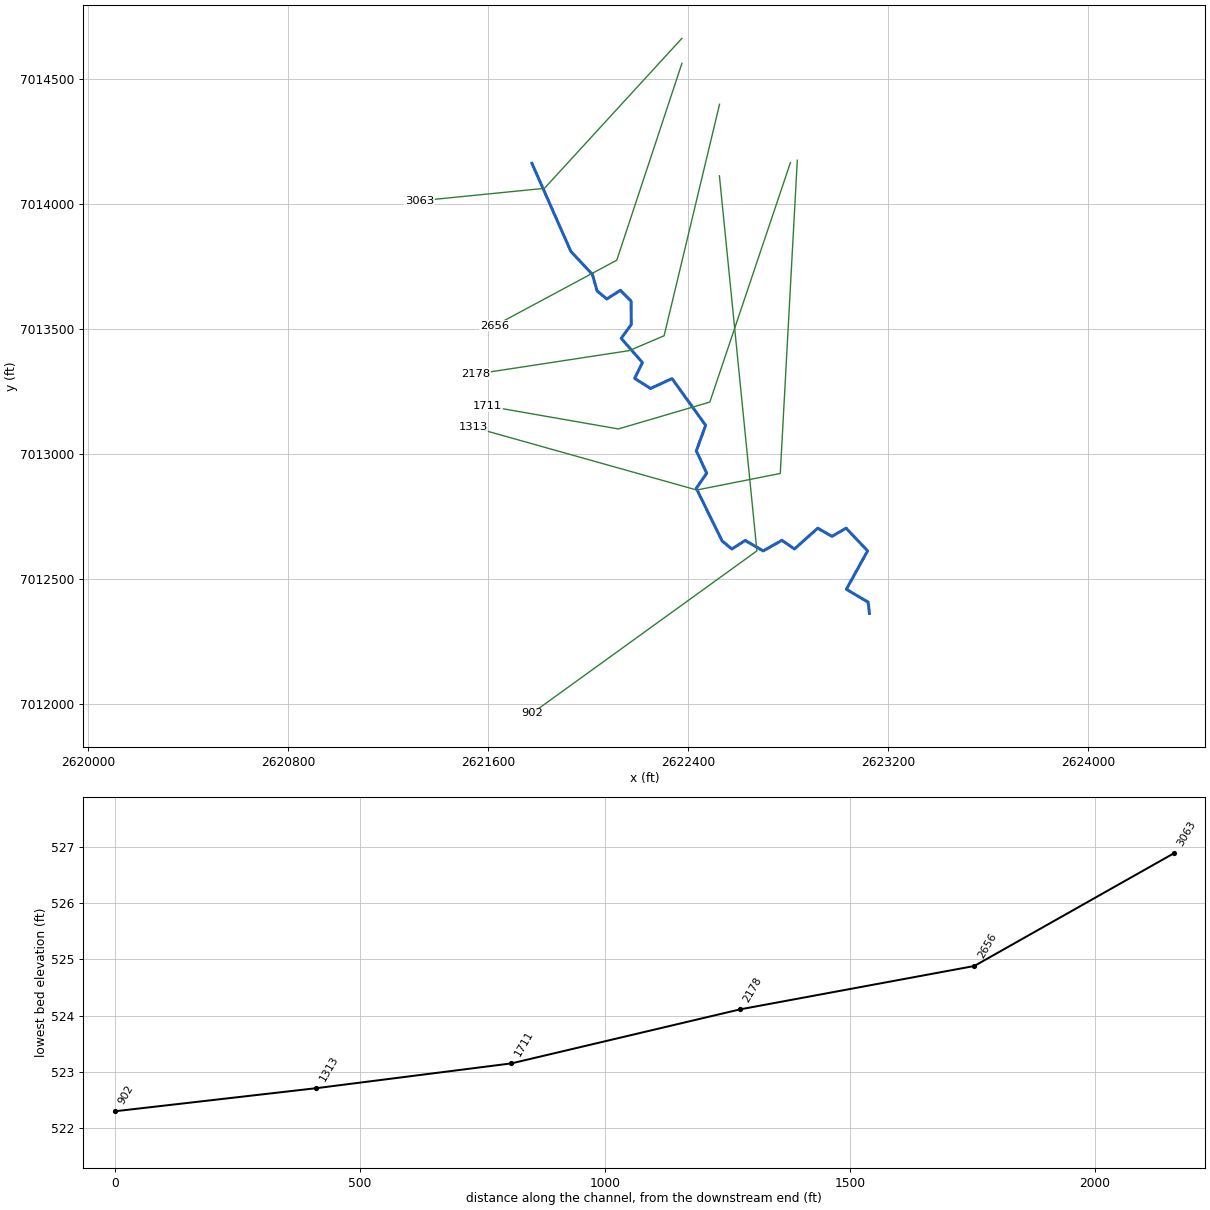
--- Hackberry Creek Tributary 4.prj (project) ---

Proj Title=Hackberry Creek Tributary 4 Base Level Engineering
Current Plan=p01
Default Exp/Contr=0.3,0.1
English Units
Geom File=g01
Flow File=f01
Plan File=p01
BEGIN DESCRIPTION:
Hackberry Creek Tributary 4
END DESCRIPTION:

--- Hackberry Creek Tributary 4.p01 (plan) ---

Plan Title=Multiple Run
Short Identifier=Multiple
Geom File=g01
Flow File=f01
Subcritical Flow
K Sum by GR= 0
Std Step Tol= 0.01
Critical Tol= 0.01
Num of Std Step Trials= 20
Max Error Tol= 0.3
Flow Tol Ratio= 0.001
Split Flow NTrial= 30
Split Flow Tol= 0.02
Split Flow Ratio= 0.02
Log Output Level= 0
Friction Slope Method= 1
Unsteady Friction Slope Method= 2
Unsteady Bridges Friction Slope Method= 1
Parabolic Critical Depth
Global Vel Dist=  1 , 1 , 1
Global Log Level= 0
CheckData=True
Encroach Param= -1, 0, 0, 0
BEGIN DESCRIPTION:
Multiple Run
END DESCRIPTION:

--- Hackberry Creek Tributary 4.f01 (steady flow) ---

Flow Title=Multiple
Number of Profiles=7
Profile Names=10-year,25-year,50-year,1pct_min,100-year,1pct_plu,500-year
River Rch & RM= Hackberry Creek ,Reach-1,3063
     420     550     653     385     767    1531    1059
River Rch & RM= Hackberry Creek ,Reach-1,902
     456     601     715     422     843    1681    1170
Boundary for River Rch & Prof#=Hackberry Creek ,Reach-1,1
Up Type=0
Dn Type=3
Dn Slope=0.005
Boundary for River Rch & Prof#=Hackberry Creek ,Reach-1,2
Up Type=0
Dn Type=3
Dn Slope=0.005
Boundary for River Rch & Prof#=Hackberry Creek ,Reach-1,3
Up Type=0
Dn Type=3
Dn Slope=0.005
Boundary for River Rch & Prof#=Hackberry Creek ,Reach-1,4
Up Type=0
Dn Type=3
Dn Slope=0.005
Boundary for River Rch & Prof#=Hackberry Creek ,Reach-1,5
Up Type=0
Dn Type=3
Dn Slope=0.005
Boundary for River Rch & Prof#=Hackberry Creek ,Reach-1,6
Up Type=0
Dn Type=3
Dn Slope=0.005
Boundary for River Rch & Prof#=Hackberry Creek ,Reach-1,7
Up Type=0
Dn Type=3
Dn Slope=0.005

--- Hackberry Creek Tributary 4.g01 (geometry) ---

Geom Title=Existing Conditions

River Reach=Hackberry Creek ,Reach-1
Reach XY= 30
      2621776.00      7014161.00      2621931.85      7013808.71
      2622017.82      7013717.00      2622036.78      7013650.61
      2622075.80      7013618.48      2622129.61      7013653.11
      2622172.54      7013609.97      2622173.63      7013516.90
      2622133.34      7013460.90      2622217.96      7013364.32
      2622187.11      7013300.57      2622250.82      7013260.60
      2622336.37      7013300.02      2622470.87      7013113.28
      2622433.62      7013011.00      2622475.02      7012921.64
      2622433.56      7012861.00      2622536.76      7012650.61
      2622575.78      7012618.46      2622629.22      7012652.67
      2622701.00      7012610.77      2622776.09      7012653.16
      2622826.00      7012618.57      2622919.33      7012701.68
      2622976.00      7012669.05      2623032.70      7012701.71
      2623118.71      7012611.11      2623033.65      7012457.36
      2623120.99      7012405.67      2623126.00      7012361.00

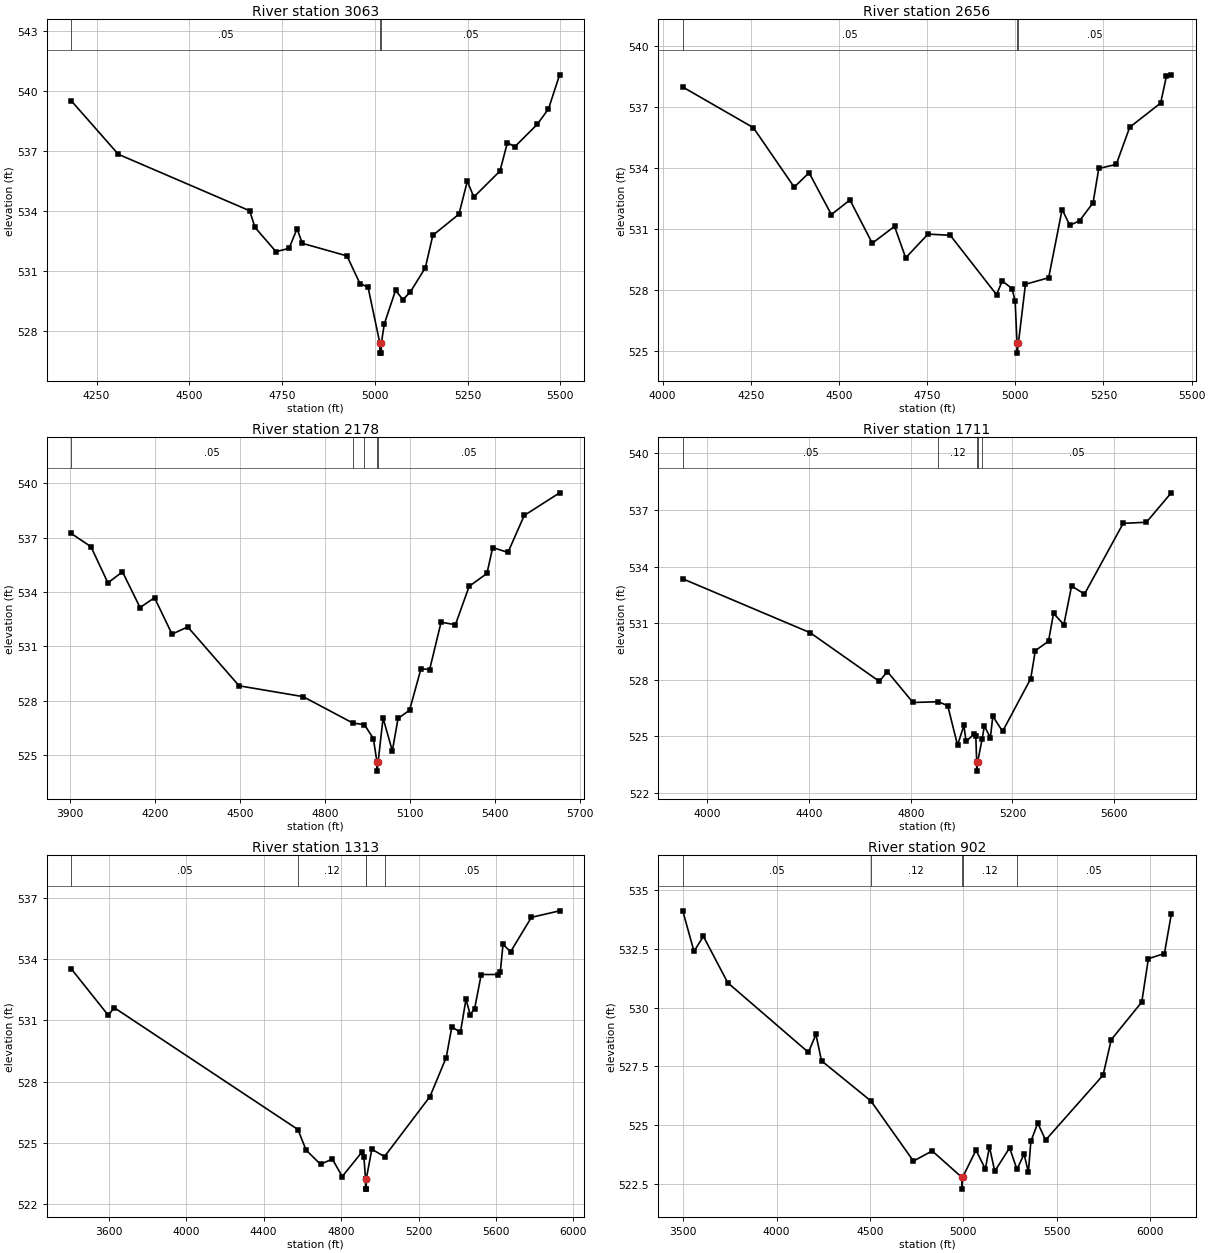
Type RM Length L Ch R = 1,3063,407,407,407
BEGIN DESCRIPTION:
Hackberry Creek Tributary 4 4.0
END DESCRIPTION:
XS GIS Cut Line= 3
      2622375.99      7014660.99      2621826.00      7014061.00
      2621326.03      7014011.00
#Sta/Elev= 30
  4181.4  539.53  4308.7  536.84  4662.7  534.01  4676.8  533.18  4733.6  531.96
  4768.7  532.13  4790.3  533.11  4804.5  532.38  4924.7  531.75  4959.9  530.36
  4981.5  530.19  5013.4  527.38  5013.7  526.88  5017.2  526.88  5017.4  527.38
  5025.5  528.35  5055.6  530.02  5075.7  529.56  5095.8  529.95  5136.0  531.16
  5156.1  532.78  5226.5  533.84  5249.1  535.49  5266.7  534.70  5337.0  536.00
  5357.1  537.42  5377.2  537.22  5437.5  538.34  5467.7  539.11  5497.8  540.82
#Mann=3,-1,0
  4181.4    0.05       0  5013.4    0.03       0  5017.4    0.05       0
Bank Sta=5013.4,5017.4
Exp/Cntr=0.3,0.1

Type RM Length L Ch R = 1,2656,478,478,478
BEGIN DESCRIPTION:
Hackberry Creek Tributary 4 3.0
END DESCRIPTION:
XS GIS Cut Line= 3
      2622376.00      7014561.01      2622115.53      7013773.66
      2621625.97      7013510.98
#Sta/Elev= 30
  4057.3  537.98  4257.4  535.98  4373.3  533.05  4415.4  533.76  4478.6  531.70
  4531.3  532.42  4594.5  530.29  4657.7  531.12  4689.3  529.57  4752.5  530.74
  4815.7  530.68  4946.8  527.76  4963.1  528.43  4990.7  528.06  4999.6  527.44
  5004.9  525.38  5005.2  524.88  5008.9  525.38  5028.8  528.27  5094.6  528.59
  5132.8  531.95  5154.7  531.17  5182.3  531.40  5220.5  532.28  5236.7  533.97
  5286.2  534.17  5324.4  536.00  5412.1  537.19  5428.4  538.51  5442.2  538.58
#Mann=3,-1,0
  4057.3    0.05       0  5004.9    0.03       0  5008.9    0.05       0
Bank Sta=5004.9,5008.9
Exp/Cntr=0.3,0.1

Type RM Length L Ch R = 1,2178,467,467,467
BEGIN DESCRIPTION:
Mapping XS 157ab2bc
END DESCRIPTION:
XS GIS Cut Line= 4
      2622526.54      7014397.30      2622304.76      7013471.35
      2622165.30      7013411.90      2621552.58      7013318.16
#Sta/Elev= 30
  3903.6  537.23  3973.6  536.50  4033.5  534.50  4084.9  535.11  4146.9  533.14
  4198.0  533.68  4259.7  531.67  4315.0  532.07  4496.2  528.82  4722.4  528.22
  4896.9  526.77  4938.7  526.67  4970.0  525.91  4982.8  524.61  4983.1  524.11
  4986.8  524.61  5004.3  527.04  5037.0  525.23  5057.2  527.02  5097.7  527.47
  5138.2  529.77  5168.5  529.71  5209.0  532.33  5259.5  532.19  5308.0  534.31
  5370.8  535.02  5391.1  536.45  5444.9  536.18  5502.3  538.22  5627.2  539.47
#Mann=5,-1,0
  3903.6    0.05       0  4896.9    0.12       0  4938.7    0.05       0
  4982.8    0.03       0  4986.8    0.05       0
Bank Sta=4982.8,4986.8
Exp/Cntr=0.3,0.1

Type RM Length L Ch R = 1,1711,398,398,398
BEGIN DESCRIPTION:
Mapping XS e751af9c
END DESCRIPTION:
XS GIS Cut Line= 4
      2622810.04      7014164.07      2622487.67      7013206.13
      2622121.85      7013098.67      2621599.67      7013189.88
#Sta/Elev= 30
  3902.9  533.35  4404.4  530.49  4676.4  527.91  4708.0  528.43  4808.7  526.79
  4908.5  526.83  4945.5  526.62  4984.1  524.53  5009.2  525.57  5017.5  524.73
  5050.8  525.13  5056.0  525.00  5059.3  523.65  5059.5  523.15  5063.3  523.65
  5080.9  524.85  5089.4  525.54  5113.4  524.93  5122.8  526.06  5161.4  525.26
  5271.9  528.05  5290.1  529.54  5342.0  530.04  5361.8  531.52  5402.4  530.92
  5432.8  532.97  5483.6  532.54  5635.8  536.29  5727.2  536.35  5825.0  537.91
#Mann=5,-1,0
  3902.9    0.05       0  4908.5    0.12       0  5059.3    0.07       0
  5063.3    0.12       0  5080.9    0.05       0
Bank Sta=5059.3,5063.3
Exp/Cntr=0.3,0.1

Type RM Length L Ch R = 1,1313,411,411,411
BEGIN DESCRIPTION:
Hackberry Creek Tributary 4 2.0
END DESCRIPTION:
XS GIS Cut Line= 4
      2622837.49      7014173.25      2622769.39      7012920.67
      2622435.43      7012854.39      2621541.13      7013105.52
#Sta/Elev= 30
  3405.1  533.55  3597.6  531.25  3627.7  531.63  4576.9  525.64  4619.1  524.63
  4693.6  523.93  4754.7  524.19  4805.7  523.33  4907.7  524.53  4917.9  524.28
  4926.1  523.21  4926.3  522.71  4929.8  522.71  4930.1  523.21  4958.6  524.67
  5024.3  524.31  5259.1  527.26  5343.1  529.18  5372.0  530.68  5416.5  530.42
  5445.3  532.05  5466.8  531.29  5489.8  531.58  5523.9  533.26  5612.2  533.26
  5622.6  533.40  5636.5  534.74  5675.7  534.38  5783.2  536.07  5928.9  536.39
#Mann=5,-1,0
  3405.1    0.05       0  4576.9    0.12       0  4926.1    0.07       0
  4930.1    0.12       0  5024.3    0.05       0
Bank Sta=4926.1,4930.1
Exp/Cntr=0.3,0.1

Type RM Length L Ch R = 1,902,0,0,0
BEGIN DESCRIPTION:
Hackberry Creek Tributary 4 1.0
END DESCRIPTION:
XS GIS Cut Line= 3
      2622526.00      7014110.96      2622676.00      7012611.00
      2621776.02      7011961.01
#Sta/Elev= 30
  3497.3  534.10  3557.6  532.38  3607.8  533.02  3738.5  531.05  4170.6  528.10
  4210.8  528.86  4241.0  527.74  4505.3  526.04  4733.4  523.49  4833.9  523.92
  4992.7  522.80  4992.9  522.30  4996.7  522.80  5068.6  523.95  5118.8  523.15
  5140.4  524.10  5169.1  523.06  5248.8  524.05  5287.9  523.14  5326.2  523.78
  5349.4  523.02  5362.5  524.32  5399.5  525.10  5441.5  524.38  5749.4  527.13
  5793.5  528.64  5956.7  530.23  5992.3  532.07  6078.2  532.29  6114.9  533.95
#Mann=5,-1,0
  3497.3    0.05       0  4505.3    0.12       0  4992.7    0.07       0
  4996.7    0.12       0  5287.9    0.05       0
Bank Sta=4992.7,4996.7
Exp/Cntr=0.3,0.1

Chan Stop Cuts=-1