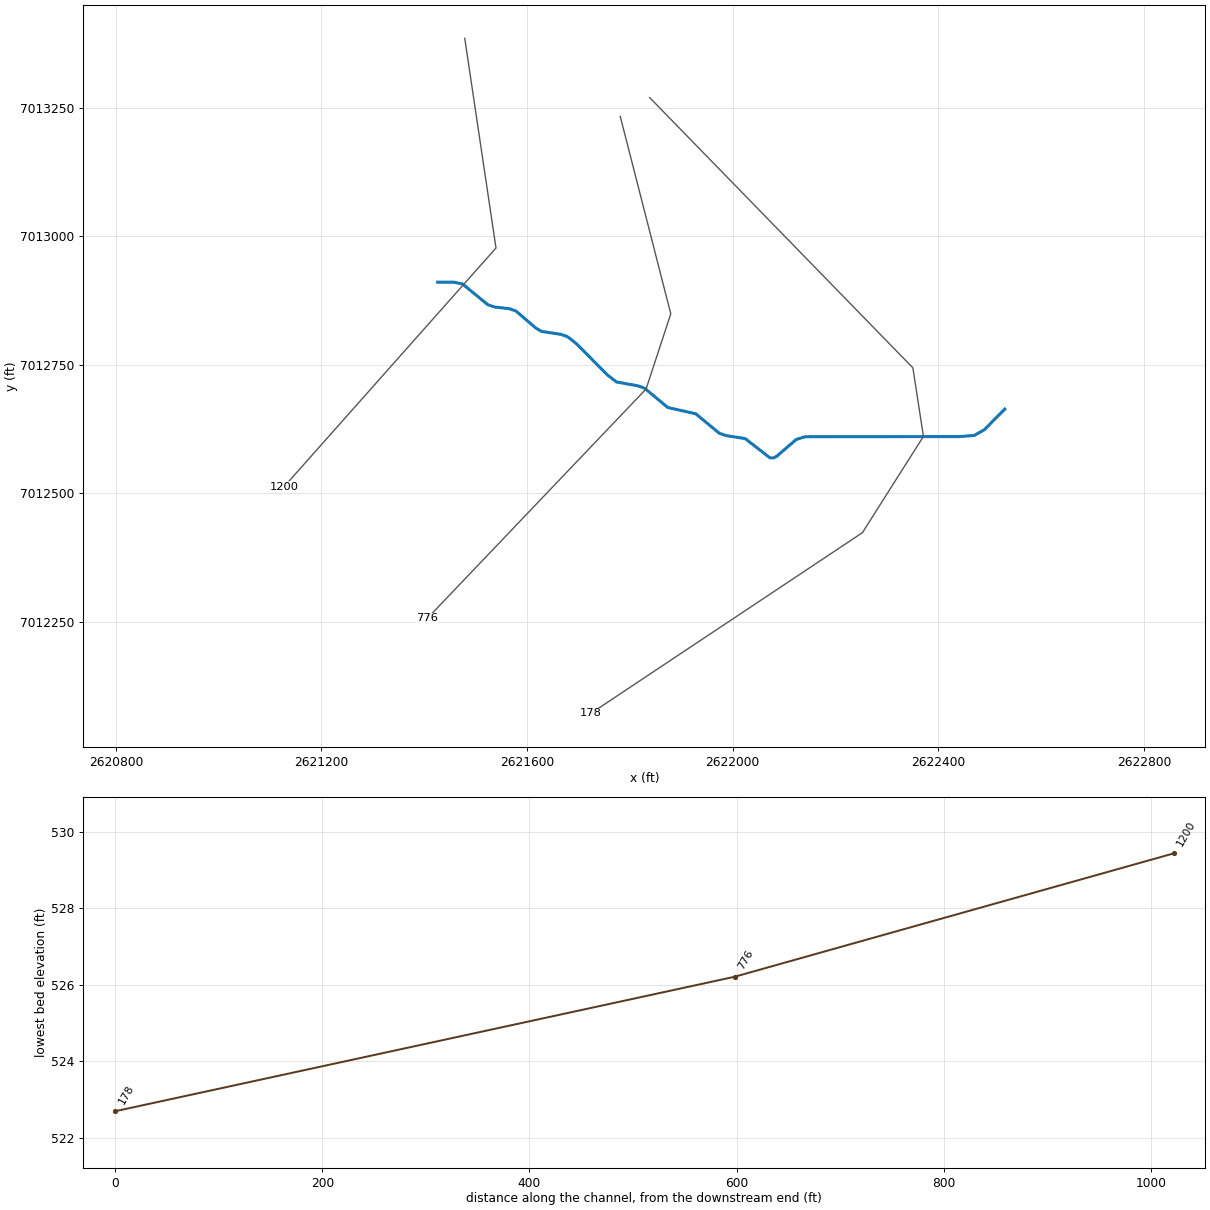
--- Hackberry Creek Tributary 4_1.prj (project) ---

Proj Title=Hackberry Creek Tributary 4_1 Base Level Engineering
Current Plan=p01
Default Exp/Contr=0.3,0.1
English Units
Geom File=g01
Flow File=f01
Plan File=p01
BEGIN DESCRIPTION:
Hackberry Creek Tributary 4_1
END DESCRIPTION:

--- Hackberry Creek Tributary 4_1.p01 (plan) ---

Plan Title=Multiple Run
Short Identifier=Multiple
Geom File=g01
Flow File=f01
Subcritical Flow
K Sum by GR= 0
Std Step Tol= 0.01
Critical Tol= 0.01
Num of Std Step Trials= 20
Max Error Tol= 0.3
Flow Tol Ratio= 0.001
Split Flow NTrial= 30
Split Flow Tol= 0.02
Split Flow Ratio= 0.02
Log Output Level= 0
Friction Slope Method= 1
Unsteady Friction Slope Method= 2
Unsteady Bridges Friction Slope Method= 1
Parabolic Critical Depth
Global Vel Dist=  1 , 1 , 1
Global Log Level= 0
CheckData=True
Encroach Param= -1, 0, 0, 0
BEGIN DESCRIPTION:
Multiple Run
END DESCRIPTION:

--- Hackberry Creek Tributary 4_1.f01 (steady flow) ---

Flow Title=Multiple
Number of Profiles=7
Profile Names=10-year,25-year,50-year,1pct_min,100-year,1pct_plu,500-year
River Rch & RM= Hackberry Creek ,Reach-1,1200
     165     203     231     131     262     522     334
Boundary for River Rch & Prof#=Hackberry Creek ,Reach-1,1
Up Type=0
Dn Type=3
Dn Slope=0.005
Boundary for River Rch & Prof#=Hackberry Creek ,Reach-1,2
Up Type=0
Dn Type=3
Dn Slope=0.005
Boundary for River Rch & Prof#=Hackberry Creek ,Reach-1,3
Up Type=0
Dn Type=3
Dn Slope=0.005
Boundary for River Rch & Prof#=Hackberry Creek ,Reach-1,4
Up Type=0
Dn Type=3
Dn Slope=0.005
Boundary for River Rch & Prof#=Hackberry Creek ,Reach-1,5
Up Type=0
Dn Type=3
Dn Slope=0.005
Boundary for River Rch & Prof#=Hackberry Creek ,Reach-1,6
Up Type=0
Dn Type=3
Dn Slope=0.005
Boundary for River Rch & Prof#=Hackberry Creek ,Reach-1,7
Up Type=0
Dn Type=3
Dn Slope=0.005

--- Hackberry Creek Tributary 4_1.g01 (geometry) ---

Geom Title=Existing Conditions

River Reach=Hackberry Creek ,Reach-1
Reach XY= 30
      2621426.00      7012911.00      2621457.81      7012910.90
      2621474.51      7012907.40      2621523.75      7012866.95
      2621536.67      7012862.62      2621565.32      7012859.37
      2621578.20      7012854.93      2621616.45      7012822.10
      2621627.73      7012815.19      2621665.37      7012809.49
      2621678.29      7012805.15      2621696.07      7012791.18
      2621755.93      7012730.82      2621773.71      7012716.85
      2621815.30      7012709.30      2621828.19      7012704.90
      2621873.80      7012667.08      2621928.20      7012654.92
      2621973.81      7012617.05      2621986.70      7012612.60
      2622024.36      7012606.57      2622072.68      7012569.04
      2622079.29      7012569.06      2622085.90      7012572.46
      2622123.55      7012604.98      2622141.16      7012610.34
      2622441.17      7012610.59      2622470.22      7012612.89
      2622489.51      7012623.92      2622529.32      7012664.10

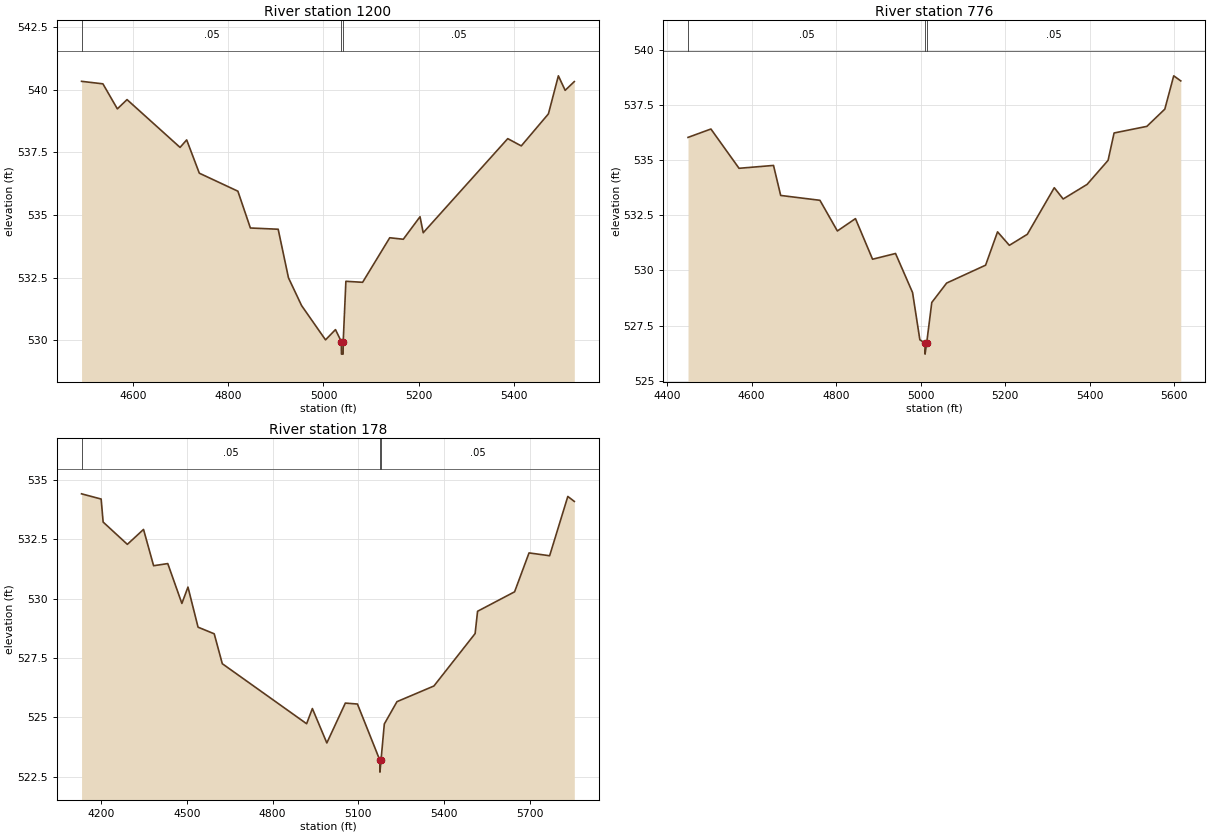
Type RM Length L Ch R = 1,1200,424,424,424
BEGIN DESCRIPTION:
Mapping XS 0013d0d2
END DESCRIPTION:
XS GIS Cut Line= 3
      2621478.71      7013385.32      2621539.47      7012977.38
      2621127.13      7012512.95
#Sta/Elev= 30
  4492.6  540.34  4537.4  540.24  4567.7  539.24  4588.0  539.61  4699.2  537.70
  4713.1  538.00  4739.6  536.67  4820.5  535.95  4846.7  534.48  4905.0  534.43
  4926.6  532.49  4954.1  531.38  5004.3  530.01  5025.2  530.42  5037.4  529.94
  5037.7  529.44  5041.2  529.44  5041.4  529.94  5047.0  532.35  5082.1  532.31
  5139.0  534.09  5167.4  534.03  5202.5  534.93  5209.2  534.29  5386.5  538.05
  5414.9  537.76  5471.8  539.04  5492.7  540.56  5506.9  539.98  5526.1  540.33
#Mann=3,-1,0
  4492.6    0.05       0  5037.4    0.03       0  5041.4    0.05       0
Bank Sta=5037.4,5041.4
Exp/Cntr=0.3,0.1

Type RM Length L Ch R = 1,776,598,598,598
BEGIN DESCRIPTION:
Mapping XS f56a77c0
END DESCRIPTION:
XS GIS Cut Line= 4
      2621781.20      7013233.52      2621879.50      7012849.45
      2621831.48      7012703.12      2621406.21      7012257.27
#Sta/Elev= 30
  4449.3  536.03  4503.5  536.41  4570.1  534.63  4651.7  534.76  4668.7  533.40
  4761.6  533.18  4802.9  531.79  4845.7  532.35  4886.2  530.51  4940.6  530.77
  4980.9  529.00  4998.2  526.86  5010.3  526.71  5010.5  526.21  5014.3  526.71
  5026.4  528.55  5061.6  529.43  5153.8  530.24  5182.1  531.75  5210.1  531.14
  5252.6  531.64  5316.4  533.75  5337.5  533.24  5394.1  533.90  5443.8  534.99
  5458.0  536.23  5535.6  536.53  5578.1  537.31  5599.2  538.82  5615.9  538.59
#Mann=3,-1,0
  4449.3    0.05       0  5010.3    0.05       0  5014.3    0.05       0
Bank Sta=5010.3,5014.3
Exp/Cntr=0.3,0.1

Type RM Length L Ch R = 1,178,0,0,0
BEGIN DESCRIPTION:
Hackberry Creek Tributary 4_1 1.0
END DESCRIPTION:
XS GIS Cut Line= 5
      2621838.31      7013270.18      2622350.49      7012744.28
      2622371.02      7012610.95      2622252.32      7012423.62
      2621724.05      7012072.10
#Sta/Elev= 30
  4131.0  534.42  4199.6  534.20  4206.6  533.23  4291.4  532.29  4348.0  532.92
  4383.3  531.39  4432.9  531.48  4482.3  529.80  4503.6  530.49  4538.9  528.80
  4595.5  528.52  4623.8  527.26  4919.0  524.73  4939.2  525.37  4989.8  523.92
  5054.6  525.60  5097.0  525.56  5175.5  523.19  5175.8  522.69  5179.5  523.19
  5191.1  524.72  5235.4  525.66  5364.7  526.32  5509.0  528.53  5517.6  529.47
  5647.2  530.29  5697.8  531.93  5769.9  531.81  5833.6  534.31  5856.3  534.10
#Mann=3,-1,0
  4131.0    0.05       0  5175.5    0.03       0  5179.5    0.05       0
Bank Sta=5175.5,5179.5
Exp/Cntr=0.3,0.1

Chan Stop Cuts=-1