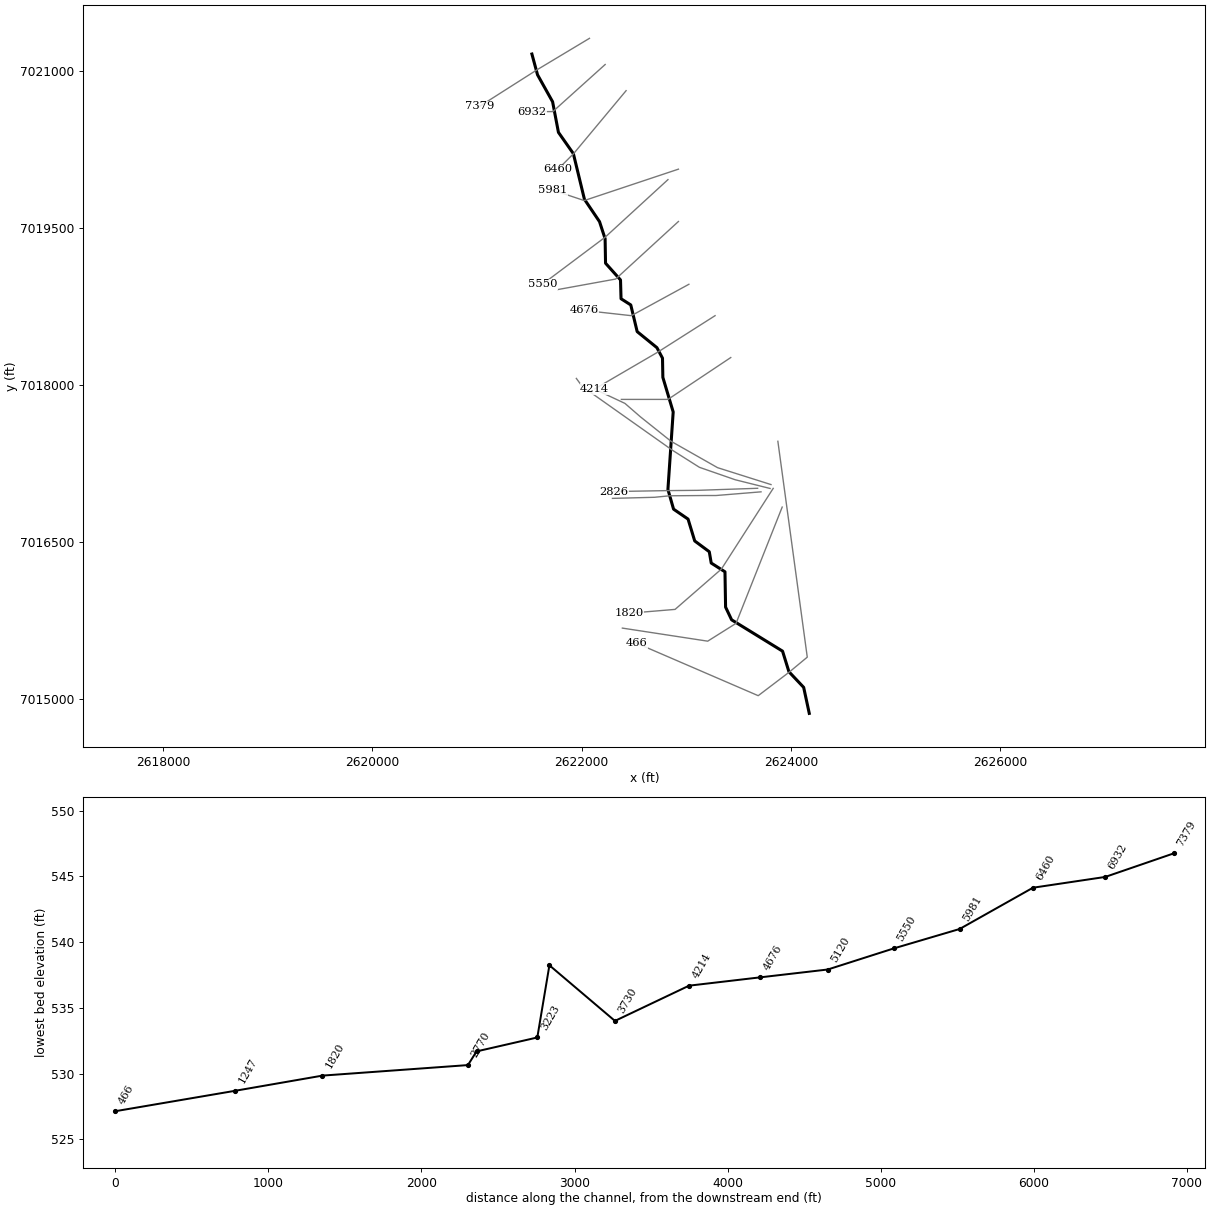
--- Hackberry Creek Tributary 5.prj (project) ---

Proj Title=Hackberry Creek Tributary 5 Base Level Engineering
Current Plan=p01
Default Exp/Contr=0.3,0.1
English Units
Geom File=g01
Flow File=f01
Plan File=p01
Y Axis Title=Elevation
X Axis Title(PF)=Main Channel Distance
X Axis Title(XS)=Station
BEGIN DESCRIPTION:
Hackberry Creek Tributary 5
END DESCRIPTION:
DSS Export Rating Curves= 0
DSS Export Rating Curve Sorted= 0
DSS Export Volume Flow Curves= 0
DXF OffsetX= 0
DXF OffsetY= 0
DXF ScaleX= 1
DXF ScaleY= 10

--- Hackberry Creek Tributary 5.p01 (plan) ---

Plan Title=Multiple Run
Short Identifier=Multiple
Geom File=g01
Flow File=f01
Subcritical Flow
K Sum by GR= 0
Std Step Tol= 0.01
Critical Tol= 0.01
Num of Std Step Trials= 20
Max Error Tol= 0.3
Flow Tol Ratio= 0.001
Split Flow NTrial= 30
Split Flow Tol= 0.02
Split Flow Ratio= 0.02
Log Output Level= 0
Friction Slope Method= 1
Unsteady Friction Slope Method= 2
Unsteady Bridges Friction Slope Method= 1
Parabolic Critical Depth
Global Vel Dist=  1 , 1 , 1
Global Log Level= 0
CheckData=True
Encroach Param= -1, 0, 0, 0
BEGIN DESCRIPTION:
Multiple Run
END DESCRIPTION:

--- Hackberry Creek Tributary 5.f01 (steady flow) ---

Flow Title=Multiple
Number of Profiles=7
Profile Names=10-year,25-year,50-year,1pct_min,100-year,1pct_plu,500-year
River Rch & RM= Hackberry Creek ,Reach-1,7379
     463     612     731     434     865    1726    1209
River Rch & RM= Hackberry Creek ,Reach-1,6460
     651     876    1059     635    1266    2527    1810
River Rch & RM= Hackberry Creek ,Reach-1,2826
     663     890    1074     642    1282    2557    1824
Boundary for River Rch & Prof#=Hackberry Creek ,Reach-1,1
Up Type=0
Dn Type=3
Dn Slope=0.005
Boundary for River Rch & Prof#=Hackberry Creek ,Reach-1,2
Up Type=0
Dn Type=3
Dn Slope=0.005
Boundary for River Rch & Prof#=Hackberry Creek ,Reach-1,3
Up Type=0
Dn Type=3
Dn Slope=0.005
Boundary for River Rch & Prof#=Hackberry Creek ,Reach-1,4
Up Type=0
Dn Type=3
Dn Slope=0.005
Boundary for River Rch & Prof#=Hackberry Creek ,Reach-1,5
Up Type=0
Dn Type=3
Dn Slope=0.005
Boundary for River Rch & Prof#=Hackberry Creek ,Reach-1,6
Up Type=0
Dn Type=3
Dn Slope=0.005
Boundary for River Rch & Prof#=Hackberry Creek ,Reach-1,7
Up Type=0
Dn Type=3
Dn Slope=0.005

--- Hackberry Creek Tributary 5.g01 (geometry) ---

Geom Title=Existing Conditions
Program Version=4.10

River Reach=Hackberry Creek ,Reach-1
Reach XY= 30
        2621526.        7021161.      2621579.82      7020962.58
      2621723.75      7020705.07      2621779.62       7020412.5
      2621922.17      7020209.42      2622027.93      7019772.95
      2622172.17      7019559.42      2622225.48      7019395.78
      2622229.55      7019162.47       2622372.6      7019002.56
      2622377.65      7018822.84       2622470.6      7018763.68
      2622531.83       7018508.7      2622720.41      7018355.39
      2622773.77       7018255.1      2622777.22      7018071.51
      2622875.93      7017740.97      2622825.55      7017000.81
      2622879.52      7016812.28      2623017.98      7016717.34
      2623081.52      7016508.56      2623220.74      7016405.52
      2623239.28      7016297.38      2623370.64       7016213.7
      2623376.51      7015876.21      2623434.13      7015754.92
      2623920.75      7015455.56      2623981.83       7015258.7
      2624122.46      7015109.53        2624176.        7014861.

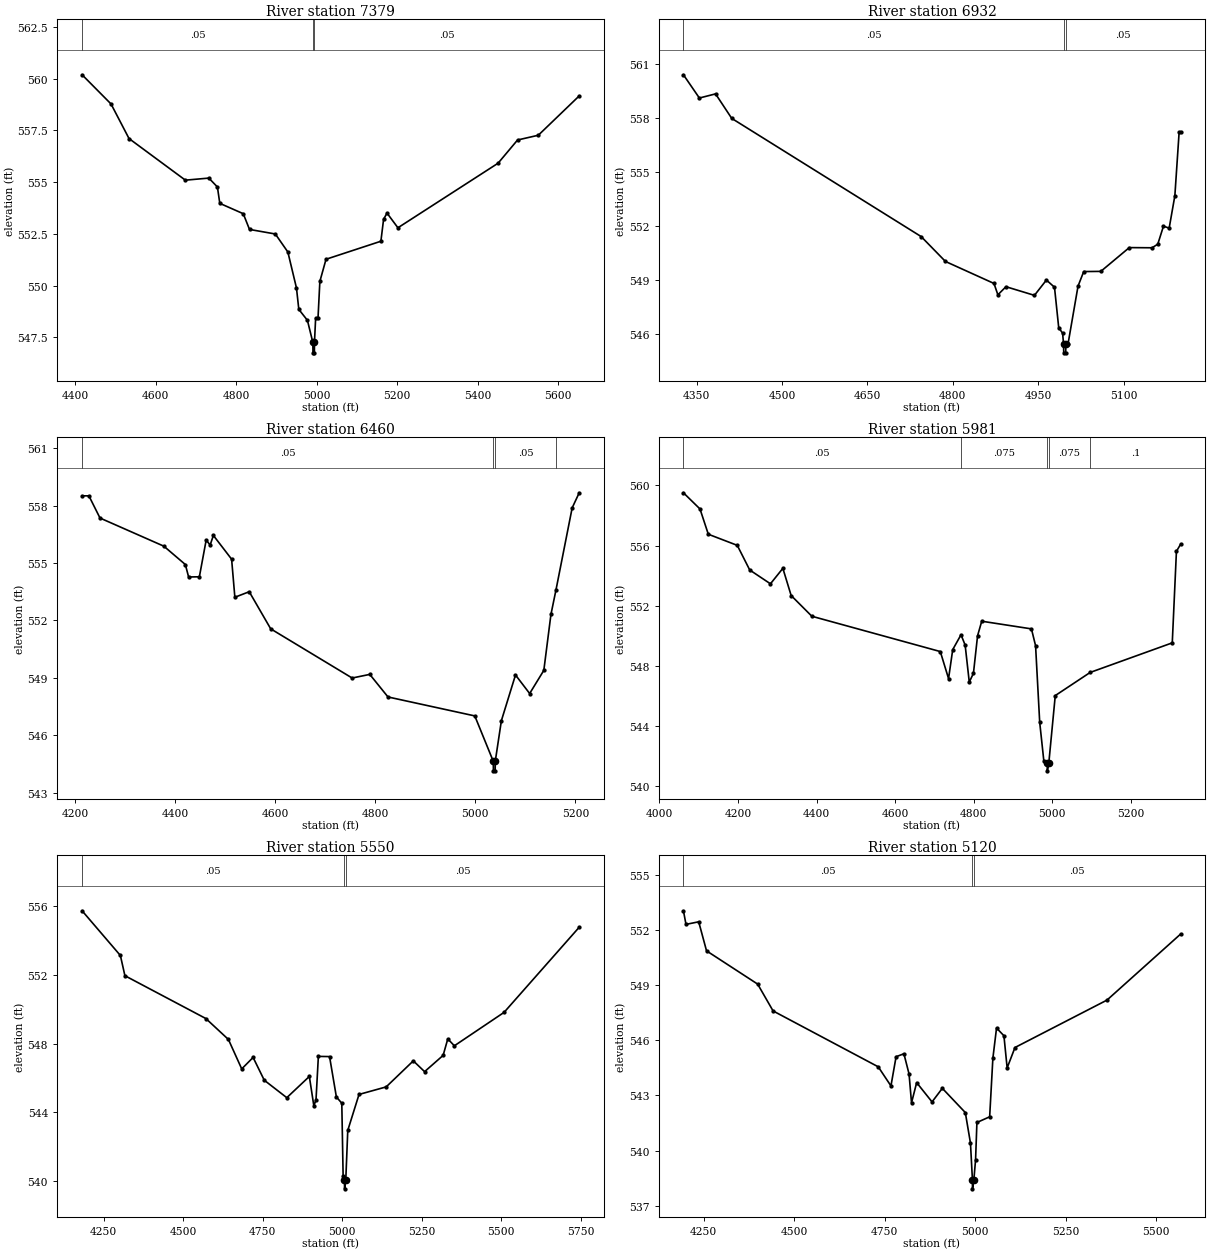
Type RM Length L Ch R = 1 ,7379    ,447,447,447
BEGIN DESCRIPTION:
Hackberry Creek Tributary 5 13.0
END DESCRIPTION:
XS GIS Cut Line= 3
        2622076.        7021311.        2621576.        7021011.
      2621026.01      7020661.01
#Sta/Elev= 30
  4416.9  560.18  4488.8  558.77  4533.5   557.1  4673.5  555.09  4731.8  555.19
  4753.1  554.76    4759  553.97  4817.3  553.47  4832.8  552.71    4897  552.49
  4928.1  551.62  4949.5  549.88  4955.3  548.85  4976.7  548.32  4990.2  547.25
  4990.5  546.75    4994  546.75  4994.2  547.25  4997.1  548.43    5003  548.43
  5007.6   550.2  5022.9  551.27  5159.2  552.14  5165.9   553.2  5174.4   553.5
  5201.5  552.79  5450.4  555.91  5498.7  557.03  5550.3  557.26  5651.9  559.16
#Mann= 3 ,-1 , 0
  4416.9     .05       0  4990.2     .03       0  4994.2     .05       0
Bank Sta=4990.2,4994.2
XS Rating Curve= 0 ,0
Exp/Cntr=0.3,0.1

Type RM Length L Ch R = 1 ,6932    ,472,472,472
BEGIN DESCRIPTION:
Hackberry Creek Tributary 5 12.0
END DESCRIPTION:
XS GIS Cut Line= 3
      2622225.99      7021060.99        2621726.        7020611.
      2621525.97        7020611.
#Sta/Elev= 30
    4327  560.39    4355   559.1  4383.4  559.33  4411.8  557.97  4744.4  551.41
    4787  550.03  4872.2  548.81    4879  548.18  4893.2  548.63  4943.2  548.15
  4964.2     549  4978.4   548.6  4985.8  546.36  4992.6  546.05  4994.3  545.46
  4994.6  544.96  4998.1  544.96  4998.3  545.46  5002.2  545.46  5019.7  548.66
  5029.7  549.47  5059.7  549.48  5109.7   550.8  5149.7  550.79  5159.7  550.99
  5169.7  551.99  5179.7  551.88  5189.7  553.68  5197.2  557.21  5199.7  557.21
#Mann= 3 ,-1 , 0
    4327     .05       0  4994.3     .03       0  4998.3     .05       0
Bank Sta=4994.3,4998.3
XS Rating Curve= 0 ,0
Exp/Cntr=0.3,0.1

Type RM Length L Ch R = 1 ,6460    ,479,479,479
BEGIN DESCRIPTION:
Hackberry Creek Tributary 5 11.0
END DESCRIPTION:
XS GIS Cut Line= 3
      2622425.98      7020810.98        2621926.        7020211.
      2621776.02      7020061.02
#Sta/Elev= 30
  4214.4  558.51    4228  558.51  4250.2  557.35  4377.7  555.88  4420.7  554.92
  4427.2  554.27  4448.7  554.28  4462.3   556.2  4470.2  555.94  4476.7  556.44
  4513.1   555.2  4519.6  553.21  4548.3   553.5  4591.2  551.56  4753.9  548.99
  4789.1  549.18  4825.5     548  4998.9  547.01  5035.8  544.64  5036.1  544.14
  5039.6  544.14  5039.8  544.64    5052  546.76  5080.2  549.15  5108.5  548.18
  5136.8  549.39    5151  552.31  5161.2  553.61  5193.4  557.88  5207.5  558.67
#Mann= 4 ,-1 , 0
  4214.4     .05       0  5035.8     .03       0  5039.8     .05       0
  5161.2      .1       0
Bank Sta=5035.8,5039.8
XS Rating Curve= 0 ,0
Exp/Cntr=0.3,0.1

Type RM Length L Ch R = 1 ,5981    ,431,431,431
BEGIN DESCRIPTION:
Hackberry Creek Tributary 5 10.0
END DESCRIPTION:
XS GIS Cut Line= 3
      2622926.01        7020061.        2622026.        7019761.
      2621726.02      7019860.99
#Sta/Elev= 30
  4061.3  559.51  4103.5  558.43  4124.6  556.75  4198.3  556.01    4230  554.37
  4282.7  553.45  4314.3  554.48  4335.4  552.67  4388.1  551.29  4714.9  548.94
  4735.9  547.14  4746.5  549.07  4767.6  550.06  4778.1  549.37  4788.6  546.91
  4799.2  547.49  4809.7  549.99  4820.3  550.96  4946.8  550.45  4957.3  549.33
  4967.8  544.23  4978.4  541.64  4986.9   541.5  4987.2     541  4990.9   541.5
  5007.4  546.01  5096.2  547.55  5305.1  549.52  5315.7  555.61  5326.2  556.08
#Mann= 5 ,-1 , 0
  4061.3     .05       0  4767.6    .075       0  4986.9     .07       0
  4990.9    .075       0  5096.2      .1       0
Bank Sta=4986.9,4990.9
XS Rating Curve= 0 ,0
Exp/Cntr=0.3,0.1

Type RM Length L Ch R = 1 ,5550    ,430,430,430
BEGIN DESCRIPTION:
Hackberry Creek Tributary 5 9.0
END DESCRIPTION:
XS GIS Cut Line= 3
      2622825.98      7019960.98        2622226.        7019411.
      2621626.01      7018961.01
#Sta/Elev= 30
  4181.8  555.75  4302.3  553.14  4316.5  551.96  4571.2  549.46  4642.1  548.24
    4684  546.52  4719.8  547.19  4754.9  545.86  4825.8  544.84  4896.7  546.08
  4910.9  544.36  4917.7  544.72  4925.1  547.25  4960.3  547.24  4981.8  544.88
  4998.8  544.52    5003  540.26  5007.3  540.02  5007.5  539.52  5011.3  540.02
  5017.6  542.93    5053  545.03  5138.4  545.47  5223.8  546.99  5259.3  546.36
  5317.6  547.31  5332.2  548.27    5353  547.87  5509.3  549.82  5745.7  554.79
#Mann= 3 ,-1 , 0
  4181.8     .05       0  5007.3     .03       0  5011.3     .05       0
Bank Sta=5007.3,5011.3
XS Rating Curve= 0 ,0
Exp/Cntr=0.3,0.1

Type RM Length L Ch R = 1 ,5120    ,444,444,444
BEGIN DESCRIPTION:
Hackberry Creek Tributary 5 8.0
END DESCRIPTION:
XS GIS Cut Line= 3
      2622925.99      7019560.99        2622326.        7019011.
      2621776.05      7018911.01
#Sta/Elev= 30
  4194.5  553.05  4201.6  552.31  4236.7  552.45  4258.3  550.87  4399.5  549.06
  4442.1   547.6  4732.5  544.56  4767.6  543.52  4781.8  545.11  4803.4  545.27
  4817.6  544.17  4824.4   542.6  4838.6   543.7  4881.1  542.65  4909.5  543.39
    4973  542.07  4987.2  540.41  4992.6  538.42  4992.8  537.92  4996.6  538.42
  5001.3   539.5    5005  541.53  5040.2  541.84  5049.1  545.03  5059.2  546.67
  5079.6  546.25  5088.5   544.5  5110.1  545.61  5364.2  548.19  5567.4  551.78
#Mann= 3 ,-1 , 0
  4194.5     .05       0  4992.6     .03       0  4996.6     .05       0
Bank Sta=4992.6,4996.6
XS Rating Curve= 0 ,0
Exp/Cntr=0.3,0.1

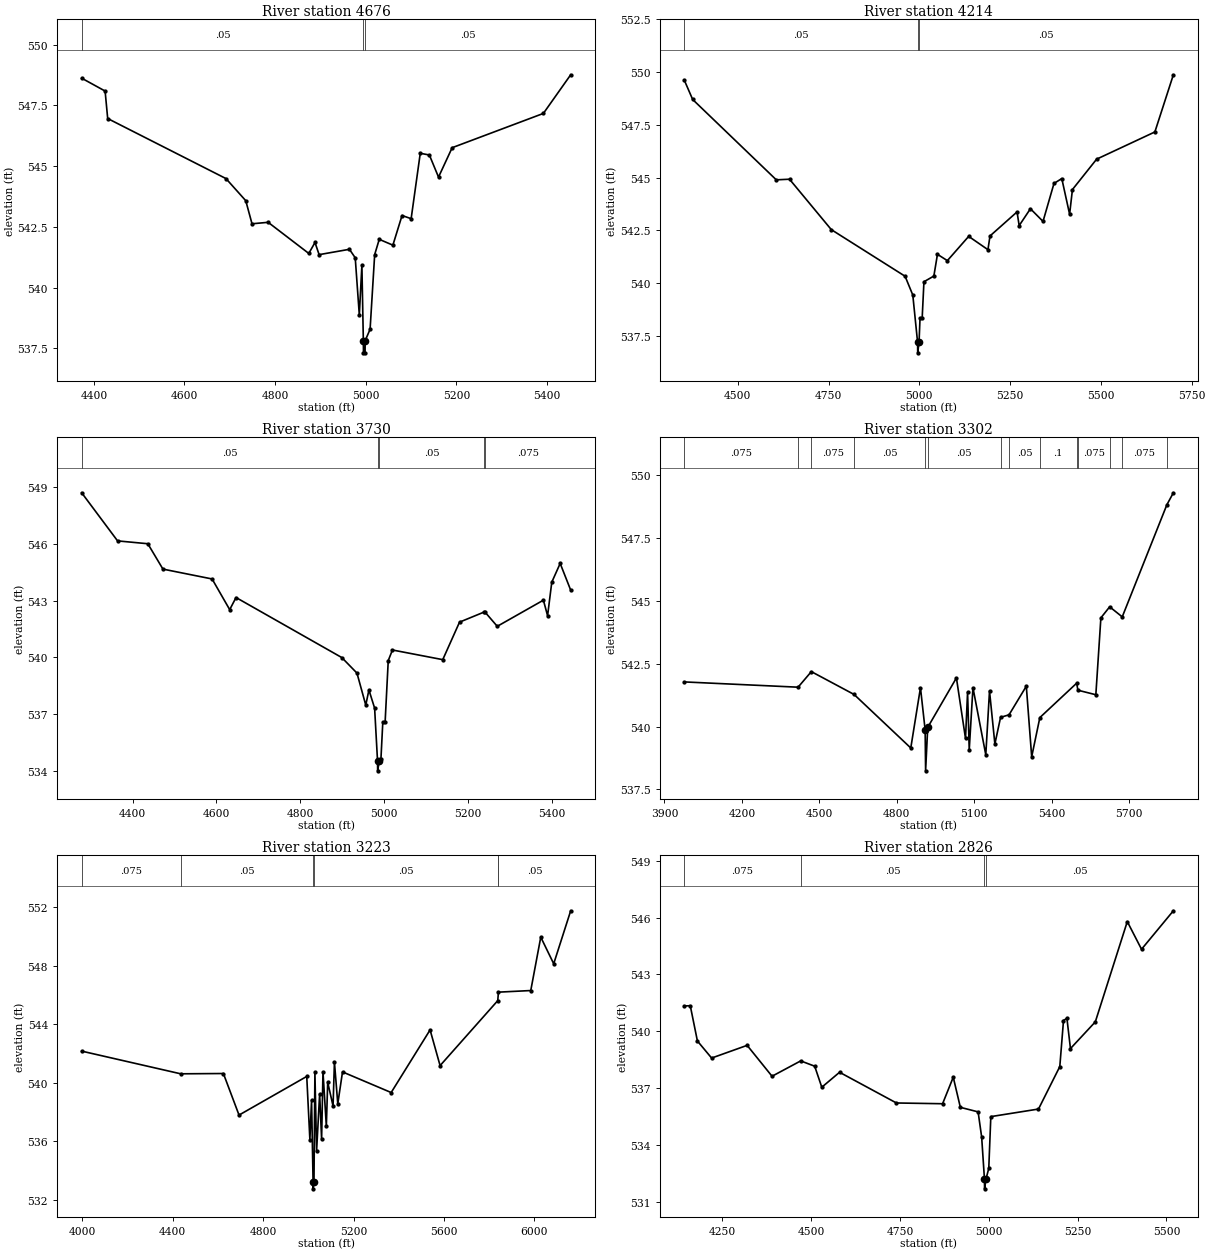
Type RM Length L Ch R = 1 ,4676    ,462,462,462
BEGIN DESCRIPTION:
Hackberry Creek Tributary 5 7.0
END DESCRIPTION:
XS GIS Cut Line= 3
      2623025.97      7018960.99        2622476.        7018661.
      2622026.04        7018711.
#Sta/Elev= 30
  4373.2  548.62  4424.9  548.09  4430.6  546.96  4691.6  544.49  4735.3  543.58
  4749.1  542.63  4784.7  542.69  4874.4  541.41  4888.1  541.86  4897.2  541.36
  4964.1  541.58  4976.9  541.23  4985.9  538.88  4991.6  540.92  4994.8  537.82
  4995.1  537.32  4998.6  537.32  4998.8  537.82  5009.7  538.29  5019.8  541.36
  5029.9  541.99    5060  541.75  5080.2  542.97  5100.3  542.84  5120.4  545.53
  5140.5  545.46  5160.7  544.55  5190.8  545.76  5392.1  547.17  5452.4  548.76
#Mann= 3 ,-1 , 0
  4373.2     .05       0  4994.8     .03       0  4998.8     .05       0
Bank Sta=4994.8,4998.8
XS Rating Curve= 0 ,0
Exp/Cntr=0.3,0.1

Type RM Length L Ch R = 1 ,4214    ,484,484,484
BEGIN DESCRIPTION:
Hackberry Creek Tributary 5 6.0
END DESCRIPTION:
XS GIS Cut Line= 3
      2623276.03      7018661.02        2622726.        7018311.
      2622125.99      7017960.99
#Sta/Elev= 30
    4353  549.61  4375.9   548.7  4606.2  544.89  4642.6  544.92  4757.7  542.53
  4960.9  540.32  4982.1  539.43  4995.3  537.19  4995.6  536.69  4999.3  537.19
    5002  538.33  5007.9  538.33  5012.8  540.06  5040.1  540.33    5050  541.36
  5077.3  541.06    5136  542.21    5189  541.58  5194.7  542.23  5269.2  543.37
    5275  542.72    5306  543.52  5340.7  542.92  5370.9  544.72  5392.4  544.95
  5413.9  543.26  5421.7  544.43  5488.3  545.87  5648.7  547.16  5699.6  549.87
#Mann= 3 ,-1 , 0
    4353     .05       0  4995.3     .03       0  4999.3     .05       0
Bank Sta=4995.3,4999.3
XS Rating Curve= 0 ,0
Exp/Cntr=0.3,0.1

Type RM Length L Ch R = 1 ,3730    ,428,428,428
BEGIN DESCRIPTION:
Hackberry Creek Tributary 5 5.0
END DESCRIPTION:
XS GIS Cut Line= 3
      2623425.99      7018260.99        2622826.        7017861.
       2622380.9        7017861.
#Sta/Elev= 30
  4278.5  548.69  4364.1  546.15  4436.2     546  4472.3  544.66  4589.5  544.14
  4631.5  542.52  4646.6  543.16  4898.9  539.99    4935  539.17    4956  537.48
  4963.5  538.28  4977.1  537.32  4984.1  534.51  4984.3  534.01  4988.1  534.51
  4992.1  534.61  4996.6  536.57  5002.1  536.57  5009.6  539.83  5019.6  540.39
  5139.6  539.88  5179.6  541.86  5237.9  542.39  5240.4  542.39  5269.6  541.64
  5379.6  543.02  5389.6   542.2  5399.6  543.97  5419.6  544.96  5444.7  543.55
#Mann= 5 ,-1 , 0
  4278.5     .05       0  4984.1     .03       0  4988.1     .05       0
  5237.9      .1       0  5240.4    .075       0
Bank Sta=4984.1,4988.1
XS Rating Curve= 0 ,0
Exp/Cntr=0.3,0.1

Type RM Length L Ch R = 1 ,3302    ,79,79,79
BEGIN DESCRIPTION:
Mapping XS eb28ef0d
END DESCRIPTION:
XS GIS Cut Line= 6
      2623810.36      7017047.25      2623299.98       7017208.7
      2622854.67       7017461.3      2622562.47      7017694.83
       2622414.9      7017822.87      2622164.55      7017940.47
#Sta/Elev= 30
  3977.3  541.78  4417.7  541.57    4469  542.19  4634.6  541.28    4854  539.15
  4891.5  541.55 4909.61  539.87  4911.4  538.24  4919.6  539.97  5030.7  541.94
  5065.9  539.53  5073.9  541.37  5080.3  539.08  5094.7  541.55  5144.4  538.88
  5158.8  541.42  5179.6  539.31  5201.6  540.37  5234.4  540.47  5301.3  541.61
  5322.1   538.8  5353.7  540.36  5496.3  541.73    5501  541.45  5570.5  541.27
    5590  544.33    5624  544.77  5672.7  544.37  5845.4  548.83  5870.6  549.31
#Mann= 14 ,-1 , 0
  3977.3    .075       0  4417.7     .05       0    4469    .075       0
  4634.6     .05       0 4909.61     .03       0  4919.6     .05       0
  5201.6      .1       0  5234.4     .05       0  5353.7      .1       0
  5496.3     .05       0    5501    .075       0    5624     .05       0
  5672.7    .075       0  5845.4     .05       0
Bank Sta=4909.61,4919.6
XS Rating Curve= 0 ,0
Exp/Cntr=0.3,0.1

Type RM Length L Ch R = 1 ,3223    ,397,397,397
BEGIN DESCRIPTION:
Mapping XS e1226d4a
END DESCRIPTION:
XS GIS Cut Line= 6
      2623801.74      7017009.97      2623468.45      7017093.29
       2623126.7      7017211.98      2622869.49      7017374.54
      2622007.51      7017983.92      2621950.58      7018061.55
#Sta/Elev= 30
  3998.5  542.16  4436.2  540.61  4624.9  540.63    4694  537.79  4993.3  540.43
  5007.2  536.11  5014.6   538.8  5021.3  533.25  5021.5  532.75  5025.3  533.25
  5029.4  540.72  5036.8  535.32  5050.3  539.24    5059  536.15  5065.1  540.74
  5079.9  537.04    5086  540.03  5109.6  538.41  5115.7  541.41  5130.5  538.56
  5151.4  540.74  5366.5  539.33  5538.5  543.61  5582.7  541.17  5837.6  545.61
  5840.6  546.19  5983.5   546.3  6027.7  549.95  6084.9  548.13    6160  551.75
#Mann= 6 ,-1 , 0
  3998.5    .075       0  4436.2     .05       0  5021.3     .03       0
  5025.3     .05       0  5837.6    .075       0  5840.6     .05       0
Bank Sta=5021.3,5025.3
XS Rating Curve= 0 ,0
Exp/Cntr=0.3,0.1

Type RM Length L Ch R = 1 ,2826    ,56,56,56
BEGIN DESCRIPTION:
Mapping XS ea0bb06d
END DESCRIPTION:
XS GIS Cut Line= 4
      2623682.74      7017011.68      2623109.78      7016992.14
      2622819.41      7016989.54      2622306.36      7016980.42
#Sta/Elev= 30
  4142.6  541.34  4159.3  541.35  4179.4  539.49  4219.4  538.59  4319.4  539.26
  4389.5  537.63  4470.2  538.44  4509.6  538.16  4529.6  537.05  4579.6  537.84
  4739.7  536.22  4869.7  536.18  4899.7  537.58  4919.7  535.99  4969.7  535.75
  4979.7  534.42  4987.6  532.19  4987.9  531.69  4991.7  532.19  4999.7  532.77
  5005.5   535.5  5139.7   535.9  5199.7  538.14  5210.1  540.57  5219.7  540.69
  5229.7  539.09  5299.7   540.5  5389.7  545.79  5429.8  544.33  5519.4  546.36
#Mann= 4 ,-1 , 0
  4142.6    .075       0  4470.2     .05       0  4987.6     .05       0
  4991.7     .05       0
Bank Sta=4987.6,4991.7
XS Rating Curve= 0 ,0
Exp/Cntr=0.3,0.1

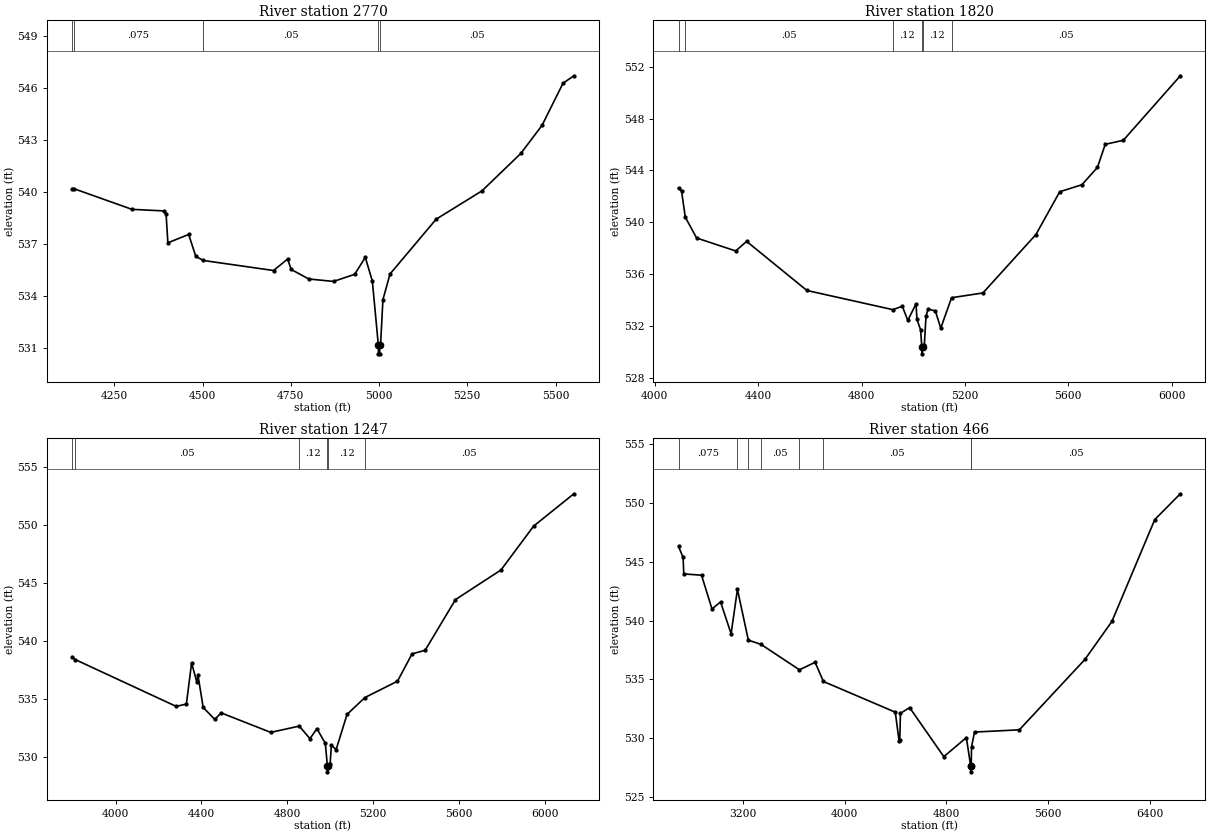
Type RM Length L Ch R = 1 ,2770    ,950,950,950
BEGIN DESCRIPTION:
Mapping XS 5d621092
END DESCRIPTION:
XS GIS Cut Line= 6
      2623715.26      7016977.82      2623285.56      7016942.66
      2623183.99      7016942.66      2622842.85      7016940.06
      2622697.02      7016925.74      2622295.94      7016915.32
#Sta/Elev= 30
  4130.3  540.18  4134.4  540.19  4300.1  538.99  4390.4   538.9  4396.7   538.7
  4401.7  537.06  4460.7  537.54  4480.7  536.28  4501.8  536.04    4701  535.46
    4741  536.12    4751  535.52    4801  534.97    4871  534.83    4931  535.24
    4961  536.22    4981  534.85    4998  531.15  4998.3  530.65  5001.8  530.65
  5002.1  531.15  5004.2  531.15    5011  533.78  5031.1  535.26  5161.7  538.42
  5291.8  540.06  5401.8  542.22  5461.8  543.84  5521.2  546.27  5551.9   546.7
#Mann= 5 ,-1 , 0
  4130.3     .05       0  4134.4    .075       0  4501.8     .05       0
    4998     .03       0  5002.1     .05       0
Bank Sta=4998,5002.1
XS Rating Curve= 0 ,0
Exp/Cntr=0.3,0.1

Type RM Length L Ch R = 1 ,1820    ,573,573,573
BEGIN DESCRIPTION:
Mapping XS 69b4ed4c
END DESCRIPTION:
XS GIS Cut Line= 4
      2623831.45      7017010.78      2623336.66      7016239.95
      2622893.95      7015854.53      2622456.41      7015818.07
#Sta/Elev= 30
  4091.8  542.65  4103.4  542.42  4117.9   540.4  4161.8  538.79  4313.1  537.79
  4355.3  538.53  4588.6  534.74  4921.2  533.26  4957.9  533.52    4979  532.43
  5010.8   533.7  5014.5  532.51  5028.8  531.69  5033.3  530.35  5033.6  529.85
  5037.5  530.35    5043  530.53  5049.6  532.74  5057.3  533.31  5085.7  533.16
  5106.6  531.83  5148.4  534.18  5269.9  534.55    5475  539.06  5567.1  542.36
  5652.9   542.9  5713.1  544.24  5743.2  546.02  5813.1  546.33  6033.8  551.31
#Mann= 6 ,-1 , 0
  4091.8    .075       0  4117.9     .05       0  4921.2     .12       0
  5033.3     .07       0  5037.5     .12       0  5148.4     .05       0
Bank Sta=5033.3,5037.5
XS Rating Curve= 0 ,0
Exp/Cntr=0.3,0.1

Type RM Length L Ch R = 1 ,1247    ,781,781,781
BEGIN DESCRIPTION:
Mapping XS 16e250c0
END DESCRIPTION:
XS GIS Cut Line= 4
      2623917.38      7016832.15      2623476.41      7015721.06
      2623205.58      7015550.93      2622390.32      7015675.82
#Sta/Elev= 30
  3796.5   538.6  3811.8  538.36  4281.9  534.33  4329.6  534.53  4353.9  538.08
  4378.2  536.42  4383.6  537.02  4407.9  534.24  4461.9  533.21  4491.6  533.77
    4723  532.09  4855.8  532.63  4905.9  531.55  4938.2  532.41  4977.6  531.14
  4987.1  529.19  4987.4  528.69  4991.4  529.19  4999.8  529.35  5005.8     531
  5027.8   530.6  5078.8  533.64  5161.9  535.09    5314   536.5  5382.1  538.86
  5442.8  539.16  5584.5  543.53  5796.9  546.09  5948.7  549.86  6136.5  552.65
#Mann= 6 ,-1 , 0
  3796.5      .1       0  3811.8     .05       0  4855.8     .12       0
  4987.1     .07       0  4991.4     .12       0  5161.9     .05       0
Bank Sta=4987.1,4991.4
XS Rating Curve= 0 ,0
Exp/Cntr=0.3,0.1

Type RM Length L Ch R = 1 ,466     ,0,0,0
BEGIN DESCRIPTION:
Hackberry Creek Tributary 5 1.0
END DESCRIPTION:
XS GIS Cut Line= 5
      2623876.01      7017460.95      2624156.97      7015398.15
      2623984.14      7015254.94      2623688.22      7015030.09
      2622521.57      7015533.56
#Sta/Elev= 30
  2693.7  546.29  2729.8  545.36  2734.9  543.96  2874.6  543.85    2957  540.98
  3024.4  541.58  3107.4  538.87  3157.2  542.65    3243  538.33  3341.4  537.98
  3645.2  535.81  3768.3  536.45  3833.5  534.82  4399.3  532.21  4429.5  529.73
  4434.8  529.84  4439.8  532.11  4512.2   532.6  4781.1  528.43  4958.6  530.05
  4992.6  527.64  4992.9  527.14  4996.9  527.64  4999.2  529.25  5022.8  530.52
  5375.6  530.71  5891.4  536.69  6103.8  539.92  6441.3  548.58  6642.3  550.77
#Mann= 8 ,-1 , 0
  2693.7    .075       0  3157.2     .05       0    3243      .1       0
  3341.4     .05       0  3645.2      .1       0  3833.5     .05       0
  4992.6     .04       0  4996.9     .05       0
Bank Sta=4992.6,4996.9
XS Rating Curve= 0 ,0
Exp/Cntr=0.3,0.1

Chan Stop Cuts=-1
Use User Specified Reach Order=0
Composite Channel Slope=5