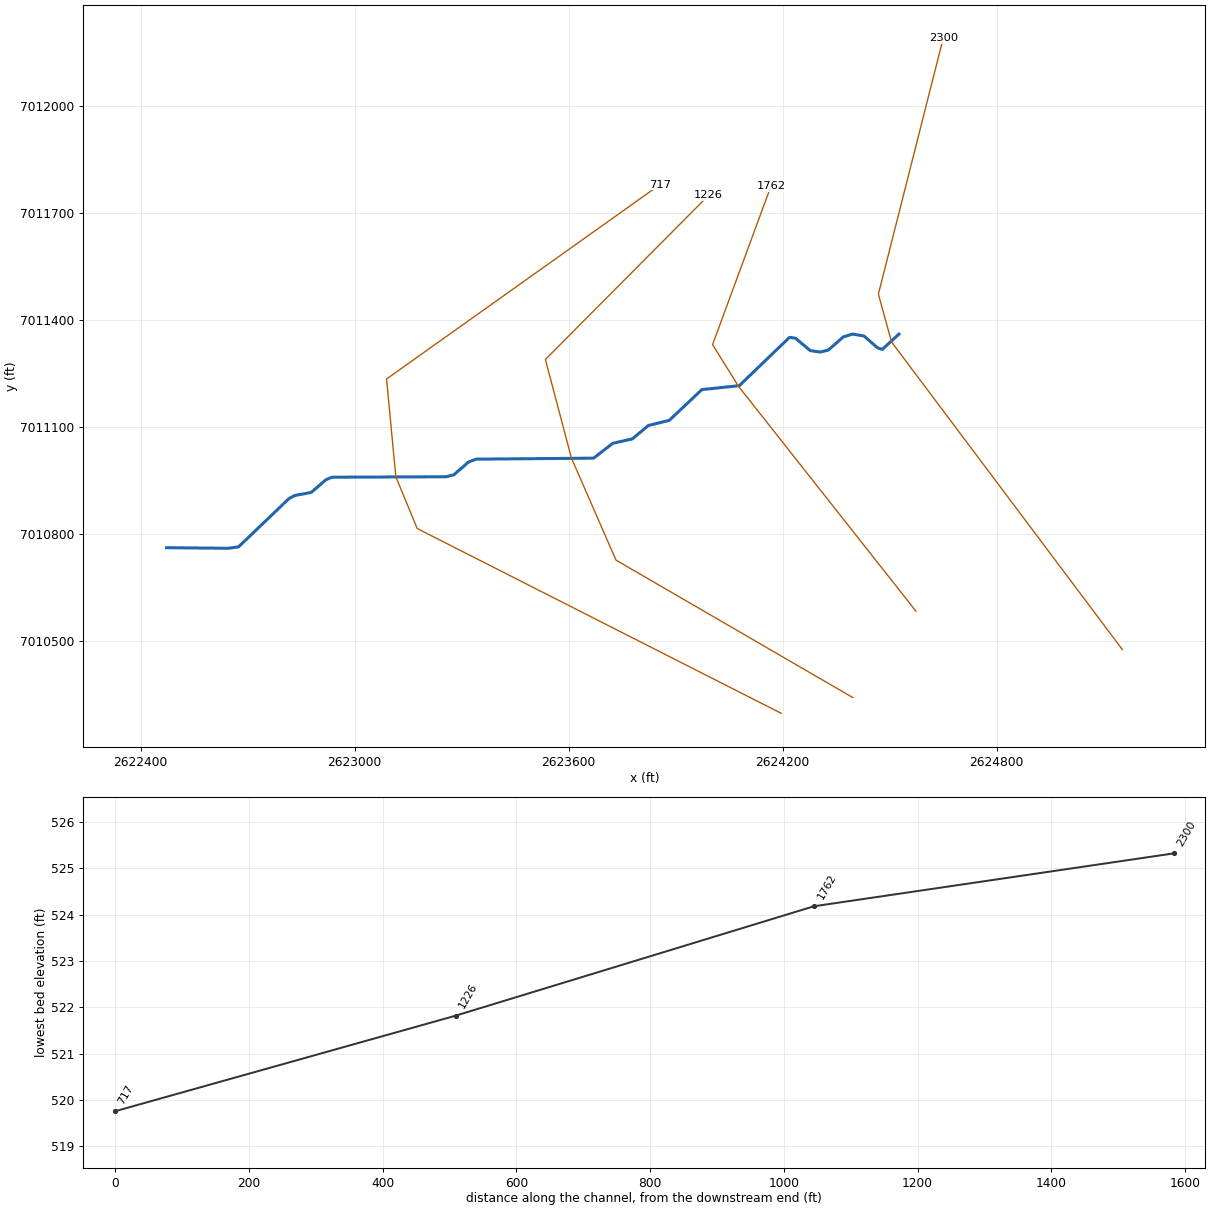
--- Hackberry Creek Tributary 6.prj (project) ---

Proj Title=Hackberry Creek Tributary 6 Base Level Engineering
Current Plan=p01
Default Exp/Contr=0.3,0.1
English Units
Geom File=g01
Flow File=f01
Plan File=p01
BEGIN DESCRIPTION:
Hackberry Creek Tributary 6
END DESCRIPTION:

--- Hackberry Creek Tributary 6.p01 (plan) ---

Plan Title=Multiple Run
Short Identifier=Multiple
Geom File=g01
Flow File=f01
Subcritical Flow
K Sum by GR= 0
Std Step Tol= 0.01
Critical Tol= 0.01
Num of Std Step Trials= 20
Max Error Tol= 0.3
Flow Tol Ratio= 0.001
Split Flow NTrial= 30
Split Flow Tol= 0.02
Split Flow Ratio= 0.02
Log Output Level= 0
Friction Slope Method= 1
Unsteady Friction Slope Method= 2
Unsteady Bridges Friction Slope Method= 1
Parabolic Critical Depth
Global Vel Dist=  1 , 1 , 1
Global Log Level= 0
CheckData=True
Encroach Param= -1, 0, 0, 0
BEGIN DESCRIPTION:
Multiple Run
END DESCRIPTION:

--- Hackberry Creek Tributary 6.f01 (steady flow) ---

Flow Title=Multiple
Number of Profiles=7
Profile Names=10-year,25-year,50-year,1pct_min,100-year,1pct_plu,500-year
River Rch & RM= Hackberry Creek ,Reach-1,2300
     359     469     556     328     654    1306     904
Boundary for River Rch & Prof#=Hackberry Creek ,Reach-1,1
Up Type=0
Dn Type=3
Dn Slope=0.005
Boundary for River Rch & Prof#=Hackberry Creek ,Reach-1,2
Up Type=0
Dn Type=3
Dn Slope=0.005
Boundary for River Rch & Prof#=Hackberry Creek ,Reach-1,3
Up Type=0
Dn Type=3
Dn Slope=0.005
Boundary for River Rch & Prof#=Hackberry Creek ,Reach-1,4
Up Type=0
Dn Type=3
Dn Slope=0.005
Boundary for River Rch & Prof#=Hackberry Creek ,Reach-1,5
Up Type=0
Dn Type=3
Dn Slope=0.005
Boundary for River Rch & Prof#=Hackberry Creek ,Reach-1,6
Up Type=0
Dn Type=3
Dn Slope=0.005
Boundary for River Rch & Prof#=Hackberry Creek ,Reach-1,7
Up Type=0
Dn Type=3
Dn Slope=0.005

--- Hackberry Creek Tributary 6.g01 (geometry) ---

Geom Title=Existing Conditions

River Reach=Hackberry Creek ,Reach-1
Reach XY= 30
      2624526.00      7011361.00      2624479.44      7011318.27
      2624466.17      7011322.44      2624428.32      7011355.52
      2624396.20      7011361.23      2624370.07      7011353.13
      2624328.19      7011316.44      2624305.80      7011310.81
      2624277.63      7011314.62      2624235.87      7011349.61
      2624219.27      7011351.85      2624078.43      7011216.53
      2623973.58      7011205.46      2623882.05      7011119.16
      2623823.81      7011104.90      2623778.20      7011067.08
      2623723.82      7011054.88      2623670.07      7011013.24
      2623341.22      7011010.48      2623319.94      7011002.86
      2623278.33      7010966.75      2623255.97      7010961.07
      2622936.50      7010959.80      2622919.92      7010952.91
      2622878.17      7010917.14      2622832.03      7010908.50
      2622816.32      7010900.24      2622674.54      7010764.53
      2622646.19      7010760.55      2622472.57      7010762.22

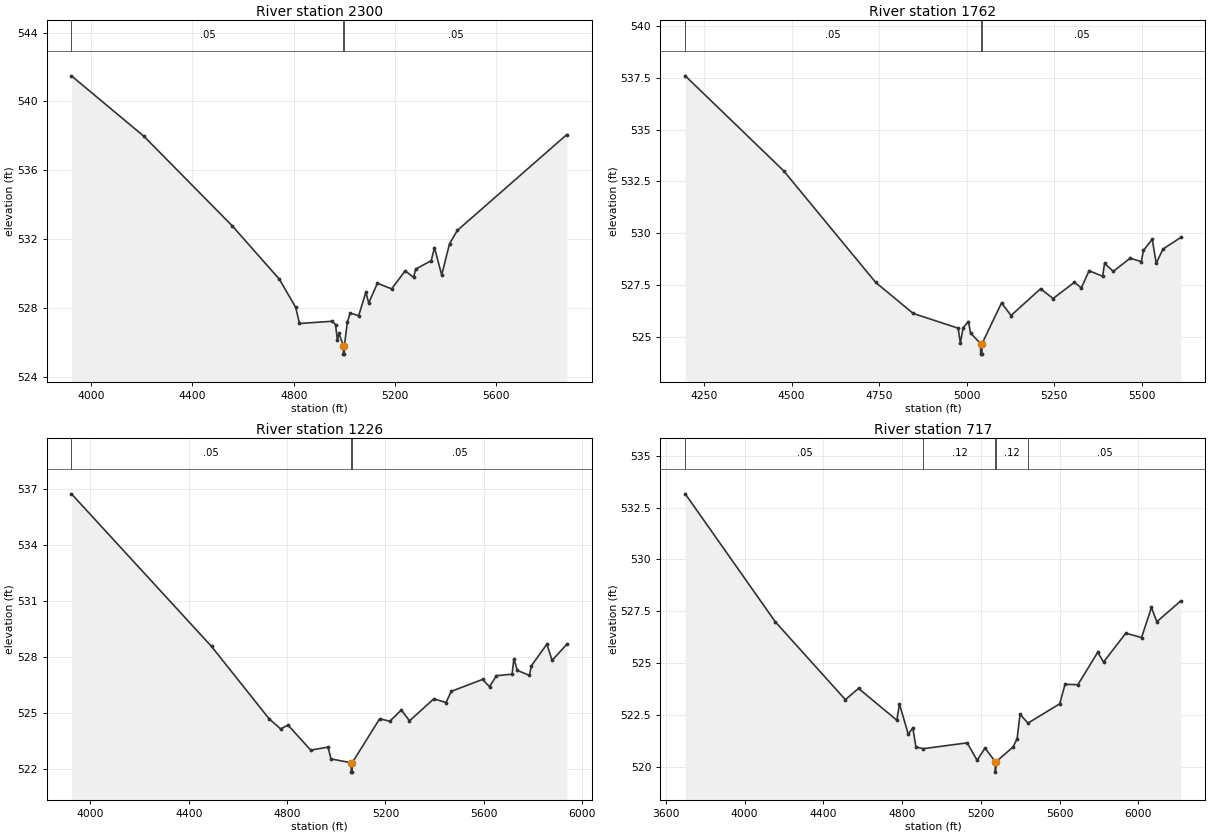
Type RM Length L Ch R = 1,2300,538,538,538
BEGIN DESCRIPTION:
Hackberry Creek Tributary 6 4.0
END DESCRIPTION:
XS GIS Cut Line= 4
      2625152.36      7010476.66      2624505.39      7011338.93
      2624468.45      7011473.21      2624650.16      7012190.28
#Sta/Elev= 30
  3922.0  541.49  4208.1  537.98  4558.1  532.76  4743.5  529.67  4808.1  528.03
  4822.7  527.10  4951.8  527.23  4965.1  527.04  4972.7  526.13  4978.9  526.52
  4996.2  525.82  4996.4  525.32  4999.9  525.32  5000.2  525.82  5011.9  527.17
  5022.9  527.71  5056.7  527.55  5085.1  528.92  5096.3  528.29  5130.7  529.44
  5186.9  529.11  5240.1  530.16  5274.0  529.78  5281.4  530.26  5343.3  530.75
  5356.0  531.51  5384.6  529.92  5415.5  531.73  5446.5  532.51  5879.0  538.08
#Mann=3,-1,0
  3922.0    0.05       0  4996.2    0.03       0  5000.2    0.05       0
Bank Sta=4996.2,5000.2
Exp/Cntr=0.3,0.1

Type RM Length L Ch R = 1,1762,536,536,536
BEGIN DESCRIPTION:
Mapping XS 3972b46a
END DESCRIPTION:
XS GIS Cut Line= 4
      2624573.85      7010584.19      2624076.48      7011214.38
      2624003.56      7011331.57      2624167.45      7011776.40
#Sta/Elev= 30
  4196.1  537.59  4476.9  533.02  4739.8  527.64  4847.2  526.14  4975.5  525.43
  4981.9  524.72  4989.9  525.46  5005.1  525.75  5010.9  525.20  5039.7  524.68
  5039.9  524.18  5043.4  524.18  5043.7  524.68  5099.5  526.65  5126.6  526.04
  5210.9  527.33  5246.7  526.86  5307.6  527.64  5327.4  527.37  5349.5  528.20
  5388.3  527.93  5393.6  528.55  5418.8  528.17  5466.7  528.80  5498.7  528.64
  5504.8  529.18  5529.9  529.71  5541.3  528.56  5560.4  529.24  5611.0  529.80
#Mann=3,-1,0
  4196.1    0.05       0  5039.7    0.03       0  5043.7    0.05       0
Bank Sta=5039.7,5043.7
Exp/Cntr=0.3,0.1

Type RM Length L Ch R = 1,1226,509,509,509
BEGIN DESCRIPTION:
Mapping XS cff50071
END DESCRIPTION:
XS GIS Cut Line= 5
      2624396.76      7010342.00      2623732.73      7010727.40
      2623607.73      7011013.86      2623534.81      7011289.90
      2623992.05      7011749.74
#Sta/Elev= 30
  3923.1  536.74  4492.6  528.56  4727.5  524.67  4773.4  524.14  4803.9  524.34
  4895.9  523.00  4966.2  523.16  4978.5  522.53  5060.5  522.32  5060.8  521.82
  5064.3  521.82  5064.5  522.32  5176.3  524.68  5217.7  524.55  5264.4  525.15
  5297.6  524.57  5396.6  525.75  5446.1  525.55  5467.3  526.15  5594.6  526.79
  5622.9  526.40  5651.2  526.99  5714.8  527.07  5721.9  527.90  5736.0  527.27
  5785.5  527.01  5792.6  527.51  5856.2  528.68  5877.4  527.81  5937.4  528.68
#Mann=3,-1,0
  3923.1    0.05       0  5060.5    0.03       0  5064.5    0.05       0
Bank Sta=5060.5,5064.5
Exp/Cntr=0.3,0.1

Type RM Length L Ch R = 1,717,0,0,0
BEGIN DESCRIPTION:
Mapping XS cdc1a36c
END DESCRIPTION:
XS GIS Cut Line= 5
      2624196.31      7010297.69      2623175.44      7010815.94
      2623115.54      7010960.98      2623089.50      7011235.21
      2623855.10      7011779.46
#Sta/Elev= 30
  3698.2  533.16  4155.6  527.00  4511.7  523.25  4578.5  523.79  4773.2  522.26
  4786.4  523.04  4831.2  521.59  4854.3  521.89  4870.2  520.97  4908.2  520.89
  5130.6  521.17  5180.8  520.33  5221.0  520.92  5273.5  520.26  5273.7  519.76
  5277.5  520.26  5363.2  520.97  5384.1  521.37  5398.8  522.54  5439.4  522.12
  5600.5  523.05  5627.6  523.99  5692.8  523.97  5793.6  525.53  5823.1  525.06
  5936.3  526.45  6016.2  526.24  6066.6  527.69  6093.7  527.00  6214.8  528.00
#Mann=5,-1,0
  3698.2    0.05       0  4908.2    0.12       0  5273.5    0.07       0
  5277.5    0.12       0  5439.4    0.05       0
Bank Sta=5273.5,5277.5
Exp/Cntr=0.3,0.1

Chan Stop Cuts=-1