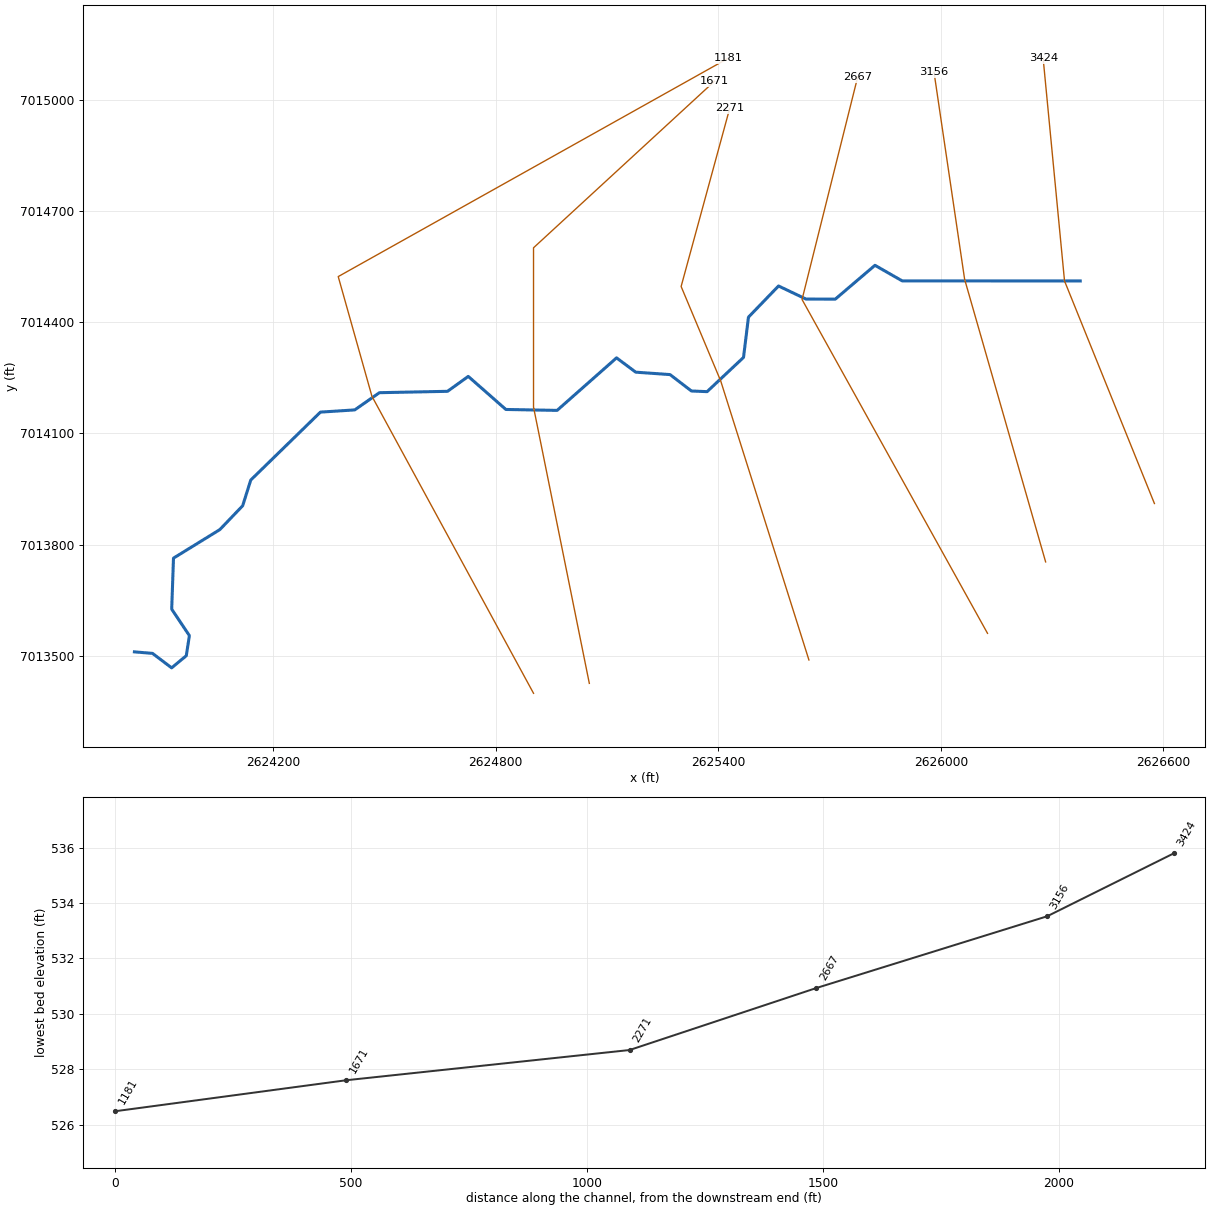
--- Hackberry Creek Tributary 7.prj (project) ---

Proj Title=Hackberry Creek Tributary 7 Base Level Engineering
Current Plan=p01
Default Exp/Contr=0.3,0.1
English Units
Geom File=g01
Flow File=f01
Plan File=p01
BEGIN DESCRIPTION:
Hackberry Creek Tributary 7
END DESCRIPTION:

--- Hackberry Creek Tributary 7.p01 (plan) ---

Plan Title=Multiple Run
Short Identifier=Multiple
Geom File=g01
Flow File=f01
Subcritical Flow
K Sum by GR= 0
Std Step Tol= 0.01
Critical Tol= 0.01
Num of Std Step Trials= 20
Max Error Tol= 0.3
Flow Tol Ratio= 0.001
Split Flow NTrial= 30
Split Flow Tol= 0.02
Split Flow Ratio= 0.02
Log Output Level= 0
Friction Slope Method= 1
Unsteady Friction Slope Method= 2
Unsteady Bridges Friction Slope Method= 1
Parabolic Critical Depth
Global Vel Dist=  1 , 1 , 1
Global Log Level= 0
CheckData=True
Encroach Param= -1, 0, 0, 0
BEGIN DESCRIPTION:
Multiple Run
END DESCRIPTION:

--- Hackberry Creek Tributary 7.f01 (steady flow) ---

Flow Title=Multiple
Number of Profiles=7
Profile Names=10-year,25-year,50-year,1pct_min,100-year,1pct_plu,500-year
River Rch & RM= Hackberry Creek ,Reach-1,3424
     391     509     602     353     705    1406     965
River Rch & RM= Hackberry Creek ,Reach-1,2667
     457     601     713     420     839    1673    1158
Boundary for River Rch & Prof#=Hackberry Creek ,Reach-1,1
Up Type=0
Dn Type=3
Dn Slope=0.005
Boundary for River Rch & Prof#=Hackberry Creek ,Reach-1,2
Up Type=0
Dn Type=3
Dn Slope=0.005
Boundary for River Rch & Prof#=Hackberry Creek ,Reach-1,3
Up Type=0
Dn Type=3
Dn Slope=0.005
Boundary for River Rch & Prof#=Hackberry Creek ,Reach-1,4
Up Type=0
Dn Type=3
Dn Slope=0.005
Boundary for River Rch & Prof#=Hackberry Creek ,Reach-1,5
Up Type=0
Dn Type=3
Dn Slope=0.005
Boundary for River Rch & Prof#=Hackberry Creek ,Reach-1,6
Up Type=0
Dn Type=3
Dn Slope=0.005
Boundary for River Rch & Prof#=Hackberry Creek ,Reach-1,7
Up Type=0
Dn Type=3
Dn Slope=0.005

--- Hackberry Creek Tributary 7.g01 (geometry) ---

Geom Title=Existing Conditions

River Reach=Hackberry Creek ,Reach-1
Reach XY= 30
      2626376.00      7014511.00      2625895.98      7014511.19
      2625822.59      7014553.19      2625715.52      7014461.95
      2625636.48      7014462.27      2625562.59      7014497.48
      2625481.52      7014413.46      2625468.14      7014304.81
      2625369.98      7014212.61      2625327.75      7014214.34
      2625270.03      7014258.62      2625177.50      7014265.10
      2625125.90      7014303.69      2624965.56      7014162.04
      2624827.47      7014164.55      2624726.10      7014253.67
      2624670.15      7014213.47      2624486.50      7014209.78
      2624420.02      7014163.36      2624327.50      7014157.39
      2624139.63      7013974.21      2624117.85      7013904.93
      2624056.23      7013840.59      2623931.35      7013763.70
      2623926.52      7013626.22      2623974.22      7013554.79
      2623965.84      7013500.59      2623926.37      7013467.95
      2623874.66      7013506.97      2623826.00      7013511.00

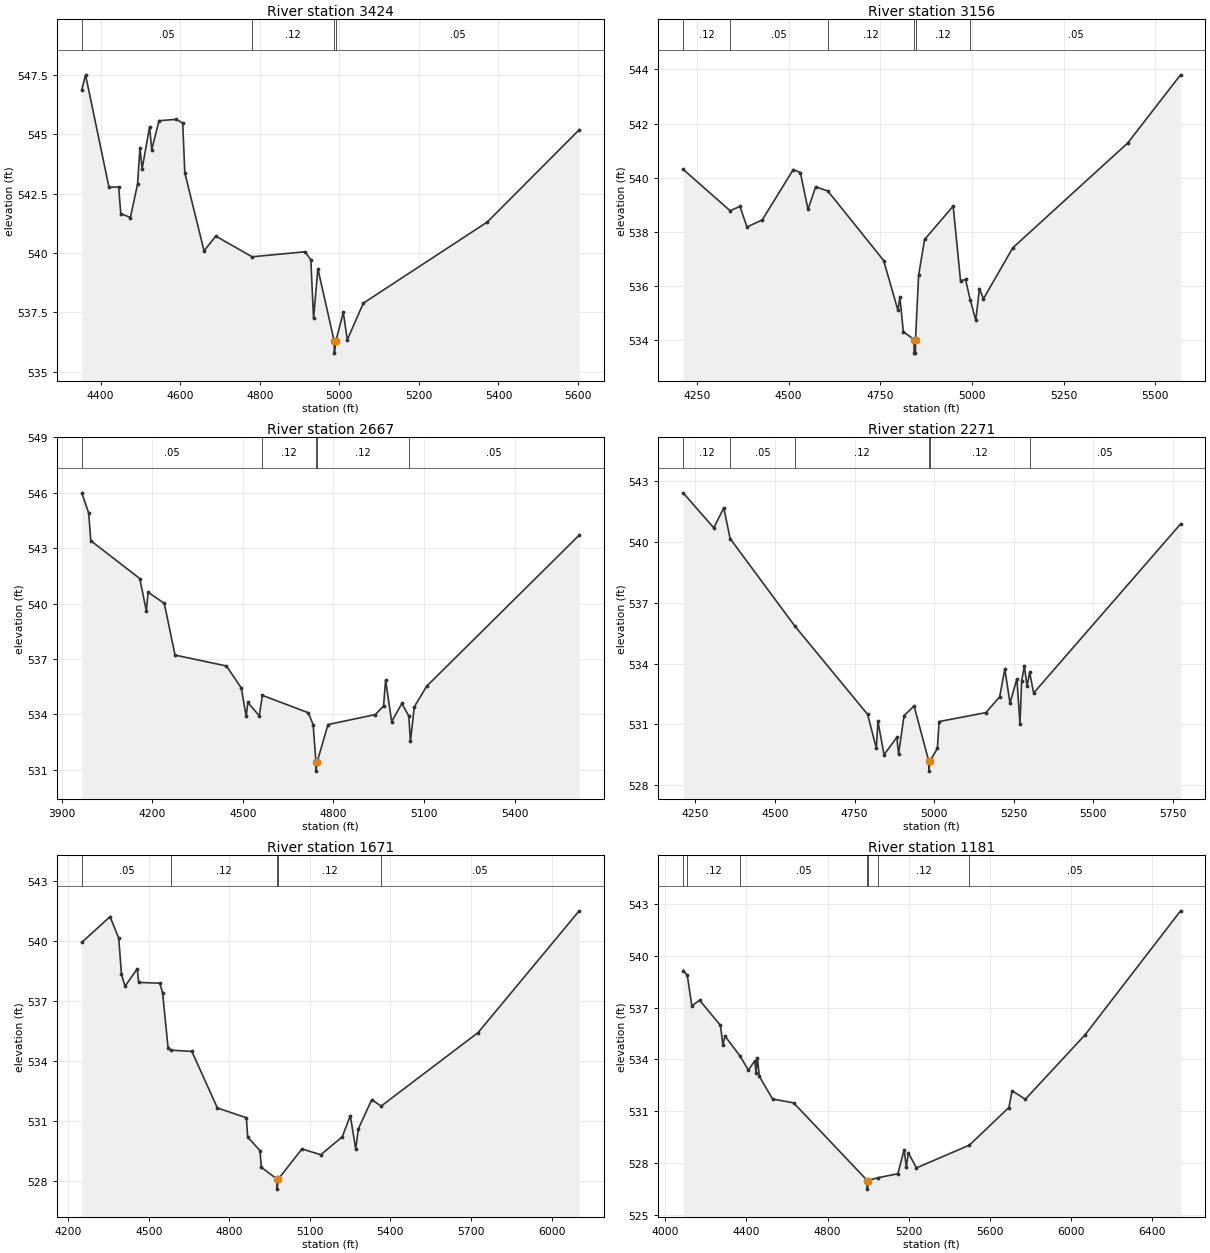
Type RM Length L Ch R = 1,3424,268,268,268
BEGIN DESCRIPTION:
Hackberry Creek Tributary 7 4.0
END DESCRIPTION:
XS GIS Cut Line= 3
      2626576.00      7013911.00      2626333.65      7014511.00
      2626276.00      7015111.03
#Sta/Elev= 30
  4352.9  546.86  4362.3  547.49  4421.3  542.76  4445.5  542.78  4450.9  541.66
  4475.0  541.49  4493.1  542.90  4499.1  544.42  4504.5  543.54  4523.3  545.30
  4528.7  544.35  4547.0  545.56  4590.2  545.62  4606.5  545.46  4611.8  543.37
  4660.1  540.09  4689.6  540.71  4780.9  539.84  4913.7  540.05  4928.4  539.72
  4935.3  537.25  4946.1  539.34  4987.2  536.29  4987.5  535.79  4991.2  536.29
  5010.0  537.50  5020.1  536.35  5060.3  537.89  5371.7  541.30  5602.8  545.18
#Mann=4,-1,0
  4352.9    0.05       0  4780.9    0.12       0  4987.2   0.035       0
  4991.2    0.05       0
Bank Sta=4987.2,4991.2
Exp/Cntr=0.3,0.1

Type RM Length L Ch R = 1,3156,489,489,489
BEGIN DESCRIPTION:
Mapping XS 7ef9e556
END DESCRIPTION:
XS GIS Cut Line= 3
      2626282.70      7013753.58      2626064.31      7014515.52
      2625981.80      7015073.64
#Sta/Elev= 30
  4212.1  540.31  4340.2  538.78  4367.0  538.94  4386.3  538.18  4427.9  538.44
  4512.5  540.30  4531.9  540.19  4552.7  538.83  4573.5  539.66  4606.8  539.51
  4759.1  536.94  4798.1  535.10  4803.3  535.59  4812.8  534.31  4842.0  534.02
  4842.2  533.52  4845.7  533.52  4846.0  534.02  4854.4  536.39  4870.8  537.72
  4948.7  538.95  4968.8  536.19  4982.4  536.24  4995.2  535.49  5010.3  534.74
  5020.4  535.89  5031.4  535.53  5111.3  537.41  5424.7  541.28  5568.9  543.80
#Mann=6,-1,0
  4212.1    0.12       0  4340.2    0.05       0  4606.8    0.12       0
  4842.0   0.035       0  4846.0    0.12       0  4995.2    0.05       0
Bank Sta=4842,4846
Exp/Cntr=0.3,0.1

Type RM Length L Ch R = 1,2667,396,396,396
BEGIN DESCRIPTION:
Hackberry Creek Tributary 7 3.0
END DESCRIPTION:
XS GIS Cut Line= 3
      2626126.01      7013560.98      2625626.00      7014461.00
      2625776.01      7015061.04
#Sta/Elev= 30
  3966.1  545.99  3989.0  544.89  3995.9  543.40  4158.3  541.35  4180.0  539.60
  4185.8  540.61  4239.5  540.01  4275.0  537.21  4445.4  536.62  4494.6  535.43
  4510.7  533.89  4516.4  534.65  4554.1  533.92  4564.6  535.03  4716.6  534.09
  4732.6  533.45  4742.0  531.43  4742.3  530.93  4746.0  531.43  4781.8  533.45
  4938.5  533.99  4965.9  534.45  4972.8  535.85  4992.8  533.61  5026.6  534.59
  5049.7  533.91  5055.0  532.54  5067.8  534.41  5109.1  535.53  5614.2  543.70
#Mann=5,-1,0
  3966.1    0.05       0  4564.6    0.12       0  4742.0    0.07       0
  4746.0    0.12       0  5049.7    0.05       0
Bank Sta=4742,4746
Exp/Cntr=0.3,0.1

Type RM Length L Ch R = 1,2271,600,600,600
BEGIN DESCRIPTION:
Mapping XS 0f1ad93c
END DESCRIPTION:
XS GIS Cut Line= 4
      2625644.51      7013489.17      2625406.74      7014241.33
      2625299.97      7014496.10      2625430.93      7014976.27
#Sta/Elev= 30
  4211.5  542.44  4307.8  540.71  4339.3  541.70  4359.1  540.18  4562.8  535.85
  4791.3  531.49  4818.4  529.82  4823.6  531.15  4842.7  529.50  4883.0  530.36
  4888.3  529.53  4905.6  531.43  4937.1  531.91  4983.2  529.19  4983.5  528.69
  4987.2  529.19  5010.3  529.81  5015.7  531.14  5162.6  531.58  5206.0  532.36
  5222.2  533.74  5238.5  532.05  5260.2  533.25  5269.8  531.02  5275.2  533.16
  5283.7  533.88  5292.0  532.88  5300.2  533.57  5312.8  532.55  5774.3  540.90
#Mann=6,-1,0
  4211.5    0.12       0  4359.1    0.05       0  4562.8    0.12       0
  4983.2    0.07       0  4987.2    0.12       0  5300.2    0.05       0
Bank Sta=4983.2,4987.2
Exp/Cntr=0.3,0.1

Type RM Length L Ch R = 1,1671,490,490,490
BEGIN DESCRIPTION:
Mapping XS 956ac0e6
END DESCRIPTION:
XS GIS Cut Line= 4
      2625052.46      7013426.08      2624902.03      7014170.96
      2624902.03      7014600.44      2625389.78      7015049.37
#Sta/Elev= 30
  4250.7  539.94  4355.9  541.23  4388.3  540.15  4398.5  538.34  4411.7  537.75
  4457.4  538.62  4462.5  537.94  4541.4  537.90  4551.6  537.42  4572.0  534.67
  4583.2  534.55  4660.5  534.49  4755.6  531.66  4863.5  531.17  4868.6  530.20
  4914.3  529.53  4919.4  528.69  4978.1  528.10  4978.3  527.60  4982.1  528.10
  5070.7  529.61  5140.7  529.32  5220.7  530.22  5250.7  531.28  5270.7  529.61
  5280.7  530.62  5330.7  532.08  5365.2  531.75  5726.5  535.43  6103.0  541.52
#Mann=5,-1,0
  4250.7    0.05       0  4583.2    0.12       0  4978.1    0.07       0
  4982.1    0.12       0  5365.2    0.05       0
Bank Sta=4978.1,4982.1
Exp/Cntr=0.3,0.1

Type RM Length L Ch R = 1,1181,0,0,0
BEGIN DESCRIPTION:
Hackberry Creek Tributary 7 1.0
END DESCRIPTION:
XS GIS Cut Line= 4
      2624902.05      7013399.30      2624466.35      7014200.15
      2624375.49      7014522.80      2625426.02      7015111.01
#Sta/Elev= 30
  4088.3  539.15  4108.7  538.88  4131.2  537.10  4169.2  537.43  4272.4  535.97
  4284.1  534.84  4294.6  535.35  4370.3  534.17  4409.5  533.38  4441.8  533.92
  4447.5  533.21  4454.5  534.09  4463.7  533.02  4529.2  531.70  4632.8  531.48
  4995.6  526.98  4995.9  526.48  4999.6  526.98  5047.5  527.14  5146.3  527.37
  5177.5  528.77  5187.9  527.77  5198.3  528.58  5237.9  527.71  5498.8  529.03
  5693.3  531.21  5709.2  532.18  5774.3  531.69  6069.3  535.43  6539.2  542.61
#Mann=7,-1,0
  4088.3    0.05       0  4108.7    0.12       0  4370.3    0.05       0
  4995.6    0.03       0  4999.6    0.05       0  5047.5    0.12       0
  5498.8    0.05       0
Bank Sta=4995.6,4999.6
Exp/Cntr=0.3,0.1

Chan Stop Cuts=-1