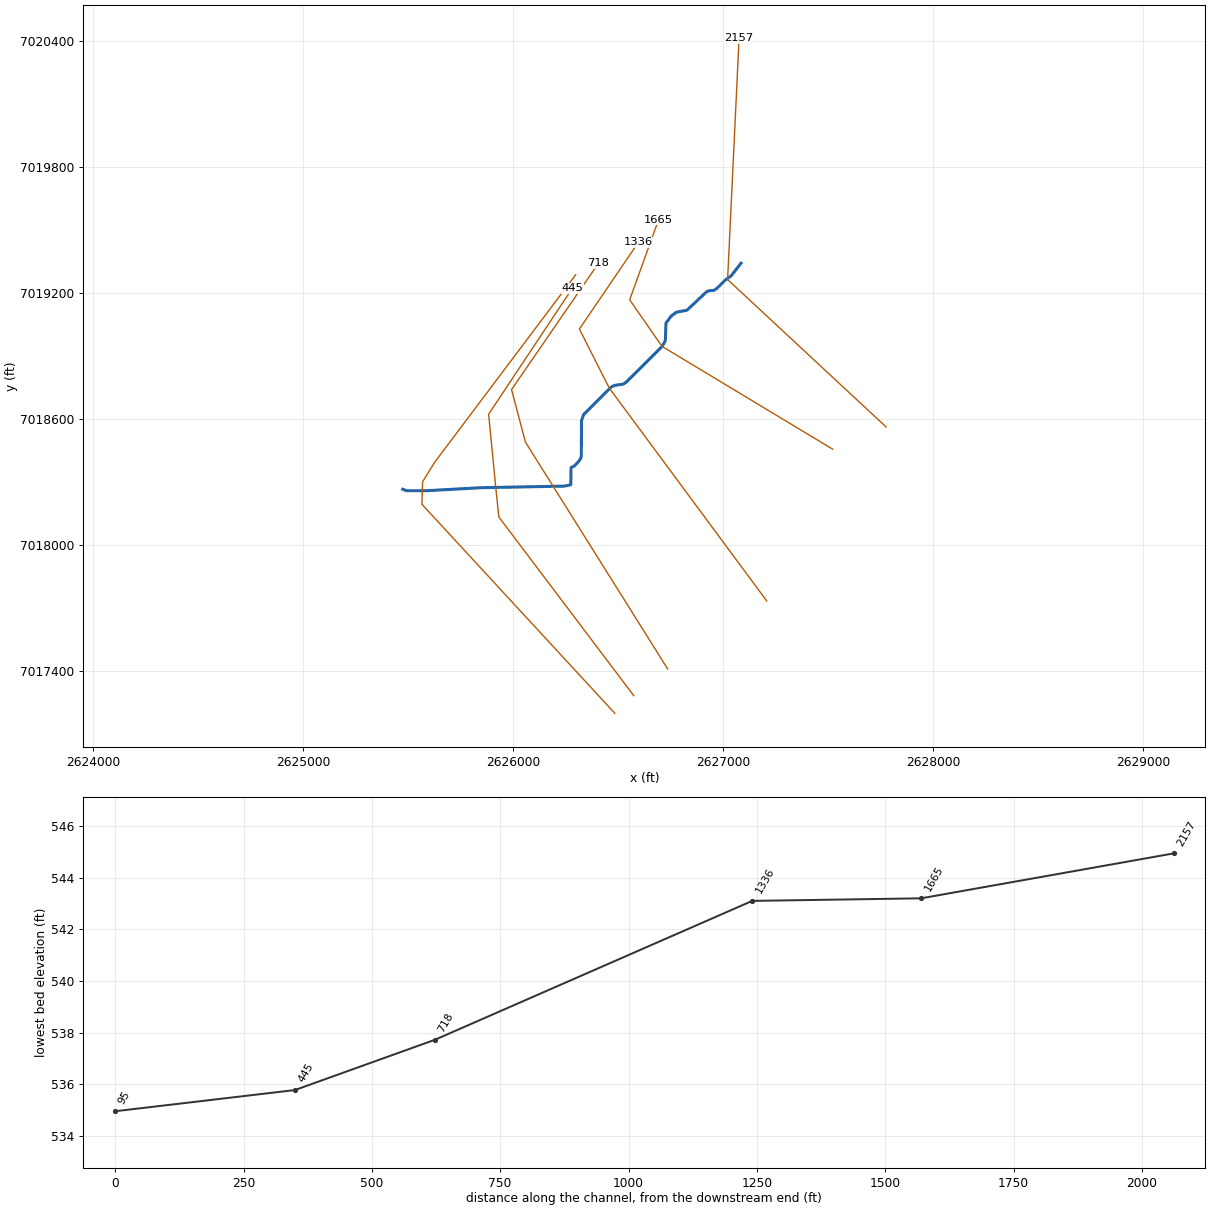
--- Hackberry Creek Tributary 8.prj (project) ---

Proj Title=Hackberry Creek Tributary 8 Base Level Engineering
Current Plan=p01
Default Exp/Contr=0.3,0.1
English Units
Geom File=g01
Flow File=f01
Plan File=p01
BEGIN DESCRIPTION:
Hackberry Creek Tributary 8
END DESCRIPTION:

--- Hackberry Creek Tributary 8.p01 (plan) ---

Plan Title=Multiple Run
Short Identifier=Multiple
Geom File=g01
Flow File=f01
Subcritical Flow
K Sum by GR= 0
Std Step Tol= 0.01
Critical Tol= 0.01
Num of Std Step Trials= 20
Max Error Tol= 0.3
Flow Tol Ratio= 0.001
Split Flow NTrial= 30
Split Flow Tol= 0.02
Split Flow Ratio= 0.02
Log Output Level= 0
Friction Slope Method= 1
Unsteady Friction Slope Method= 2
Unsteady Bridges Friction Slope Method= 1
Parabolic Critical Depth
Global Vel Dist=  1 , 1 , 1
Global Log Level= 0
CheckData=True
Encroach Param= -1, 0, 0, 0
BEGIN DESCRIPTION:
Multiple Run
END DESCRIPTION:

--- Hackberry Creek Tributary 8.f01 (steady flow) ---

Flow Title=Multiple
Number of Profiles=7
Profile Names=10-year,25-year,50-year,1pct_min,100-year,1pct_plu,500-year
River Rch & RM= Hackberry Creek ,Reach-1,2157
     243     306     355     204     408     813     537
River Rch & RM= Hackberry Creek ,Reach-1,718
     659     885    1067     638    1273    2539    1809
Boundary for River Rch & Prof#=Hackberry Creek ,Reach-1,1
Up Type=0
Dn Type=3
Dn Slope=0.005
Boundary for River Rch & Prof#=Hackberry Creek ,Reach-1,2
Up Type=0
Dn Type=3
Dn Slope=0.005
Boundary for River Rch & Prof#=Hackberry Creek ,Reach-1,3
Up Type=0
Dn Type=3
Dn Slope=0.005
Boundary for River Rch & Prof#=Hackberry Creek ,Reach-1,4
Up Type=0
Dn Type=3
Dn Slope=0.005
Boundary for River Rch & Prof#=Hackberry Creek ,Reach-1,5
Up Type=0
Dn Type=3
Dn Slope=0.005
Boundary for River Rch & Prof#=Hackberry Creek ,Reach-1,6
Up Type=0
Dn Type=3
Dn Slope=0.005
Boundary for River Rch & Prof#=Hackberry Creek ,Reach-1,7
Up Type=0
Dn Type=3
Dn Slope=0.005

--- Hackberry Creek Tributary 8.g01 (geometry) ---

Geom Title=Existing Conditions

River Reach=Hackberry Creek ,Reach-1
Reach XY= 30
      2627085.16      7019340.69      2627038.29      7019280.36
      2627010.51      7019260.39      2626973.12      7019222.90
      2626957.04      7019211.50      2626932.15      7019209.31
      2626919.80      7019203.21      2626828.26      7019116.87
      2626777.40      7019107.13      2626752.05      7019088.19
      2626728.08      7019055.29      2626724.83      7018971.49
      2626709.54      7018944.25      2626539.21      7018774.63
      2626524.35      7018764.98      2626482.05      7018758.47
      2626466.32      7018750.22      2626336.48      7018620.80
      2626325.96      7018591.02      2626324.94      7018421.09
      2626320.52      7018407.97      2626306.35      7018389.83
      2626289.64      7018374.18      2626276.00      7018367.87
      2626274.87      7018285.85      2626244.49      7018279.34
      2625847.35      7018271.75      2625591.28      7018257.64
      2625491.45      7018257.64      2625474.72      7018264.53

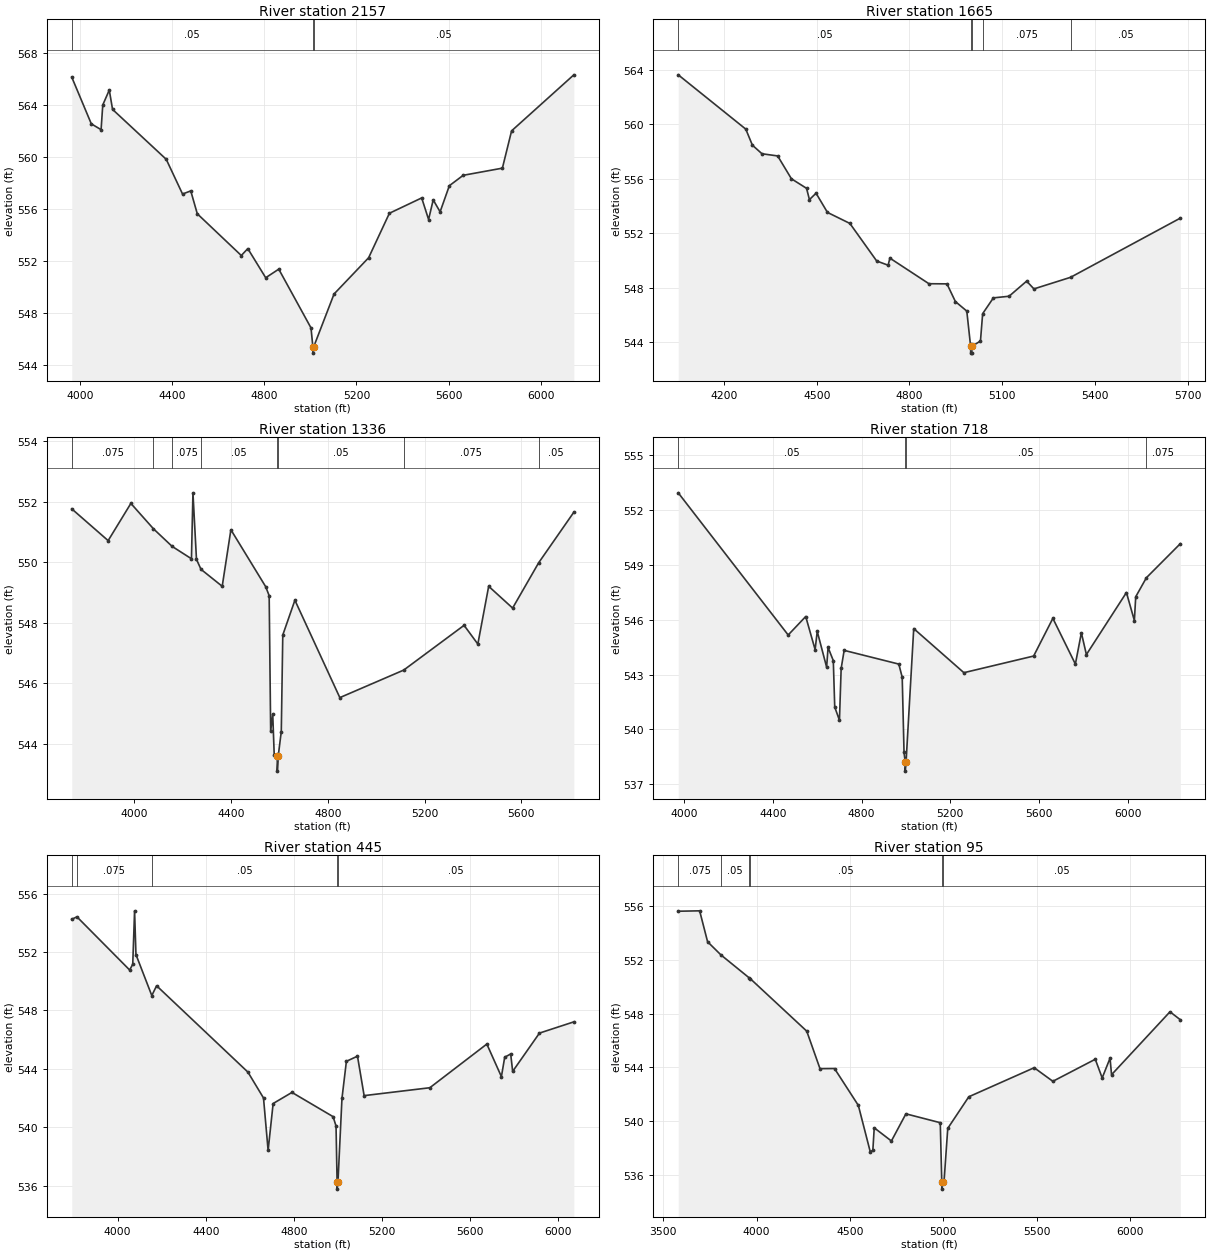
Type RM Length L Ch R = 1,2157,492,492,492
BEGIN DESCRIPTION:
Hackberry Creek Tributary 8 4.0
END DESCRIPTION:
XS GIS Cut Line= 3
      2627775.99      7018561.01      2627021.36      7019262.56
      2627076.00      7020411.00
#Sta/Elev= 30
  3963.8  566.17  4048.6  562.58  4091.1  562.13  4098.4  564.03  4126.7  565.18
  4140.9  563.69  4374.0  559.85  4444.8  557.18  4480.5  557.42  4508.8  555.66
  4699.9  552.45  4728.2  552.98  4805.9  550.74  4862.6  551.40  5002.6  546.88
  5010.6  545.44  5010.9  544.94  5014.6  545.44  5102.7  549.49  5252.9  552.28
  5343.0  555.70  5483.2  556.88  5513.2  555.22  5533.2  556.73  5563.2  555.81
  5603.3  557.82  5663.4  558.62  5833.6  559.17  5873.6  562.04  6143.9  566.35
#Mann=3,-1,0
  3963.8    0.05       0  5010.6    0.04       0  5014.6    0.05       0
Bank Sta=5010.6,5014.6
Exp/Cntr=0.3,0.1

Type RM Length L Ch R = 1,1665,329,329,329
BEGIN DESCRIPTION:
Mapping XS 104df436
END DESCRIPTION:
XS GIS Cut Line= 4
      2627521.38      7018455.26      2626708.86      7018944.85
      2626555.21      7019166.21      2626692.69      7019547.50
#Sta/Elev= 30
  4052.3  563.65  4270.7  559.66  4292.1  558.48  4323.1  557.85  4373.8  557.69
  4418.3  556.01  4467.2  555.31  4476.5  554.48  4497.9  554.95  4534.8  553.54
  4607.3  552.73  4694.0  549.97  4730.9  549.66  4736.7  550.18  4862.9  548.30
  4921.2  548.29  4948.4  546.99  4985.3  546.29  4997.7  543.70  4997.9  543.20
  5001.4  543.20  5001.7  543.70  5029.5  544.09  5036.6  546.10  5071.3  547.26
  5122.0  547.38  5178.8  548.49  5202.4  547.92  5320.8  548.77  5675.7  553.12
#Mann=5,-1,0
  4052.3    0.05       0  4997.7    0.03       0  5001.7    0.05       0
  5036.6   0.075       0  5320.8    0.05       0
Bank Sta=4997.7,5001.7
Exp/Cntr=0.3,0.1

Type RM Length L Ch R = 1,1336,618,618,618
BEGIN DESCRIPTION:
Mapping XS fc6b439e
END DESCRIPTION:
XS GIS Cut Line= 4
      2627208.16      7017732.01      2626458.16      7018745.90
      2626315.80      7019027.15      2626597.06      7019440.35
#Sta/Elev= 30
  3740.8  551.77  3891.2  550.72  3985.2  551.95  4078.7  551.11  4155.7  550.53
  4235.7  550.12  4241.9  552.30  4256.5  550.10  4275.3  549.77  4362.9  549.21
  4398.8  551.08  4542.5  549.20  4557.1  548.90  4563.3  544.42  4571.8  544.99
  4578.0  543.63  4590.6  543.60  4590.8  543.10  4594.6  543.60  4607.2  544.41
  4613.4  547.60  4663.5  548.75  4849.3  545.53  5113.4  546.44  5363.1  547.92
  5420.0  547.30  5464.8  549.21  5563.8  548.49  5671.7  549.99  5817.0  551.66
#Mann=8,-1,0
  3740.8   0.075       0  4078.7    0.05       0  4155.7   0.075       0
  4275.3    0.05       0  4590.6    0.03       0  4594.6    0.05       0
  5113.4   0.075       0  5671.7    0.05       0
Bank Sta=4590.6,4594.6
Exp/Cntr=0.3,0.1

Type RM Length L Ch R = 1,718,273,273,273
BEGIN DESCRIPTION:
Mapping XS 01403c63
END DESCRIPTION:
XS GIS Cut Line= 4
      2626735.96      7017409.06      2626058.86      7018488.95
      2625992.89      7018738.95      2626406.11      7019339.68
#Sta/Elev= 30
  3973.9  552.93  4469.3  545.16  4548.3  546.17  4590.7  544.36  4600.2  545.36
  4642.6  543.40  4649.0  544.48  4672.6  543.76  4679.1  541.22  4700.3  540.50
  4708.0  543.33  4721.5  544.32  4967.8  543.57  4983.1  542.85  4991.3  538.75
  4996.5  538.22  4996.7  537.72  5000.5  538.22  5035.0  545.51  5261.0  543.10
  5575.3  544.01  5661.9  546.07  5763.4  543.57  5790.4  545.28  5813.0  544.09
  5993.4  547.48  6029.2  545.95  6035.3  547.25  6083.4  548.29  6236.2  550.15
#Mann=4,-1,0
  3973.9    0.05       0  4996.5    0.03       0  5000.5    0.05       0
  6083.4   0.075       0
Bank Sta=4996.5,5000.5
Exp/Cntr=0.3,0.1

Type RM Length L Ch R = 1,445,350,350,350
BEGIN DESCRIPTION:
Mapping XS 481c9c9c
END DESCRIPTION:
XS GIS Cut Line= 5
      2626574.79      7017281.50      2625932.42      7018132.21
      2625918.53      7018264.15      2625883.81      7018621.79
      2626282.07      7019220.91
#Sta/Elev= 30
  3792.3  554.24  3815.7  554.41  4054.8  550.77  4068.9  551.16  4077.2  554.82
  4083.4  551.83  4155.3  549.02  4177.1  549.69  4591.3  543.78  4662.0  542.01
  4682.9  538.42  4705.7  541.63  4791.1  542.39  4977.7  540.73  4991.0  540.09
  4995.8  536.27  4996.1  535.77  4999.8  536.27  5017.9  541.98  5038.0  544.52
  5088.3  544.87  5118.4  542.17  5416.4  542.71  5675.0  545.70  5741.1  543.47
  5756.1  544.80  5783.2  545.02  5792.2  543.83  5913.7  546.45  6069.7  547.22
#Mann=5,-1,0
  3792.3    0.05       0  3815.7   0.075       0  4155.3    0.05       0
  4995.8    0.03       0  4999.8    0.05       0
Bank Sta=4995.8,4999.8
Exp/Cntr=0.3,0.1

Type RM Length L Ch R = 1,95,0,0,0
BEGIN DESCRIPTION:
Hackberry Creek Tributary 8 1.0
END DESCRIPTION:
XS GIS Cut Line= 5
      2626484.76      7017197.48      2625566.10      7018192.97
      2625569.57      7018300.61      2625627.41      7018393.63
      2626298.17      7019285.15
#Sta/Elev= 30
  3580.7  555.62  3695.3  555.65  3737.8  553.35  3809.3  552.37  3960.9  550.66
  3965.8  550.61  4268.6  546.70  4339.5  543.91  4417.2  543.92  4544.7  541.18
  4608.3  537.74  4622.4  537.83  4629.8  539.51  4721.7  538.53  4799.4  540.55
  4983.3  539.89  4991.4  535.45  4991.6  534.95  4995.4  535.45  5003.4  535.50
  5023.4  539.47  5136.1  541.82  5486.0  543.98  5586.0  542.97  5813.0  544.61
  5850.0  543.22  5892.1  544.69  5900.1  543.46  6212.9  548.14  6268.2  547.55
#Mann=6,-1,0
  3580.7   0.075       0  3809.3    0.05       0  3960.9   0.075       0
  3965.8    0.05       0  4991.4    0.03       0  4995.4    0.05       0
Bank Sta=4991.4,4995.4
Exp/Cntr=0.3,0.1

Chan Stop Cuts=-1