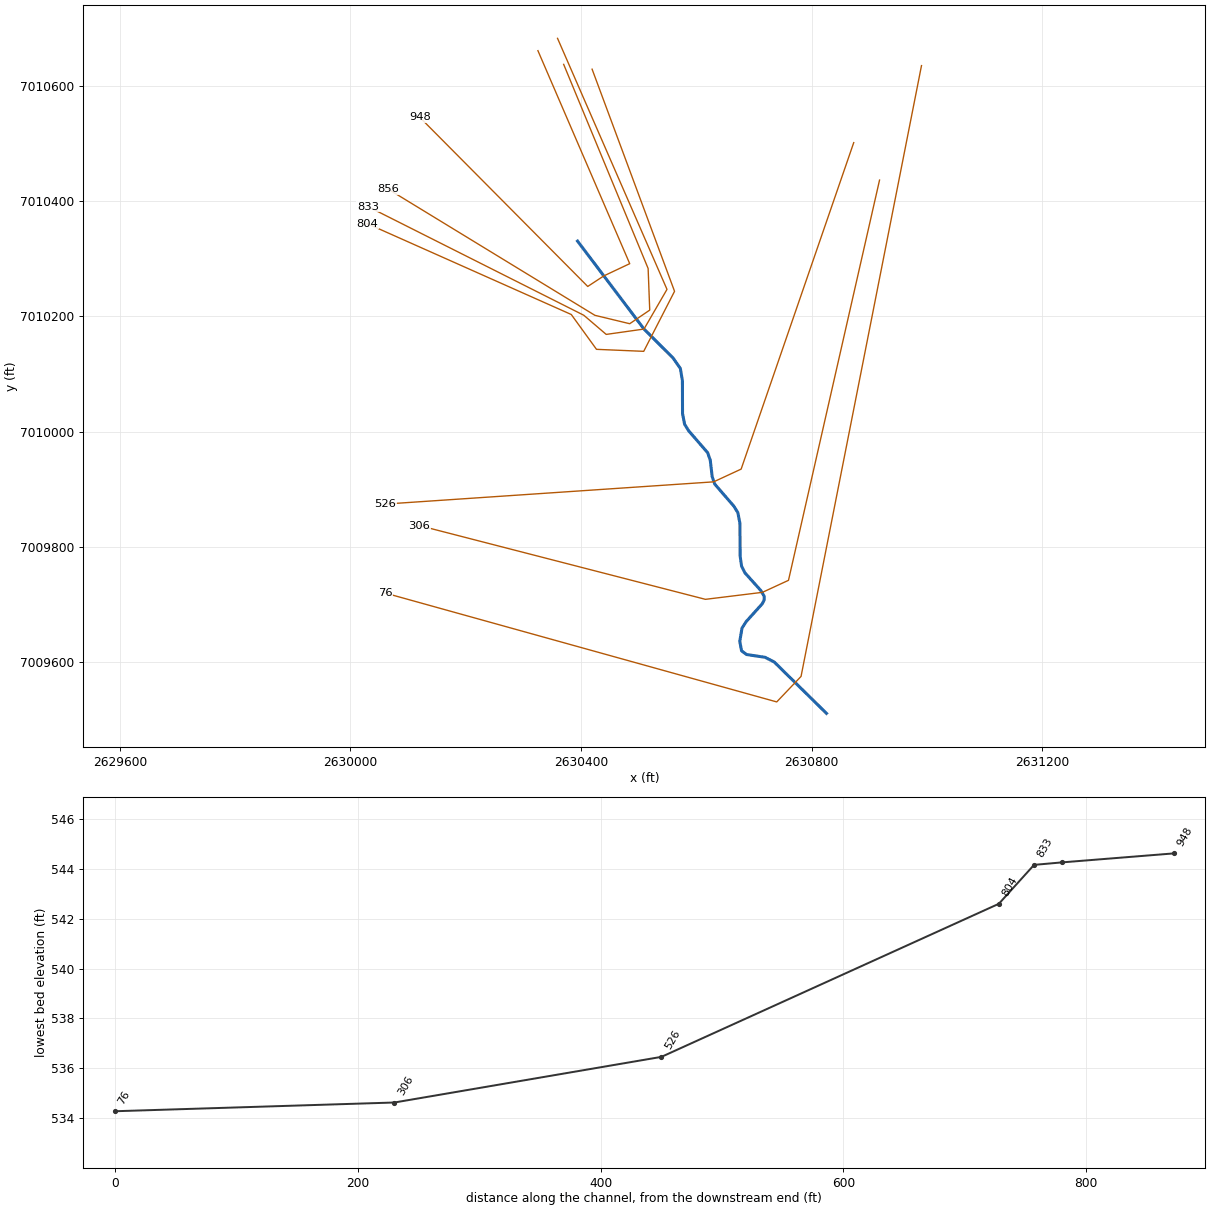
--- Hackberry Creek Tributary 9.prj (project) ---

Proj Title=Hackberry Creek Tributary 9 Base Level Engineering
Current Plan=p01
Default Exp/Contr=0.3,0.1
English Units
Geom File=g01
Flow File=f01
Plan File=p01
Y Axis Title=Elevation
X Axis Title(PF)=Main Channel Distance
X Axis Title(XS)=Station
BEGIN DESCRIPTION:
Hackberry Creek Tributary 9
END DESCRIPTION:
DSS Export Rating Curves= 0
DSS Export Rating Curve Sorted= 0
DSS Export Volume Flow Curves= 0
DXF OffsetX= 0
DXF OffsetY= 0
DXF ScaleX= 1
DXF ScaleY= 10

--- Hackberry Creek Tributary 9.p01 (plan) ---

Plan Title=Multiple Run
Short Identifier=Multiple
Geom File=g01
Flow File=f01
Subcritical Flow
K Sum by GR= 0
Std Step Tol= 0.01
Critical Tol= 0.01
Num of Std Step Trials= 20
Max Error Tol= 0.3
Flow Tol Ratio= 0.001
Split Flow NTrial= 30
Split Flow Tol= 0.02
Split Flow Ratio= 0.02
Log Output Level= 0
Friction Slope Method= 1
Unsteady Friction Slope Method= 2
Unsteady Bridges Friction Slope Method= 1
Parabolic Critical Depth
Global Vel Dist=  1 , 1 , 1
Global Log Level= 0
CheckData=True
Encroach Param= -1, 0, 0, 0
BEGIN DESCRIPTION:
Multiple Run
END DESCRIPTION:

--- Hackberry Creek Tributary 9.f01 (steady flow) ---

Flow Title=Multiple
Program Version=4.10
Number of Profiles= 7
Profile Names=10-year,25-year,50-year,1pct_min,100-year,1pct_plu,500-year
River Rch & RM=Hackberry Creek,Reach-1         ,948
     173     213     242     138     275     549     352
Boundary for River Rch & Prof#=Hackberry Creek,Reach-1         , 1
Up Type= 0
Dn Type= 3
Dn Slope=0.0015
Boundary for River Rch & Prof#=Hackberry Creek,Reach-1         , 2
Up Type= 0
Dn Type= 3
Dn Slope=0.0015
Boundary for River Rch & Prof#=Hackberry Creek,Reach-1         , 3
Up Type= 0
Dn Type= 3
Dn Slope=0.0015
Boundary for River Rch & Prof#=Hackberry Creek,Reach-1         , 4
Up Type= 0
Dn Type= 3
Dn Slope=0.0015
Boundary for River Rch & Prof#=Hackberry Creek,Reach-1         , 5
Up Type= 0
Dn Type= 3
Dn Slope=0.0015
Boundary for River Rch & Prof#=Hackberry Creek,Reach-1         , 6
Up Type= 0
Dn Type= 3
Dn Slope=0.0015
Boundary for River Rch & Prof#=Hackberry Creek,Reach-1         , 7
Up Type= 0
Dn Type= 3
Dn Slope=0.0015
DSS Import GetInterval= 0
DSS Import GetPeak= 0
DSS Import FillOption= 0

--- Hackberry Creek Tributary 9.g01 (geometry) ---

Geom Title=Existing Conditions

River Reach=Hackberry Creek ,Reach-1
Reach XY= 30
      2630394.04      7010330.47      2630509.37      7010177.84
      2630559.64      7010127.80      2630572.44      7010109.52
      2630576.01      7010088.28      2630576.23      7010031.10
      2630579.83      7010012.59      2630586.84      7010001.35
      2630619.89      7009963.18      2630624.33      7009950.31
      2630627.67      7009921.69      2630632.11      7009908.82
      2630665.16      7009870.65      2630672.18      7009859.41
      2630675.78      7009840.90      2630676.19      7009783.72
      2630678.67      7009766.48      2630684.50      7009754.83
      2630712.04      7009724.19      2630717.89      7009714.27
      2630717.87      7009707.65      2630714.44      7009701.02
      2630686.80      7009670.41      2630679.42      7009658.99
      2630675.55      7009635.91      2630678.66      7009619.49
      2630687.36      7009613.10      2630719.36      7009608.31
      2630735.33      7009600.17      2630826.00      7009511.00

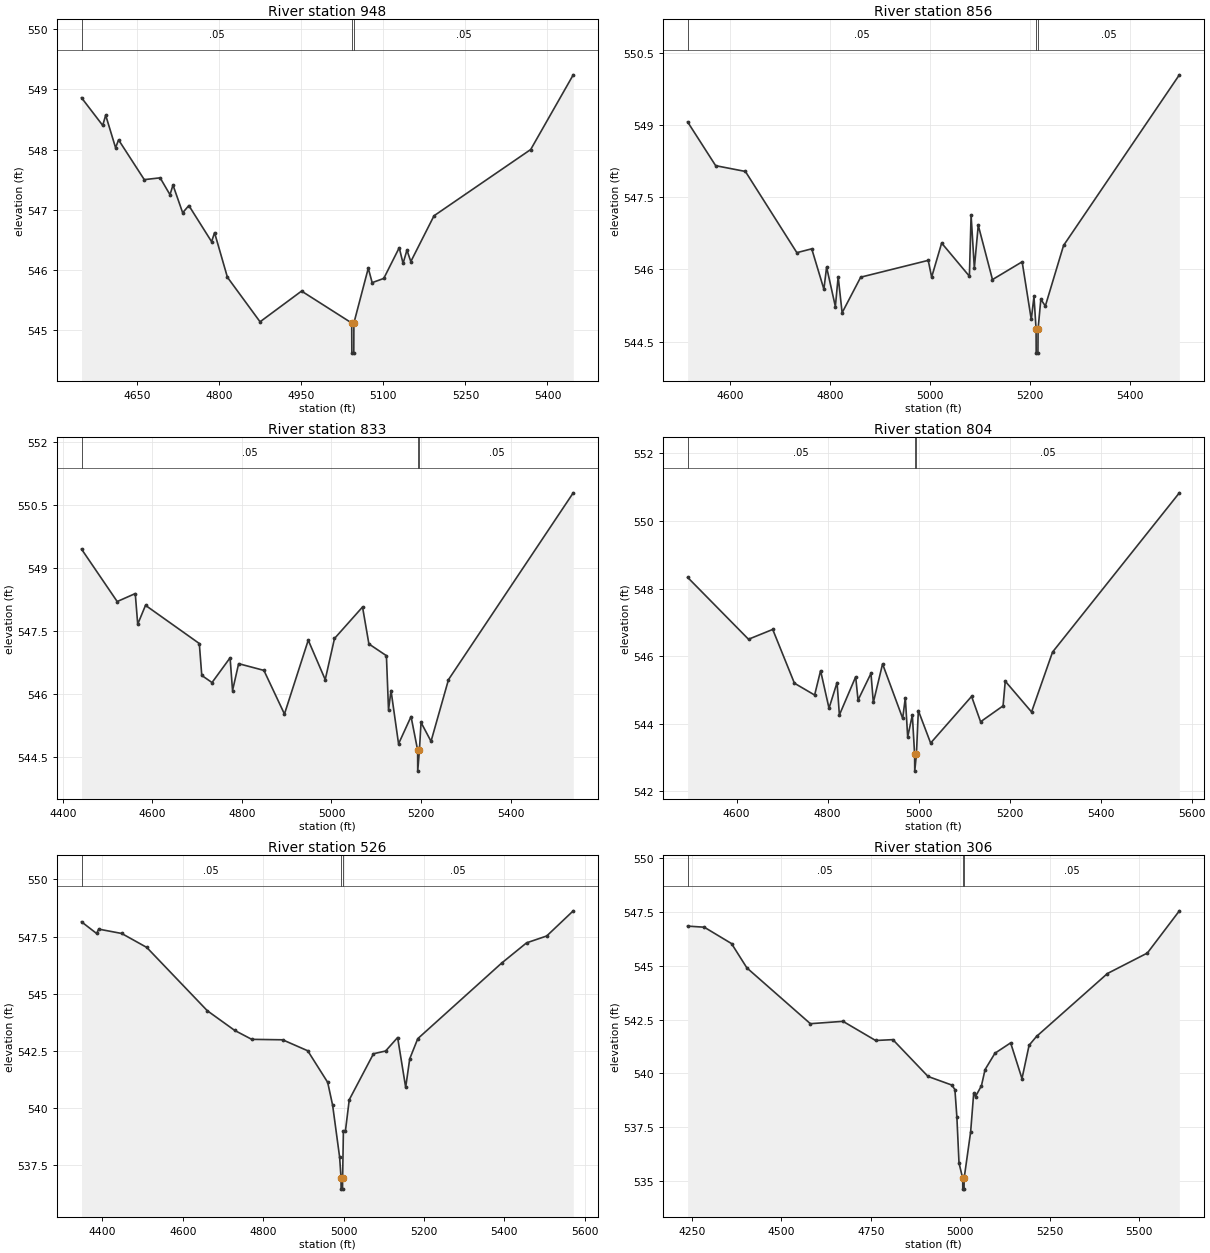
Type RM Length L Ch R = 1,948,92,92,92
BEGIN DESCRIPTION:
Mapping XS 215e9b30
END DESCRIPTION:
XS GIS Cut Line= 5
      2630325.31      7010660.86      2630484.59      7010291.29
      2630439.67      7010270.08      2630411.73      7010251.74
      2630120.25      7010545.29
#Sta/Elev= 30
  4547.9  548.86  4586.7  548.40  4592.1  548.57  4610.2  548.03  4615.7  548.16
  4662.7  547.50  4691.7  547.53  4709.7  547.25  4715.2  547.41  4732.9  546.95
  4744.2  547.07  4785.8  546.47  4791.2  546.62  4814.7  545.88  4874.4  545.14
  4950.3  545.65  5042.0  545.12  5042.3  544.62  5045.8  544.62  5046.0  545.12
  5072.3  546.03  5079.4  545.79  5100.6  545.86  5128.9  546.37  5135.9  546.11
  5143.0  546.33  5150.1  546.14  5192.5  546.90  5369.3  548.00  5447.1  549.24
#Mann=3,-1,0
  4547.9    0.05       0  5042.0    0.03       0  5046.0    0.05       0
Bank Sta=5042,5046
Exp/Cntr=0.3,0.1

Type RM Length L Ch R = 1,856,23,23,23
BEGIN DESCRIPTION:
Mapping XS a7238f3c
END DESCRIPTION:
XS GIS Cut Line= 6
      2630370.01      7010637.08      2630516.53      7010282.93
      2630519.31      7010210.71      2630484.59      7010187.10
      2630424.17      7010201.68      2630065.82      7010420.44
#Sta/Elev= 30
  4515.6  549.07  4571.6  548.16  4631.0  548.04  4733.8  546.35  4763.5  546.43
  4787.8  545.59  4793.2  546.05  4810.7  545.23  4816.3  545.85  4824.2  545.10
  4861.3  545.84  4996.2  546.19  5003.0  545.84  5023.0  546.55  5078.4  545.86
  5081.8  547.13  5088.3  546.03  5096.1  546.92  5124.5  545.79  5183.8  546.16
  5202.0  544.96  5207.4  545.44  5211.6  544.76  5211.8  544.26  5215.3  544.26
  5215.6  544.76  5221.1  545.38  5230.1  545.24  5266.5  546.50  5497.8  550.05
#Mann=3,-1,0
  4515.6    0.05       0  5211.6    0.03       0  5215.6    0.05       0
Bank Sta=5211.6,5215.6
Exp/Cntr=0.3,0.1

Type RM Length L Ch R = 1,833,29,29,29
BEGIN DESCRIPTION:
Hackberry Creek Tributary 9 5.0
END DESCRIPTION:
XS GIS Cut Line= 6
      2630359.34      7010682.27      2630549.26      7010246.68
      2630509.37      7010177.84      2630443.81      7010168.55
      2630404.92      7010201.78      2630030.45      7010390.31
#Sta/Elev= 30
  4442.0  549.45  4521.7  548.20  4562.0  548.39  4567.5  547.66  4584.9  548.11
  4705.0  547.20  4710.5  546.44  4733.4  546.27  4773.7  546.86  4779.2  546.08
  4792.8  546.72  4849.2  546.56  4895.1  545.52  4948.2  547.28  4986.1  546.34
  5006.8  547.32  5069.4  548.07  5083.6  547.19  5122.7  546.91  5127.4  545.62
  5133.0  546.08  5149.8  544.81  5177.7  545.46  5192.4  544.66  5192.6  544.16
  5196.4  544.66  5200.0  545.32  5222.3  544.87  5261.3  546.34  5539.8  550.79
#Mann=3,-1,0
  4442.0    0.05       0  5192.4    0.03       0  5196.4    0.05       0
Bank Sta=5192.4,5196.4
Exp/Cntr=0.3,0.1

Type RM Length L Ch R = 1,804,278,278,278
BEGIN DESCRIPTION:
Mapping XS 1302c3bb
END DESCRIPTION:
XS GIS Cut Line= 6
      2630419.32      7010628.74      2630562.37      7010243.35
      2630508.89      7010139.18      2630426.95      7010142.65
      2630383.20      7010203.07      2630029.32      7010360.65
#Sta/Elev= 30
  4492.5  548.33  4626.3  546.50  4679.5  546.79  4727.2  545.20  4771.6  544.85
  4784.7  545.57  4803.2  544.46  4820.9  545.22  4826.0  544.26  4861.8  545.39
  4867.0  544.70  4895.4  545.49  4900.6  544.63  4920.9  545.77  4965.1  544.16
  4970.9  544.77  4976.1  543.61  4986.3  544.26  4991.3  543.10  4991.6  542.60
  4995.3  543.10  4999.5  544.39  5026.5  543.43  5116.5  544.81  5136.3  544.06
  5185.7  544.53  5190.5  545.26  5248.3  544.35  5294.4  546.12  5573.1  550.83
#Mann=3,-1,0
  4492.5    0.05       0  4991.3    0.03       0  4995.3    0.05       0
Bank Sta=4991.3,4995.3
Exp/Cntr=0.3,0.1

Type RM Length L Ch R = 1,526,220,220,220
BEGIN DESCRIPTION:
Hackberry Creek Tributary 9 2.0
END DESCRIPTION:
XS GIS Cut Line= 4
      2630873.26      7010501.30      2630677.93      7009934.85
      2630630.19      7009912.73      2630060.19      7009874.14
#Sta/Elev= 30
  4348.2  548.15  4385.7  547.64  4391.0  547.83  4448.1  547.64  4510.5  547.03
  4661.2  544.26  4729.3  543.40  4771.6  543.01  4848.5  542.99  4910.9  542.51
  4960.5  541.13  4972.8  540.13  4990.2  537.86  4993.7  536.96  4993.9  536.46
  4997.4  536.46  4997.7  536.96  4999.6  539.00  5004.6  539.00  5014.2  540.37
  5074.4  542.38  5104.6  542.50  5134.5  543.09  5154.5  540.91  5164.6  542.16
  5184.6  543.04  5392.9  546.34  5455.2  547.23  5505.3  547.53  5571.3  548.63
#Mann=3,-1,0
  4348.2    0.05       0  4993.7    0.03       0  4997.7    0.05       0
Bank Sta=4993.7,4997.7
Exp/Cntr=0.3,0.1

Type RM Length L Ch R = 1,306,230,230,230
BEGIN DESCRIPTION:
Mapping XS 6123e8cb
END DESCRIPTION:
XS GIS Cut Line= 5
      2630918.06      7010436.31      2630760.07      7009741.86
      2630714.93      7009721.03      2630615.97      7009708.87
      2630119.33      7009836.93
#Sta/Elev= 30
  4237.6  546.84  4284.1  546.79  4360.3  546.03  4403.3  544.90  4580.7  542.31
  4671.9  542.42  4763.1  541.53  4811.3  541.57  4909.7  539.86  4976.3  539.46
  4984.7  539.25  4990.2  537.98  4996.2  535.84  5006.5  535.13  5006.8  534.63
  5010.3  534.63  5010.5  535.13  5028.7  537.29  5037.2  539.08  5042.3  538.93
  5058.9  539.43  5069.0  540.18  5096.7  540.94  5140.5  541.42  5172.2  539.76
  5192.1  541.31  5212.9  541.72  5411.1  544.64  5522.6  545.59  5612.1  547.55
#Mann=3,-1,0
  4237.6    0.05       0  5006.5    0.03       0  5010.5    0.05       0
Bank Sta=5006.5,5010.5
Exp/Cntr=0.3,0.1

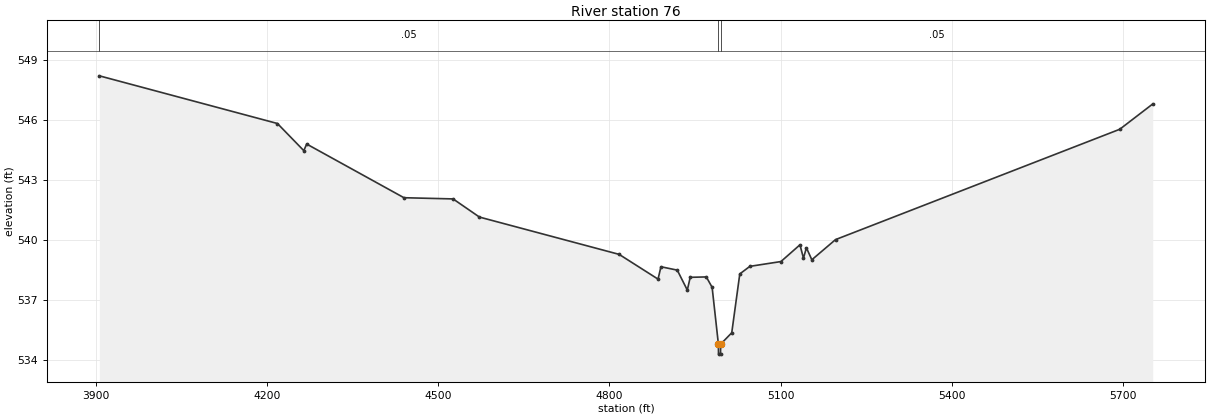
Type RM Length L Ch R = 1,76,0,0,0
BEGIN DESCRIPTION:
Hackberry Creek Tributary 9 1.0
END DESCRIPTION:
XS GIS Cut Line= 4
      2630990.86      7010634.94      2630781.88      7009575.15
      2630739.69      7009530.88      2630060.22      7009719.79
#Sta/Elev= 30
  3905.9  548.23  4218.1  545.84  4264.3  544.48  4269.4  544.81  4439.9  542.12
  4526.0  542.06  4572.2  541.15  4817.1  539.28  4885.3  538.04  4890.4  538.66
  4919.0  538.49  4936.6  537.49  4941.7  538.13  4969.9  538.15  4980.1  537.63
  4991.1  534.78  4991.3  534.28  4994.8  534.28  4995.1  534.78  5014.5  535.35
  5028.6  538.30  5046.3  538.68  5100.7  538.92  5134.1  539.76  5140.2  539.09
  5145.4  539.61  5154.9  539.01  5196.4  540.02  5694.6  545.55  5752.5  546.82
#Mann=3,-1,0
  3905.9    0.05       0  4991.1    0.03       0  4995.1    0.05       0
Bank Sta=4991.1,4995.1
Exp/Cntr=0.3,0.1

Chan Stop Cuts=-1