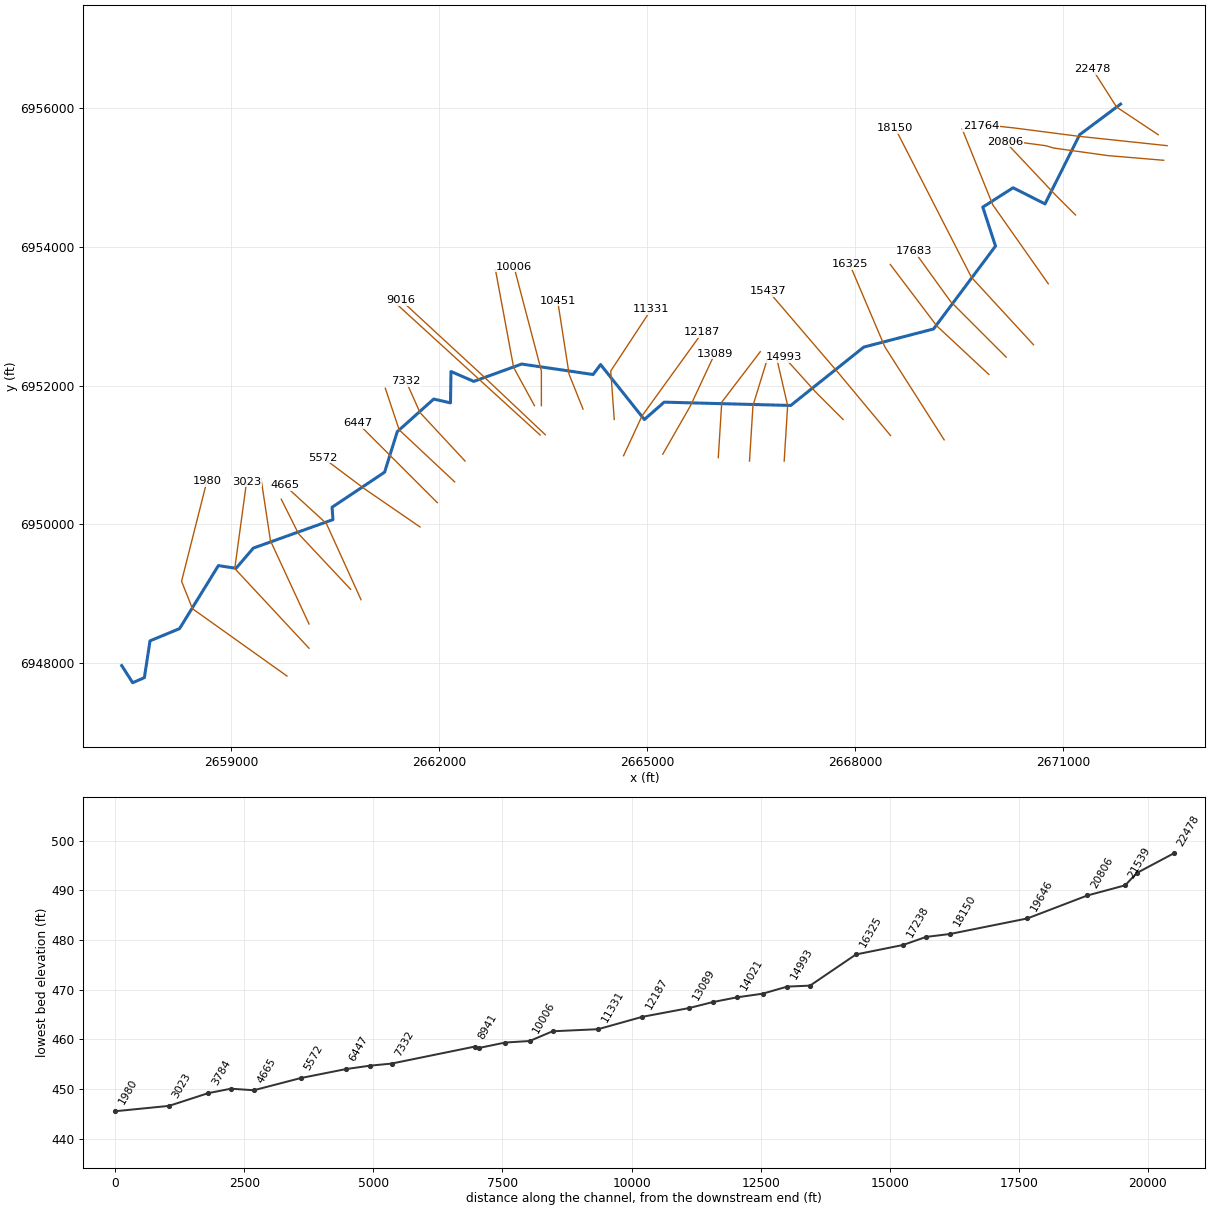
--- Hardin Branch.prj (project) ---

Proj Title=Hardin Branch Base Level Engineering
Current Plan=p01
Default Exp/Contr=0.3,0.1
English Units
Geom File=g01
Flow File=f01
Plan File=p01
BEGIN DESCRIPTION:
Hardin Branch
END DESCRIPTION:

--- Hardin Branch.p01 (plan) ---

Plan Title=Multiple Run
Short Identifier=Multiple
Geom File=g01
Flow File=f01
Subcritical Flow
K Sum by GR= 0
Std Step Tol= 0.01
Critical Tol= 0.01
Num of Std Step Trials= 20
Max Error Tol= 0.3
Flow Tol Ratio= 0.001
Split Flow NTrial= 30
Split Flow Tol= 0.02
Split Flow Ratio= 0.02
Log Output Level= 0
Friction Slope Method= 1
Unsteady Friction Slope Method= 2
Unsteady Bridges Friction Slope Method= 1
Parabolic Critical Depth
Global Vel Dist=  1 , 1 , 1
Global Log Level= 0
CheckData=True
Encroach Param= -1, 0, 0, 0
BEGIN DESCRIPTION:
Multiple Run
END DESCRIPTION:

--- Hardin Branch.f01 (steady flow) ---

Flow Title=Multiple
Number of Profiles=7
Profile Names=10-year,25-year,50-year,1pct_min,100-year,1pct_plu,500-year
River Rch & RM= Hardin Branch,Reach-1,22478
     527     701     841     500     999    1992    1407
River Rch & RM= Hardin Branch,Reach-1,21539
     745    1011    1228     739    1475    2943    2129
River Rch & RM= Hardin Branch,Reach-1,18150
    1065    1466    1797    1091    2176    4342    3191
River Rch & RM= Hardin Branch,Reach-1,12187
    1300    1799    2212    1345    2683    5354    3951
River Rch & RM= Hardin Branch,Reach-1,4665
    1489    2072    2558    1561    3114    6213    4617
Boundary for River Rch & Prof#=Hardin Branch,Reach-1,1
Up Type=0
Dn Type=3
Dn Slope=0.005
Boundary for River Rch & Prof#=Hardin Branch,Reach-1,2
Up Type=0
Dn Type=3
Dn Slope=0.005
Boundary for River Rch & Prof#=Hardin Branch,Reach-1,3
Up Type=0
Dn Type=3
Dn Slope=0.005
Boundary for River Rch & Prof#=Hardin Branch,Reach-1,4
Up Type=0
Dn Type=3
Dn Slope=0.005
Boundary for River Rch & Prof#=Hardin Branch,Reach-1,5
Up Type=0
Dn Type=3
Dn Slope=0.005
Boundary for River Rch & Prof#=Hardin Branch,Reach-1,6
Up Type=0
Dn Type=3
Dn Slope=0.005
Boundary for River Rch & Prof#=Hardin Branch,Reach-1,7
Up Type=0
Dn Type=3
Dn Slope=0.005

--- Hardin Branch.g01 (geometry) ---

Geom Title=Existing Conditions

River Reach=Hardin Branch,Reach-1
Reach XY= 30
      2671826.00      6956061.00      2671236.48      6955620.80
      2670735.79      6954621.43      2670275.70      6954853.80
      2669838.95      6954574.64      2670022.39      6954012.50
      2669128.54      6952816.70      2668123.58      6952555.59
      2667070.07      6951713.24      2665246.10      6951761.10
      2664960.43      6951510.69      2664329.03      6952303.25
      2664221.35      6952159.97      2663191.28      6952310.63
      2662501.12      6952060.71      2662172.73      6952203.18
      2662165.65      6951750.76      2661923.63      6951805.63
      2661398.30      6951334.74      2661215.96      6950750.93
      2660458.69      6950244.72      2660471.24      6950066.58
      2659323.03      6949655.48      2659074.36      6949364.14
      2658819.81      6949403.19      2658259.73      6948493.78
      2657833.98      6948317.37      2657753.14      6947787.16
      2657584.15      6947713.49      2657426.00      6947961.00

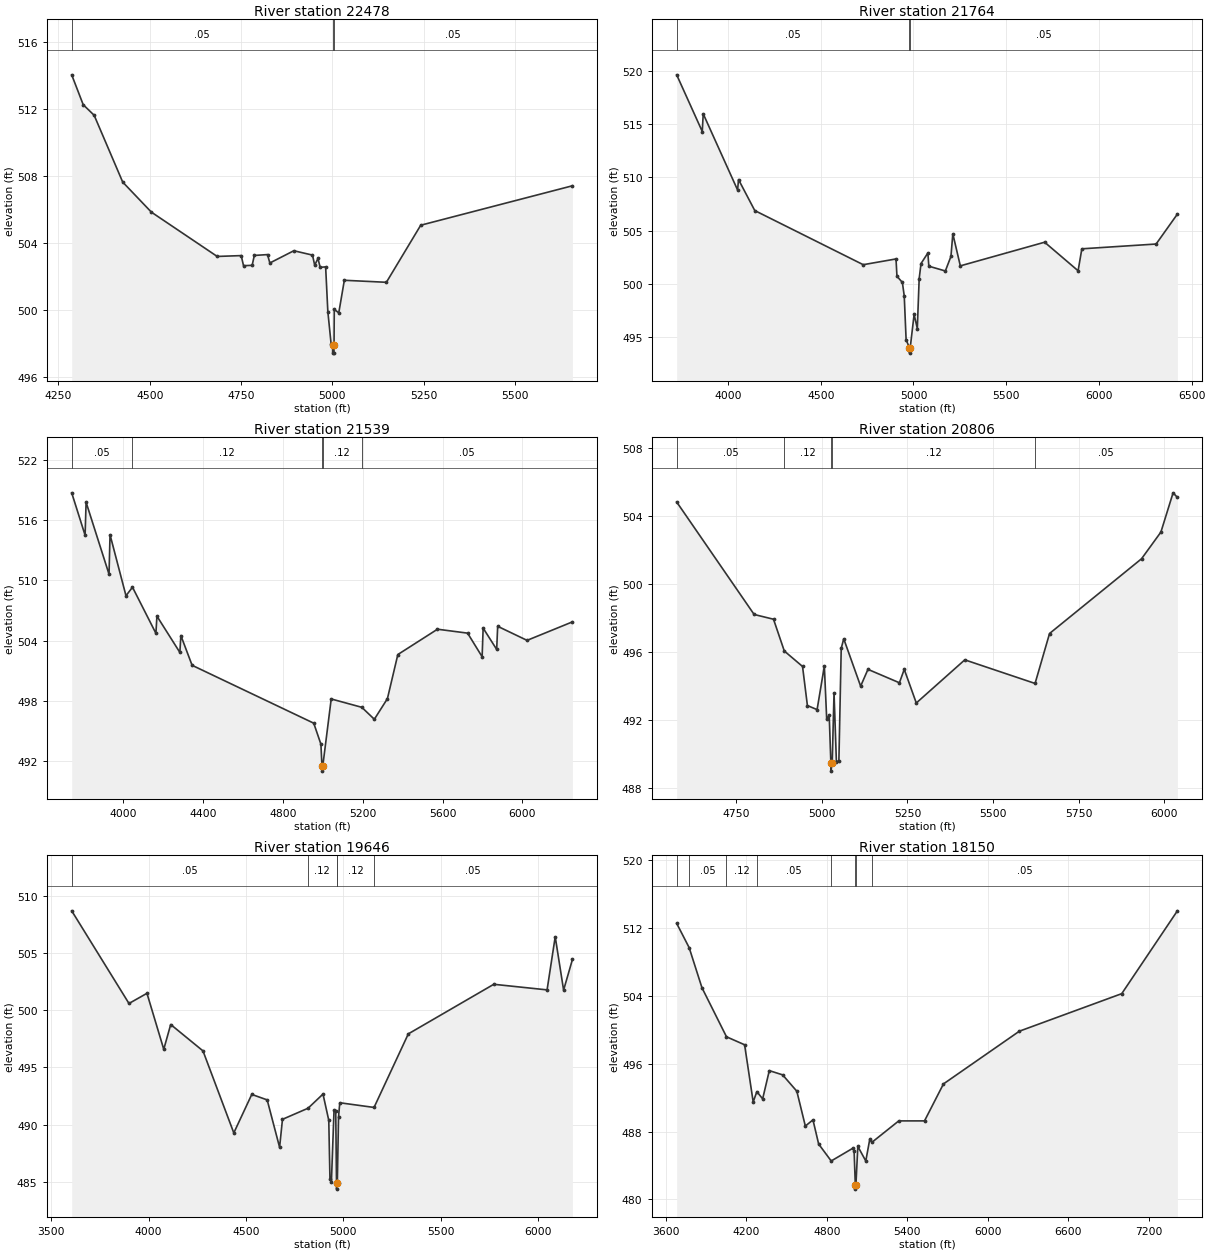
Type RM Length L Ch R = 1,22478,714,714,714
BEGIN DESCRIPTION:
Hardin Branch 43.0
END DESCRIPTION:
XS GIS Cut Line= 3
      2672367.55      6955618.77      2671767.53      6956018.79
      2671418.42      6956567.39
#Sta/Elev= 30
  4286.3  514.03  4317.8  512.25  4347.8  511.62  4426.0  507.64  4504.5  505.85
  4684.8  503.21  4750.5  503.26  4756.9  502.66  4780.5  502.68  4786.5  503.27
  4822.6  503.32  4829.0  502.82  4894.7  503.55  4945.8  503.29  4951.8  502.69
  4960.8  503.09  4966.8  502.56  4981.8  502.59  4987.8  499.93  4996.8  498.00
  5000.8  497.95  5001.1  497.45  5004.6  497.45  5004.8  497.95  5005.4  500.05
  5017.8  499.85  5033.0  501.79  5148.2  501.67  5242.2  505.07  5657.7  507.42
#Mann=3,-1,0
  4286.3    0.05       0  5000.8    0.04       0  5004.8    0.05       0
Bank Sta=5000.8,5004.8
Exp/Cntr=0.3,0.1

Type RM Length L Ch R = 1,21764,225,225,225
BEGIN DESCRIPTION:
Mapping XS 8399fc2e
END DESCRIPTION:
XS GIS Cut Line= 5
      2672496.37      6955461.25      2671226.38      6955595.84
      2670288.12      6955717.15      2669927.87      6955756.21
      2669813.57      6955745.90
#Sta/Elev= 30
  3722.9  519.62  3860.9  514.30  3866.0  515.96  4051.4  508.81  4056.4  509.79
  4144.1  506.88  4728.9  501.80  4905.7  502.34  4910.8  500.71  4940.0  500.14
  4950.1  498.87  4960.2  494.76  4978.3  494.00  4978.5  493.50  4982.3  494.00
  5003.3  497.13  5020.6  495.81  5030.6  500.49  5040.7  501.91  5077.6  502.90
  5082.7  501.66  5171.8  501.21  5202.0  502.58  5212.1  504.70  5252.5  501.69
  5707.2  503.91  5887.7  501.23  5907.9  503.29  6308.4  503.74  6423.2  506.55
#Mann=3,-1,0
  3722.9    0.05       0  4978.3    0.05       0  4982.3    0.05       0
Bank Sta=4978.3,4982.3
Exp/Cntr=0.3,0.1

Type RM Length L Ch R = 1,21539,733,733,733
BEGIN DESCRIPTION:
Mapping XS 0d2b93c9
END DESCRIPTION:
XS GIS Cut Line= 6
      2672446.95      6955250.31      2671643.15      6955317.84
      2670859.30      6955427.22      2670749.54      6955460.13
      2670256.83      6955526.35      2669959.13      6955541.88
#Sta/Elev= 30
  3742.1  518.71  3809.2  514.49  3814.2  517.77  3929.1  510.61  3934.1  514.54
  4014.0  508.47  4046.6  509.32  4163.9  504.73  4169.0  506.44  4283.9  502.83
  4288.9  504.51  4345.2  501.55  4954.5  495.79  4990.4  493.70  4995.7  491.52
  4996.0  491.02  4999.7  491.52  5042.0  498.20  5195.1  497.37  5258.0  496.18
  5323.5  498.23  5375.7  502.62  5574.3  505.14  5725.1  504.75  5797.9  502.40
  5803.0  505.25  5870.8  503.13  5875.8  505.43  6023.0  504.03  6250.2  505.87
#Mann=5,-1,0
  3742.1    0.05       0  4046.6    0.12       0  4995.7    0.07       0
  4999.7    0.12       0  5195.1    0.05       0
Bank Sta=4995.7,4999.7
Exp/Cntr=0.3,0.1

Type RM Length L Ch R = 1,20806,1160,1160,1160
BEGIN DESCRIPTION:
Hardin Branch 40.0
END DESCRIPTION:
XS GIS Cut Line= 3
      2671176.04      6954460.96      2670876.00      6954761.00
      2670164.29      6955517.25
#Sta/Elev= 30
  4575.9  504.81  4802.2  498.19  4858.8  497.91  4890.3  496.04  4943.6  495.13
  4957.8  492.83  4986.1  492.59  5007.3  495.15  5014.2  492.01  5021.5  492.27
  5026.3  489.47  5026.6  488.97  5030.3  489.47  5035.6  493.58  5042.5  489.52
  5049.8  489.59  5056.6  496.19  5063.9  496.76  5113.3  493.97  5134.7  494.96
  5226.6  494.17  5240.7  494.96  5275.9  492.98  5417.6  495.52  5622.9  494.13
  5665.2  497.07  5934.0  501.47  5990.5  503.04  6026.1  505.35  6038.7  505.08
#Mann=5,-1,0
  4575.9    0.05       0  4890.3    0.12       0  5026.3    0.07       0
  5030.3    0.12       0  5622.9    0.05       0
Bank Sta=5026.3,5030.3
Exp/Cntr=0.3,0.1

Type RM Length L Ch R = 1,19646,1496,1496,1496
BEGIN DESCRIPTION:
Hardin Branch 37.0
END DESCRIPTION:
XS GIS Cut Line= 3
      2670782.89      6953469.03      2669981.15      6954610.62
      2669540.85      6955703.02
#Sta/Elev= 30
  3605.0  508.71  3899.3  500.60  3991.7  501.49  4078.0  496.59  4113.7  498.76
  4279.5  496.45  4437.9  489.27  4530.2  492.64  4609.4  492.16  4673.2  488.01
  4688.0  490.46  4819.3  491.43  4896.2  492.67  4925.9  490.37  4932.0  485.21
  4939.4  485.01  4952.9  491.25  4961.6  491.22  4965.7  484.85  4965.9  484.35
  4969.7  484.85  4976.0  490.67  4982.5  491.91  5158.5  491.50  5334.6  497.94
  5773.7  502.28  6047.6  501.79  6089.4  506.44  6132.5  501.77  6177.8  504.45
#Mann=5,-1,0
  3605.0    0.05       0  4819.3    0.12       0  4965.7    0.07       0
  4969.7    0.12       0  5158.5    0.05       0
Bank Sta=4965.7,4969.7
Exp/Cntr=0.3,0.1

Type RM Length L Ch R = 1,18150,467,467,467
BEGIN DESCRIPTION:
Hardin Branch 36.0
END DESCRIPTION:
XS GIS Cut Line= 3
      2670570.25      6952589.09      2669676.00      6953561.00
      2668577.19      6955710.62
#Sta/Elev= 30
  3679.5  512.57  3772.5  509.71  3868.0  504.98  4051.1  499.19  4186.1  498.25
  4250.2  491.50  4277.5  492.72  4320.8  491.87  4370.4  495.20  4469.7  494.70
  4575.7  492.77  4639.2  488.66  4696.0  489.39  4738.5  486.54  4832.1  484.54
  4993.1  486.04  5003.0  485.71  5011.9  481.72  5012.3  481.22  5016.4  481.72
  5030.7  486.26  5090.1  484.54  5119.6  487.09  5135.6  486.74  5336.1  489.27
  5528.1  489.27  5669.4  493.63  6235.6  499.85  6999.3  504.28  7414.4  514.05
#Mann=8,-1,0
  3679.5    0.12       0  3772.5    0.05       0  4051.1    0.12       0
  4277.5    0.05       0  4832.1    0.12       0  5011.9    0.07       0
  5016.4    0.12       0  5135.6    0.05       0
Bank Sta=5011.9,5016.4
Exp/Cntr=0.3,0.1

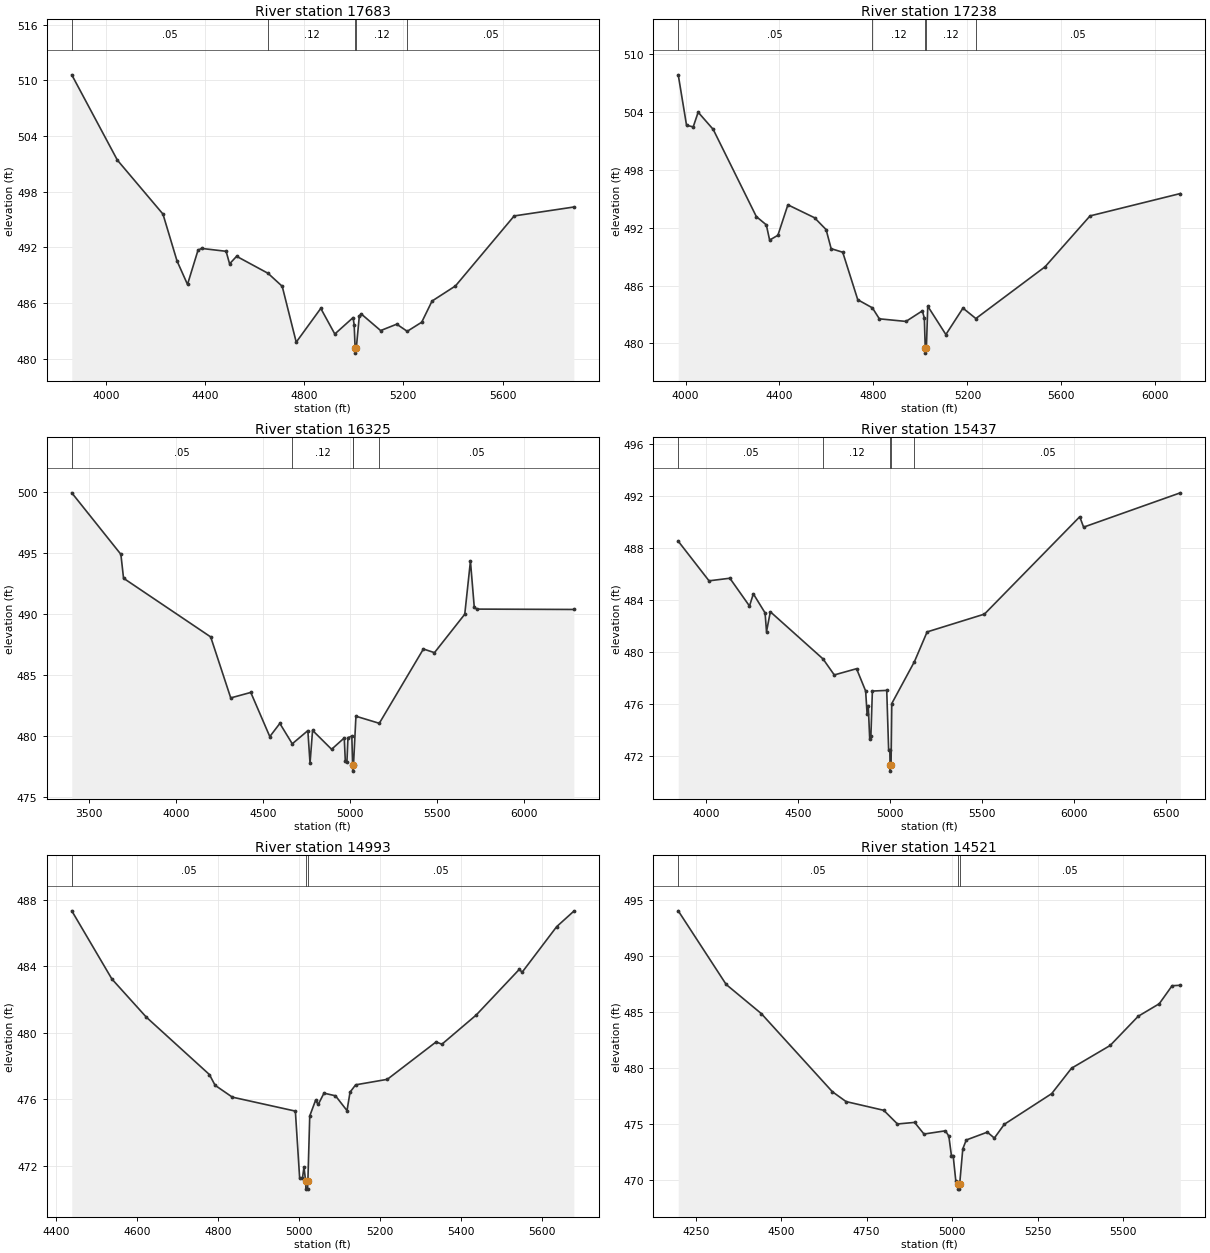
Type RM Length L Ch R = 1,17683,445,445,445
BEGIN DESCRIPTION:
Hardin Branch 35.0
END DESCRIPTION:
XS GIS Cut Line= 3
      2670176.02      6952410.98      2669376.00      6953211.00
      2668853.18      6953935.20
#Sta/Elev= 30
  3863.0  510.60  4046.9  501.41  4230.7  495.60  4287.3  490.56  4329.7  488.02
  4372.1  491.71  4386.3  491.90  4485.3  491.59  4499.4  490.24  4527.7  491.05
  4654.4  489.22  4711.6  487.82  4768.1  481.80  4867.1  485.44  4923.7  482.68
  4997.5  484.45  5001.8  483.65  5005.7  481.12  5006.1  480.62  5010.2  481.12
  5022.6  484.64  5031.2  484.82  5108.5  483.05  5173.5  483.74  5215.7  482.97
  5274.1  483.95  5315.8  486.23  5410.3  487.86  5647.0  495.40  5887.6  496.36
#Mann=5,-1,0
  3863.0    0.05       0  4654.4    0.12       0  5005.7    0.07       0
  5010.2    0.12       0  5215.7    0.05       0
Bank Sta=5005.7,5010.2
Exp/Cntr=0.3,0.1

Type RM Length L Ch R = 1,17238,913,913,913
BEGIN DESCRIPTION:
Hardin Branch 34.0
END DESCRIPTION:
XS GIS Cut Line= 3
      2669926.02      6952160.98      2669176.00      6952861.00
      2668505.33      6953747.43
#Sta/Elev= 30
  3969.0  507.88  4004.4  502.64  4032.8  502.48  4053.8  504.00  4117.8  502.22
  4301.5  493.17  4344.0  492.31  4358.1  490.73  4393.3  491.23  4435.8  494.39
  4549.2  493.05  4598.5  491.82  4620.0  489.84  4669.3  489.47  4733.3  484.54
  4795.5  483.70  4825.2  482.56  4938.5  482.29  5008.5  483.39  5016.8  482.61
  5020.6  479.50  5021.2  479.00  5025.4  479.50  5031.3  483.87  5108.4  480.93
  5181.2  483.67  5236.1  482.59  5530.7  487.96  5722.2  493.24  6106.5  495.56
#Mann=5,-1,0
  3969.0    0.05       0  4795.5    0.12       0  5020.6    0.07       0
  5025.4    0.12       0  5236.1    0.05       0
Bank Sta=5020.6,5025.4
Exp/Cntr=0.3,0.1

Type RM Length L Ch R = 1,16325,888,888,888
BEGIN DESCRIPTION:
Hardin Branch 32.0
END DESCRIPTION:
XS GIS Cut Line= 3
      2669282.06      6951217.55      2668426.00      6952561.00
      2667921.58      6953747.29
#Sta/Elev= 30
  3402.7  499.90  3684.6  494.86  3699.9  492.90  4200.1  488.09  4315.2  483.09
  4430.3  483.54  4539.5  479.92  4597.1  481.00  4668.4  479.33  4757.9  480.41
  4770.4  477.74  4785.0  480.43  4894.2  478.88  4966.9  479.81  4972.9  477.92
  4982.2  477.85  4988.1  479.83  5010.3  479.96  5015.0  477.59  5015.6  477.09
  5019.9  477.59  5033.9  481.59  5168.0  481.01  5421.2  487.10  5484.7  486.80
  5658.6  489.95  5691.2  494.30  5712.9  490.57  5726.6  490.37  6284.8  490.34
#Mann=5,-1,0
  3402.7    0.05       0  4668.4    0.12       0  5015.0    0.07       0
  5019.9    0.12       0  5168.0    0.05       0
Bank Sta=5015,5019.9
Exp/Cntr=0.3,0.1

Type RM Length L Ch R = 1,15437,444,444,444
BEGIN DESCRIPTION:
Hardin Branch 30.0
END DESCRIPTION:
XS GIS Cut Line= 3
      2668509.43      6951278.95      2667776.00      6952161.00
      2666747.34      6953363.39
#Sta/Elev= 30
  3848.0  488.50  4015.4  485.45  4128.7  485.65  4235.4  483.51  4256.3  484.45
  4320.1  482.98  4327.9  481.54  4348.7  483.07  4635.3  479.44  4696.3  478.21
  4817.4  478.69  4866.9  476.97  4874.7  475.20  4881.2  475.80  4889.0  473.27
  4895.5  473.55  4903.4  476.97  4981.5  477.02  4991.9  472.41  4998.4  472.41
  4999.6  471.31  5000.4  470.81  5005.0  471.31  5008.9  476.01  5132.3  479.24
  5201.0  481.52  5512.7  482.89  6030.8  490.38  6051.7  489.58  6577.5  492.22
#Mann=5,-1,0
  3848.0    0.05       0  4635.3    0.12       0  4999.6    0.07       0
  5005.0    0.12       0  5132.3    0.05       0
Bank Sta=4999.6,5005
Exp/Cntr=0.3,0.1

Type RM Length L Ch R = 1,14993,472,472,472
BEGIN DESCRIPTION:
Hardin Branch 29.0
END DESCRIPTION:
XS GIS Cut Line= 3
      2667826.00      6951511.00      2667426.00      6951911.00
      2666975.98      6952411.03
#Sta/Elev= 30
  4439.4  487.34  4538.4  483.24  4623.2  480.95  4778.8  477.50  4793.0  476.85
  4835.4  476.14  4990.9  475.30  5001.5  471.27  5008.4  471.27  5012.2  471.94
  5016.1  471.11  5017.0  470.61  5020.9  470.61  5021.8  471.11  5026.4  475.01
  5040.6  475.94  5047.3  475.70  5061.5  476.38  5089.9  476.22  5118.3  475.33
  5125.8  476.44  5139.6  476.88  5217.7  477.21  5338.1  479.46  5352.3  479.32
  5436.7  481.07  5543.2  483.82  5550.3  483.65  5635.5  486.39  5677.8  487.32
#Mann=3,-1,0
  4439.4    0.05       0  5016.1    0.03       0  5021.8    0.05       0
Bank Sta=5016.1,5021.8
Exp/Cntr=0.3,0.1

Type RM Length L Ch R = 1,14521,500,500,500
BEGIN DESCRIPTION:
Hardin Branch 28.0
END DESCRIPTION:
XS GIS Cut Line= 3
      2666976.00      6950910.97      2667026.00      6951711.00
      2666875.99      6952361.03
#Sta/Elev= 30
  4198.8  494.05  4339.1  487.47  4441.8  484.87  4649.7  477.89  4689.8  477.01
  4800.0  476.23  4840.1  475.01  4890.2  475.15  4917.7  474.11  4980.4  474.40
  4990.4  473.92  4997.9  472.19  5003.0  472.19  5010.7  469.94  5016.2  469.69
  5017.2  469.19  5021.2  469.19  5022.2  469.69  5031.2  472.79  5041.4  473.58
  5103.0  474.28  5123.5  473.75  5152.6  474.98  5291.2  477.72  5349.3  479.99
  5462.2  482.02  5544.3  484.63  5605.9  485.75  5643.5  487.36  5667.5  487.40
#Mann=3,-1,0
  4198.8    0.05       0  5016.2    0.03       0  5022.2    0.05       0
Bank Sta=5016.2,5022.2
Exp/Cntr=0.3,0.1

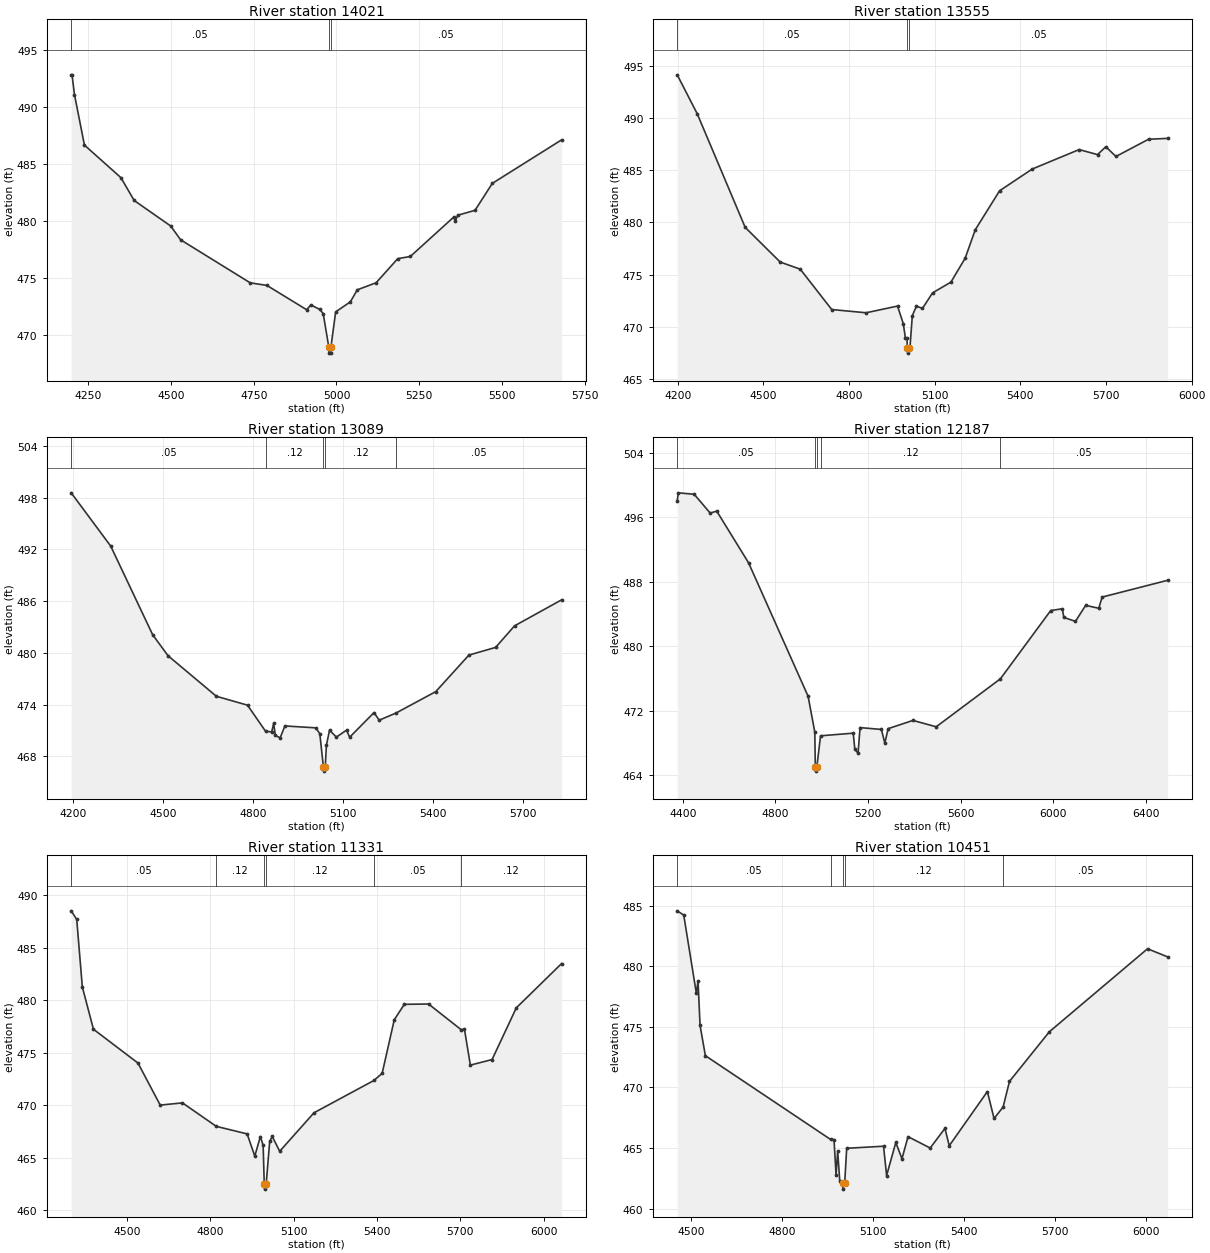
Type RM Length L Ch R = 1,14021,466,466,466
BEGIN DESCRIPTION:
Hardin Branch 27.0
END DESCRIPTION:
XS GIS Cut Line= 3
      2666476.00      6950911.05      2666526.00      6951711.00
      2666726.00      6952361.01
#Sta/Elev= 30
  4198.5  492.81  4201.0  492.81  4208.5  491.07  4238.5  486.66  4348.7  483.81
  4388.8  481.81  4499.0  479.58  4529.1  478.37  4739.5  474.60  4789.6  474.38
  4909.8  472.25  4922.4  472.67  4949.9  472.27  4959.9  471.90  4976.9  468.95
  4977.9  468.45  4982.0  468.45  4983.0  468.95  4997.5  472.06  5041.9  472.94
  5062.8  473.99  5119.7  474.61  5185.1  476.72  5223.0  476.91  5353.8  480.35
  5359.0  480.01  5366.2  480.52  5418.5  480.95  5470.8  483.31  5680.1  487.12
#Mann=3,-1,0
  4198.5    0.05       0  4976.9    0.03       0  4983.0    0.05       0
Bank Sta=4976.9,4983
Exp/Cntr=0.3,0.1

Type RM Length L Ch R = 1,13555,466,466,466
BEGIN DESCRIPTION:
Hardin Branch 26.0
END DESCRIPTION:
XS GIS Cut Line= 3
      2666026.00      6950960.98      2666076.00      6951761.00
      2666631.39      6952489.32
#Sta/Elev= 30
  4198.4  494.12  4268.6  490.39  4436.4  479.53  4559.1  476.21  4629.3  475.53
  4739.5  471.67  4859.7  471.36  4969.9  472.00  4990.0  470.33  4997.5  468.96
  5003.1  468.96  5004.2  468.00  5005.2  467.50  5010.3  468.00  5013.5  468.04
  5021.8  471.09  5036.3  472.00  5057.1  471.77  5092.5  473.26  5156.9  474.29
  5206.8  476.58  5242.2  479.30  5327.4  483.03  5441.7  485.11  5605.9  486.97
  5670.3  486.49  5699.4  487.24  5734.8  486.31  5849.1  487.96  5915.9  488.04
#Mann=3,-1,0
  4198.4    0.05       0  5004.2    0.03       0  5010.3    0.05       0
Bank Sta=5004.2,5010.3
Exp/Cntr=0.3,0.1

Type RM Length L Ch R = 1,13089,902,902,902
BEGIN DESCRIPTION:
Hardin Branch 25.0
END DESCRIPTION:
XS GIS Cut Line= 3
      2665226.01      6951011.02      2665626.00      6951711.00
      2665975.98      6952460.96
#Sta/Elev= 30
  4193.9  498.56  4325.6  492.38  4465.3  482.10  4516.4  479.67  4677.6  474.96
  4781.3  473.93  4841.9  470.88  4861.9  470.84  4868.4  471.81  4874.1  470.42
  4890.0  470.14  4905.8  471.52  5008.8  471.30  5022.2  470.61  5034.0  466.78
  5035.1  466.28  5040.2  466.78  5044.2  469.29  5054.5  471.03  5077.3  470.23
  5111.2  471.03  5121.5  470.21  5202.7  473.07  5220.0  472.19  5275.5  473.01
  5408.4  475.50  5518.8  479.74  5607.8  480.63  5670.9  483.13  5827.7  486.15
#Mann=5,-1,0
  4193.9    0.05       0  4841.9    0.12       0  5034.0    0.07       0
  5040.2    0.12       0  5275.5    0.05       0
Bank Sta=5034,5040.2
Exp/Cntr=0.3,0.1

Type RM Length L Ch R = 1,12187,856,856,856
BEGIN DESCRIPTION:
Hardin Branch 23.0
END DESCRIPTION:
XS GIS Cut Line= 3
      2664660.53      6950988.46      2664926.00      6951561.00
      2665795.84      6952766.07
#Sta/Elev= 30
  4376.0  498.05  4380.7  499.04  4449.4  498.86  4518.2  496.53  4546.6  496.77
  4684.0  490.36  4941.0  473.81  4970.0  469.36  4972.2  465.02  4973.3  464.52
  4978.7  465.02  4994.8  468.90  5135.9  469.23  5142.8  467.23  5156.8  466.75
  5165.3  469.92  5257.4  469.69  5272.1  468.01  5286.8  469.79  5393.6  470.81
  5494.1  470.02  5771.2  475.97  5988.5  484.44  6038.8  484.66  6045.0  483.58
  6095.3  483.10  6139.4  485.08  6195.9  484.72  6210.6  486.11  6493.3  488.19
#Mann=5,-1,0
  4376.0    0.05       0  4972.2    0.07       0  4978.7    0.05       0
  4994.8    0.12       0  5771.2    0.05       0
Bank Sta=4972.2,4978.7
Exp/Cntr=0.3,0.1

Type RM Length L Ch R = 1,11331,880,880,880
BEGIN DESCRIPTION:
Hardin Branch 21.0
END DESCRIPTION:
XS GIS Cut Line= 3
      2664526.00      6951511.03      2664476.00      6952211.00
      2665061.24      6953101.45
#Sta/Elev= 30
  4298.0  488.49  4318.0  487.67  4338.1  481.26  4378.2  477.23  4538.6  474.02
  4618.8  470.02  4699.0  470.23  4820.7  468.00  4932.1  467.28  4959.6  465.17
  4979.7  467.03  4989.7  466.20  4993.7  462.53  4994.8  462.03  5000.7  462.53
  5013.3  466.57  5022.4  467.04  5049.4  465.63  5173.0  469.29  5388.8  472.36
  5418.6  473.04  5462.2  478.13  5498.4  479.60  5585.8  479.63  5702.8  477.20
  5715.3  477.21  5736.4  473.82  5814.7  474.35  5902.1  479.27  6065.3  483.48
#Mann=6,-1,0
  4298.0    0.05       0  4820.7    0.12       0  4993.7    0.07       0
  5000.7    0.12       0  5388.8    0.05       0  5702.8    0.12       0
Bank Sta=4993.7,5000.7
Exp/Cntr=0.3,0.1

Type RM Length L Ch R = 1,10451,445,445,445
BEGIN DESCRIPTION:
Hardin Branch 19.0
END DESCRIPTION:
XS GIS Cut Line= 3
      2664075.98      6951661.05      2663876.00      6952161.00
      2663710.01      6953226.48
#Sta/Elev= 30
  4454.0  484.57  4475.5  484.22  4517.2  477.75  4522.6  478.81  4529.3  475.12
  4546.8  472.62  4959.5  465.71  4970.9  465.69  4977.7  462.78  4983.0  464.75
  4989.8  462.29  4999.0  462.11  5000.1  461.61  5006.1  462.11  5012.7  464.98
  5134.2  465.15  5144.3  462.73  5174.6  465.46  5194.9  464.12  5215.0  465.94
  5287.9  465.00  5336.6  466.62  5350.8  465.19  5476.5  469.66  5498.5  467.44
  5528.3  468.38  5549.4  470.50  5680.7  474.59  6004.5  481.44  6070.8  480.77
#Mann=5,-1,0
  4454.0    0.05       0  4959.5    0.12       0  4999.0    0.07       0
  5006.1    0.12       0  5528.3    0.05       0
Bank Sta=4999,5006.1
Exp/Cntr=0.3,0.1

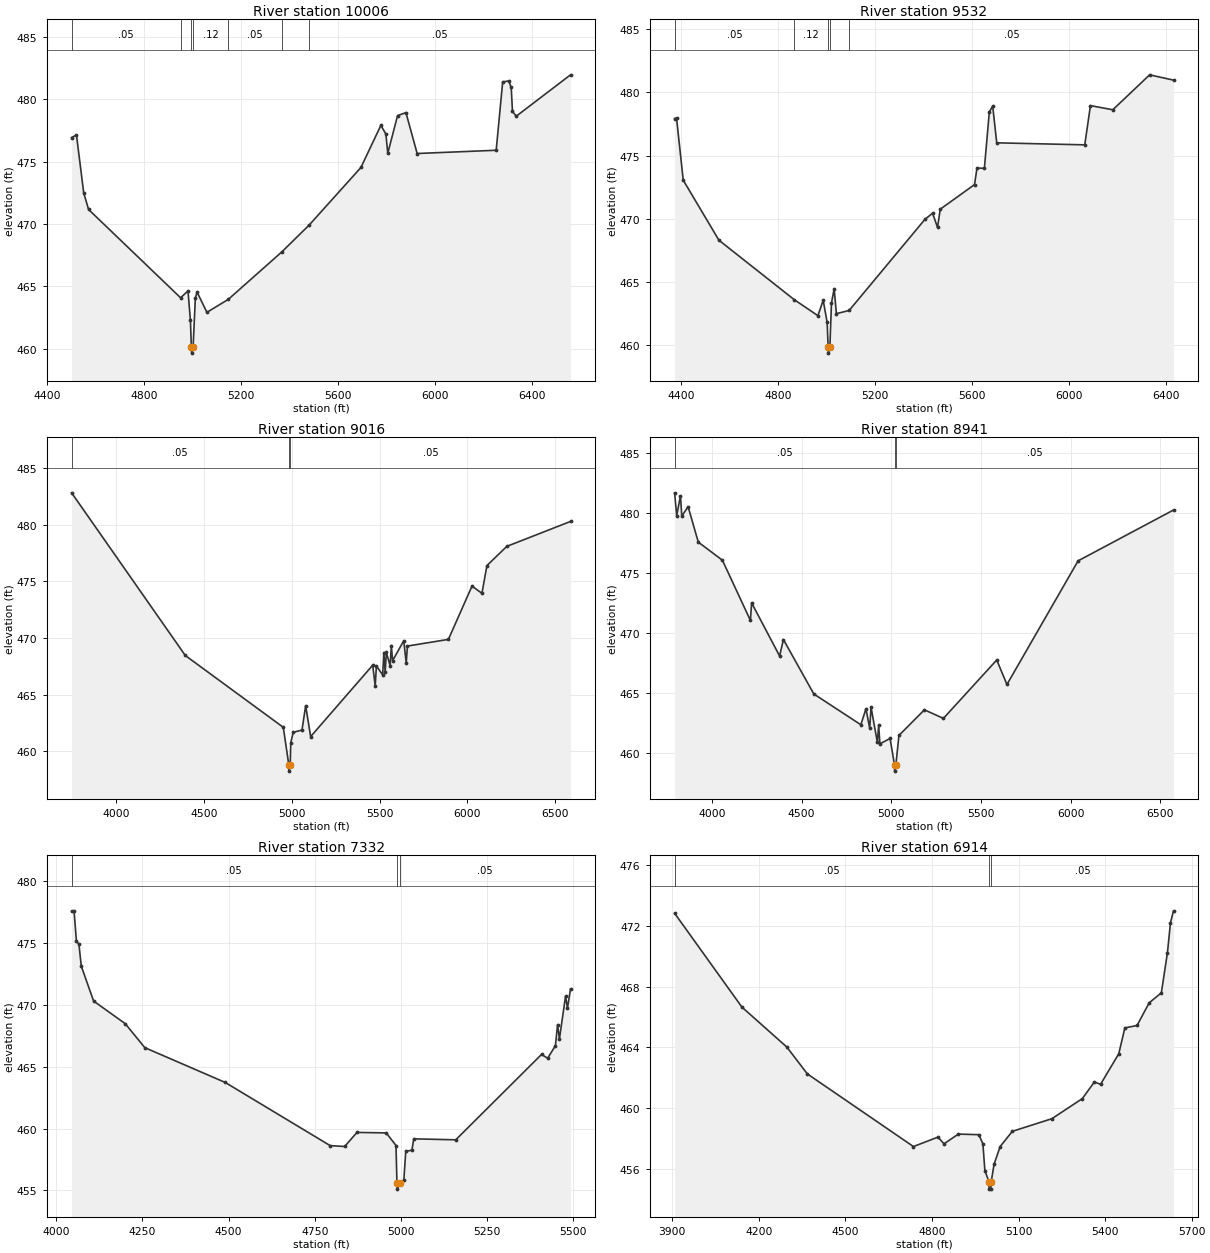
Type RM Length L Ch R = 1,10006,474,474,474
BEGIN DESCRIPTION:
Hardin Branch 18.0
END DESCRIPTION:
XS GIS Cut Line= 3
      2663476.00      6951710.99      2663476.00      6952211.00
      2663080.14      6953717.55
#Sta/Elev= 30
  4500.4  476.94  4520.4  477.15  4550.4  472.49  4570.4  471.17  4949.9  464.09
  4980.4  464.64  4990.4  462.28  4994.3  460.15  4995.4  459.65  5001.5  460.15
  5010.8  464.08  5018.0  464.54  5058.4  462.92  5146.5  463.96  5368.0  467.78
  5480.1  469.92  5693.7  474.54  5775.9  477.92  5796.6  477.22  5804.4  475.68
  5844.8  478.70  5879.3  478.94  5925.5  475.66  6251.5  475.92  6278.3  481.40
  6303.2  481.48  6313.5  480.96  6318.7  479.04  6334.2  478.65  6558.1  481.97
#Mann=7,-1,0
  4500.4    0.05       0  4949.9    0.12       0  4994.3    0.07       0
  5001.5    0.12       0  5146.5    0.05       0  5368.0    0.12       0
  5480.1    0.05       0
Bank Sta=4994.3,5001.5
Exp/Cntr=0.3,0.1

Type RM Length L Ch R = 1,9532,516,516,516
BEGIN DESCRIPTION:
Hardin Branch 17.0
END DESCRIPTION:
XS GIS Cut Line= 3
      2663376.02      6951710.96      2663076.00      6952261.00
      2662814.46      6953667.75
#Sta/Elev= 30
  4373.3  477.93  4381.4  477.96  4408.9  473.05  4556.1  468.29  4866.5  463.58
  4964.2  462.31  4986.1  463.53  5002.4  461.78  5006.4  459.84  5007.5  459.34
  5013.7  459.84  5020.2  463.31  5031.3  464.44  5040.5  462.47  5093.0  462.72
  5405.9  469.95  5437.2  470.43  5457.6  469.30  5468.8  470.75  5610.1  472.70
  5620.3  474.01  5650.8  473.99  5671.2  478.46  5685.1  478.92  5701.7  476.01
  6064.7  475.85  6088.2  478.96  6180.4  478.63  6332.3  481.40  6430.7  480.98
#Mann=5,-1,0
  4373.3    0.05       0  4866.5    0.12       0  5006.4    0.07       0
  5013.7    0.12       0  5093.0    0.05       0
Bank Sta=5006.4,5013.7
Exp/Cntr=0.3,0.1

Type RM Length L Ch R = 1,9016,75,75,75
BEGIN DESCRIPTION:
Mapping XS 44446994
END DESCRIPTION:
XS GIS Cut Line= 3
      2663532.01      6951291.10      2662619.81      6952153.17
      2661453.00      6953231.22
#Sta/Elev= 30
  3744.9  482.82  4392.8  468.45  4951.5  462.10  4983.4  458.73  4984.5  458.23
  4990.8  458.73  4994.0  460.74  5008.1  461.66  5058.0  461.86  5079.0  464.01
  5107.3  461.28  5461.1  467.59  5475.3  465.76  5482.1  467.52  5517.8  466.74
  5524.6  468.71  5532.0  466.97  5538.8  468.72  5560.4  467.54  5567.2  469.33
  5574.5  467.99  5638.0  469.75  5652.2  467.79  5659.0  469.28  5892.6  469.87
  6027.0  474.58  6083.7  473.94  6112.1  476.39  6225.5  478.09  6588.6  480.29
#Mann=3,-1,0
  3744.9    0.05       0  4983.4    0.03       0  4990.8    0.05       0
Bank Sta=4983.4,4990.8
Exp/Cntr=0.3,0.1

Type RM Length L Ch R = 1,8941,1609,1609,1609
BEGIN DESCRIPTION:
Mapping XS 1c2b0400
END DESCRIPTION:
XS GIS Cut Line= 3
      2663458.23      6951286.76      2662564.12      6952102.74
      2661405.30      6953161.74
#Sta/Elev= 30
  3792.3  481.68  3804.0  479.78  3825.0  481.44  3832.4  479.74  3867.6  480.53
  3924.3  477.58  4058.8  476.07  4214.8  471.06  4221.6  472.52  4377.5  468.10
  4398.6  469.47  4568.2  464.94  4830.3  462.38  4858.7  463.71  4879.6  462.09
  4887.0  463.84  4922.2  460.92  4929.6  462.35  4936.4  460.79  4993.1  461.24
  5017.8  459.02  5018.9  458.52  5025.2  459.02  5042.5  461.49  5184.3  463.62
  5290.4  462.91  5587.6  467.77  5644.4  465.73  6040.9  476.02  6572.6  480.25
#Mann=3,-1,0
  3792.3    0.05       0  5017.8    0.03       0  5025.2    0.05       0
Bank Sta=5017.8,5025.2
Exp/Cntr=0.3,0.1

Type RM Length L Ch R = 1,7332,418,418,418
BEGIN DESCRIPTION:
Hardin Branch 13.0
END DESCRIPTION:
XS GIS Cut Line= 3
      2662376.00      6950911.00      2661726.00      6951611.00
      2661526.00      6952061.01
#Sta/Elev= 30
  4044.5  477.58  4051.6  477.62  4058.4  475.20  4065.8  474.90  4072.6  473.14
  4108.3  470.32  4200.1  468.49  4256.8  466.55  4490.4  463.73  4794.8  458.62
  4836.8  458.55  4872.5  459.69  4957.5  459.65  4985.8  458.63  4988.5  455.60
  4989.8  455.10  4996.8  455.60  5008.6  455.86  5014.1  458.16  5031.9  458.25
  5037.4  459.17  5159.1  459.09  5408.1  466.00  5425.8  465.69  5448.4  466.71
  5454.6  468.41  5460.0  467.25  5477.8  470.72  5483.3  469.74  5492.2  471.30
#Mann=3,-1,0
  4044.5    0.05       0  4988.5    0.04       0  4996.8    0.05       0
Bank Sta=4988.5,4996.8
Exp/Cntr=0.3,0.1

Type RM Length L Ch R = 1,6914,467,467,467
BEGIN DESCRIPTION:
Hardin Branch 12.0
END DESCRIPTION:
XS GIS Cut Line= 3
      2662226.00      6950611.00      2661426.00      6951361.00
      2661226.02      6951960.95
#Sta/Elev= 30
  3908.1  472.82  4141.4  466.65  4297.2  464.02  4368.0  462.26  4735.8  457.48
  4820.8  458.10  4841.8  457.66  4891.6  458.30  4962.4  458.26  4976.6  457.66
  4983.4  455.90  4997.1  455.18  4998.3  454.68  5004.2  454.68  5005.5  455.18
  5015.2  456.31  5036.3  457.48  5078.5  458.48  5215.5  459.31  5320.9  460.63
  5363.1  461.73  5384.2  461.57  5447.4  463.58  5468.5  465.28  5510.7  465.44
  5552.8  466.93  5595.0  467.59  5616.1  470.23  5626.6  472.20  5637.1  472.98
#Mann=3,-1,0
  3908.1    0.05       0  4997.1    0.03       0  5005.5    0.05       0
Bank Sta=4997.1,5005.5
Exp/Cntr=0.3,0.1

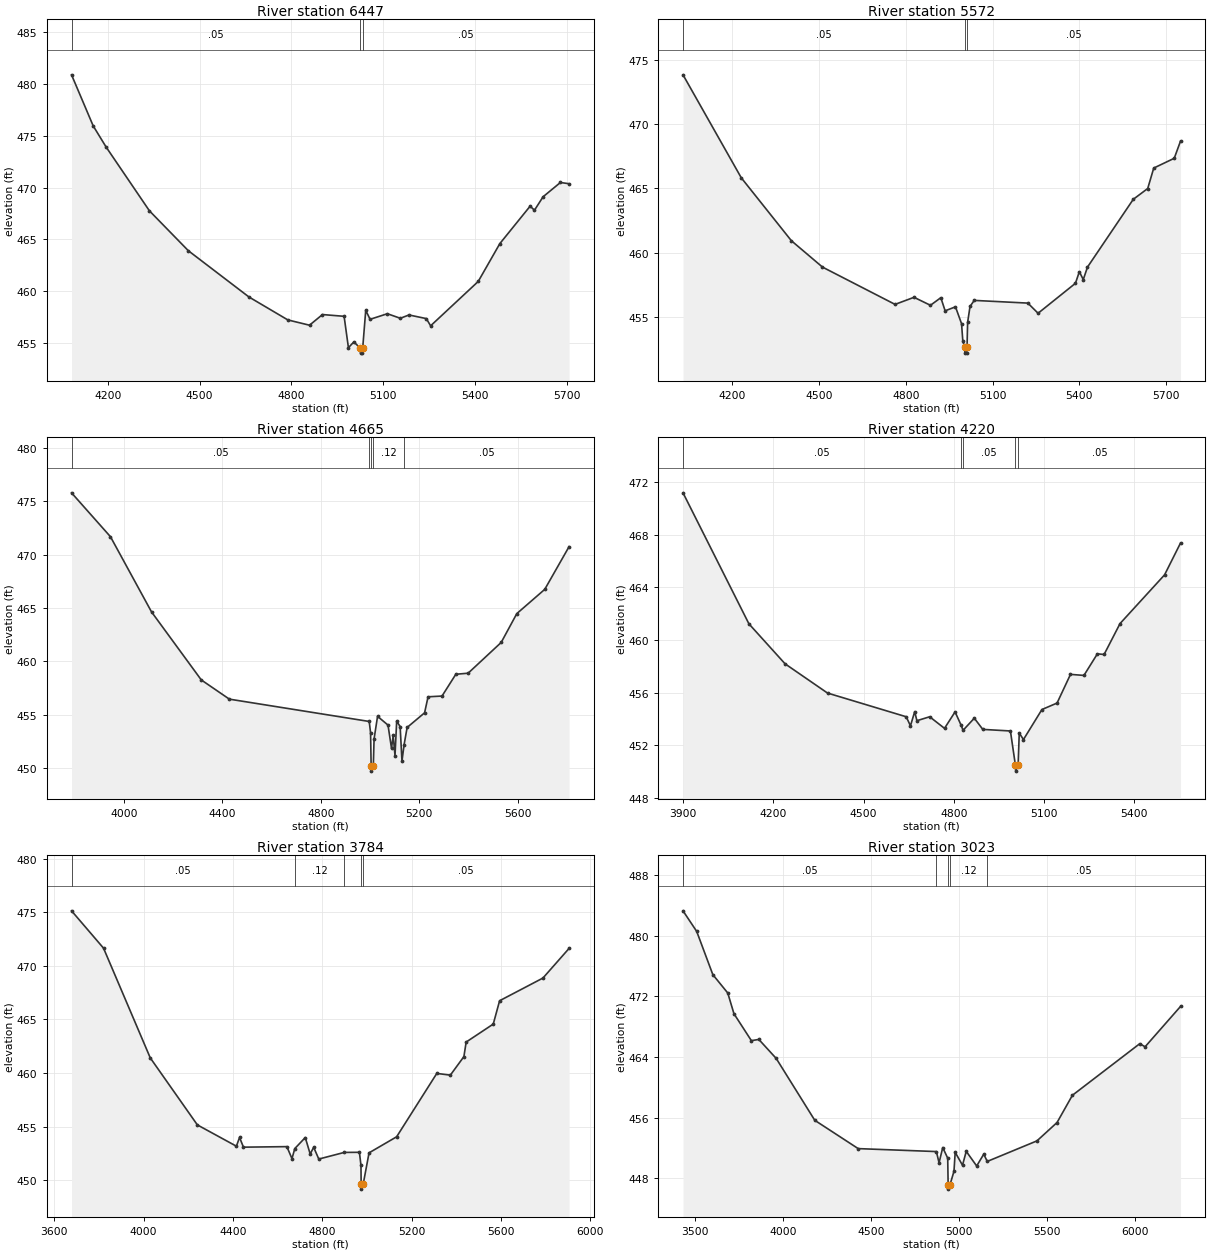
Type RM Length L Ch R = 1,6447,875,875,875
BEGIN DESCRIPTION:
Hardin Branch 11.0
END DESCRIPTION:
XS GIS Cut Line= 3
      2661976.03      6950310.97      2661326.00      6950961.00
      2660825.99      6951461.01
#Sta/Elev= 30
  4081.2  480.90  4152.0  475.96  4194.4  473.91  4335.8  467.75  4463.1  463.89
  4661.1  459.42  4788.3  457.20  4859.1  456.69  4901.5  457.72  4972.2  457.55
  4986.3  454.52  5004.0  455.07  5024.6  454.49  5025.8  453.99  5031.7  453.99
  5033.0  454.49  5042.9  458.13  5057.1  457.26  5113.6  457.80  5156.0  457.36
  5184.3  457.68  5240.9  457.33  5255.0  456.63  5410.6  460.92  5481.3  464.58
  5580.3  468.20  5594.5  467.81  5622.7  469.11  5679.3  470.49  5707.6  470.37
#Mann=3,-1,0
  4081.2    0.05       0  5024.6    0.03       0  5033.0    0.05       0
Bank Sta=5024.6,5033
Exp/Cntr=0.3,0.1

Type RM Length L Ch R = 1,5572,907,907,907
BEGIN DESCRIPTION:
Hardin Branch 9.0
END DESCRIPTION:
XS GIS Cut Line= 3
      2661726.00      6949961.00      2660926.00      6950511.00
      2660326.02      6950960.98
#Sta/Elev= 30
  4029.4  473.82  4231.0  465.81  4404.2  460.92  4511.8  458.87  4762.8  455.97
  4828.4  456.52  4885.2  455.90  4921.1  456.49  4936.0  455.47  4971.8  455.78
  4992.8  454.47  4997.2  453.11  5003.2  452.68  5004.5  452.18  5010.6  452.18
  5011.8  452.68  5013.8  454.57  5022.1  455.81  5036.7  456.28  5222.1  456.07
  5257.5  455.28  5386.7  457.61  5400.2  458.51  5413.8  457.90  5428.4  458.87
  5586.7  464.14  5636.7  464.98  5657.5  466.57  5728.4  467.33  5750.2  468.67
#Mann=3,-1,0
  4029.4    0.05       0  5003.2    0.03       0  5011.8    0.05       0
Bank Sta=5003.2,5011.8
Exp/Cntr=0.3,0.1

Type RM Length L Ch R = 1,4665,445,445,445
BEGIN DESCRIPTION:
Hardin Branch 7.0
END DESCRIPTION:
XS GIS Cut Line= 3
      2660876.00      6948911.00      2660376.00      6950011.00
      2659776.04      6950560.97
#Sta/Elev= 30
  3787.1  475.79  3945.3  471.68  4112.2  464.64  4314.4  458.27  4428.6  456.47
  4997.0  454.38  5002.5  453.32  5004.8  450.23  5006.1  449.73  5013.7  450.23
  5016.7  452.74  5030.9  454.86  5073.4  454.04  5087.6  451.86  5094.4  453.07
  5101.8  451.18  5108.6  454.41  5122.7  453.90  5130.1  450.67  5138.8  452.21
  5151.1  453.82  5222.0  455.19  5236.2  456.69  5292.9  456.76  5349.0  458.80
  5399.0  458.90  5533.4  461.78  5596.9  464.48  5710.4  466.75  5809.3  470.75
#Mann=5,-1,0
  3787.1    0.05       0  4997.0    0.12       0  5004.8    0.07       0
  5013.7    0.12       0  5138.8    0.05       0
Bank Sta=5004.8,5013.7
Exp/Cntr=0.3,0.1

Type RM Length L Ch R = 1,4220,436,436,436
BEGIN DESCRIPTION:
Hardin Branch 6.0
END DESCRIPTION:
XS GIS Cut Line= 3
      2660725.99      6949061.01      2659976.00      6949861.00
      2659725.99      6950361.02
#Sta/Elev= 30
  3898.9  471.18  4118.2  461.23  4238.6  458.19  4379.8  455.97  4641.6  454.17
  4655.8  453.48  4669.9  454.56  4677.2  453.87  4719.7  454.17  4769.1  453.29
  4804.2  454.54  4824.7  453.51  4830.8  453.14  4868.2  454.06  4896.5  453.21
  4988.4  453.09  5004.7  450.54  5006.1  450.04  5014.1  450.54  5017.8  452.93
  5031.8  452.44  5093.3  454.72  5143.6  455.21  5188.3  457.39  5233.0  457.31
  5277.8  458.95  5300.1  458.90  5353.2  461.25  5501.4  464.95  5554.5  467.37
#Mann=5,-1,0
  3898.9    0.05       0  4824.7    0.12       0  4830.8    0.05       0
  5004.7    0.03       0  5014.1    0.05       0
Bank Sta=5004.7,5014.1
Exp/Cntr=0.3,0.1

Type RM Length L Ch R = 1,3784,761,761,761
BEGIN DESCRIPTION:
Hardin Branch 5.0
END DESCRIPTION:
XS GIS Cut Line= 3
      2660126.00      6948560.99      2659570.48      6949761.49
      2659434.89      6950656.68
#Sta/Elev= 30
  3677.2  475.15  3820.5  471.66  4029.8  461.41  4240.7  455.15  4415.5  453.16
  4429.6  453.98  4447.1  453.07  4641.5  453.12  4664.4  452.00  4677.1  452.94
  4724.0  453.97  4746.0  452.43  4761.6  453.06  4784.5  451.96  4898.7  452.58
  4966.4  452.59  4973.4  451.37  4974.2  449.65  4975.5  449.15  4983.7  449.65
  5009.6  452.54  5133.1  454.04  5313.0  459.96  5373.7  459.80  5434.4  461.53
  5444.5  462.89  5565.9  464.57  5594.3  466.75  5788.4  468.87  5905.4  471.64
#Mann=5,-1,0
  3677.2    0.05       0  4677.1    0.12       0  4898.7    0.05       0
  4974.2    0.04       0  4983.7    0.05       0
Bank Sta=4974.2,4983.7
Exp/Cntr=0.3,0.1

Type RM Length L Ch R = 1,3023,1043,1043,1043
BEGIN DESCRIPTION:
Hardin Branch 4.0
END DESCRIPTION:
XS GIS Cut Line= 3
      2660126.00      6948211.00      2659055.87      6949360.61
      2659226.00      6950610.98
#Sta/Elev= 30
  3429.4  483.26  3507.3  480.55  3599.2  474.85  3684.2  472.43  3719.4  469.70
  3818.6  466.15  3861.1  466.31  3960.2  463.80  4179.6  455.65  4426.8  451.92
  4871.9  451.53  4887.1  450.05  4908.1  452.06  4936.4  450.66  4938.9  447.08
  4940.3  446.58  4948.5  447.08  4972.1  448.94  4978.9  451.43  5020.6  449.73
  5041.9  451.56  5101.3  449.63  5141.7  451.19  5161.5  450.23  5444.5  452.94
  5558.9  455.36  5646.3  458.95  6029.8  465.75  6060.1  465.34  6261.9  470.66
#Mann=5,-1,0
  3429.4    0.05       0  4871.9    0.12       0  4938.9    0.07       0
  4948.5    0.12       0  5161.5    0.05       0
Bank Sta=4938.9,4948.5
Exp/Cntr=0.3,0.1

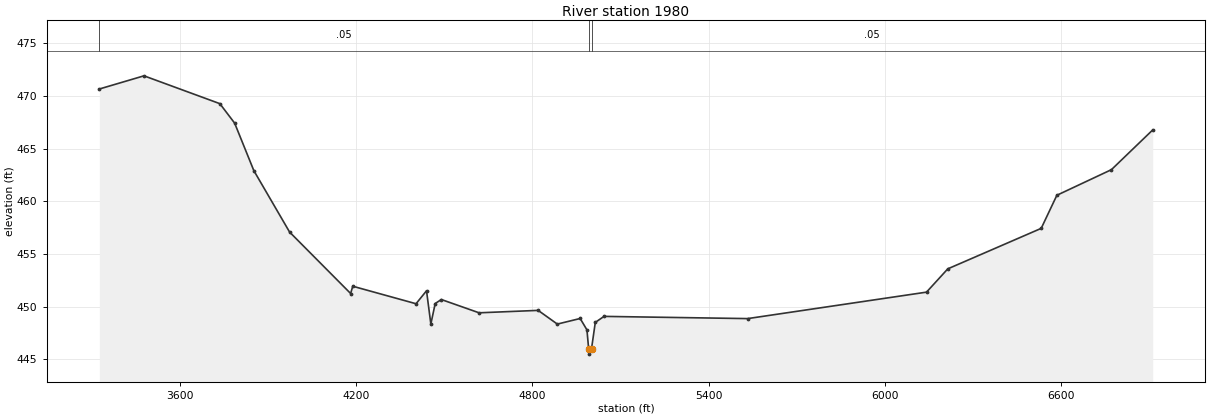
Type RM Length L Ch R = 1,1980,0,0,0
BEGIN DESCRIPTION:
Hardin Branch 3.0
END DESCRIPTION:
XS GIS Cut Line= 4
      2659808.01      6947810.23      2658445.95      6948781.34
      2658288.95      6949177.39      2658653.23      6950617.19
#Sta/Elev= 30
  3327.2  470.65  3479.1  471.90  3737.2  469.26  3787.6  467.41  3852.8  462.91
  3974.5  457.08  4182.2  451.25  4189.4  451.94  4404.7  450.28  4440.4  451.51
  4455.1  448.36  4469.9  450.30  4490.8  450.68  4619.2  449.42  4820.2  449.65
  4885.4  448.35  4963.1  448.88  4986.2  447.80  4992.0  446.00  4993.4  445.50
  5001.7  446.00  5014.6  448.51  5044.3  449.08  5532.9  448.87  6141.5  451.38
  6213.9  453.59  6531.7  457.43  6585.0  460.57  6770.7  463.00  6911.2  466.77
#Mann=3,-1,0
  3327.2    0.05       0  4992.0    0.04       0  5001.7    0.05       0
Bank Sta=4992,5001.7
Exp/Cntr=0.3,0.1

Chan Stop Cuts=-1