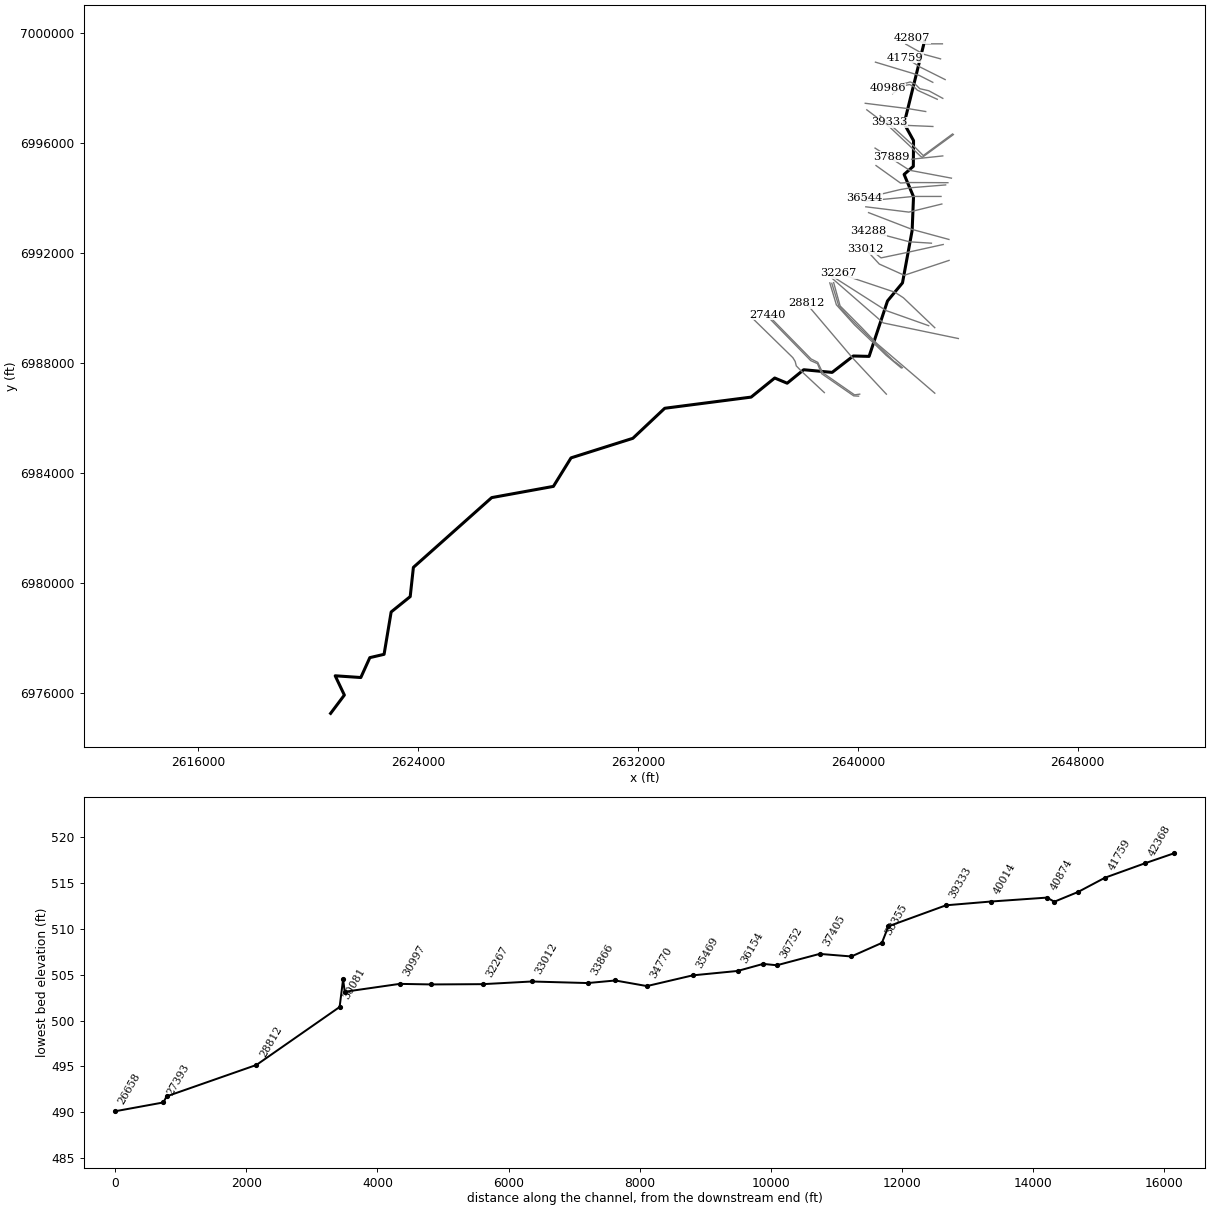
--- High Point Creek.prj (project) ---

Proj Title=High Point Creek Base Level Engineering
Current Plan=p01
Default Exp/Contr=0.3,0.1
English Units
Geom File=g01
Flow File=f01
Plan File=p01
Y Axis Title=Elevation
X Axis Title(PF)=Main Channel Distance
X Axis Title(XS)=Station
BEGIN DESCRIPTION:
High Point Creek
END DESCRIPTION:
DSS Export Rating Curves= 0
DSS Export Rating Curve Sorted= 0
DSS Export Volume Flow Curves= 0
DXF OffsetX= 0
DXF OffsetY= 0
DXF ScaleX= 1
DXF ScaleY= 10

--- High Point Creek.p01 (plan) ---

Plan Title=Multiple Run
Short Identifier=Multiple
Geom File=g01
Flow File=f01
Subcritical Flow
K Sum by GR= 0
Std Step Tol= 0.01
Critical Tol= 0.01
Num of Std Step Trials= 20
Max Error Tol= 0.3
Flow Tol Ratio= 0.001
Split Flow NTrial= 30
Split Flow Tol= 0.02
Split Flow Ratio= 0.02
Log Output Level= 0
Friction Slope Method= 1
Unsteady Friction Slope Method= 2
Unsteady Bridges Friction Slope Method= 1
Parabolic Critical Depth
Global Vel Dist=  1 , 1 , 1
Global Log Level= 0
CheckData=True
Encroach Param= -1, 0, 0, 0
BEGIN DESCRIPTION:
Multiple Run
END DESCRIPTION:

--- High Point Creek.f01 (steady flow) ---

Flow Title=Multiple
Program Version=4.10
Number of Profiles= 7
Profile Names=10-year,25-year,50-year,1pct_min,100-year,1pct_plu,500-year
River Rch & RM=High Point Creek,Reach-1         ,42807
     305     389     453     262     523    1043     695
River Rch & RM=High Point Creek,Reach-1         ,42368
     619     826     992     591    1179    2353    1664
River Rch & RM=High Point Creek,Reach-1         ,40986
     815    1099    1328     795    1586    3165    2262
River Rch & RM=High Point Creek,Reach-1         ,36544
    1045    1423    1732    1043    2080    4150    3001
River Rch & RM=High Point Creek,Reach-1         ,32267
    1195    1639    2004    1210    2415    4819    3511
River Rch & RM=High Point Creek,Reach-1         ,31480
    1630    2272    2808    1714    3419    6823    5075
River Rch & RM=High Point Creek,Reach-1         ,28812
    1688    2352    2907    1773    3538    7060    5247
River Rch & RM=High Point Creek,Reach-1         ,27440
    1878    2626    3251    1986    3963    7908    5896
River Rch & RM=High Point Creek,Reach-1         ,23217
    1928    2695    3337    2039    4069    8118    6052
River Rch & RM=High Point Creek,Reach-1         ,22034
    1943    2714    3359    2051    4093    8166    6081
River Rch & RM=High Point Creek,Reach-1         ,20923
    1918    2676    3308    2018    4026    8034    5969
River Rch & RM=High Point Creek,Reach-1         ,19108
    2051    2875    3566    2182    4354    8688    6497
River Rch & RM=High Point Creek,Reach-1         ,18688
    2118    2969    3684    2255    4499    8977    6716
River Rch & RM=High Point Creek,Reach-1         ,14703
    2128    2981    3696    2260    4510    8998    6720
River Rch & RM=High Point Creek,Reach-1         ,13204
    2395    3369    4190    2569    5126   10227    7678
River Rch & RM=High Point Creek,Reach-1         ,11105
    2479    3487    4336    2658    5303   10580    7937
River Rch & RM=High Point Creek,Reach-1         ,5548
    2638    3720    4633    2844    5674   11322    8519
Boundary for River Rch & Prof#=High Point Creek,Reach-1         , 1
Up Type= 0
Dn Type= 3
Dn Slope=0.00285
Boundary for River Rch & Prof#=High Point Creek,Reach-1         , 2
Up Type= 0
Dn Type= 3
Dn Slope=0.00285
Boundary for River Rch & Prof#=High Point Creek,Reach-1         , 3
Up Type= 0
Dn Type= 3
Dn Slope=0.00285
Boundary for River Rch & Prof#=High Point Creek,Reach-1         , 4
Up Type= 0
Dn Type= 3
Dn Slope=0.00285
Boundary for River Rch & Prof#=High Point Creek,Reach-1         , 5
Up Type= 0
Dn Type= 3
Dn Slope=0.00285
Boundary for River Rch & Prof#=High Point Creek,Reach-1         , 6
Up Type= 0
Dn Type= 3
Dn Slope=0.00285
Boundary for River Rch & Prof#=High Point Creek,Reach-1         , 7
Up Type= 0
Dn Type= 3
Dn Slope=0.00285
DSS Import GetInterval= 0
DSS Import GetPeak= 0
DSS Import FillOption= 0

--- High Point Creek.g01 (geometry) ---

Geom Title=Existing Conditions

River Reach=High Point Creek,Reach-1
Reach XY= 30
      2642426.00      6999711.00      2641683.55      6996710.99
      2642025.93      6996090.97      2642018.23      6995157.59
      2641683.22      6994861.31      2642025.45      6994050.36
      2641974.90      6992821.55      2641623.75      6990916.93
      2641079.29      6990259.64      2640409.48      6988244.06
      2639834.50      6988258.41      2639065.45      6987662.10
      2638031.89      6987759.04      2637429.64      6987268.70
      2636977.22      6987457.56      2636120.07      6986763.25
      2632977.56      6986357.24      2631817.56      6985264.40
      2629569.81      6984553.18      2628928.30      6983516.06
      2626684.30      6983107.93      2623836.48      6980570.80
      2623720.66      6979508.26      2623027.62      6978949.19
      2622770.55      6977408.53      2622252.16      6977288.15
      2621924.45      6976564.75      2620992.21      6976628.22
      2621325.98      6975926.41      2620826.00      6975261.00

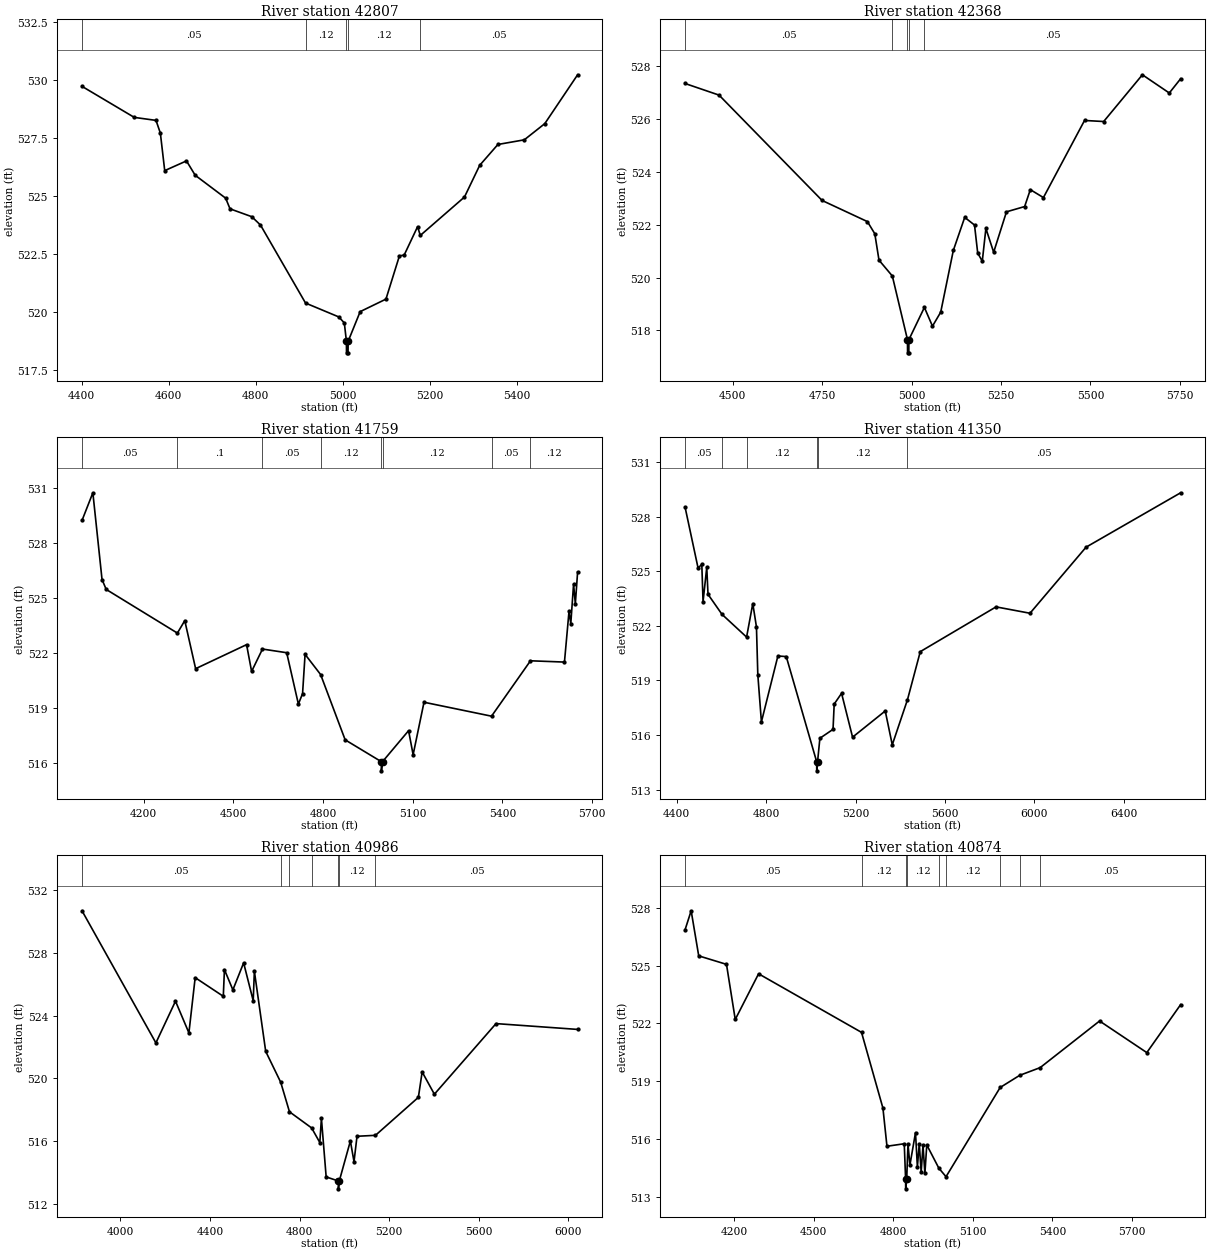
Type RM Length L Ch R = 1,42807,439,439,439
BEGIN DESCRIPTION:
High Point Creek 74.0
END DESCRIPTION:
XS GIS Cut Line= 3
      2643075.95      6999611.00      2642476.00      6999611.00
      2641975.97      6999811.01
#Sta/Elev= 30
  4400.9  529.74  4520.9  528.40  4570.9  528.27  4580.9  527.72  4590.9  526.10
  4640.9  526.52  4660.9  525.90  4730.9  524.91  4740.9  524.45  4790.9  524.11
  4810.9  523.75  4914.4  520.38  4990.9  519.78  5003.5  519.52  5008.3  518.73
  5008.5  518.23  5012.0  518.23  5012.3  518.73  5039.9  520.01  5099.1  520.55
  5130.1  522.42  5140.9  522.45  5171.8  523.68  5178.0  523.30  5279.5  524.96
  5314.5  526.33  5356.3  527.23  5416.9  527.43  5464.0  528.13  5539.4  530.24
#Mann=5,-1,0
  4400.9    0.05       0  4914.4    0.12       0  5008.3    0.07       0
  5012.3    0.12       0  5178.0    0.05       0
Bank Sta=5008.3,5012.3
Exp/Cntr=0.3,0.1

Type RM Length L Ch R = 1,42368,609,609,609
BEGIN DESCRIPTION:
High Point Creek 72.0
END DESCRIPTION:
XS GIS Cut Line= 3
      2643007.77      6999064.45      2642396.87      6999231.01
      2641742.13      6999600.92
#Sta/Elev= 30
  4366.8  527.35  4461.9  526.91  4749.9  522.92  4876.5  522.12  4897.2  521.66
  4908.9  520.66  4946.2  520.06  4988.5  517.65  4988.8  517.15  4992.3  517.15
  4992.5  517.65  5035.8  518.87  5058.4  518.16  5081.4  518.69  5116.7  521.03
  5148.5  522.28  5175.9  521.99  5184.8  520.93  5197.6  520.62  5207.7  521.86
  5229.4  520.96  5265.2  522.49  5316.0  522.69  5331.9  523.33  5368.5  523.03
  5483.4  525.95  5536.9  525.91  5645.1  527.68  5720.3  526.99  5752.0  527.53
#Mann=5,-1,0
  4366.8    0.05       0  4946.2    0.12       0  4988.5    0.07       0
  4992.5    0.12       0  5035.8    0.05       0
Bank Sta=4988.5,4992.5
Exp/Cntr=0.3,0.1

Type RM Length L Ch R = 1,41759,409,409,409
BEGIN DESCRIPTION:
High Point Creek 70.0
END DESCRIPTION:
XS GIS Cut Line= 3
      2643175.97      6998311.02      2642276.00      6998761.00
      2641726.01      6999110.99
#Sta/Elev= 30
  3993.8  529.23  4030.1  530.74  4060.8  526.01  4074.8  525.47  4312.9  523.09
  4337.6  523.77  4373.9  521.15  4544.4  522.46  4561.2  521.00  4597.6  522.22
  4678.6  522.02  4717.7  519.22  4731.7  519.79  4740.1  521.93  4792.1  520.83
  4874.2  517.27  4995.2  516.08  4995.5  515.58  4999.2  516.08  5086.4  517.77
  5101.6  516.46  5138.0  519.32  5363.9  518.56  5494.2  521.58  5607.9  521.51
  5623.1  524.27  5629.1  523.61  5638.4  525.76  5644.3  524.69  5651.9  526.42
#Mann=8,-1,0
  3993.8    0.05       0  4312.9     0.1       0  4597.6    0.05       0
  4792.1    0.12       0  4995.2    0.07       0  4999.2    0.12       0
  5363.9    0.05       0  5494.2    0.12       0
Bank Sta=4995.2,4999.2
Exp/Cntr=0.3,0.1

Type RM Length L Ch R = 1,41350,364,364,364
BEGIN DESCRIPTION:
High Point Creek 69.0
END DESCRIPTION:
XS GIS Cut Line= 3
      2642726.01      6998210.99      2642224.38      6998467.04
      2640640.82      6998944.59
#Sta/Elev= 30
  4436.8  528.53  4495.2  525.17  4511.8  525.38  4517.4  523.33  4534.0  525.21
  4539.6  523.73  4602.1  522.63  4712.2  521.38  4739.9  523.22  4756.3  521.94
  4762.4  519.31  4778.5  516.72  4852.2  520.34  4889.6  520.31  5025.7  514.53
  5026.0  514.03  5029.7  514.53  5040.1  515.82  5098.9  516.31  5104.1  517.70
  5137.1  518.29  5186.3  515.88  5332.5  517.32  5363.9  515.46  5432.0  517.94
  5489.2  520.58  5828.2  523.04  5980.1  522.69  6230.8  526.32  6654.0  529.31
#Mann=6,-1,0
  4436.8    0.05       0  4602.1     0.1       0  4712.2    0.12       0
  5025.7    0.07       0  5029.7    0.12       0  5432.0    0.05       0
Bank Sta=5025.7,5029.7
Exp/Cntr=0.3,0.1

Type RM Length L Ch R = 1,40986,112,112,112
BEGIN DESCRIPTION:
High Point Creek 68.0
END DESCRIPTION:
XS GIS Cut Line= 6
      2643090.28      6997628.27      2642581.20      6997904.30
      2642252.64      6997979.82      2642076.05      6998156.06
      2641904.33      6998224.61      2641080.73      6997992.02
#Sta/Elev= 30
  3828.3  530.68  4158.3  522.26  4245.8  524.92  4305.7  522.90  4333.7  526.42
  4459.3  525.23  4464.4  526.93  4502.1  525.64  4550.1  527.36  4592.9  524.95
  4598.1  526.83  4648.7  521.72  4715.8  519.75  4754.8  517.87  4853.9  516.84
  4890.4  515.91  4897.5  517.45  4918.7  513.72  4973.2  513.46  4973.5  512.96
  4977.3  513.46  5026.9  516.01  5043.1  514.69  5056.5  516.31  5138.9  516.37
  5330.5  518.79  5347.4  520.41  5402.0  518.99  5677.3  523.49  6041.7  523.12
#Mann=7,-1,0
  3828.3    0.05       0  4715.8    0.12       0  4754.8    0.05       0
  4853.9    0.12       0  4973.2    0.07       0  4977.3    0.12       0
  5138.9    0.05       0
Bank Sta=4973.2,4977.3
Exp/Cntr=0.3,0.1

Type RM Length L Ch R = 1,40874,860,860,860
BEGIN DESCRIPTION:
High Point Creek 67.0
END DESCRIPTION:
XS GIS Cut Line= 6
      2642888.06      6997594.56      2642165.27      6997925.83
      2642029.85      6998059.40      2641884.89      6998129.82
      2641652.25      6998084.68      2641263.28      6997795.37
#Sta/Elev= 30
  4014.7  526.85  4037.8  527.84  4066.3  525.50  4171.0  525.06  4204.0  522.20
  4292.0  524.57  4680.1  521.53  4760.8  517.60  4776.0  515.62  4841.2  515.75
  4846.3  513.91  4846.6  513.41  4850.4  513.91  4855.3  515.73  4862.5  514.64
  4883.6  516.33  4890.7  514.55  4897.8  515.75  4904.9  514.28  4911.9  515.67
  4919.0  514.21  4926.1  515.69  4971.7  514.48  4998.7  514.04  5202.8  518.67
  5276.4  519.30  5353.5  519.70  5577.6  522.12  5755.7  520.48  5883.2  522.97
#Mann=9,-1,0
  4014.7    0.05       0  4680.1    0.12       0  4846.3    0.07       0
  4850.4    0.12       0  4971.7    0.05       0  4998.7    0.12       0
  5202.8    0.05       0  5276.4    0.12       0  5353.5    0.05       0
Bank Sta=4846.3,4850.4
Exp/Cntr=0.3,0.1

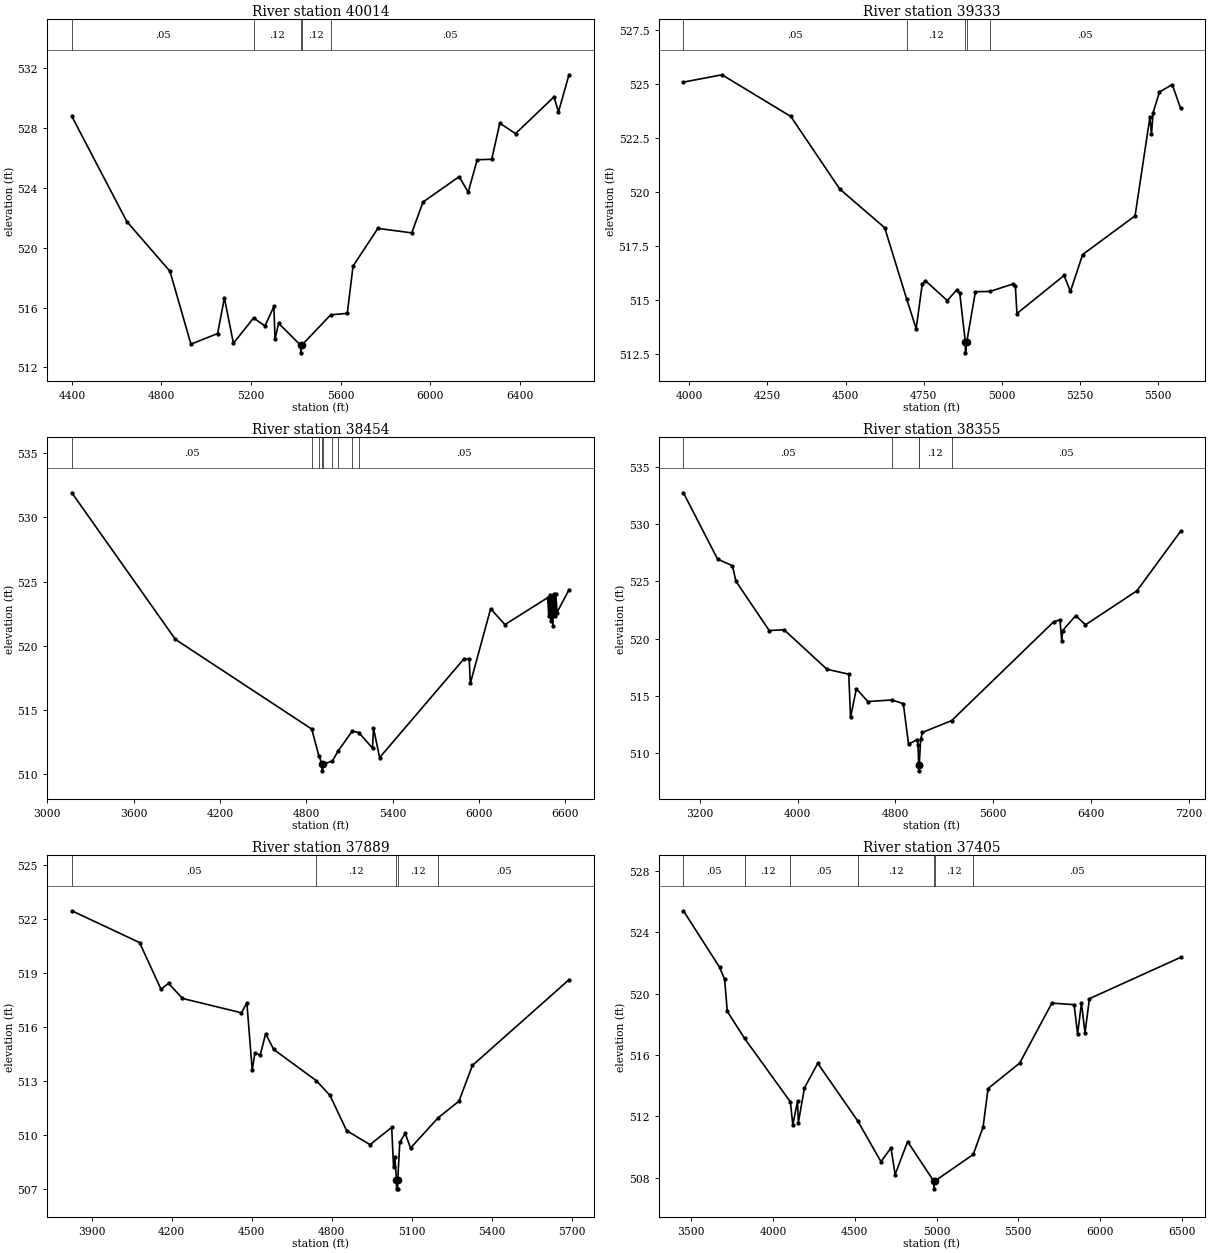
Type RM Length L Ch R = 1,40014,681,681,681
BEGIN DESCRIPTION:
High Point Creek 66.0
END DESCRIPTION:
XS GIS Cut Line= 3
      2642468.16      6997149.03      2641868.19      6997249.02
      2640269.57      6997448.85
#Sta/Elev= 30
  4400.1  528.79  4645.6  521.76  4838.2  518.43  4931.8  513.56  5050.9  514.27
  5081.1  516.65  5121.4  513.62  5211.4  515.31  5262.5  514.78  5302.1  516.08
  5307.2  513.89  5323.0  514.96  5421.6  513.48  5422.0  512.98  5425.8  513.48
  5555.6  515.52  5629.7  515.62  5655.5  518.78  5766.4  521.30  5917.6  521.00
  5967.9  523.06  6129.2  524.76  6169.5  523.72  6209.8  525.89  6274.6  525.92
  6310.6  528.33  6381.1  527.64  6552.5  530.09  6572.6  529.09  6619.4  531.57
#Mann=5,-1,0
  4400.1    0.05       0  5211.4    0.12       0  5421.6    0.03       0
  5425.8    0.12       0  5555.6    0.05       0
Bank Sta=5421.6,5425.8
Exp/Cntr=0.3,0.1

Type RM Length L Ch R = 1,39333,879,879,879
BEGIN DESCRIPTION:
High Point Creek 65.0
END DESCRIPTION:
XS GIS Cut Line= 3
      2642729.21      6996604.99      2641711.50      6996647.67
      2641149.73      6996753.19
#Sta/Elev= 30
  3981.4  525.10  4104.7  525.44  4324.9  523.51  4481.5  520.15  4625.2  518.36
  4695.3  515.07  4725.9  513.69  4745.3  515.75  4755.3  515.91  4825.4  514.99
  4855.4  515.48  4865.4  515.32  4883.2  513.07  4883.6  512.57  4887.7  513.07
  4915.4  515.40  4961.7  515.41  5036.1  515.76  5043.2  515.66  5048.3  514.39
  5198.9  516.15  5219.3  515.41  5258.4  517.12  5426.1  518.91  5473.5  523.47
  5478.6  522.69  5483.8  523.69  5504.2  524.64  5544.9  524.99  5571.6  523.89
#Mann=5,-1,0
  3981.4    0.05       0  4695.3    0.12       0  4883.2    0.03       0
  4887.7    0.12       0  4961.7    0.05       0
Bank Sta=4883.2,4887.7
Exp/Cntr=0.3,0.1

Type RM Length L Ch R = 1,38454,99,99,99
BEGIN DESCRIPTION:
High Point Creek 64.0
END DESCRIPTION:
XS GIS Cut Line= 5
      2643442.67      6996331.53      2642380.20      6995547.70
      2642020.53      6995908.55      2640984.37      6996852.39
      2640812.51      6996995.61
#Sta/Elev= 30
  3170.2  531.92  3890.0  520.51  4837.5  513.53  4886.9  511.45  4910.7  510.78
  4911.2  510.28  4915.4  510.78  4981.3  511.05  5022.9  511.86  5119.1  513.37
  5164.4  513.26  5259.9  512.05  5266.7  513.61  5309.3  511.31  5897.1  519.02
  5932.2  518.97  5939.5  517.08  6080.9  522.90  6180.2  521.66  6477.6  523.76
  6484.7  522.33  6491.2  523.95  6499.0  521.95  6505.5  523.88  6513.3  521.58
  6519.8  524.06  6527.7  522.34  6534.2  524.01  6542.0  522.60  6625.3  524.37
#Mann=9,-1,0
  3170.2    0.05       0  4837.5    0.12       0  4886.9    0.05       0
  4910.7    0.07       0  4915.4    0.05       0  4981.3    0.12       0
  5022.9    0.05       0  5119.1    0.12       0  5164.4    0.05       0
Bank Sta=4910.7,4915.4
Exp/Cntr=0.3,0.1

Type RM Length L Ch R = 1,38355,466,466,466
BEGIN DESCRIPTION:
High Point Creek 63.0
END DESCRIPTION:
XS GIS Cut Line= 6
      2643476.02      6996311.01      2642343.74      6995482.60
      2642276.04      6995526.87      2641952.25      6995837.84
      2641161.45      6996581.55      2640326.00      6997211.00
#Sta/Elev= 30
  3067.2  532.71  3346.3  526.93  3467.6  526.35  3496.9  524.99  3768.7  520.70
  3889.9  520.77  4241.2  517.32  4418.8  516.90  4433.5  513.12  4480.9  515.62
  4575.3  514.51  4772.4  514.65  4865.2  514.32  4907.7  510.80  4978.5  511.20
  4985.4  510.75  4990.3  508.97  4990.8  508.47  4995.0  508.97  5006.8  511.21
  5021.0  511.82  5260.1  512.85  6095.8  521.48  6145.8  521.63  6160.3  519.79
  6167.5  520.70  6274.9  522.00  6354.0  521.20  6774.5  524.16  7131.6  529.35
#Mann=5,-1,0
  3067.2    0.05       0  4772.4    0.12       0  4990.3    0.07       0
  4995.0    0.12       0  5260.1    0.05       0
Bank Sta=4990.3,4995
Exp/Cntr=0.3,0.1

Type RM Length L Ch R = 1,37889,484,484,484
BEGIN DESCRIPTION:
High Point Creek 62.0
END DESCRIPTION:
XS GIS Cut Line= 3
      2643088.52      6995534.68      2641926.00      6995411.00
      2641237.01      6995500.82
#Sta/Elev= 30
  3825.9  522.47  4079.8  520.70  4160.3  518.10  4188.5  518.43  4240.7  517.59
  4462.0  516.79  4482.1  517.35  4502.2  513.61  4512.3  514.55  4532.4  514.44
  4552.5  515.63  4582.7  514.75  4742.7  513.01  4793.8  512.19  4856.2  510.23
  4943.7  509.45  5025.2  510.41  5032.0  508.23  5037.0  508.75  5043.0  507.49
  5043.6  506.99  5047.3  506.99  5047.8  507.49  5055.5  509.57  5075.7  510.08
  5095.8  509.26  5199.6  510.95  5277.3  511.87  5327.8  513.86  5689.8  518.63
#Mann=5,-1,0
  3825.9    0.05       0  4742.7    0.12       0  5043.0    0.07       0
  5047.8    0.12       0  5199.6    0.05       0
Bank Sta=5043,5047.8
Exp/Cntr=0.3,0.1

Type RM Length L Ch R = 1,37405,653,653,653
BEGIN DESCRIPTION:
High Point Creek 61.0
END DESCRIPTION:
XS GIS Cut Line= 3
      2643403.70      6994726.16      2641881.99      6995012.95
      2640625.97      6995819.90
#Sta/Elev= 30
  3451.5  525.40  3673.0  521.71  3703.6  520.93  3719.7  518.84  3825.5  517.08
  4105.9  512.94  4120.8  511.43  4149.4  512.99  4154.5  511.58  4192.0  513.86
  4273.4  515.45  4517.1  511.71  4660.1  509.04  4721.2  509.94  4746.5  508.20
  4822.9  510.35  4983.1  507.77  4983.8  507.27  4988.3  507.77  5224.6  509.51
  5284.8  511.30  5315.2  513.81  5508.7  515.47  5705.6  519.38  5841.6  519.28
  5862.9  517.37  5886.7  519.37  5908.3  517.45  5935.4  519.67  6492.9  522.36
#Mann=7,-1,0
  3451.5    0.05       0  3825.5    0.12       0  4105.9    0.05       0
  4517.1    0.12       0  4983.1    0.07       0  4988.3    0.12       0
  5224.6    0.05       0
Bank Sta=4983.1,4988.3
Exp/Cntr=0.3,0.1

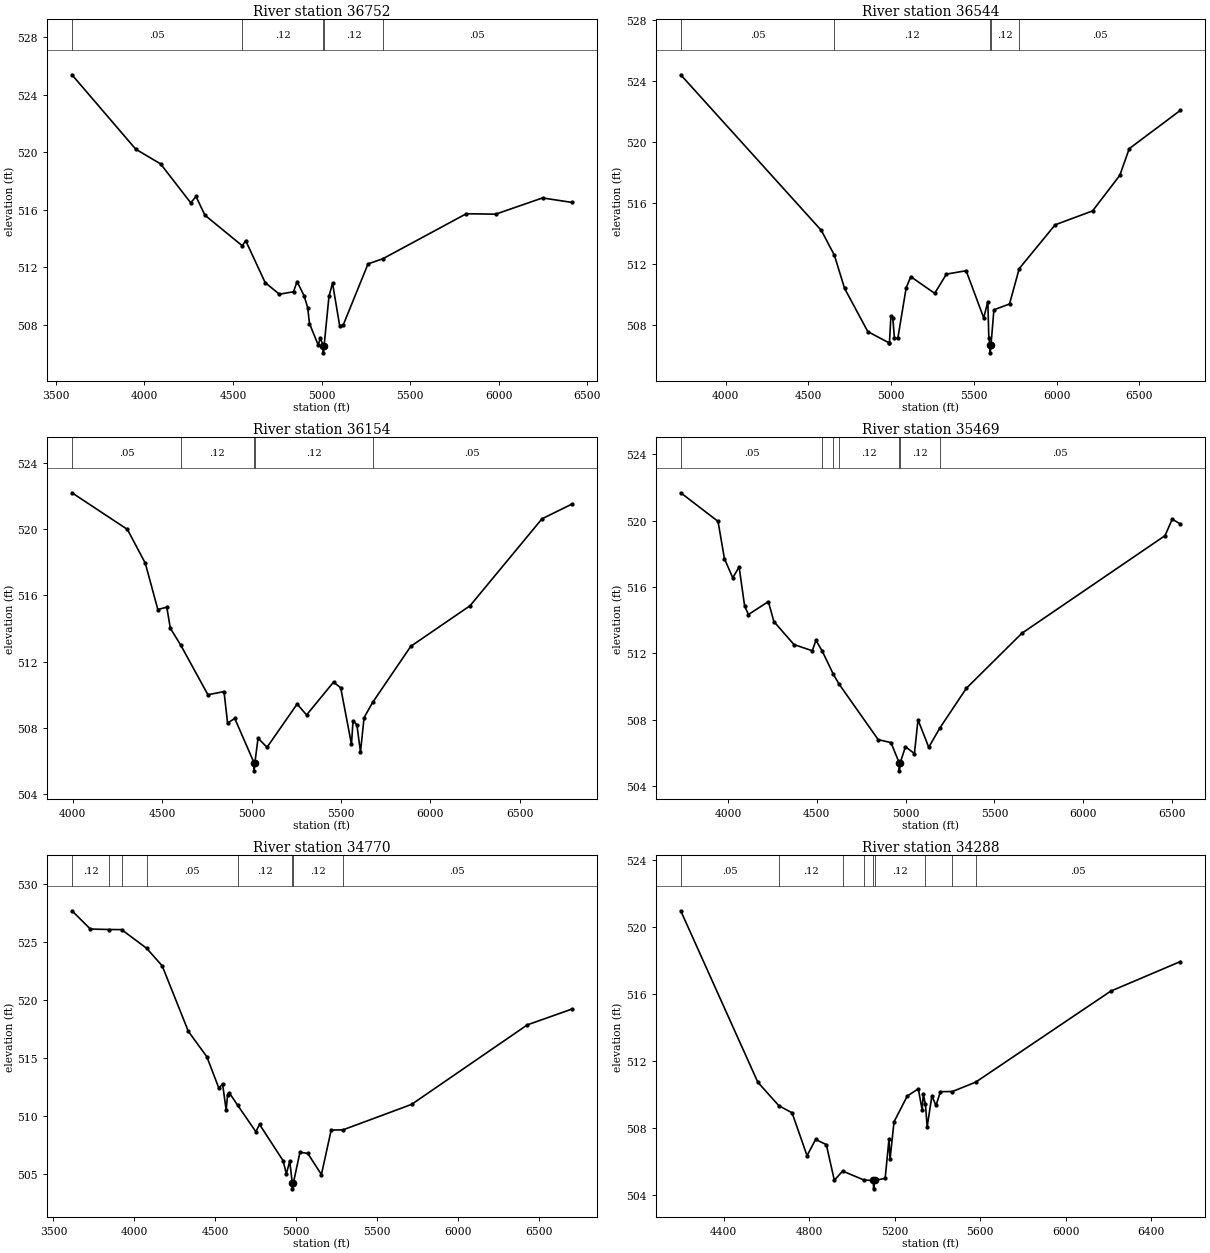
Type RM Length L Ch R = 1,36752,208,208,208
BEGIN DESCRIPTION:
High Point Creek 60.0
END DESCRIPTION:
XS GIS Cut Line= 4
      2643275.97      6994561.00      2641867.58      6994566.94
      2641549.50      6994549.15      2640660.86      6995184.36
#Sta/Elev= 30
  3591.6  525.38  3951.6  520.20  4091.6  519.18  4261.6  516.47  4291.6  516.91
  4341.6  515.61  4552.6  513.48  4571.6  513.84  4681.6  510.92  4761.6  510.11
  4841.6  510.28  4861.6  510.99  4901.6  509.99  4921.6  509.17  4931.6  508.07
  4981.6  506.55  4991.6  507.08  5009.0  506.53  5009.7  506.03  5014.2  506.53
  5041.6  509.96  5061.7  510.88  5101.7  507.93  5121.8  507.96  5262.0  512.22
  5346.0  512.58  5816.3  515.71  5982.2  515.68  6246.3  516.81  6410.9  516.50
#Mann=5,-1,0
  3591.6    0.05       0  4552.6    0.12       0  5009.0    0.07       0
  5014.2    0.12       0  5346.0    0.05       0
Bank Sta=5009,5014.2
Exp/Cntr=0.3,0.1

Type RM Length L Ch R = 1,36544,390,390,390
BEGIN DESCRIPTION:
Mapping XS 6711c6da
END DESCRIPTION:
XS GIS Cut Line= 4
      2643193.68      6994479.63      2641940.20      6994378.93
      2641533.95      6994309.49      2640219.47      6993993.87
#Sta/Elev= 30
  3727.7  524.40  4578.1  514.20  4656.6  512.58  4718.6  510.40  4859.0  507.57
  4984.8  506.85  4989.9  506.85  4998.6  508.58  5009.8  508.47  5019.9  507.16
  5040.2  507.12  5090.9  510.44  5118.8  511.17  5263.4  510.08  5334.4  511.34
  5453.5  511.56  5559.8  508.47  5584.6  509.54  5590.7  507.17  5598.3  506.68
  5599.0  506.18  5603.6  506.68  5621.4  509.00  5715.7  509.38  5774.5  511.70
  5991.7  514.57  6218.0  515.48  6382.5  517.81  6439.7  519.56  6749.2  522.07
#Mann=5,-1,0
  3727.7    0.05       0  4656.6    0.12       0  5598.3    0.07       0
  5603.6    0.12       0  5774.5    0.05       0
Bank Sta=5598.3,5603.6
Exp/Cntr=0.3,0.1

Type RM Length L Ch R = 1,36154,685,685,685
BEGIN DESCRIPTION:
High Point Creek 58.0
END DESCRIPTION:
XS GIS Cut Line= 3
      2643026.04      6994061.00      2642026.00      6994061.00
      2640240.77      6993889.37
#Sta/Elev= 30
  3996.2  522.18  4306.2  519.97  4406.2  517.93  4476.2  515.14  4526.2  515.28
  4546.2  514.01  4604.8  512.98  4756.2  510.00  4846.2  510.19  4866.2  508.29
  4906.2  508.57  5013.6  505.91  5014.4  505.41  5019.0  505.91  5036.4  507.38
  5086.7  506.83  5254.9  509.44  5307.7  508.78  5458.4  510.76  5498.5  510.42
  5558.8  507.01  5567.4  508.43  5589.0  508.19  5609.1  506.54  5629.1  508.62
  5677.8  509.55  5890.3  512.92  6221.9  515.37  6623.7  520.61  6789.7  521.49
#Mann=5,-1,0
  3996.2    0.05       0  4604.8    0.12       0  5013.6    0.07       0
  5019.0    0.12       0  5677.8    0.05       0
Bank Sta=5013.6,5019
Exp/Cntr=0.3,0.1

Type RM Length L Ch R = 1,35469,699,699,699
BEGIN DESCRIPTION:
High Point Creek 56.0
END DESCRIPTION:
XS GIS Cut Line= 3
      2643055.17      6993786.00      2641855.52      6993491.10
      2640290.07      6993684.37
#Sta/Elev= 30
  3734.4  521.67  3944.3  519.95  3980.6  517.70  4027.3  516.55  4063.1  517.21
  4094.0  514.86  4115.6  514.34  4227.8  515.12  4258.7  513.92  4372.0  512.53
  4475.0  512.16  4495.6  512.79  4530.9  512.14  4594.0  510.73  4626.5  510.14
  4845.7  506.81  4917.8  506.63  4963.6  505.43  4964.7  504.93  4970.2  505.43
  4999.5  506.38  5049.9  505.97  5070.0  508.00  5130.5  506.35  5193.1  507.51
  5342.1  509.90  5654.4  513.21  6460.5  519.09  6500.8  520.08  6547.1  519.79
#Mann=7,-1,0
  3734.4    0.05       0  4530.9    0.12       0  4594.0    0.05       0
  4626.5    0.12       0  4963.6    0.07       0  4970.2    0.12       0
  5193.1    0.05       0
Bank Sta=4963.6,4970.2
Exp/Cntr=0.3,0.1

Type RM Length L Ch R = 1,34770,482,482,482
BEGIN DESCRIPTION:
High Point Creek 55.0
END DESCRIPTION:
XS GIS Cut Line= 3
      2643313.49      6992496.98      2641976.00      6992861.00
      2640390.46      6993472.45
#Sta/Elev= 30
  3614.7  527.67  3728.2  526.10  3843.0  526.06  3921.2  526.05  4075.3  524.45
  4171.7  522.94  4333.4  517.30  4447.5  515.12  4521.9  512.41  4544.8  512.78
  4566.8  510.52  4575.9  511.86  4586.3  512.01  4637.8  510.95  4750.1  508.67
  4772.8  509.30  4917.9  506.19  4938.6  505.05  4959.4  506.14  4974.9  504.26
  4976.0  503.76  4981.8  504.26  5022.3  506.90  5070.4  506.81  5155.0  504.99
  5215.2  508.81  5287.7  508.83  5711.6  511.02  6426.3  517.86  6700.2  519.21
#Mann=8,-1,0
  3614.7    0.12       0  3843.0    0.05       0  3921.2    0.12       0
  4075.3    0.05       0  4637.8    0.12       0  4974.9    0.07       0
  4981.8    0.12       0  5287.7    0.05       0
Bank Sta=4974.9,4981.8
Exp/Cntr=0.3,0.1

Type RM Length L Ch R = 1,34288,422,422,422
BEGIN DESCRIPTION:
High Point Creek 54.0
END DESCRIPTION:
XS GIS Cut Line= 3
      2642676.04      6992361.00      2641876.00      6992411.00
      2640390.48      6992805.85
#Sta/Elev= 30
  4198.8  520.97  4559.5  510.74  4658.3  509.33  4719.9  508.91  4790.0  506.35
  4830.1  507.32  4880.2  507.01  4917.7  504.88  4956.4  505.43  5057.9  504.89
  5100.4  504.87  5101.5  504.37  5107.4  504.87  5155.6  505.00  5173.4  507.32
  5178.5  506.13  5197.0  508.37  5259.1  509.91  5310.8  510.34  5328.8  509.08
  5334.0  510.02  5344.0  509.42  5352.2  508.07  5374.2  509.91  5393.6  509.35
  5414.3  510.17  5470.5  510.18  5579.3  510.74  6211.0  516.17  6537.5  517.94
#Mann=9,-1,0
  4198.8    0.05       0  4658.3    0.12       0  4956.4    0.05       0
  5057.9    0.12       0  5100.4    0.03       0  5107.4    0.12       0
  5344.0    0.05       0  5470.5    0.12       0  5579.3    0.05       0
Bank Sta=5100.4,5107.4
Exp/Cntr=0.3,0.1

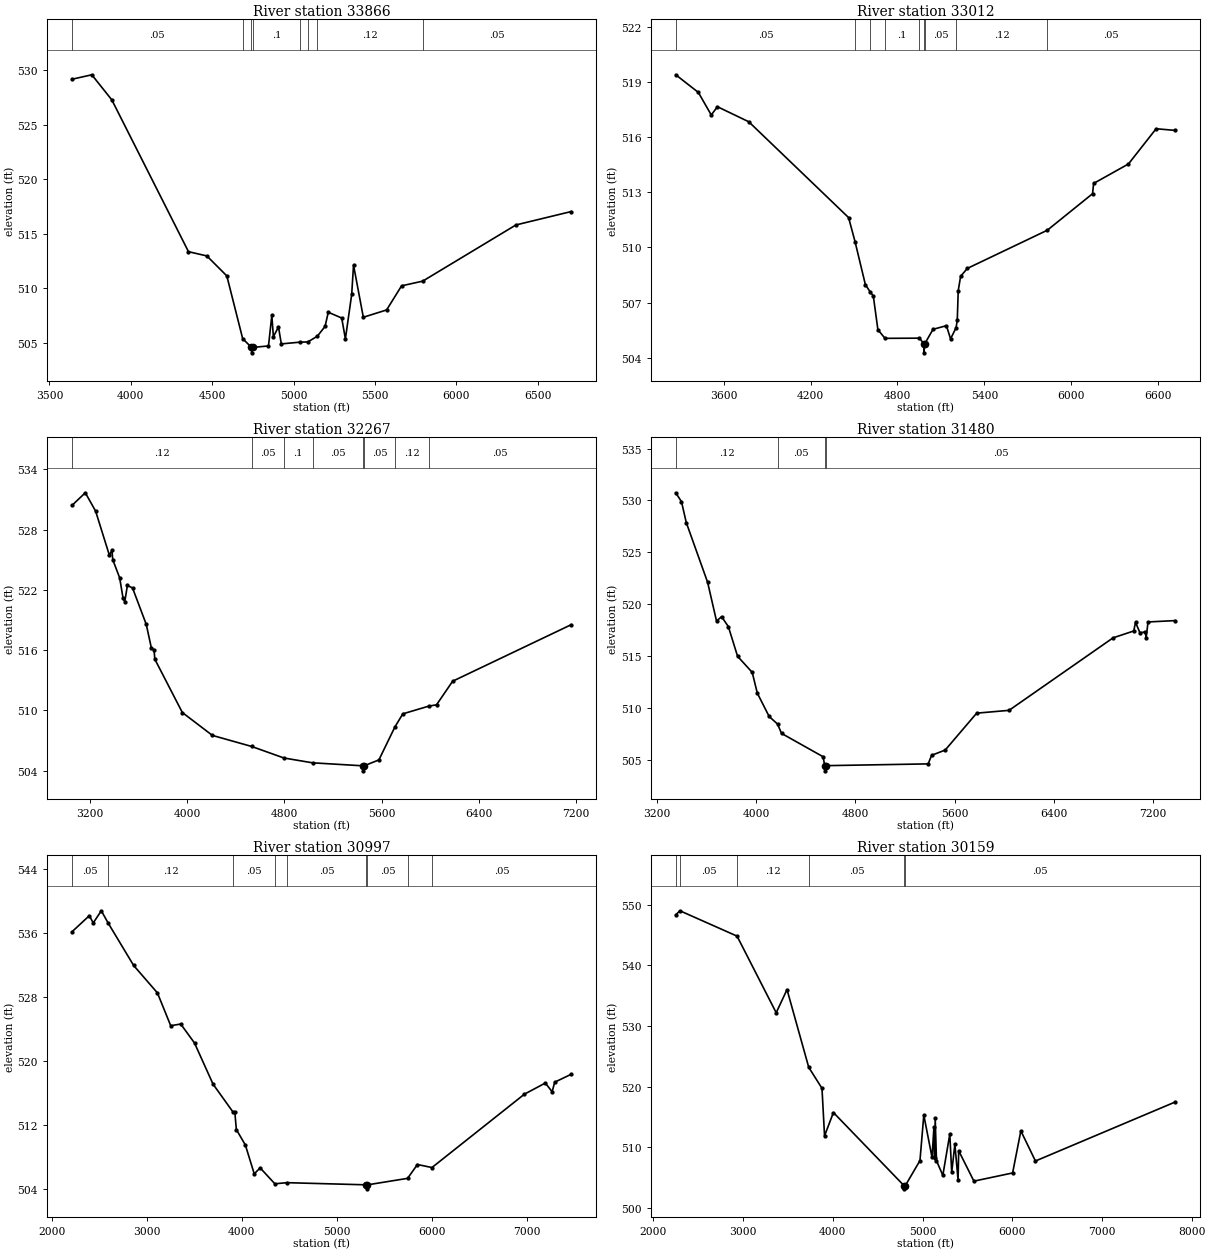
Type RM Length L Ch R = 1,33866,854,854,854
BEGIN DESCRIPTION:
Mapping XS 9779e075
END DESCRIPTION:
XS GIS Cut Line= 4
      2643105.15      6992313.40      2641782.21      6992021.73
      2640844.97      6991826.47      2640252.75      6992296.09
#Sta/Elev= 30
  3638.5  529.16  3760.5  529.57  3883.4  527.27  4354.4  513.36  4467.3  512.97
  4590.0  511.14  4687.4  505.39  4741.4  504.59  4742.5  504.09  4748.5  504.59
  4846.0  504.72  4866.4  507.52  4876.0  505.57  4907.4  506.46  4924.8  504.91
  5040.8  505.07  5087.7  505.09  5145.8  505.61  5193.6  506.51  5213.2  507.81
  5295.8  507.28  5318.4  505.37  5357.1  509.44  5368.4  512.13  5428.6  507.35
  5571.6  508.02  5663.6  510.23  5793.3  510.66  6366.2  515.81  6706.4  517.04
#Mann=8,-1,0
  3638.5    0.05       0  4687.4     0.1       0  4741.4    0.07       0
  4748.5     0.1       0  5040.8    0.12       0  5087.7    0.05       0
  5145.8    0.12       0  5793.3    0.05       0
Bank Sta=4741.4,4748.5
Exp/Cntr=0.3,0.1

Type RM Length L Ch R = 1,33012,745,745,745
BEGIN DESCRIPTION:
Mapping XS 5eadd66b
END DESCRIPTION:
XS GIS Cut Line= 4
      2643318.71      6991735.28      2641688.46      6991193.60
      2640780.84      6991601.71      2640282.76      6992143.25
#Sta/Elev= 30
  3268.6  519.41  3424.6  518.45  3513.8  517.22  3556.5  517.67  3772.9  516.85
  4462.2  511.63  4506.8  510.32  4578.1  507.98  4610.4  507.59  4633.0  507.36
  4664.7  505.52  4713.9  505.05  4952.0  505.06  4981.5  504.76  4982.6  504.26
  4988.7  504.76  5045.3  505.54  5137.9  505.74  5166.6  505.02  5204.7  505.63
  5212.9  506.04  5219.4  507.64  5236.0  508.43  5282.3  508.86  5834.6  510.94
  6147.2  512.93  6154.6  513.49  6395.0  514.55  6586.2  516.47  6717.4  516.38
#Mann=9,-1,0
  3268.6    0.05       0  4506.8    0.12       0  4610.4    0.05       0
  4713.9     0.1       0  4952.0    0.05       0  4981.5    0.03       0
  4988.7    0.05       0  5204.7    0.12       0  5834.6    0.05       0
Bank Sta=4981.5,4988.7
Exp/Cntr=0.3,0.1

Type RM Length L Ch R = 1,32267,787,787,787
BEGIN DESCRIPTION:
Mapping XS 2a37d51c
END DESCRIPTION:
XS GIS Cut Line= 4
      2642797.87      6989287.33      2641657.21      6990375.89
      2641344.71      6990579.02      2639293.41      6991266.26
#Sta/Elev= 30
  3050.0  530.42  3160.1  531.68  3245.0  529.85  3357.9  525.47  3379.3  525.93
  3386.2  525.01  3442.8  523.21  3471.2  521.16  3485.3  520.83  3506.7  522.45
  3549.2  522.19  3662.1  518.56  3704.5  516.19  3725.9  516.03  3732.8  515.09
  3959.3  509.78  4206.8  507.50  4529.9  506.40  4795.8  505.25  5031.2  504.77
  5447.3  504.47  5448.5  503.97  5455.9  504.47  5578.1  505.06  5709.7  508.34
  5775.1  509.65  5989.4  510.42  6052.7  510.55  6185.3  512.90  7162.8  518.54
#Mann=8,-1,0
  3050.0    0.12       0  4529.9    0.05       0  4795.8     0.1       0
  5031.2    0.05       0  5447.3    0.07       0  5455.9    0.05       0
  5709.7    0.12       0  5989.4    0.05       0
Bank Sta=5447.3,5455.9
Exp/Cntr=0.3,0.1

Type RM Length L Ch R = 1,31480,483,483,483
BEGIN DESCRIPTION:
High Point Creek 48.0
END DESCRIPTION:
XS GIS Cut Line= 3
      2642575.99      6989361.00      2641026.00      6989911.00
      2639016.62      6991193.58
#Sta/Elev= 30
  3350.7  530.74  3397.0  529.88  3435.6  527.87  3607.8  522.11  3679.6  518.38
  3720.6  518.80  3775.1  517.84  3849.4  514.98  3967.6  513.43  4008.6  511.43
  4104.1  509.18  4171.8  508.45  4203.9  507.55  4539.1  505.30  4552.7  504.44
  4554.3  503.94  4564.0  504.44  5386.9  504.61  5415.0  505.44  5524.2  505.94
  5778.4  509.50  6039.4  509.77  6878.8  516.76  7045.5  517.42  7059.6  518.26
  7095.2  517.25  7139.4  517.33  7145.3  516.74  7160.6  518.29  7379.2  518.42
#Mann=4,-1,0
  3350.7    0.12       0  4171.8    0.05       0  4552.7    0.03       0
  4564.0    0.05       0
Bank Sta=4552.7,4564
Exp/Cntr=0.3,0.1

Type RM Length L Ch R = 1,30997,838,838,838
BEGIN DESCRIPTION:
High Point Creek 47.0
END DESCRIPTION:
XS GIS Cut Line= 3
      2643655.41      6988893.43      2640926.00      6989461.00
      2639063.47      6991084.22
#Sta/Elev= 30
  2212.2  536.11  2395.5  538.13  2436.3  537.22  2521.3  538.74  2595.2  537.17
  2861.8  531.91  3112.2  528.48  3252.3  524.38  3357.6  524.59  3502.8  522.22
  3698.0  517.08  3906.7  513.62  3927.5  513.56  3943.4  511.41  4038.5  509.47
  4131.8  505.87  4193.9  506.62  4348.9  504.63  4476.7  504.77  5312.9  504.50
  5314.4  504.00  5324.2  504.50  5746.5  505.31  5850.2  507.04  6003.0  506.66
  6977.1  515.83  7197.3  517.22  7268.3  516.13  7296.1  517.33  7470.6  518.32
#Mann=9,-1,0
  2212.2    0.05       0  2595.2    0.12       0  3906.7    0.05       0
  4348.9     0.1       0  4476.7    0.05       0  5312.9    0.03       0
  5324.2    0.05       0  5746.5    0.12       0  6003.0    0.05       0
Bank Sta=5312.9,5324.2
Exp/Cntr=0.3,0.1

Type RM Length L Ch R = 1,30159,25,25,25
BEGIN DESCRIPTION:
Mapping XS 06f0a95f
END DESCRIPTION:
XS GIS Cut Line= 6
      2642799.61      6986905.38      2642158.95      6987457.49
      2640688.46      6988714.43      2640136.38      6989292.56
      2639355.13      6990079.02      2639121.15      6990926.56
#Sta/Elev= 30
  2248.3  548.34  2294.9  549.01  2931.7  544.83  3368.2  532.19  3488.9  536.01
  3730.8  523.19  3878.7  519.72  3907.2  511.88  4006.0  515.73  4795.0  503.64
  4796.6  503.14  4806.6  503.64  4971.0  507.80  5013.8  515.31  5105.8  508.31
  5126.8  513.33  5134.1  508.16  5141.0  514.76  5155.1  507.78  5225.9  505.36
  5303.6  512.16  5325.0  505.89  5360.2  510.48  5395.8  504.61  5402.7  509.42
  5572.5  504.41  6003.9  505.76  6095.8  512.70  6258.4  507.73  7815.7  517.46
#Mann=6,-1,0
  2248.3    0.12       0  2294.9    0.05       0  2931.7    0.12       0
  3730.8    0.05       0  4795.0    0.03       0  4806.6    0.05       0
Bank Sta=4795,4806.6
Exp/Cntr=0.3,0.1

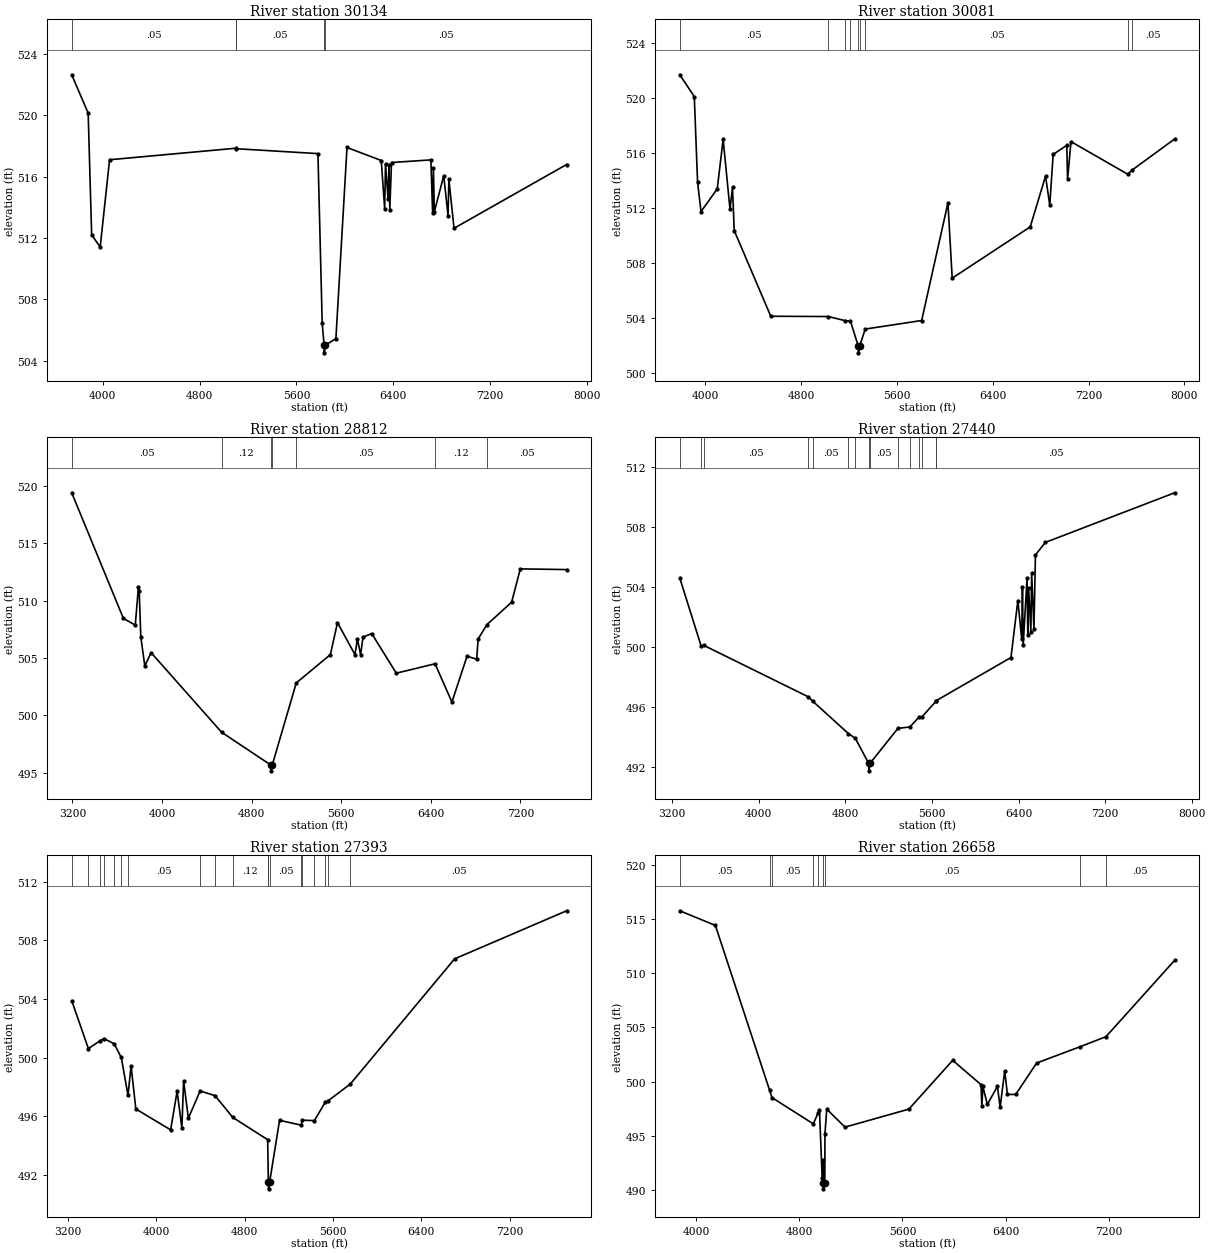
Type RM Length L Ch R = 1,30134,53,53,53
BEGIN DESCRIPTION:
Mapping XS 040ee50c
END DESCRIPTION:
XS GIS Cut Line= 6
      2641620.73      6987834.25      2641372.41      6988029.93
      2641322.76      6988057.71      2639724.92      6989620.68
      2639308.26      6990073.81      2639053.04      6990901.95
#Sta/Elev= 30
  3742.9  522.64  3878.8  520.14  3907.7  512.20  3978.2  511.41  4055.9  517.10
  5098.5  517.85  5100.5  517.82  5778.1  517.50  5813.3  506.47  5828.9  505.01
  5830.5  504.51  5840.5  505.01  5926.6  505.44  6018.4  517.90  6301.4  517.05
  6329.7  513.91  6336.6  516.83  6358.0  514.53  6365.3  516.76  6372.1  513.85
  6386.3  516.92  6711.8  517.09  6726.0  513.64  6732.8  516.59  6740.2  513.70
  6817.9  516.06  6853.6  513.45  6860.4  515.83  6903.0  512.63  7833.6  516.79
#Mann=5,-1,0
  3742.9    0.05       0  5098.5    0.12       0  5100.5    0.05       0
  5828.9    0.03       0  5840.5    0.05       0
Bank Sta=5828.9,5840.5
Exp/Cntr=0.3,0.1

Type RM Length L Ch R = 1,30081,1269,1269,1269
BEGIN DESCRIPTION:
Mapping XS bfd9e04b
END DESCRIPTION:
XS GIS Cut Line= 6
      2641579.08      6987823.82      2641023.28      6988290.00
      2640677.86      6988627.73      2639875.77      6989393.36
      2639219.71      6990120.68      2638980.12      6990917.59
#Sta/Elev= 30
  3788.8  521.70  3910.2  520.12  3937.6  513.89  3966.2  511.75  4101.5  513.40
  4150.9  517.00  4208.1  511.92  4229.0  513.51  4243.3  510.37  4548.4  504.14
  5028.8  504.12  5168.7  503.82  5212.7  503.79  5278.1  501.98  5279.7  501.48
  5289.7  501.98  5337.0  503.21  5807.2  503.83  6026.4  512.38  6062.0  506.91
  6713.1  510.64  6840.9  514.33  6876.0  512.22  6904.4  515.91  7018.0  516.57
  7024.7  514.12  7053.1  516.84  7526.3  514.47  7561.2  514.76  7917.8  517.03
#Mann=9,-1,0
  3788.8    0.05       0  5028.8    0.12       0  5168.7    0.05       0
  5212.7    0.12       0  5278.1    0.03       0  5289.7    0.12       0
  5337.0    0.05       0  7526.3    0.12       0  7561.2    0.05       0
Bank Sta=5278.1,5289.7
Exp/Cntr=0.3,0.1

Type RM Length L Ch R = 1,28812,1372,1372,1372
BEGIN DESCRIPTION:
Mapping XS 5a555ceb
END DESCRIPTION:
XS GIS Cut Line= 3
      2641037.45      6986870.66      2639803.05      6988193.60
      2638115.58      6990183.15
#Sta/Elev= 30
  3194.6  519.42  3655.8  508.46  3761.9  507.87  3790.2  511.20  3797.0  510.86
  3811.2  506.87  3846.9  504.32  3903.5  505.47  4532.4  498.53  4973.0  495.66
  4974.6  495.16  4984.7  495.66  5199.3  502.83  5503.6  505.30  5567.3  508.09
  5723.3  505.30  5745.3  506.66  5773.9  505.28  5794.8  506.82  5872.7  507.14
  6092.4  503.68  6438.1  504.50  6588.9  501.16  6724.0  505.16  6809.8  504.90
  6823.2  506.68  6902.1  507.92  7121.7  509.87  7199.7  512.78  7612.8  512.72
#Mann=7,-1,0
  3194.6    0.05       0  4532.4    0.12       0  4973.0    0.07       0
  4984.7    0.12       0  5199.3    0.05       0  6438.1    0.12       0
  6902.1    0.05       0
Bank Sta=4973,4984.7
Exp/Cntr=0.3,0.1

Type RM Length L Ch R = 1,27440,47,47,47
BEGIN DESCRIPTION:
Mapping XS 51947aa6
END DESCRIPTION:
XS GIS Cut Line= 6
      2640068.66      6986870.68      2639881.17      6986844.64
      2638719.71      6987651.93      2638542.63      6988026.93
      2638297.84      6988151.93      2636714.82      6989766.24
#Sta/Elev= 30
  3269.6  504.60  3468.1  500.04  3492.2  500.10  4456.8  496.67  4496.4  496.39
  4829.0  494.21  4892.3  493.90  5015.6  492.23  5017.3  491.73  5027.8  492.23
  5285.2  494.56  5396.5  494.66  5478.5  495.30  5509.1  495.34  5641.1  496.40
  5641.9  496.42  6330.5  499.29  6394.0  503.09  6429.2  500.54  6436.6  504.01
  6443.4  500.13  6479.1  504.60  6485.9  500.76  6493.3  503.92  6514.2  501.02
  6521.6  504.92  6542.6  501.21  6556.8  506.14  6648.6  506.97  7842.7  510.28
#Mann=15,-1,0
  3269.6    0.05       0  3468.1    0.12       0  3492.2    0.05       0
  4456.8    0.12       0  4496.4    0.05       0  4829.0    0.12       0
  4892.3    0.05       0  5015.6    0.03       0  5027.8    0.05       0
  5285.2    0.12       0  5396.5    0.05       0  5478.5    0.12       0
  5509.1    0.05       0  5641.1    0.12       0  5641.9    0.05       0
Bank Sta=5015.6,5027.8
Exp/Cntr=0.3,0.1

Type RM Length L Ch R = 1,27393,735,735,735
BEGIN DESCRIPTION:
Mapping XS 7c424797
END DESCRIPTION:
XS GIS Cut Line= 6
      2640027.00      6986797.77      2639849.92      6986808.18
      2638683.26      6987615.48      2638532.21      6987980.06
      2638287.42      6988089.43      2636746.49      6989666.81
#Sta/Elev= 30
  3234.1  503.89  3385.0  500.63  3491.2  501.16  3526.3  501.31  3617.4  500.96
  3682.9  500.03  3743.7  497.44  3771.8  499.45  3814.8  496.51  4130.0  495.09
  4188.7  497.72  4231.8  495.21  4247.5  498.43  4290.5  495.88  4397.0  497.74
  4532.6  497.42  4692.3  495.94  5008.8  494.42  5015.3  491.57  5017.0  491.07
  5027.5  491.57  5116.5  495.74  5312.1  495.41  5323.1  495.75  5432.4  495.72
  5531.6  496.99  5550.8  497.04  5757.1  498.21  6701.5  506.74  7716.5  510.02
#Mann=19,-1,0
  3234.1    0.05       0  3385.0    0.12       0  3491.2    0.05       0
  3526.3    0.12       0  3617.4    0.05       0  3682.9    0.12       0
  3743.7    0.05       0  4397.0    0.12       0  4532.6    0.05       0
  4692.3    0.12       0  5008.8    0.05       0  5015.3    0.07       0
  5027.5    0.05       0  5312.1    0.12       0  5323.1    0.05       0
  5432.4    0.12       0  5531.6    0.05       0  5550.8    0.12       0
  5757.1    0.05       0
Bank Sta=5015.3,5027.5
Exp/Cntr=0.3,0.1

Type RM Length L Ch R = 1,26658,72,72,72
BEGIN DESCRIPTION:
Mapping XS fc0453e3
END DESCRIPTION:
XS GIS Cut Line= 6
      2638782.25      6986927.08      2637955.83      6987697.94
      2637761.38      6987899.33      2637721.59      6988059.79
      2637636.38      6988197.94      2636136.40      6989663.20
#Sta/Elev= 30
  3874.8  515.75  4150.9  514.40  4571.7  499.18  4588.7  498.53  4909.6  496.10
  4946.0  497.08  4957.5  497.38  4978.5  491.08  4985.8  492.80  4986.4  490.61
  4988.1  490.11  4998.8  490.61  5000.0  495.20  5014.0  497.46  5155.5  495.80
  5650.3  497.46  5989.8  501.96  6209.0  499.72  6216.0  497.71  6223.1  499.57
  6258.4  497.89  6336.3  499.56  6357.4  497.64  6392.9  500.98  6414.0  498.82
  6477.7  498.81  6640.3  501.71  6973.6  503.20  7177.3  504.14  7709.4  511.18
#Mann=9,-1,0
  3874.8    0.05       0  4571.7    0.12       0  4588.7    0.05       0
  4909.6    0.12       0  4946.0    0.05       0  4986.4    0.03       0
  4998.8    0.05       0  6973.6    0.12       0  7177.3    0.05       0
Bank Sta=4986.4,4998.8
Exp/Cntr=0.3,0.1