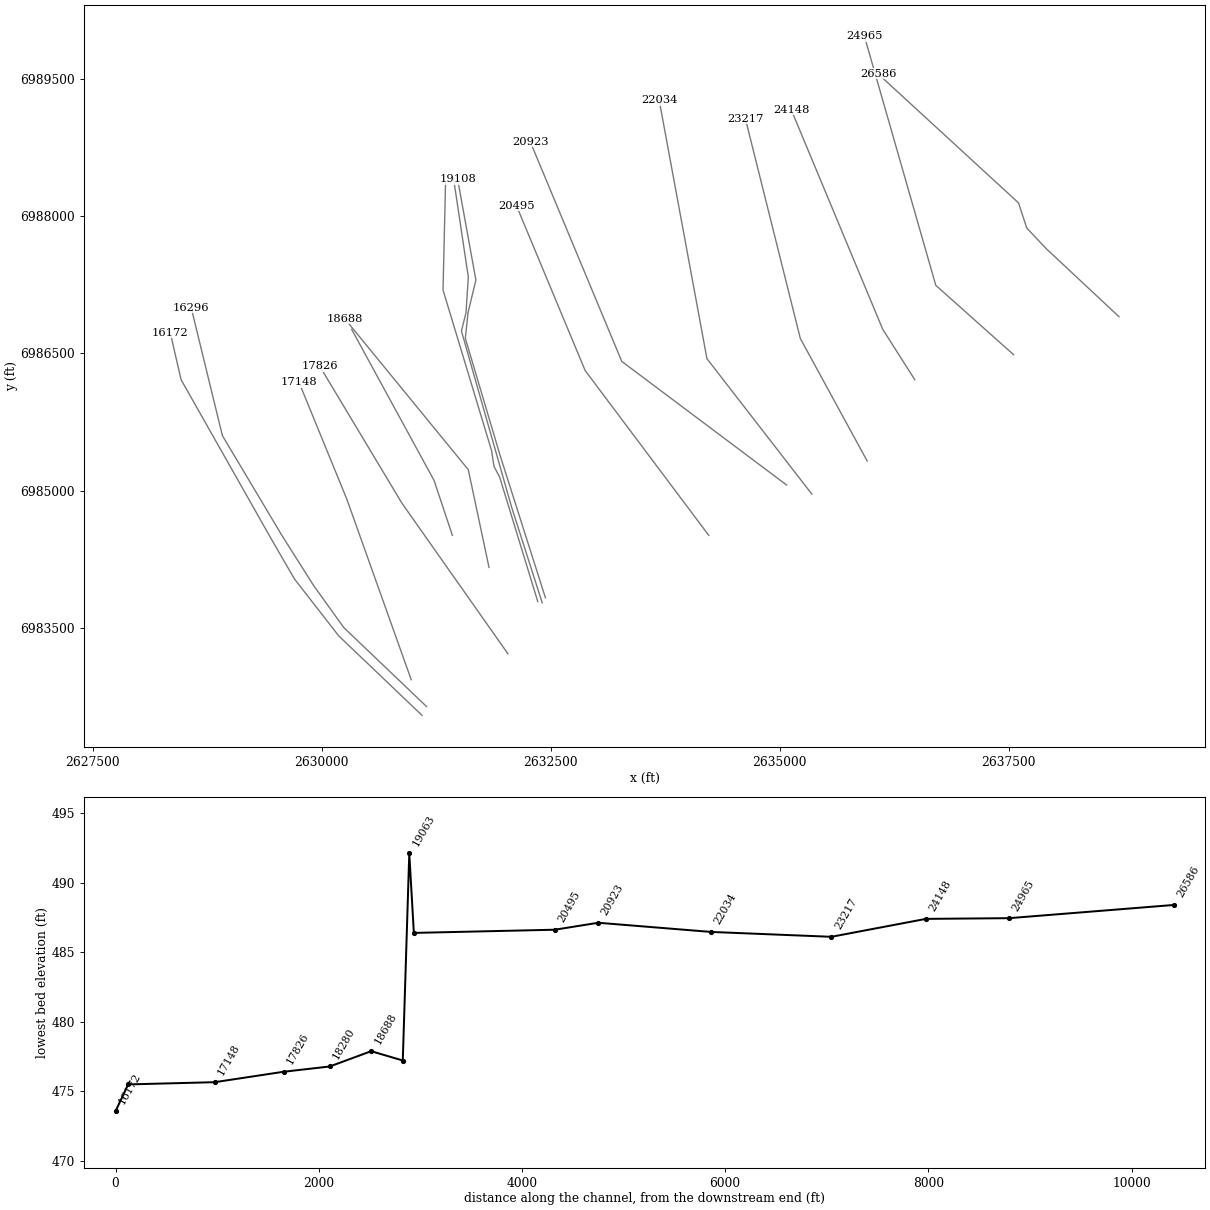
HEC-RAS study High Point Creek.prj: High Point Creek Base Level Engineering

--- High Point Creek.g01 (geometry) --- (continued)

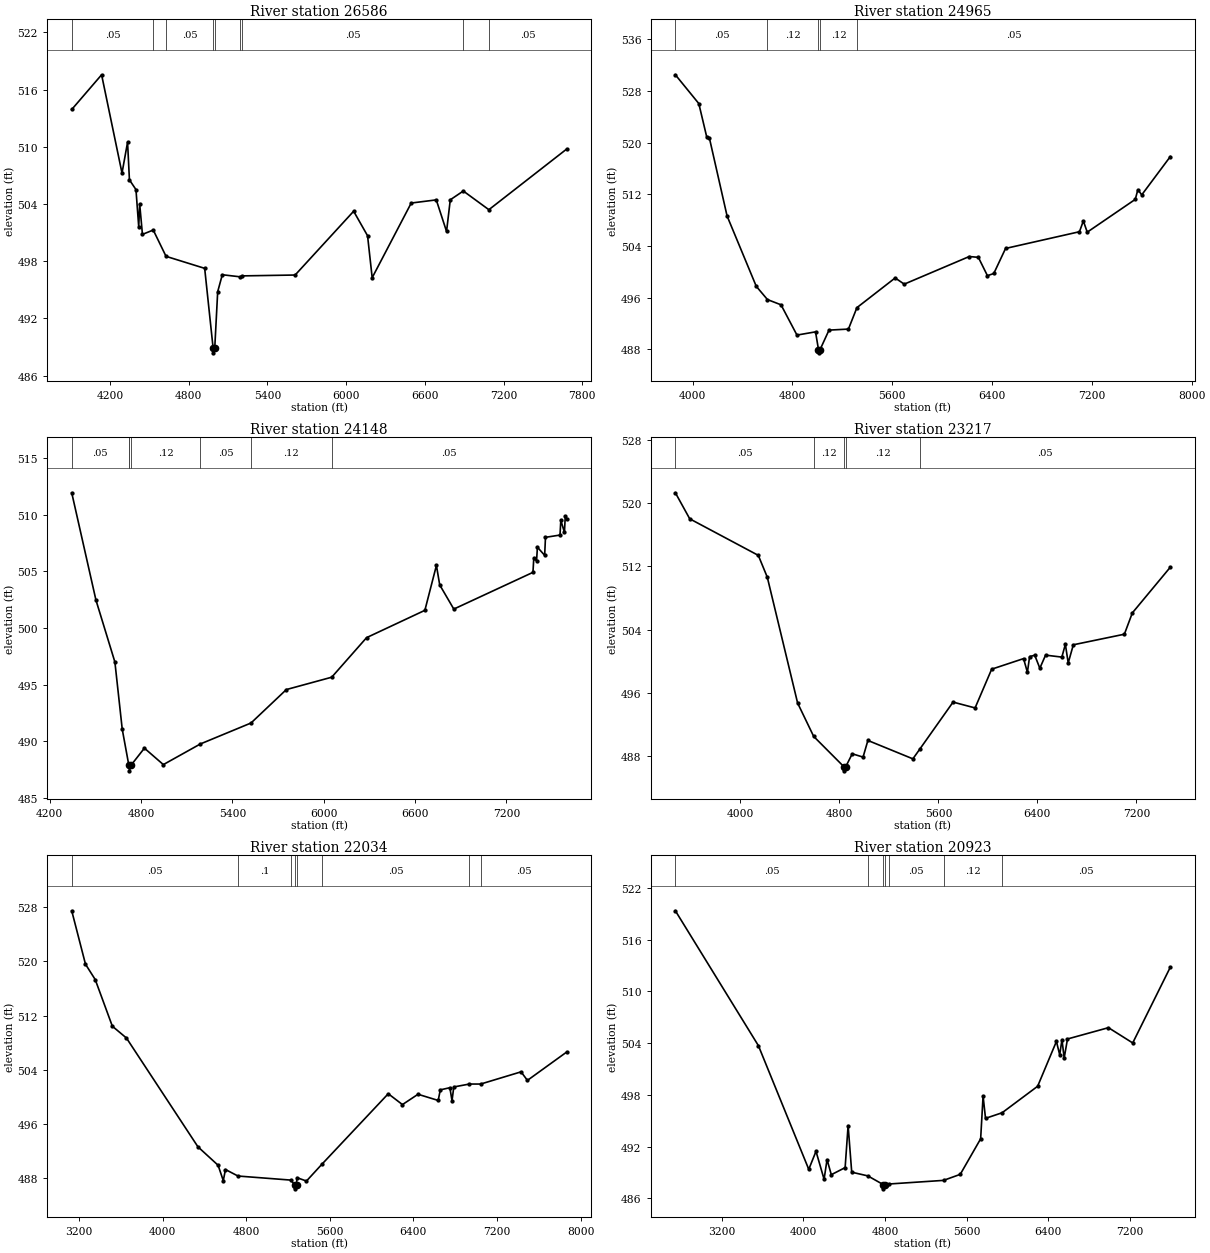
Type RM Length L Ch R = 1,26586,1621,1621,1621
BEGIN DESCRIPTION:
Mapping XS b7114090
END DESCRIPTION:
XS GIS Cut Line= 5
      2638705.85      6986899.31      2637909.52      6987643.88
      2637699.02      6987867.08      2637608.60      6988142.39
      2636073.87      6989552.12
#Sta/Elev= 30
  3909.8  513.91  4137.4  517.55  4292.9  507.24  4335.2  510.48  4349.4  506.53
  4399.2  505.51  4420.2  501.61  4427.5  504.00  4448.5  500.81  4530.8  501.27
  4628.3  498.51  4922.7  497.25  4987.0  488.89  4988.7  488.39  4999.4  488.89
  5021.8  494.80  5057.0  496.58  5194.5  496.36  5208.1  496.46  5611.8  496.55
  6057.6  503.24  6163.6  500.67  6198.8  496.27  6496.3  504.10  6687.1  504.43
  6765.4  501.12  6793.8  504.44  6893.1  505.36  7087.8  503.40  7680.5  509.76
#Mann=9,-1,0
  3909.8    0.05       0  4530.8    0.12       0  4628.3    0.05       0
  4987.0    0.03       0  4999.4    0.05       0  5194.5    0.12       0
  5208.1    0.05       0  6893.1    0.12       0  7087.8    0.05       0
Bank Sta=4987,4999.4
Exp/Cntr=0.3,0.1

Type RM Length L Ch R = 1,24965,817,817,817
BEGIN DESCRIPTION:
High Point Creek 36.0
END DESCRIPTION:
XS GIS Cut Line= 3
      2637554.91      6986484.28      2636705.36      6987241.59
      2635925.99      6989961.02
#Sta/Elev= 30
  3861.9  530.51  4049.8  526.05  4114.1  520.81  4135.0  520.68  4276.3  508.64
  4510.4  497.74  4600.1  495.69  4708.6  494.88  4836.5  490.19  4985.3  490.69
  5009.1  487.94  5010.8  487.44  5021.7  487.94  5093.3  490.96  5249.0  491.12
  5317.0  494.44  5623.5  499.04  5696.4  498.08  6217.7  502.36  6290.4  502.23
  6363.1  499.39  6414.1  499.73  6508.5  503.61  7100.7  506.20  7131.9  507.87
  7163.1  506.13  7548.0  511.21  7568.8  512.71  7600.0  511.91  7828.9  517.84
#Mann=5,-1,0
  3861.9    0.05       0  4600.1    0.12       0  5009.1    0.07       0
  5021.7    0.12       0  5317.0    0.05       0
Bank Sta=5009.1,5021.7
Exp/Cntr=0.3,0.1

Type RM Length L Ch R = 1,24148,931,931,931
BEGIN DESCRIPTION:
High Point Creek 35.0
END DESCRIPTION:
XS GIS Cut Line= 3
      2636476.01      6986210.99      2636126.00      6986761.00
      2635126.01      6989160.97
#Sta/Elev= 30
  4344.0  511.92  4503.2  502.45  4627.6  496.99  4675.9  491.06  4718.6  487.93
  4721.2  487.89  4723.0  487.39  4733.9  487.89  4821.5  489.39  4946.0  487.94
  5189.1  489.76  5522.0  491.61  5754.3  494.56  6052.2  495.65  6281.3  499.14
  6664.3  501.55  6740.1  505.51  6761.8  503.79  6854.4  501.66  7374.4  504.90
  7379.8  506.14  7398.2  505.92  7403.6  507.12  7451.3  506.40  7456.7  507.99
  7552.1  508.19  7557.5  509.49  7581.3  508.43  7586.7  509.87  7595.9  509.64
#Mann=7,-1,0
  4344.0    0.05       0  4718.6    0.12       0  4721.2    0.07       0
  4733.9    0.12       0  5189.1    0.05       0  5522.0    0.12       0
  6052.2    0.05       0
Bank Sta=4721.2,4733.9
Exp/Cntr=0.3,0.1

Type RM Length L Ch R = 1,23217,1183,1183,1183
BEGIN DESCRIPTION:
High Point Creek 33.0
END DESCRIPTION:
XS GIS Cut Line= 3
      2635955.95      6985322.84      2635226.00      6986661.00
      2634625.99      6989061.03
#Sta/Elev= 30
  3475.3  521.33  3591.4  518.03  4145.3  513.40  4217.9  510.63  4462.8  494.69
  4592.7  490.46  4838.1  486.60  4839.9  486.10  4850.8  486.60  4904.2  488.26
  4991.5  487.84  5030.5  489.95  5393.9  487.62  5450.2  488.86  5718.6  494.81
  5896.4  494.07  6030.4  498.98  6288.1  500.32  6319.0  498.59  6337.0  500.57
  6378.3  500.75  6419.5  499.10  6465.9  500.76  6597.3  500.51  6625.7  502.13
  6648.8  499.77  6690.1  502.07  7102.4  503.41  7166.8  506.11  7473.5  511.90
#Mann=5,-1,0
  3475.3    0.05       0  4592.7    0.12       0  4838.1    0.07       0
  4850.8    0.12       0  5450.2    0.05       0
Bank Sta=4838.1,4850.8
Exp/Cntr=0.3,0.1

Type RM Length L Ch R = 1,22034,1111,1111,1111
BEGIN DESCRIPTION:
High Point Creek 32.0
END DESCRIPTION:
XS GIS Cut Line= 3
      2635351.65      6984961.84      2634206.02      6986440.96
      2633685.00      6989260.42
#Sta/Elev= 30
  3129.1  527.47  3260.8  519.59  3354.1  517.32  3518.0  510.44  3652.9  508.70
  4337.3  492.65  4530.2  489.93  4580.0  487.66  4600.8  489.30  4720.7  488.34
  5226.3  487.74  5268.1  486.95  5269.9  486.45  5281.1  486.95  5284.8  488.10
  5376.3  487.60  5522.4  490.05  6159.3  500.48  6295.0  498.88  6444.1  500.40
  6637.3  499.49  6657.6  501.05  6749.2  501.37  6769.5  499.45  6786.7  501.48
  6935.8  501.91  7044.1  501.91  7430.5  503.71  7491.5  502.45  7867.2  506.63
#Mann=8,-1,0
  3129.1    0.05       0  4720.7     0.1       0  5226.3    0.12       0
  5268.1    0.07       0  5281.1    0.12       0  5522.4    0.05       0
  6935.8    0.12       0  7044.1    0.05       0
Bank Sta=5268.1,5281.1
Exp/Cntr=0.3,0.1

Type RM Length L Ch R = 1,20923,428,428,428
BEGIN DESCRIPTION:
High Point Creek 30.0
END DESCRIPTION:
XS GIS Cut Line= 3
      2635075.97      6985061.03      2633276.00      6986411.00
      2632275.98      6988811.04
#Sta/Elev= 30
  2745.9  519.34  3559.4  503.71  4053.1  489.37  4124.0  491.46  4203.1  488.22
  4232.3  490.50  4274.0  488.75  4409.4  489.57  4438.6  494.45  4474.0  489.04
  4632.0  488.61  4781.9  487.61  4783.8  487.11  4795.3  487.61  4837.7  487.67
  5373.6  488.09  5537.5  488.79  5737.4  492.91  5761.2  497.87  5785.1  495.28
  5948.0  495.93  6295.9  499.00  6480.0  504.20  6512.0  502.64  6534.2  504.40
  6555.9  502.27  6588.4  504.48  6989.7  505.79  7227.5  504.02  7595.9  512.80
#Mann=7,-1,0
  2745.9    0.05       0  4632.0     0.1       0  4781.9    0.03       0
  4795.3     0.1       0  4837.7    0.05       0  5373.6    0.12       0
  5948.0    0.05       0
Bank Sta=4781.9,4795.3
Exp/Cntr=0.3,0.1

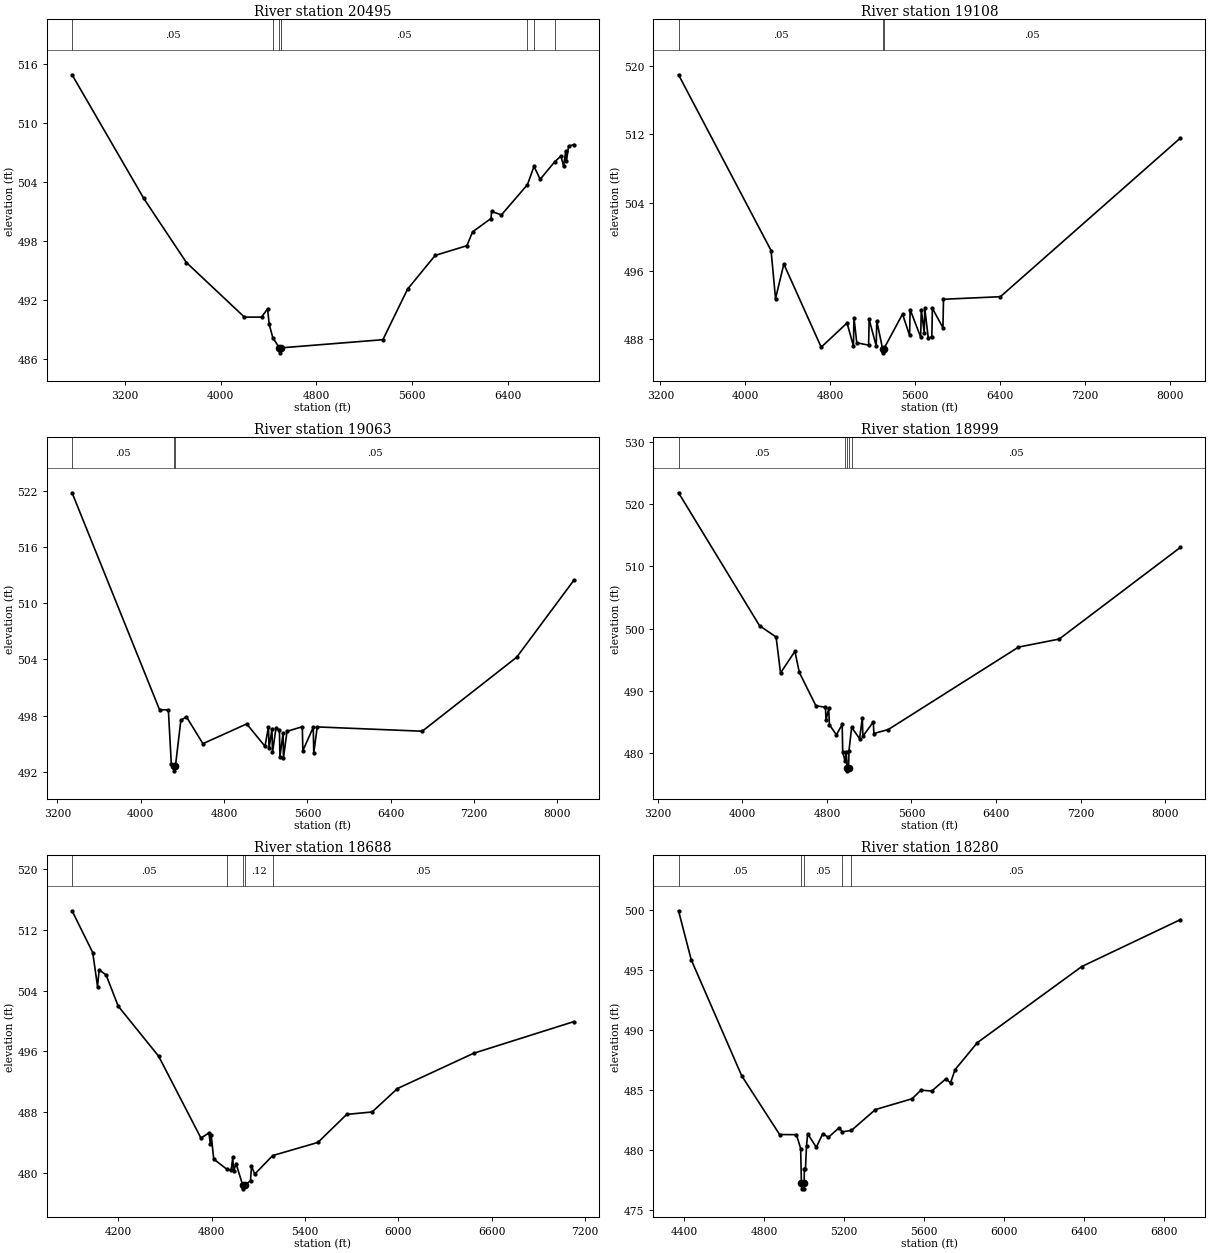
Type RM Length L Ch R = 1,20495,1387,1387,1387
BEGIN DESCRIPTION:
High Point Creek 29.0
END DESCRIPTION:
XS GIS Cut Line= 3
      2634226.00      6984511.01      2632876.00      6986311.00
      2632126.00      6988111.01
#Sta/Elev= 30
  2754.5  514.95  3354.5  502.35  3711.8  495.81  4197.2  490.25  4341.0  490.25
  4391.0  491.10  4404.5  489.51  4435.2  488.14  4490.5  487.11  4492.4  486.61
  4503.9  487.11  4505.8  487.12  5356.0  487.95  5563.0  493.11  5793.7  496.54
  6059.1  497.53  6106.8  498.94  6260.6  500.30  6266.0  501.02  6348.4  500.67
  6565.9  503.75  6620.8  505.61  6672.8  504.30  6794.5  506.09  6846.2  506.66
  6868.4  505.64  6886.8  507.20  6892.2  506.15  6910.6  507.67  6954.5  507.84
#Mann=8,-1,0
  2754.5    0.05       0  4435.2     0.1       0  4490.5    0.03       0
  4503.9     0.1       0  4505.8    0.05       0  6565.9   0.075       0
  6620.8    0.05       0  6794.5   0.075       0
Bank Sta=4490.5,4503.9
Exp/Cntr=0.3,0.1

Type RM Length L Ch R = 1,19108,45,45,45
BEGIN DESCRIPTION:
Mapping XS ce983125
END DESCRIPTION:
XS GIS Cut Line= 6
      2632441.93      6983829.91      2631948.88      6985378.50
      2631567.35      6986663.15      2631597.07      6986943.34
      2631682.79      6987299.25      2631483.91      6988397.65
#Sta/Elev= 30
  3370.6  518.97  4242.8  498.37  4284.8  492.73  4363.0  496.79  4715.1  487.04
  4958.8  489.88  5018.8  487.18  5024.0  490.51  5050.5  487.56  5162.0  487.28
  5167.2  490.30  5233.7  487.18  5238.9  490.14  5293.2  486.88  5295.2  486.38
  5306.9  486.88  5481.8  490.92  5548.2  488.42  5553.4  491.45  5653.0  488.22
  5658.3  491.44  5686.2  488.76  5691.5  491.60  5724.7  488.08  5757.9  488.27
  5763.1  491.59  5862.7  489.33  5867.9  492.66  6404.1  492.96  8100.0  511.55
#Mann=3,-1,0
  3370.6    0.05       0  5293.2    0.03       0  5306.9    0.05       0
Bank Sta=5293.2,5306.9
Exp/Cntr=0.3,0.1

Type RM Length L Ch R = 1,19063,64,64,64
BEGIN DESCRIPTION:
Mapping XS 6f3678a9
END DESCRIPTION:
XS GIS Cut Line= 6
      2632407.20      6983774.37      2632073.88      6984816.00
      2631524.81      6986742.96      2631574.72      6986942.18
      2631600.06      6987332.01      2631435.00      6988434.04
#Sta/Elev= 30
  3340.3  521.79  4180.1  498.63  4264.9  498.60  4293.3  492.83  4319.0  492.60
  4320.9  492.10  4332.7  492.60  4384.7  497.48  4437.7  497.88  4596.6  495.00
  5016.9  497.11  5192.9  494.72  5226.2  496.82  5231.4  494.50  5259.5  496.54
  5264.7  494.06  5297.9  496.65  5331.2  496.45  5336.4  493.62  5366.9  496.16
  5369.8  493.48  5404.3  496.32  5551.0  496.81  5556.2  494.26  5655.9  496.73
  5661.1  494.02  5694.3  496.79  6702.4  496.33  7609.3  504.23  8158.4  512.45
#Mann=3,-1,0
  3340.3    0.05       0  4319.0    0.03       0  4332.7    0.05       0
Bank Sta=4319,4332.7
Exp/Cntr=0.3,0.1

Type RM Length L Ch R = 1,18999,311,311,311
BEGIN DESCRIPTION:
Mapping XS 167eb25a
END DESCRIPTION:
XS GIS Cut Line= 6
      2632358.59      6983788.26      2631942.27      6985147.42
      2631880.28      6985264.74      2631854.64      6985434.91
      2631323.88      6987191.00      2631351.63      6988377.20
#Sta/Elev= 30
  3395.7  521.81  4162.0  500.49  4318.9  498.67  4360.8  492.90  4496.7  496.37
  4538.6  492.99  4695.4  487.64  4785.9  487.40  4791.1  485.34  4816.5  487.21
  4823.4  484.60  4889.4  482.97  4944.2  484.65  4949.1  480.26  4970.6  478.76
  4982.9  480.17  4990.6  477.70  4992.5  477.20  5004.3  477.70  5008.2  480.36
  5033.6  484.17  5108.7  482.37  5134.7  485.68  5139.9  482.74  5238.8  485.05
  5244.0  483.19  5381.0  483.83  6612.4  497.05  6997.2  498.34  8143.7  513.04
#Mann=5,-1,0
  3395.7    0.05       0  4970.6    0.12       0  4990.6    0.07       0
  5004.3    0.12       0  5033.6    0.05       0
Bank Sta=4990.6,5004.3
Exp/Cntr=0.3,0.1

Type RM Length L Ch R = 1,18688,408,408,408
BEGIN DESCRIPTION:
High Point Creek 25.0
END DESCRIPTION:
XS GIS Cut Line= 3
      2631826.00      6984160.99      2631599.80      6985228.50
      2630249.80      6986878.49
#Sta/Elev= 30
  3904.2  514.55  4037.1  509.03  4067.8  504.55  4078.1  506.75  4122.6  506.09
  4200.6  501.97  4460.1  495.37  4732.2  484.56  4783.3  485.25  4792.5  483.80
  4797.6  485.02  4814.0  481.80  4897.2  480.47  4926.4  480.34  4936.4  482.02
  4941.6  480.21  4957.1  481.20  5000.3  478.37  5002.3  477.87  5014.1  478.37
  5050.3  478.94  5056.7  480.87  5077.5  479.81  5192.9  482.26  5483.1  483.99
  5668.3  487.69  5831.3  488.01  5994.2  491.10  6484.5  495.76  7127.3  499.93
#Mann=5,-1,0
  3904.2    0.05       0  4897.2    0.12       0  5000.3    0.07       0
  5014.1    0.12       0  5192.9    0.05       0
Bank Sta=5000.3,5014.1
Exp/Cntr=0.3,0.1

Type RM Length L Ch R = 1,18280,454,454,454
BEGIN DESCRIPTION:
High Point Creek 24.0
END DESCRIPTION:
XS GIS Cut Line= 3
      2631426.01      6984510.96      2631226.00      6985111.00
      2630326.00      6986761.01
#Sta/Elev= 30
  4371.8  499.92  4435.1  495.85  4688.1  486.18  4877.8  481.29  4962.1  481.28
  4983.2  480.12  4986.9  477.27  4988.8  476.77  4998.7  476.77  5000.7  477.27
  5001.7  478.40  5007.1  478.40  5012.4  480.35  5018.1  481.35  5061.7  480.23
  5094.0  481.37  5121.5  481.05  5175.2  481.85  5191.7  481.52  5237.0  481.63
  5357.4  483.37  5541.1  484.27  5585.2  484.99  5638.9  484.91  5710.5  485.93
  5733.3  485.59  5756.1  486.69  5867.6  488.94  6390.7  495.28  6883.8  499.18
#Mann=5,-1,0
  4371.8    0.05       0  4986.9    0.03       0  5000.7    0.05       0
  5191.7    0.12       0  5237.0    0.05       0
Bank Sta=4986.9,5000.7
Exp/Cntr=0.3,0.1

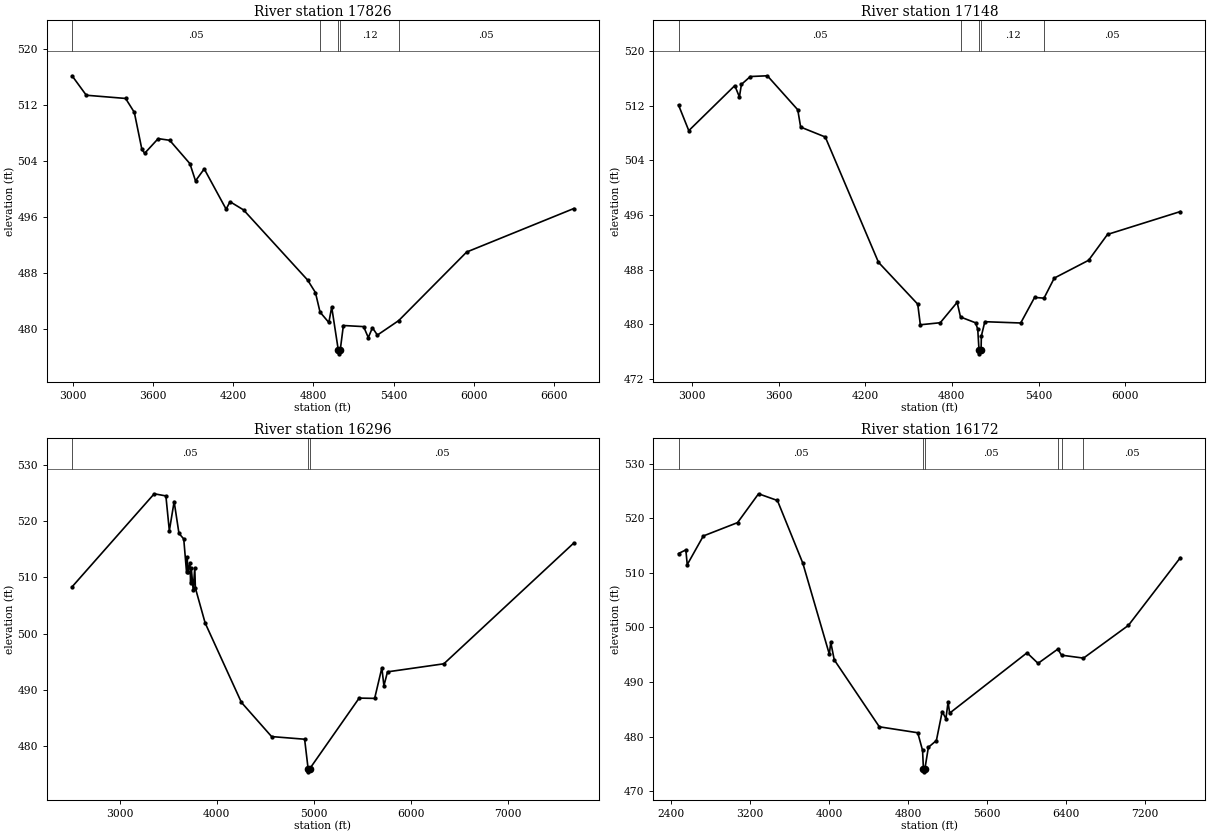
Type RM Length L Ch R = 1,17826,678,678,678
BEGIN DESCRIPTION:
High Point Creek 23.0
END DESCRIPTION:
XS GIS Cut Line= 3
      2632032.19      6983218.81      2630876.00      6984861.00
      2629975.98      6986361.03
#Sta/Elev= 30
  2992.1  516.13  3098.6  513.35  3393.0  512.89  3458.3  510.90  3514.9  505.61
  3535.8  505.05  3636.9  507.15  3723.1  506.91  3874.6  503.57  3916.5  501.11
  3981.8  502.82  4145.6  497.07  4175.2  498.13  4276.2  496.96  4755.9  486.94
  4814.5  485.15  4849.2  482.35  4914.9  480.87  4936.4  483.07  4986.1  476.89
  4988.1  476.39  5000.0  476.89  5023.8  480.44  5175.4  480.28  5210.4  478.71
  5241.5  480.12  5278.4  479.07  5438.0  481.14  5947.0  490.94  6749.8  497.16
#Mann=5,-1,0
  2992.1    0.05       0  4849.2    0.12       0  4986.1    0.07       0
  5000.0    0.12       0  5438.0    0.05       0
Bank Sta=4986.1,5000
Exp/Cntr=0.3,0.1

Type RM Length L Ch R = 1,17148,852,852,852
BEGIN DESCRIPTION:
High Point Creek 22.0
END DESCRIPTION:
XS GIS Cut Line= 3
      2630976.64      6982934.10      2630273.80      6984904.92
      2629750.66      6986183.97
#Sta/Elev= 30
  2907.6  512.10  2978.6  508.35  3297.1  514.95  3329.0  513.29  3343.1  515.13
  3404.7  516.28  3522.6  516.39  3733.0  511.41  3753.2  508.87  3923.5  507.42
  4291.8  489.06  4563.8  482.92  4581.8  479.90  4719.8  480.20  4836.6  483.19
  4859.9  481.04  4964.0  480.19  4979.2  479.26  4988.2  476.14  4990.2  475.64
  5002.3  476.14  5004.3  478.24  5028.2  480.35  5276.8  480.16  5372.9  483.91
  5438.0  483.80  5509.1  486.74  5746.8  489.35  5877.7  493.14  6381.9  496.49
#Mann=5,-1,0
  2907.6    0.05       0  4859.9    0.12       0  4988.2    0.07       0
  5002.3    0.12       0  5438.0    0.05       0
Bank Sta=4988.2,5002.3
Exp/Cntr=0.3,0.1

Type RM Length L Ch R = 1,16296,124,124,124
BEGIN DESCRIPTION:
Mapping XS f892da8e
END DESCRIPTION:
XS GIS Cut Line= 6
      2631143.33      6982642.38      2630240.55      6983503.50
      2629908.71      6983965.91      2629559.99      6984517.39
      2628914.16      6985600.72      2628573.95      6986996.26
#Sta/Elev= 30
  2510.1  508.32  3356.0  524.84  3476.1  524.46  3511.7  518.28  3561.1  523.46
  3610.8  517.81  3660.1  516.82  3688.4  511.02  3695.4  513.60  3702.6  511.03
  3723.7  512.58  3730.9  508.97  3737.8  511.58  3757.4  507.74  3773.6  511.70
  3779.8  508.11  3880.4  501.90  4253.7  487.81  4564.7  481.74  4904.7  481.27
  4941.0  475.98  4943.0  475.48  4955.3  475.98  5466.2  488.57  5625.8  488.52
  5699.8  493.93  5721.2  490.77  5758.2  493.23  6338.5  494.66  7677.0  516.11
#Mann=3,-1,0
  2510.1    0.05       0  4941.0    0.05       0  4955.3    0.05       0
Bank Sta=4941,4955.3
Exp/Cntr=0.3,0.1

Type RM Length L Ch R = 1,16172,1469,1469,1469
BEGIN DESCRIPTION:
Mapping XS 35447747
END DESCRIPTION:
XS GIS Cut Line= 6
      2631094.70      6982545.17      2630184.99      6983413.22
      2629702.54      6984033.19      2629462.16      6984447.18
      2628462.77      6986211.83      2628344.71      6986725.75
#Sta/Elev= 30
  2478.3  513.54  2552.2  514.20  2566.4  511.50  2729.0  516.75  3075.6  519.20
  3287.9  524.48  3478.8  523.25  3735.7  511.77  4004.0  495.10  4018.5  497.27
  4053.8  494.06  4509.8  481.80  4898.6  480.71  4947.5  477.46  4956.1  474.05
  4958.1  473.55  4970.4  474.05  5006.2  478.05  5087.1  479.28  5146.2  484.60
  5183.8  483.27  5205.4  486.35  5221.3  484.30  6004.2  495.35  6115.9  493.42
  6315.8  496.03  6353.7  494.92  6575.5  494.38  7030.1  500.38  7555.3  512.77
#Mann=6,-1,0
  2478.3    0.05       0  4956.1    0.03       0  4970.4    0.05       0
  6315.8   0.075       0  6353.7     0.1       0  6575.5    0.05       0
Bank Sta=4956.1,4970.4
Exp/Cntr=0.3,0.1