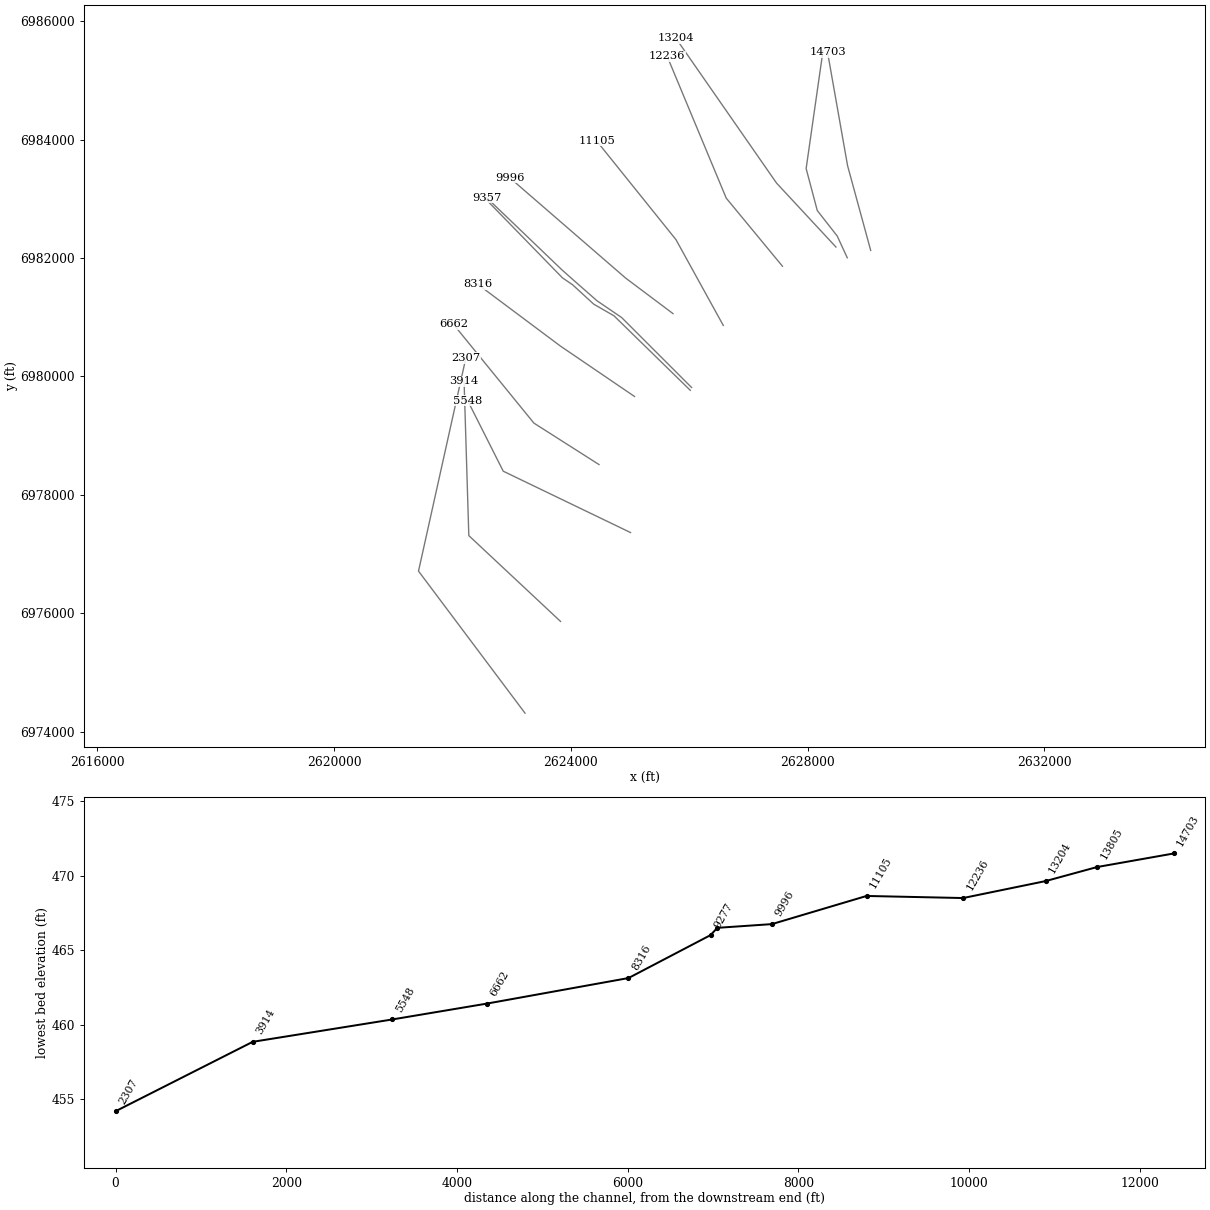
HEC-RAS study High Point Creek.prj: High Point Creek Base Level Engineering

--- High Point Creek.g01 (geometry) --- (continued)

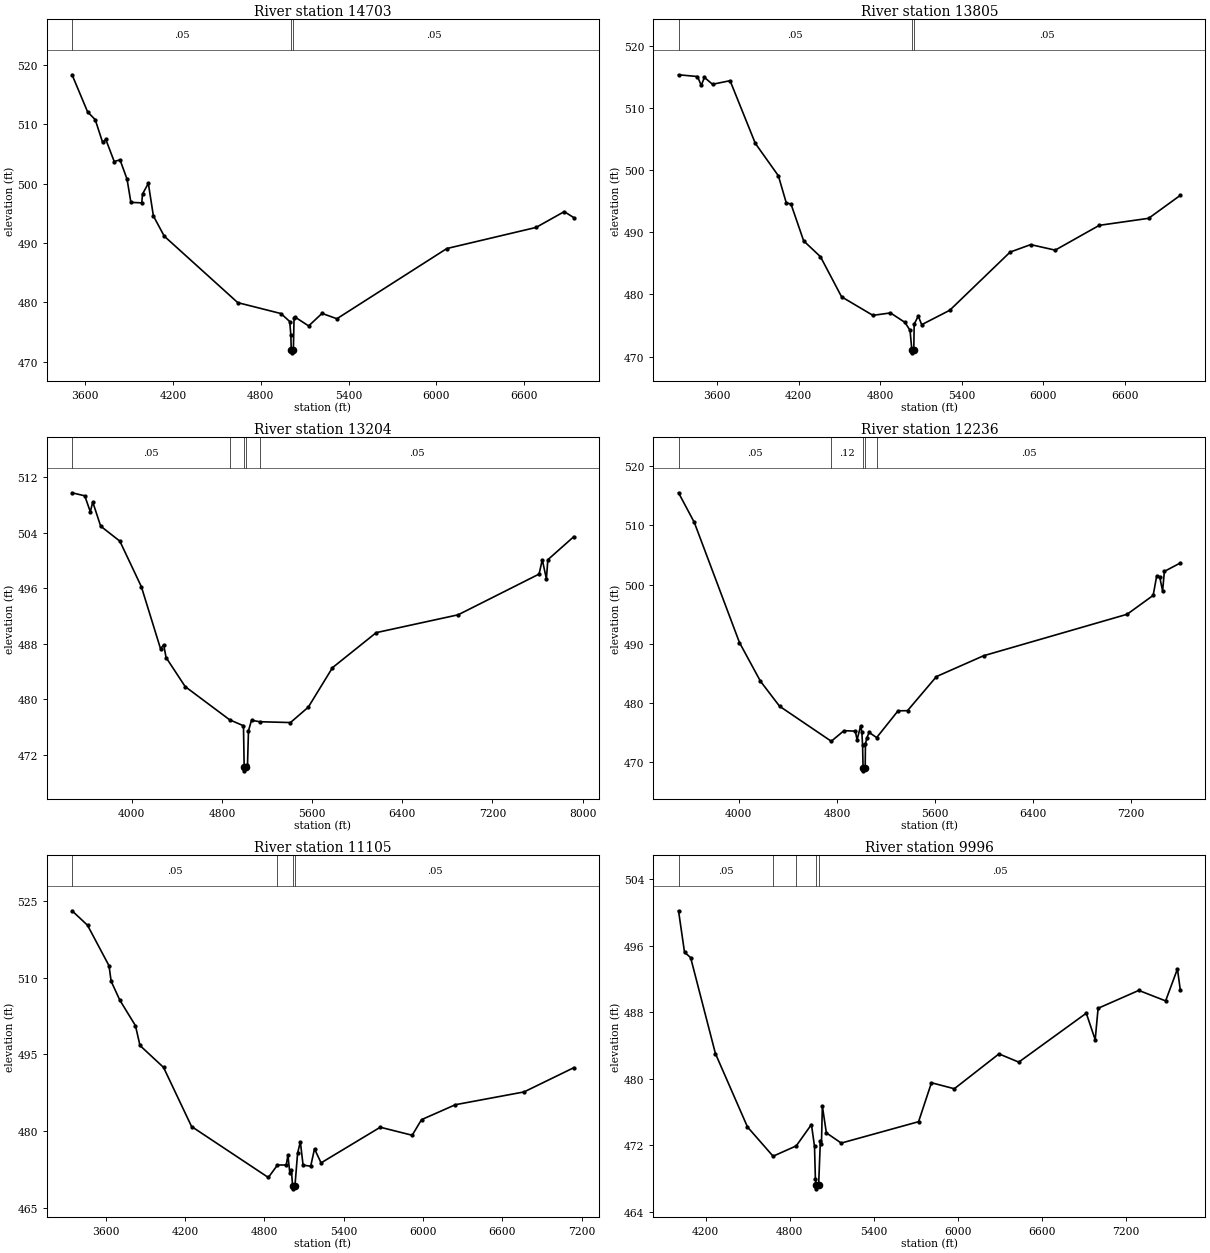
Type RM Length L Ch R = 1,14703,898,898,898
BEGIN DESCRIPTION:
High Point Creek 18.0
END DESCRIPTION:
XS GIS Cut Line= 3
      2629066.93      6982128.53      2628676.00      6983561.00
      2628337.77      6985475.70
#Sta/Elev= 30
  3510.4  518.32  3616.6  512.07  3668.5  510.77  3719.0  506.95  3741.0  507.43
  3798.4  503.72  3838.1  504.00  3886.1  500.75  3912.4  496.84  3986.7  496.76
  3991.8  498.24  4031.6  500.04  4066.1  494.56  4140.4  491.15  4642.8  479.96
  4938.3  478.12  4997.8  476.78  5005.4  474.54  5008.3  472.01  5010.3  471.51
  5022.8  472.01  5027.4  477.38  5035.9  477.50  5127.3  476.04  5218.7  478.15
  5320.2  477.25  6071.7  489.07  6681.0  492.62  6873.9  495.28  6939.6  494.27
#Mann=3,-1,0
  3510.4    0.05       0  5008.3    0.04       0  5022.8    0.05       0
Bank Sta=5008.3,5022.8
Exp/Cntr=0.3,0.1

Type RM Length L Ch R = 1,13805,601,601,601
BEGIN DESCRIPTION:
High Point Creek 17.0
END DESCRIPTION:
XS GIS Cut Line= 5
      2628671.08      6982003.54      2628501.72      6982370.84
      2628164.16      6982802.11      2627976.00      6983511.00
      2628261.20      6985502.21
#Sta/Elev= 30
  3313.9  515.33  3453.1  515.05  3481.5  513.62  3504.5  514.91  3564.4  513.80
  3693.6  514.38  3879.5  504.30  4049.6  499.08  4107.4  494.74  4142.7  494.52
  4235.8  488.61  4359.7  486.06  4515.3  479.61  4746.0  476.63  4875.3  477.02
  4982.0  475.50  5019.7  474.22  5032.6  471.10  5034.6  470.60  5047.2  471.10
  5050.0  475.21  5080.3  476.52  5105.4  475.13  5312.2  477.45  5757.1  486.81
  5908.7  488.01  6089.1  487.12  6413.8  491.11  6777.4  492.24  7011.0  495.94
#Mann=3,-1,0
  3313.9    0.05       0  5032.6    0.03       0  5047.2    0.05       0
Bank Sta=5032.6,5047.2
Exp/Cntr=0.3,0.1

Type RM Length L Ch R = 1,13204,968,968,968
BEGIN DESCRIPTION:
High Point Creek 16.0
END DESCRIPTION:
XS GIS Cut Line= 3
      2628479.65      6982185.62      2627476.20      6983265.46
      2625775.99      6985711.02
#Sta/Elev= 30
  3470.4  509.74  3583.0  509.30  3632.4  507.00  3653.9  508.41  3724.2  504.93
  3894.3  502.77  4085.3  496.20  4255.4  487.26  4283.2  487.82  4304.7  485.99
  4474.3  481.80  4869.3  477.01  4991.3  476.16  4997.6  470.16  4999.6  469.66
  5014.7  470.16  5027.0  470.47  5035.8  475.44  5062.8  476.95  5134.8  476.74
  5408.5  476.62  5566.5  478.84  5781.2  484.53  6169.2  489.58  6896.0  492.15
  7614.4  498.02  7642.9  500.09  7679.4  497.33  7692.1  500.09  7923.0  503.42
#Mann=5,-1,0
  3470.4    0.05       0  4869.3    0.12       0  4997.6    0.07       0
  5014.7    0.12       0  5134.8    0.05       0
Bank Sta=4997.6,5014.7
Exp/Cntr=0.3,0.1

Type RM Length L Ch R = 1,12236,1131,1131,1131
BEGIN DESCRIPTION:
High Point Creek 14.0
END DESCRIPTION:
XS GIS Cut Line= 3
      2627575.98      6981861.02      2626626.00      6983011.00
      2625626.01      6985410.99
#Sta/Elev= 30
  3508.6  515.53  3636.9  510.53  4005.6  490.20  4176.2  483.68  4332.6  479.44
  4754.1  473.52  4857.5  475.31  4950.0  475.23  4964.4  473.76  4993.0  476.09
  5002.9  475.16  5009.4  472.84  5013.3  469.02  5015.3  468.52  5030.5  469.02
  5032.7  473.06  5044.1  474.08  5062.5  475.02  5124.0  474.14  5298.7  478.67
  5375.6  478.69  5611.8  484.46  5996.3  487.98  7166.3  494.99  7378.7  498.18
  7407.9  501.51  7431.8  501.33  7455.6  498.92  7470.2  502.24  7600.2  503.66
#Mann=5,-1,0
  3508.6    0.05       0  4754.1    0.12       0  5013.3    0.07       0
  5030.5    0.12       0  5124.0    0.05       0
Bank Sta=5013.3,5030.5
Exp/Cntr=0.3,0.1

Type RM Length L Ch R = 1,11105,1109,1109,1109
BEGIN DESCRIPTION:
High Point Creek 12.0
END DESCRIPTION:
XS GIS Cut Line= 3
      2626575.98      6980861.04      2625776.00      6982311.00
      2624434.52      6983979.37
#Sta/Elev= 30
  3344.2  523.09  3461.0  520.26  3623.8  512.33  3639.8  509.30  3705.2  505.61
  3823.8  500.60  3858.1  496.72  4036.4  492.43  4248.4  480.86  4829.4  470.88
  4898.3  473.32  4964.7  473.33  4977.4  475.24  4992.2  471.67  5003.4  472.39
  5013.1  469.16  5015.1  468.66  5030.4  469.16  5050.6  475.63  5071.4  477.87
  5092.2  473.30  5149.8  473.09  5178.6  476.49  5228.2  473.74  5676.2  480.72
  5917.7  479.15  5988.2  482.20  6244.9  485.13  6764.1  487.63  7141.0  492.38
#Mann=4,-1,0
  3344.2    0.05       0  4898.3    0.12       0  5013.1    0.07       0
  5030.4    0.05       0
Bank Sta=5013.1,5030.4
Exp/Cntr=0.3,0.1

Type RM Length L Ch R = 1,9996,639,639,639
BEGIN DESCRIPTION:
High Point Creek 10.0
END DESCRIPTION:
XS GIS Cut Line= 3
      2625726.03      6981060.98      2624926.00      6981661.00
      2622970.13      6983353.59
#Sta/Elev= 30
  4005.2  500.19  4047.9  495.21  4091.7  494.56  4268.8  483.03  4497.9  474.21
  4681.0  470.69  4846.4  471.93  4955.2  474.50  4977.1  471.87  4983.4  467.93
  4989.2  467.27  4991.2  466.77  5006.7  467.27  5019.0  472.57  5026.6  472.10
  5033.2  476.72  5061.7  473.50  5168.1  472.27  5720.9  474.84  5813.0  479.52
  5976.4  478.80  6295.6  482.99  6437.1  482.00  6919.6  487.88  6983.3  484.69
  7004.1  488.47  7294.8  490.62  7486.7  489.36  7571.2  493.20  7591.8  490.64
#Mann=5,-1,0
  4005.2    0.05       0  4681.0    0.12       0  4846.4    0.05       0
  4989.2    0.04       0  5006.7    0.05       0
Bank Sta=4989.2,5006.7
Exp/Cntr=0.3,0.1

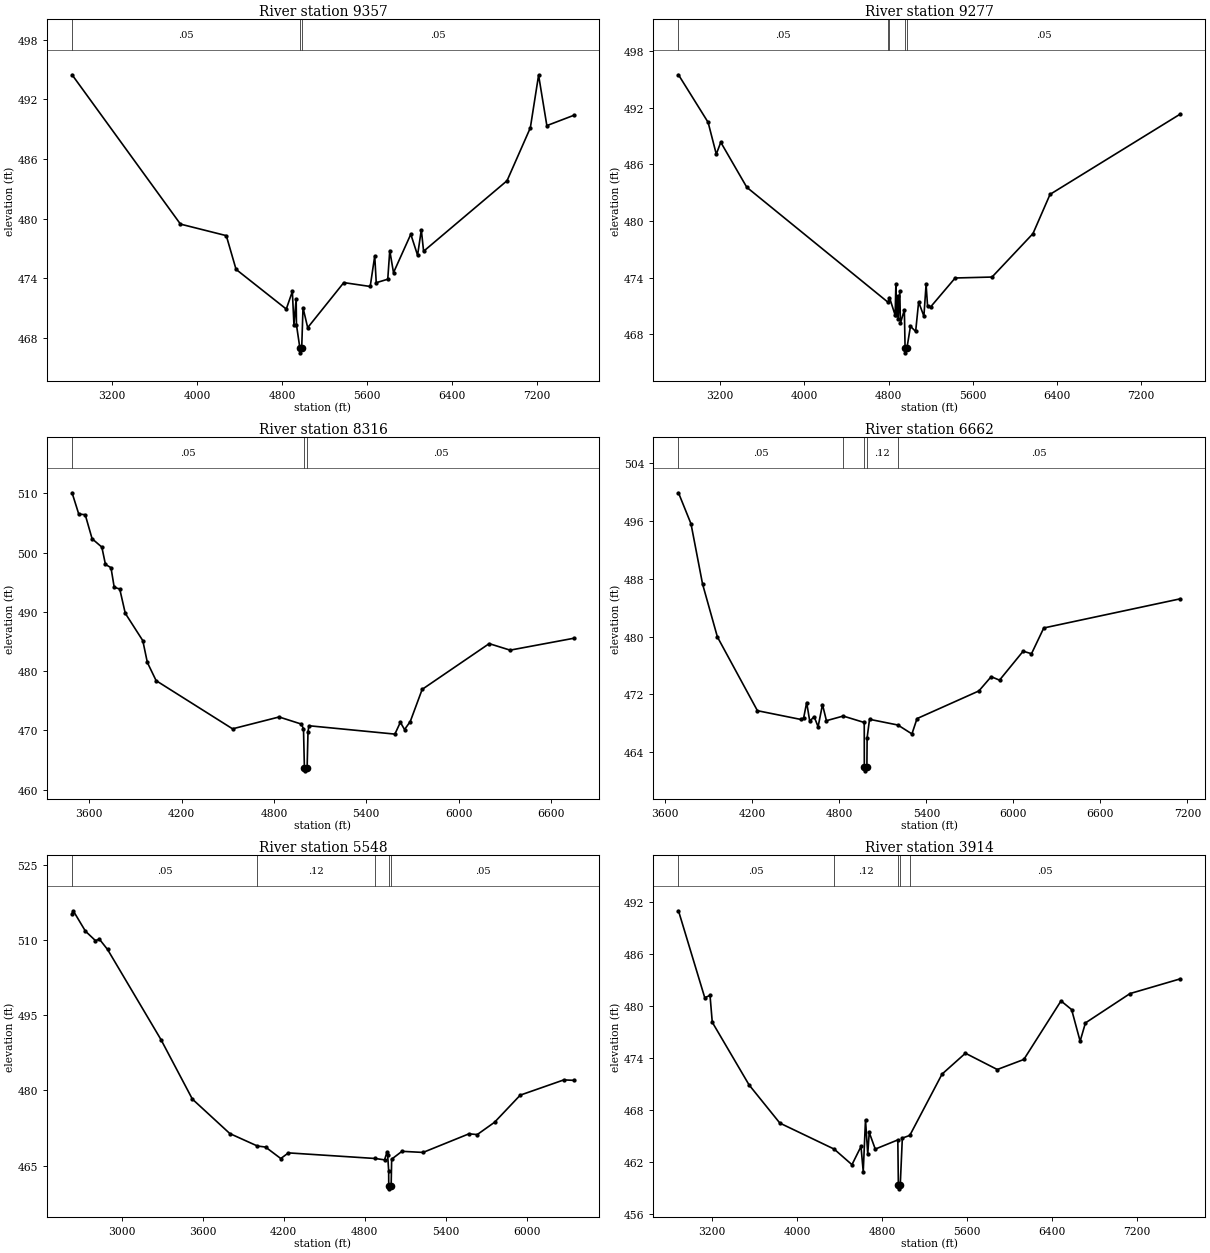
Type RM Length L Ch R = 1,9357,80,80,80
BEGIN DESCRIPTION:
Mapping XS bb286b0b
END DESCRIPTION:
XS GIS Cut Line= 6
      2626040.00      6979812.84      2624859.47      6980993.37
      2624442.41      6981277.58      2624034.07      6981635.92
      2623847.61      6981801.89      2622580.93      6983015.84
#Sta/Elev= 30
  2825.4  494.47  3845.2  479.46  4276.5  478.30  4368.4  474.91  4841.0  470.92
  4898.1  472.69  4913.1  469.35  4934.1  471.95  4936.7  469.34  4968.7  467.02
  4970.7  466.52  4986.2  467.02  4998.4  471.06  5042.4  469.05  5382.2  473.58
  5630.7  473.19  5673.3  476.26  5687.5  473.57  5795.8  473.92  5814.7  476.80
  5849.9  474.58  6012.6  478.44  6076.4  476.33  6111.6  478.88  6133.1  476.73
  6918.2  483.82  7137.4  489.14  7215.1  494.43  7292.8  489.36  7547.5  490.40
#Mann=3,-1,0
  2825.4    0.05       0  4968.7    0.03       0  4986.2    0.05       0
Bank Sta=4968.7,4986.2
Exp/Cntr=0.3,0.1

Type RM Length L Ch R = 1,9277,961,961,961
BEGIN DESCRIPTION:
Mapping XS 54423acc
END DESCRIPTION:
XS GIS Cut Line= 6
      2626018.34      6979765.06      2624729.55      6981023.44
      2624386.89      6981220.42      2624030.25      6981547.38
      2623857.68      6981665.43      2622546.08      6983011.63
#Sta/Elev= 30
  2803.5  495.49  3085.2  490.45  3162.9  487.08  3205.4  488.34  3452.8  483.57
  4796.0  471.38  4808.9  471.89  4862.6  470.02  4869.6  473.31  4875.3  470.05
  4885.4  472.02  4891.1  469.62  4906.9  472.57  4912.7  469.16  4950.1  470.58
  4957.1  466.53  4959.1  466.03  4974.6  466.53  5008.1  468.84  5057.5  468.30
  5085.8  471.42  5135.8  469.91  5156.7  473.29  5170.9  470.96  5199.3  470.89
  5433.0  473.96  5783.3  474.06  6172.3  478.66  6334.8  482.82  7572.8  491.33
#Mann=5,-1,0
  2803.5    0.05       0  4796.0    0.12       0  4808.9    0.05       0
  4957.1    0.03       0  4974.6    0.05       0
Bank Sta=4957.1,4974.6
Exp/Cntr=0.3,0.1

Type RM Length L Ch R = 1,8316,1654,1654,1654
BEGIN DESCRIPTION:
High Point Creek 7.0
END DESCRIPTION:
XS GIS Cut Line= 3
      2625076.03      6979660.98      2623826.00      6980511.00
      2622423.69      6981558.48
#Sta/Elev= 30
  3487.9  510.08  3531.3  506.49  3573.3  506.38  3618.1  502.32  3681.4  500.91
  3704.9  497.99  3740.8  497.44  3761.8  494.13  3797.7  493.84  3833.7  489.74
  3947.5  485.13  3977.3  481.44  4034.3  478.37  4531.1  470.24  4833.5  472.24
  4977.2  471.05  4992.1  470.27  4998.1  463.65  5000.1  463.15  5015.7  463.65
  5021.5  469.78  5027.7  470.76  5586.2  469.35  5621.8  471.35  5648.9  470.12
  5686.1  471.47  5763.5  476.90  6199.2  484.62  6335.1  483.52  6749.9  485.53
#Mann=3,-1,0
  3487.9    0.05       0  4998.1    0.03       0  5015.7    0.05       0
Bank Sta=4998.1,5015.7
Exp/Cntr=0.3,0.1

Type RM Length L Ch R = 1,6662,1114,1114,1114
BEGIN DESCRIPTION:
High Point Creek 6.0
END DESCRIPTION:
XS GIS Cut Line= 3
      2624476.02      6978510.99      2623376.00      6979211.00
      2622013.99      6980883.12
#Sta/Elev= 30
  3690.8  499.86  3777.2  495.57  3856.8  487.26  3959.2  479.94  4235.2  469.75
  4532.4  468.55  4553.6  468.71  4574.7  470.88  4595.9  468.31  4626.4  468.92
  4653.5  467.53  4683.9  470.59  4711.0  468.37  4826.6  469.01  4971.8  468.12
  4972.3  461.94  4974.3  461.44  4990.0  461.94  4991.7  466.02  5008.3  468.56
  5203.9  467.77  5300.6  466.54  5335.8  468.66  5762.3  472.48  5847.1  474.45
  5904.5  473.97  6067.5  477.97  6125.0  477.62  6209.7  481.18  7151.3  485.21
#Mann=5,-1,0
  3690.8    0.05       0  4826.6    0.12       0  4972.3    0.07       0
  4990.0    0.12       0  5203.9    0.05       0
Bank Sta=4972.3,4990
Exp/Cntr=0.3,0.1

Type RM Length L Ch R = 1,5548,1634,1634,1634
BEGIN DESCRIPTION:
Mapping XS 2b6d515a
END DESCRIPTION:
XS GIS Cut Line= 3
      2625008.82      6977362.27      2622857.74      6978398.75
      2622258.86      6979586.10
#Sta/Elev= 30
  2632.4  515.25  2641.0  515.81  2731.5  511.74  2804.9  509.88  2835.3  510.13
  2895.4  508.09  3291.0  490.12  3523.6  478.26  3801.1  471.39  4005.2  468.91
  4065.6  468.70  4178.5  466.41  4235.0  467.54  4877.8  466.42  4947.3  466.15
  4964.4  467.62  4970.0  467.14  4977.7  463.97  4978.1  460.87  4980.1  460.37
  4996.0  460.87  4999.9  466.29  5076.3  467.85  5232.4  467.63  5572.6  471.34
  5633.9  471.19  5761.9  473.64  5952.3  479.05  6275.1  482.09  6350.0  482.00
#Mann=5,-1,0
  2632.4    0.05       0  4005.2    0.12       0  4877.8    0.05       0
  4978.1    0.03       0  4996.0    0.05       0
Bank Sta=4978.1,4996
Exp/Cntr=0.3,0.1

Type RM Length L Ch R = 1,3914,1607,1607,1607
BEGIN DESCRIPTION:
High Point Creek 4.0
END DESCRIPTION:
XS GIS Cut Line= 3
      2623826.00      6975861.00      2622276.00      6977311.00
      2622196.28      6979914.39
#Sta/Elev= 30
  2882.2  490.98  3129.6  480.95  3179.4  481.20  3200.5  478.11  3547.3  470.87
  3837.4  466.46  4348.5  463.46  4516.4  461.66  4601.4  463.76  4622.5  460.85
  4643.9  466.84  4665.0  462.89  4679.1  465.38  4735.8  463.46  4948.3  464.52
  4953.4  459.37  4955.4  458.87  4971.4  459.37  4990.8  464.73  5061.1  465.04
  5364.9  472.12  5585.0  474.53  5885.1  472.65  6135.2  473.81  6485.4  480.57
  6585.4  479.57  6665.5  475.92  6715.5  478.03  7135.7  481.42  7609.3  483.12
#Mann=5,-1,0
  2882.2    0.05       0  4348.5    0.12       0  4953.4    0.07       0
  4971.4    0.12       0  5061.1    0.05       0
Bank Sta=4953.4,4971.4
Exp/Cntr=0.3,0.1

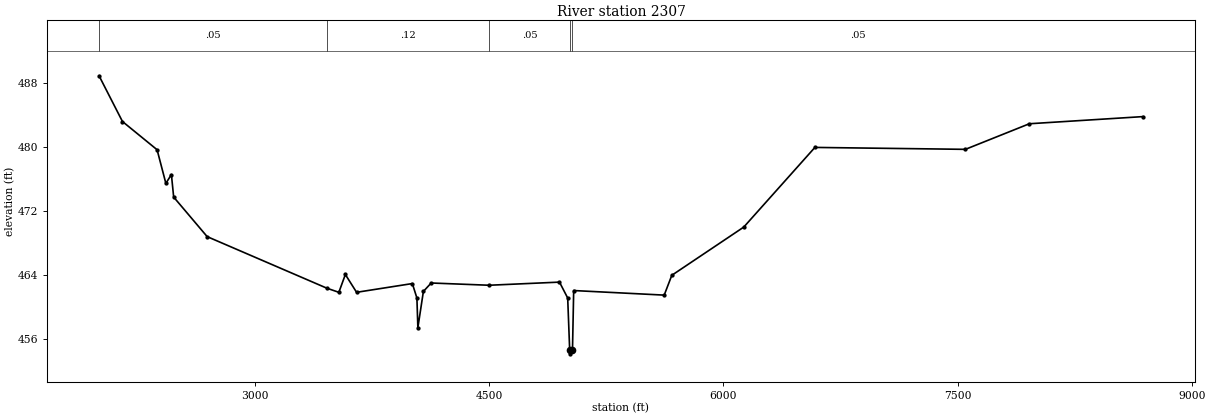
Type RM Length L Ch R = 1,2307,0,0,0
BEGIN DESCRIPTION:
High Point Creek 2.0
END DESCRIPTION:
XS GIS Cut Line= 3
      2623226.01      6974310.99      2621426.00      6976711.00
      2622225.99      6980310.97
#Sta/Elev= 30
  1999.6  488.87  2149.6  483.17  2371.5  479.65  2427.7  475.46  2463.2  476.56
  2477.7  473.75  2692.3  468.82  3459.6  462.39  3536.1  461.88  3577.7  464.10
  3649.6  461.88  4006.9  462.97  4036.1  461.17  4042.3  457.47  4077.7  461.99
  4127.7  463.04  4499.1  462.76  4949.6  463.15  5002.2  461.17  5014.9  454.71
  5016.9  454.21  5033.0  454.71  5040.6  462.10  5620.6  461.53  5669.3  464.00
  6130.3  470.01  6586.1  479.94  7550.3  479.70  7960.1  482.89  8687.4  483.78
#Mann=5,-1,0
  1999.6    0.05       0  3459.6    0.12       0  4499.1    0.05       0
  5014.9    0.03       0  5033.0    0.05       0
Bank Sta=5014.9,5033
Exp/Cntr=0.3,0.1

Chan Stop Cuts=-1