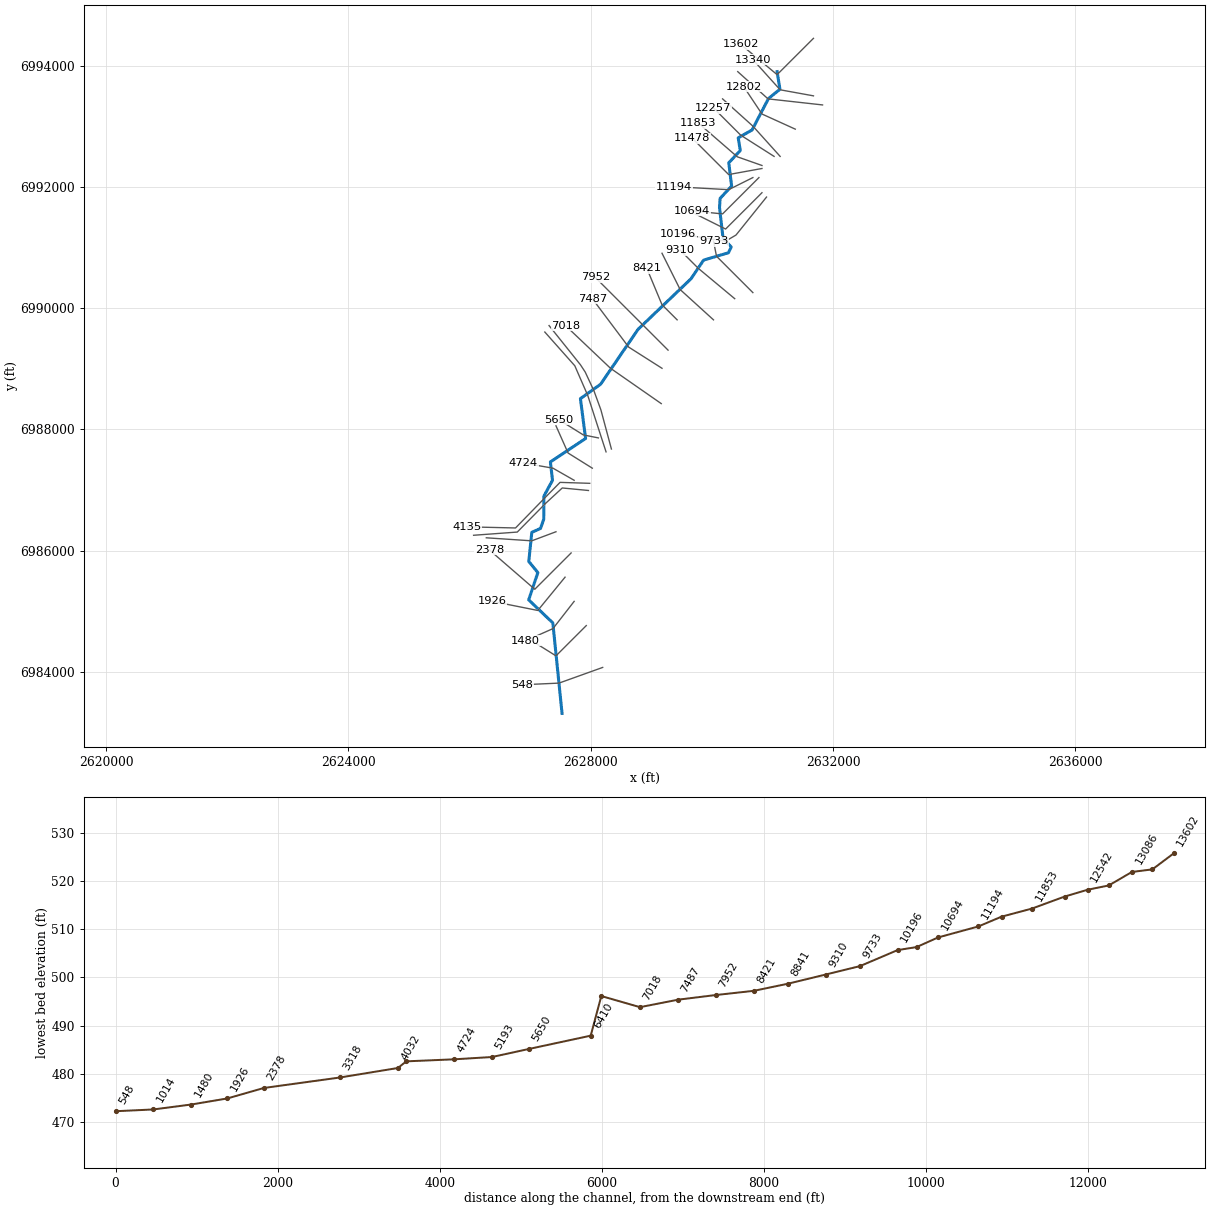
--- High Point Creek Trib 1.prj (project) ---

Proj Title=High Point Creek Trib 1 Base Level Engineering
Current Plan=p01
Default Exp/Contr=0.3,0.1
English Units
Geom File=g01
Flow File=f01
Plan File=p01
BEGIN DESCRIPTION:
High Point Creek Trib 1
END DESCRIPTION:

--- High Point Creek Trib 1.p01 (plan) ---

Plan Title=Multiple Run
Short Identifier=Multiple
Geom File=g01
Flow File=f01
Subcritical Flow
K Sum by GR= 0
Std Step Tol= 0.01
Critical Tol= 0.01
Num of Std Step Trials= 20
Max Error Tol= 0.3
Flow Tol Ratio= 0.001
Split Flow NTrial= 30
Split Flow Tol= 0.02
Split Flow Ratio= 0.02
Log Output Level= 0
Friction Slope Method= 1
Unsteady Friction Slope Method= 2
Unsteady Bridges Friction Slope Method= 1
Parabolic Critical Depth
Global Vel Dist=  1 , 1 , 1
Global Log Level= 0
CheckData=True
Encroach Param= -1, 0, 0, 0
BEGIN DESCRIPTION:
Multiple Run
END DESCRIPTION:

--- High Point Creek Trib 1.f01 (steady flow) ---

Flow Title=Multiple
Number of Profiles=7
Profile Names=10-year,25-year,50-year,1pct_min,100-year,1pct_plu,500-year
River Rch & RM= High Point Creek,Reach-1,13602
     294     375     437     254     506    1010     675
River Rch & RM= High Point Creek,Reach-1,9733
     382     497     587     344     687    1371     941
River Rch & RM= High Point Creek,Reach-1,7952
     714     961    1161     695    1386    2766    1977
Boundary for River Rch & Prof#=High Point Creek,Reach-1,1
Up Type=0
Dn Type=3
Dn Slope=0.005
Boundary for River Rch & Prof#=High Point Creek,Reach-1,2
Up Type=0
Dn Type=3
Dn Slope=0.005
Boundary for River Rch & Prof#=High Point Creek,Reach-1,3
Up Type=0
Dn Type=3
Dn Slope=0.005
Boundary for River Rch & Prof#=High Point Creek,Reach-1,4
Up Type=0
Dn Type=3
Dn Slope=0.005
Boundary for River Rch & Prof#=High Point Creek,Reach-1,5
Up Type=0
Dn Type=3
Dn Slope=0.005
Boundary for River Rch & Prof#=High Point Creek,Reach-1,6
Up Type=0
Dn Type=3
Dn Slope=0.005
Boundary for River Rch & Prof#=High Point Creek,Reach-1,7
Up Type=0
Dn Type=3
Dn Slope=0.005

--- High Point Creek Trib 1.g01 (geometry) ---

Geom Title=Existing Conditions

River Reach=High Point Creek,Reach-1
Reach XY= 30
      2631076.00      6993911.00      2631122.94      6993619.30
      2630933.86      6993467.17      2630662.77      6992947.28
      2630433.80      6992817.21      2630467.96      6992607.68
      2630277.98      6992405.33      2630325.07      6992021.48
      2630135.30      6991817.67      2630125.23      6991666.05
      2630183.80      6991157.58      2630318.24      6991014.38
      2630272.69      6990919.11      2629862.33      6990797.77
      2629656.21      6990490.91      2628781.62      6989655.38
      2628162.37      6988747.79      2627829.36      6988509.75
      2627914.91      6987850.92      2627333.79      6987464.43
      2627368.64      6987160.92      2627227.22      6986900.50
      2627223.74      6986516.93      2627170.89      6986366.11
      2627026.98      6986300.73      2626976.97      6985821.29
      2627126.51      6985635.98      2626975.49      6985185.96
      2627374.02      6984805.33      2627526.00      6983311.00

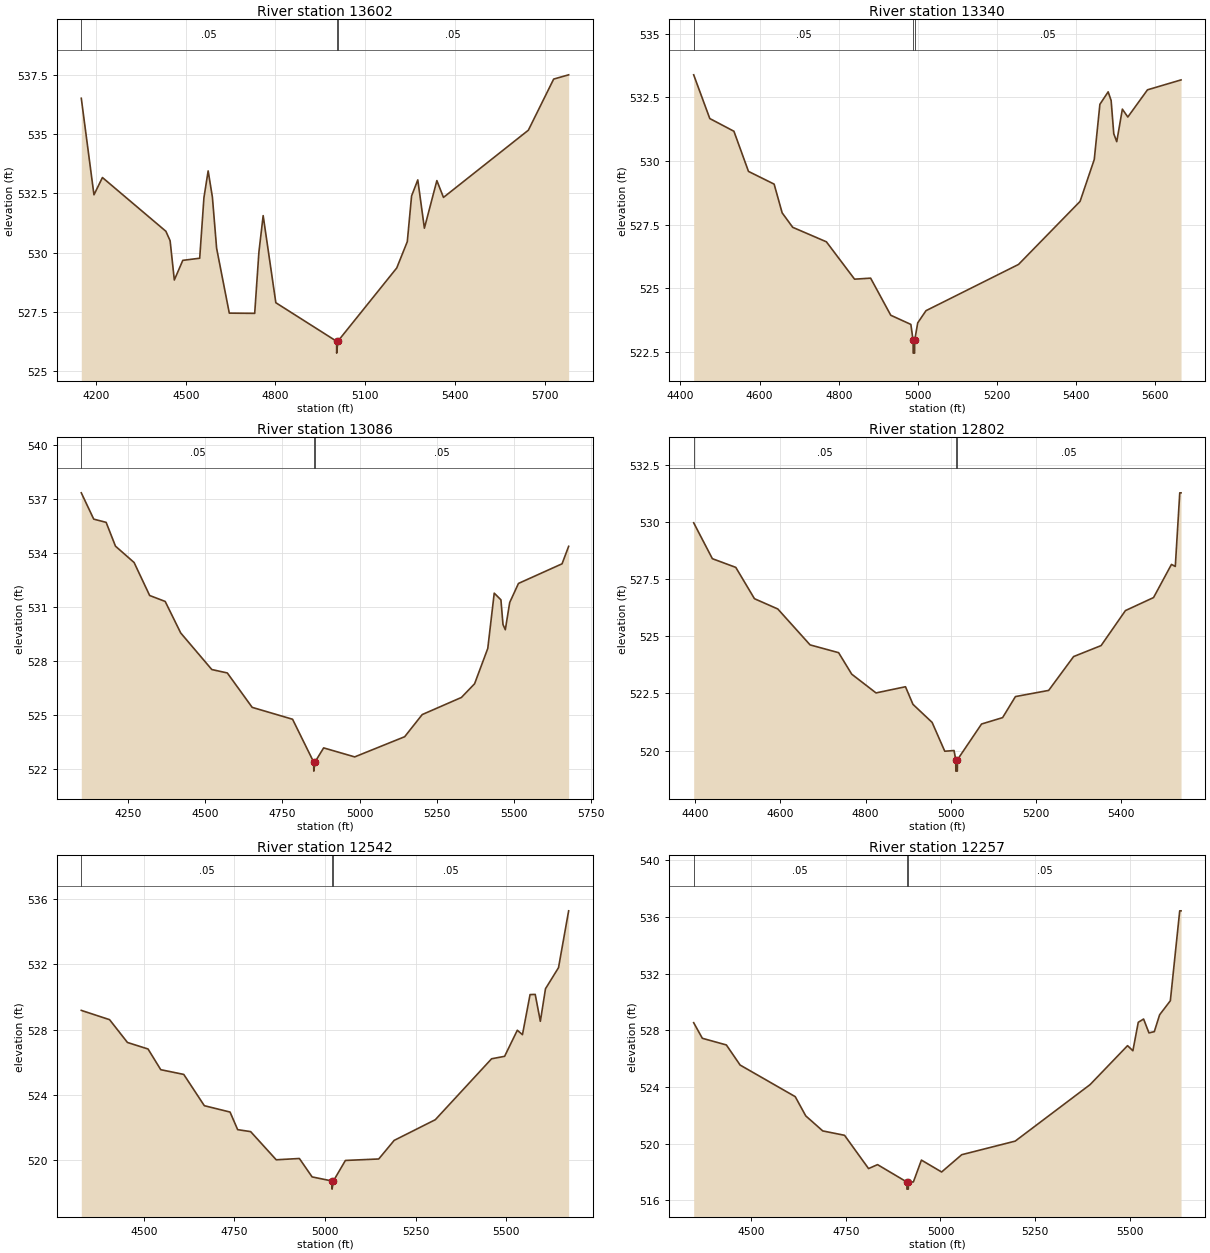
Type RM Length L Ch R = 1,13602,262,262,262
BEGIN DESCRIPTION:
High Point Creek Trib 1 33.0
END DESCRIPTION:
XS GIS Cut Line= 3
      2631675.98      6994460.98      2631076.00      6993861.00
      2630476.01      6994360.99
#Sta/Elev= 30
  4150.7  536.52  4193.1  532.44  4221.4  533.17  4433.5  530.90  4447.7  530.50
  4461.8  528.84  4490.1  529.67  4546.6  529.76  4560.8  532.32  4574.9  533.45
  4589.1  532.34  4603.2  530.18  4645.6  527.44  4730.5  527.43  4744.6  530.02
  4758.8  531.56  4801.2  527.88  5004.4  526.25  5004.6  525.75  5008.4  526.25
  5205.5  529.35  5240.7  530.46  5255.0  532.39  5275.8  533.07  5297.9  531.03
  5339.6  533.04  5361.7  532.33  5645.5  535.17  5730.1  537.33  5780.2  537.51
#Mann=3,-1,0
  4150.7    0.05       0  5004.4    0.04       0  5008.4    0.05       0
Bank Sta=5004.4,5008.4
Exp/Cntr=0.3,0.1

Type RM Length L Ch R = 1,13340,254,254,254
BEGIN DESCRIPTION:
High Point Creek Trib 1 32.0
END DESCRIPTION:
XS GIS Cut Line= 3
      2631676.03      6993510.99      2631126.00      6993611.00
      2630676.02      6994110.98
#Sta/Elev= 30
  4433.4  533.39  4474.1  531.67  4535.1  531.17  4571.9  529.59  4636.7  529.09
  4657.0  527.96  4683.7  527.39  4768.8  526.82  4840.0  525.35  4880.6  525.39
  4931.5  523.93  4982.3  523.57  4987.9  522.94  4988.2  522.44  4991.7  522.44
  4991.9  522.94  4999.6  523.63  5020.5  524.11  5254.4  525.93  5409.9  528.41
  5445.8  530.06  5460.0  532.23  5480.9  532.72  5488.4  532.38  5495.1  531.07
  5502.6  530.76  5516.8  532.04  5530.6  531.73  5580.3  532.80  5665.1  533.19
#Mann=3,-1,0
  4433.4    0.05       0  4987.9    0.05       0  4991.9    0.05       0
Bank Sta=4987.9,4991.9
Exp/Cntr=0.3,0.1

Type RM Length L Ch R = 1,13086,284,284,284
BEGIN DESCRIPTION:
High Point Creek Trib 1 31.0
END DESCRIPTION:
XS GIS Cut Line= 3
      2631826.00      6993361.00      2630926.00      6993461.00
      2630426.02      6993910.98
#Sta/Elev= 30
  4098.6  537.34  4138.9  535.88  4179.1  535.70  4209.3  534.38  4269.7  533.47
  4320.0  531.64  4370.3  531.31  4420.6  529.56  4521.2  527.53  4571.5  527.34
  4652.0  525.43  4782.8  524.77  4851.2  522.39  4851.5  521.89  4855.2  522.39
  4883.4  523.18  4984.0  522.68  5145.8  523.80  5202.6  525.03  5329.6  525.98
  5372.2  526.74  5414.9  528.70  5435.8  531.77  5457.5  531.40  5464.2  530.03
  5471.7  529.74  5485.9  531.25  5514.3  532.31  5655.5  533.40  5676.8  534.37
#Mann=3,-1,0
  4098.6    0.05       0  4851.2    0.05       0  4855.2    0.05       0
Bank Sta=4851.2,4855.2
Exp/Cntr=0.3,0.1

Type RM Length L Ch R = 1,12802,260,260,260
BEGIN DESCRIPTION:
High Point Creek Trib 1 30.0
END DESCRIPTION:
XS GIS Cut Line= 3
      2631376.00      6992961.00      2630826.00      6993211.00
      2630525.99      6993661.01
#Sta/Elev= 30
  4396.1  529.96  4440.0  528.39  4495.0  528.01  4538.9  526.64  4593.8  526.19
  4669.6  524.62  4736.6  524.28  4767.4  523.34  4824.5  522.52  4893.7  522.79
  4911.3  522.02  4956.3  521.23  4986.0  519.97  5007.8  520.00  5011.8  519.60
  5012.0  519.10  5015.5  519.10  5015.8  519.60  5072.4  521.16  5121.9  521.44
  5152.0  522.36  5230.1  522.63  5288.7  524.11  5353.3  524.59  5410.4  526.12
  5476.5  526.69  5518.6  528.14  5527.6  528.05  5538.1  531.27  5541.1  531.27
#Mann=3,-1,0
  4396.1    0.05       0  5011.8    0.03       0  5015.8    0.05       0
Bank Sta=5011.8,5015.8
Exp/Cntr=0.3,0.1

Type RM Length L Ch R = 1,12542,285,285,285
BEGIN DESCRIPTION:
High Point Creek Trib 1 29.0
END DESCRIPTION:
XS GIS Cut Line= 3
      2631126.01      6992510.99      2630676.00      6993011.00
      2630175.99      6993461.01
#Sta/Elev= 30
  4327.3  529.18  4405.4  528.61  4454.8  527.21  4511.6  526.81  4546.7  525.54
  4610.2  525.25  4667.0  523.33  4738.0  522.94  4759.0  521.86  4794.8  521.74
  4865.5  520.01  4929.4  520.09  4964.5  518.96  5019.3  518.71  5019.6  518.21
  5023.3  518.71  5056.4  519.97  5148.4  520.06  5191.0  521.20  5304.6  522.47
  5460.0  526.21  5495.9  526.36  5531.0  527.96  5545.2  527.69  5566.2  530.15
  5580.4  530.16  5594.6  528.51  5608.8  530.51  5644.7  531.80  5672.7  535.29
#Mann=3,-1,0
  4327.3    0.05       0  5019.3    0.03       0  5023.3    0.05       0
Bank Sta=5019.3,5023.3
Exp/Cntr=0.3,0.1

Type RM Length L Ch R = 1,12257,404,404,404
BEGIN DESCRIPTION:
High Point Creek Trib 1 28.0
END DESCRIPTION:
XS GIS Cut Line= 3
      2631025.99      6992511.00      2630476.00      6992861.00
      2630026.01      6993310.99
#Sta/Elev= 30
  4347.6  528.54  4370.5  527.44  4434.0  526.97  4470.4  525.55  4616.0  523.32
  4643.9  521.96  4688.8  520.90  4746.4  520.59  4809.9  518.24  4833.6  518.52
  4911.2  517.29  4911.4  516.79  4914.9  516.79  4915.2  517.29  4928.4  517.30
  4949.6  518.84  5003.0  518.00  5056.1  519.22  5197.5  520.18  5395.5  524.17
  5494.5  526.92  5508.6  526.56  5522.8  528.57  5536.9  528.80  5551.1  527.82
  5565.2  527.91  5579.3  529.10  5607.6  530.09  5632.4  536.44  5635.9  536.44
#Mann=3,-1,0
  4347.6    0.05       0  4911.2    0.05       0  4915.2    0.05       0
Bank Sta=4911.2,4915.2
Exp/Cntr=0.3,0.1

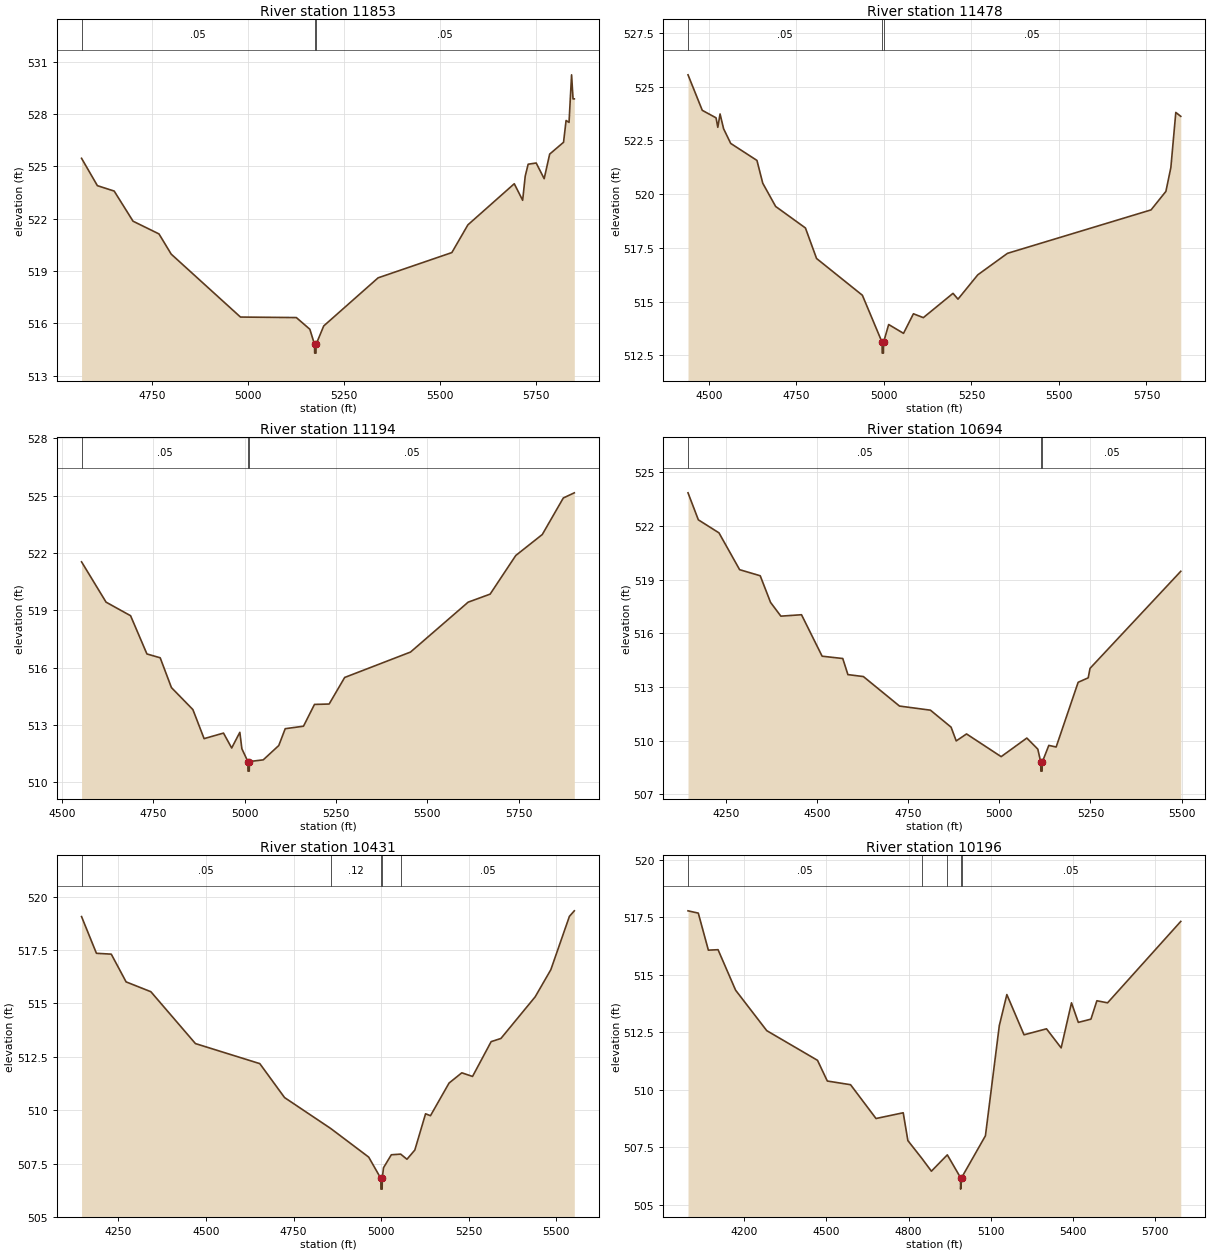
Type RM Length L Ch R = 1,11853,375,375,375
BEGIN DESCRIPTION:
High Point Creek Trib 1 26.0
END DESCRIPTION:
XS GIS Cut Line= 3
      2630826.04      6992360.99      2630418.00      6992504.67
      2629776.01      6993061.00
#Sta/Elev= 30
  4567.4  525.47  4608.6  523.90  4652.3  523.59  4701.4  521.86  4768.9  521.13
  4800.7  519.97  4980.9  516.36  5126.3  516.33  5161.4  515.66  5173.6  514.79
  5173.9  514.29  5177.4  514.29  5177.6  514.79  5197.5  515.85  5339.0  518.61
  5530.9  520.06  5572.6  521.65  5693.3  524.01  5715.1  523.06  5721.8  524.45
  5729.4  525.13  5750.3  525.20  5771.1  524.30  5785.4  525.71  5821.5  526.39
  5828.1  527.64  5835.8  527.53  5842.4  530.26  5846.2  528.88  5849.5  528.88
#Mann=3,-1,0
  4567.4    0.05       0  5173.6    0.05       0  5177.6    0.05       0
Bank Sta=5173.6,5177.6
Exp/Cntr=0.3,0.1

Type RM Length L Ch R = 1,11478,284,284,284
BEGIN DESCRIPTION:
High Point Creek Trib 1 25.0
END DESCRIPTION:
XS GIS Cut Line= 3
      2630826.02      6992311.00      2630276.00      6992211.00
      2629675.97      6992811.03
#Sta/Elev= 30
  4440.4  525.55  4481.1  523.90  4520.5  523.55  4525.5  523.11  4531.9  523.73
  4542.1  523.04  4562.4  522.36  4637.3  521.57  4653.9  520.51  4690.7  519.43
  4775.8  518.43  4807.6  517.01  4938.5  515.30  4994.9  513.11  4995.1  512.61
  4998.6  512.61  4998.9  513.11  5013.6  513.94  5056.0  513.53  5084.3  514.44
  5112.6  514.26  5197.4  515.39  5211.6  515.12  5268.1  516.25  5353.0  517.25
  5763.1  519.27  5805.5  520.13  5819.7  521.24  5833.8  523.80  5848.0  523.62
#Mann=3,-1,0
  4440.4    0.05       0  4994.9    0.03       0  4998.9    0.05       0
Bank Sta=4994.9,4998.9
Exp/Cntr=0.3,0.1

Type RM Length L Ch R = 1,11194,500,500,500
BEGIN DESCRIPTION:
High Point Creek Trib 1 24.0
END DESCRIPTION:
XS GIS Cut Line= 3
      2630675.99      6992161.00      2630276.00      6991961.00
      2629375.99      6992011.00
#Sta/Elev= 30
  4553.7  521.54  4620.8  519.43  4687.9  518.72  4732.6  516.72  4768.9  516.52
  4799.7  514.96  4858.4  513.81  4889.1  512.29  4942.2  512.58  4964.6  511.80
  4986.9  512.62  4992.5  511.76  5008.9  511.09  5009.2  510.59  5012.7  510.59
  5012.9  511.09  5051.0  511.18  5093.5  511.93  5111.1  512.81  5161.1  512.94
  5191.2  514.08  5231.3  514.10  5273.8  515.49  5454.1  516.82  5611.8  519.43
  5671.9  519.85  5742.0  521.87  5814.7  522.97  5872.2  524.88  5902.3  525.15
#Mann=3,-1,0
  4553.7    0.05       0  5008.9    0.03       0  5012.9    0.05       0
Bank Sta=5008.9,5012.9
Exp/Cntr=0.3,0.1

Type RM Length L Ch R = 1,10694,263,263,263
BEGIN DESCRIPTION:
High Point Creek Trib 1 23.0
END DESCRIPTION:
XS GIS Cut Line= 3
      2630776.02      6992161.02      2630176.00      6991561.00
      2629675.95      6991611.00
#Sta/Elev= 30
  4146.6  523.86  4174.9  522.35  4231.5  521.62  4288.1  519.56  4344.6  519.22
  4372.9  517.73  4401.2  516.96  4457.8  517.04  4514.3  514.72  4570.9  514.59
  4585.0  513.69  4627.5  513.58  4726.5  511.93  4811.3  511.70  4867.9  510.75
  4882.0  509.98  4910.3  510.37  5005.2  509.10  5075.6  510.14  5105.7  509.52
  5113.8  508.79  5114.0  508.29  5117.5  508.29  5117.8  508.79  5135.9  509.73
  5156.0  509.64  5216.3  513.26  5243.9  513.51  5248.9  514.04  5497.7  519.47
#Mann=3,-1,0
  4146.6    0.05       0  5113.8    0.03       0  5117.8    0.05       0
Bank Sta=5113.8,5117.8
Exp/Cntr=0.3,0.1

Type RM Length L Ch R = 1,10431,235,235,235
BEGIN DESCRIPTION:
High Point Creek Trib 1 22.0
END DESCRIPTION:
XS GIS Cut Line= 3
      2630826.03      6991911.03      2630226.00      6991311.00
      2629725.99      6991561.01
#Sta/Elev= 30
  4144.5  519.07  4187.0  517.35  4229.4  517.31  4271.8  516.01  4342.5  515.55
  4469.8  513.12  4653.7  512.18  4724.4  510.59  4856.4  509.14  4964.8  507.80
  4999.5  506.80  4999.7  506.30  5003.2  506.30  5003.5  506.80  5007.0  507.30
  5029.4  507.91  5056.1  507.94  5074.1  507.70  5096.5  508.13  5127.2  509.83
  5141.2  509.74  5194.3  511.27  5230.7  511.75  5261.4  511.58  5314.5  513.21
  5342.5  513.36  5440.3  515.31  5485.0  516.58  5538.1  519.08  5552.1  519.34
#Mann=5,-1,0
  4144.5    0.05       0  4856.4    0.12       0  4999.5    0.07       0
  5003.5    0.12       0  5056.1    0.05       0
Bank Sta=4999.5,5003.5
Exp/Cntr=0.3,0.1

Type RM Length L Ch R = 1,10196,463,463,463
BEGIN DESCRIPTION:
High Point Creek Trib 1 21.0
END DESCRIPTION:
XS GIS Cut Line= 4
      2630901.23      6991839.23      2630397.75      6991212.06
      2630226.00      6991111.00      2629442.32      6991233.97
#Sta/Elev= 30
  3995.9  517.77  4033.4  517.67  4070.1  516.06  4105.4  516.08  4169.4  514.32
  4283.0  512.56  4468.1  511.27  4503.8  510.37  4588.6  510.21  4681.4  508.74
  4780.6  508.99  4797.6  507.78  4848.4  507.01  4883.4  506.45  4941.4  507.16
  4989.6  506.17  4989.9  505.67  4993.6  506.17  5080.4  507.99  5131.0  512.78
  5158.5  514.13  5221.1  512.38  5303.1  512.64  5356.5  511.81  5394.2  513.77
  5419.1  512.92  5465.1  513.06  5486.8  513.86  5525.8  513.77  5792.7  517.31
#Mann=5,-1,0
  3995.9    0.05       0  4848.4    0.12       0  4941.4    0.05       0
  4989.6    0.04       0  4993.6    0.05       0
Bank Sta=4989.6,4993.6
Exp/Cntr=0.3,0.1

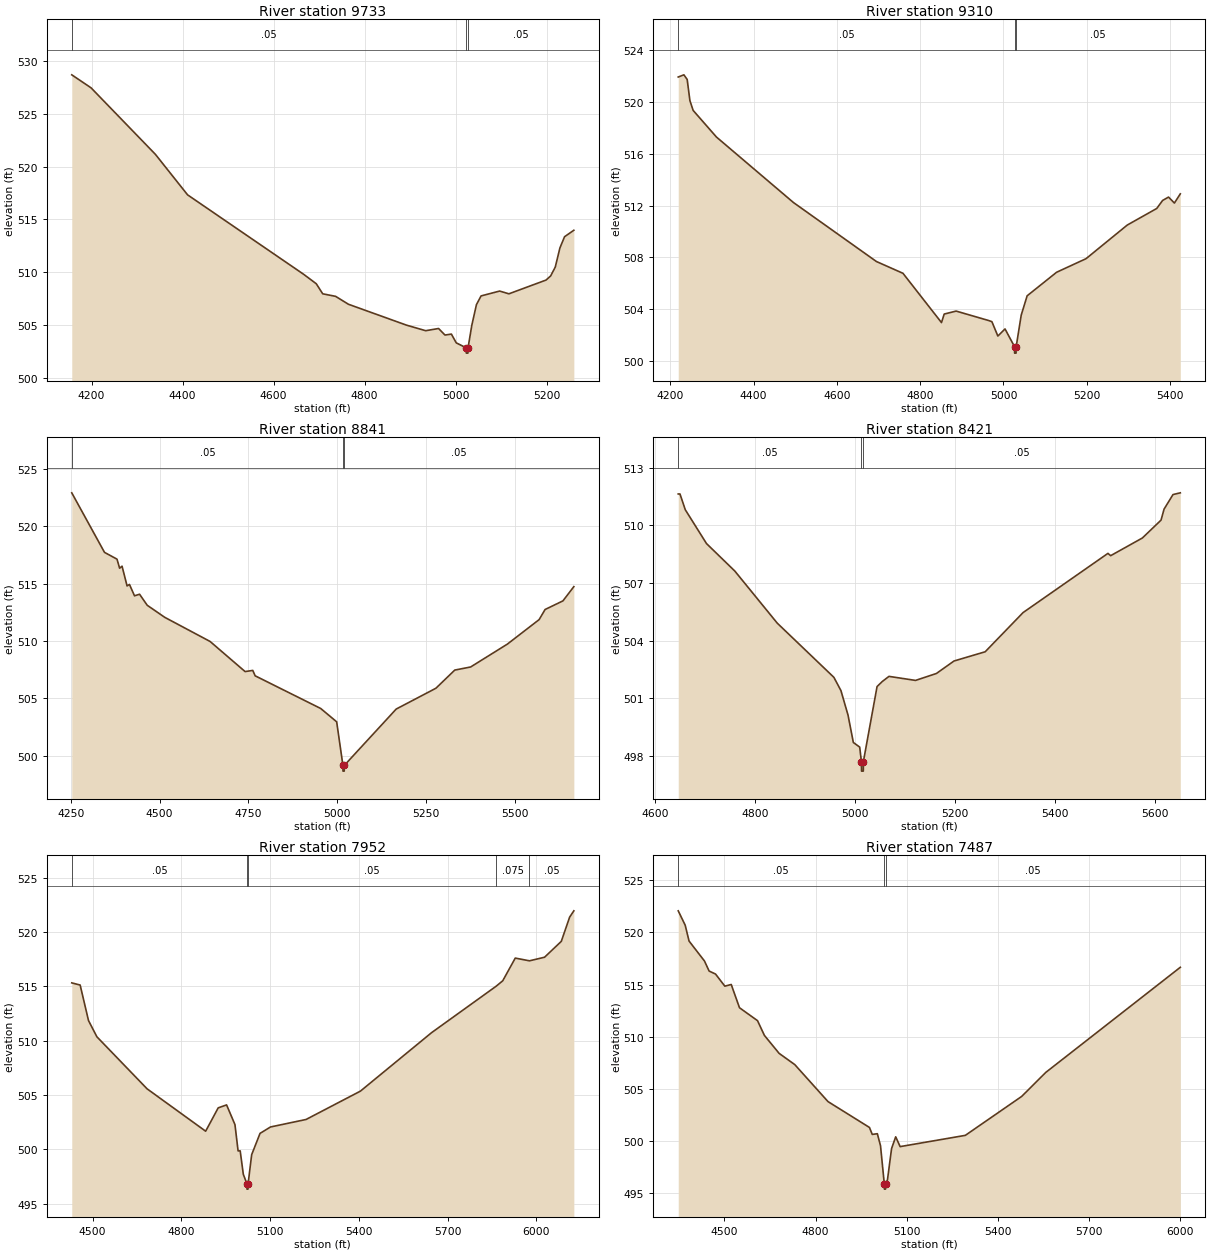
Type RM Length L Ch R = 1,9733,423,423,423
BEGIN DESCRIPTION:
High Point Creek Trib 1 20.0
END DESCRIPTION:
XS GIS Cut Line= 3
      2630675.97      6990261.03      2630076.00      6990861.00
      2630026.01      6991110.96
#Sta/Elev= 30
  4156.5  528.67  4198.9  527.44  4340.3  521.15  4411.0  517.32  4665.6  509.82
  4693.9  508.91  4708.0  507.96  4736.3  507.72  4764.6  506.97  4891.9  505.00
  4934.3  504.47  4962.6  504.68  4976.7  504.06  4990.8  504.15  5001.5  503.32
  5023.4  502.85  5023.6  502.35  5027.1  502.35  5027.4  502.85  5035.6  504.97
  5045.8  506.93  5056.0  507.76  5096.8  508.22  5117.2  507.96  5198.8  509.26
  5208.9  509.65  5219.1  510.49  5229.3  512.30  5239.5  513.36  5259.9  513.97
#Mann=3,-1,0
  4156.5    0.05       0  5023.4    0.04       0  5027.4    0.05       0
Bank Sta=5023.4,5027.4
Exp/Cntr=0.3,0.1

Type RM Length L Ch R = 1,9310,469,469,469
BEGIN DESCRIPTION:
High Point Creek Trib 1 19.0
END DESCRIPTION:
XS GIS Cut Line= 3
      2630375.98      6990161.01      2629776.00      6990661.00
      2629475.98      6990961.02
#Sta/Elev= 30
  4219.2  521.94  4232.8  522.11  4240.7  521.75  4247.2  520.12  4255.0  519.36
  4311.0  517.30  4495.8  512.24  4695.0  507.68  4758.7  506.77  4851.2  502.96
  4857.7  503.62  4886.3  503.85  4964.4  503.12  4972.2  503.03  4986.5  501.92
  5003.7  502.47  5026.5  501.10  5026.7  500.60  5030.2  500.60  5030.5  501.10
  5042.6  503.54  5056.8  505.03  5127.5  506.85  5198.2  507.90  5297.2  510.50
  5367.9  511.78  5382.0  512.40  5396.2  512.66  5410.3  512.20  5424.5  512.91
#Mann=3,-1,0
  4219.2    0.05       0  5026.5    0.04       0  5030.5    0.05       0
Bank Sta=5026.5,5030.5
Exp/Cntr=0.3,0.1

Type RM Length L Ch R = 1,8841,420,420,420
BEGIN DESCRIPTION:
High Point Creek Trib 1 18.0
END DESCRIPTION:
XS GIS Cut Line= 3
      2630026.00      6989811.00      2629476.00      6990311.00
      2629176.01      6990910.98
#Sta/Elev= 30
  4252.7  522.89  4344.9  517.71  4380.1  517.12  4387.5  516.33  4394.3  516.51
  4408.5  514.79  4415.2  514.92  4429.4  513.93  4443.6  514.07  4465.2  513.11
  4514.5  512.06  4642.3  509.96  4740.9  507.34  4762.5  507.44  4769.3  506.97
  4953.8  504.13  4998.8  502.97  5016.4  499.18  5016.6  498.68  5020.1  498.68
  5020.4  499.18  5166.5  504.08  5278.3  505.89  5331.4  507.47  5376.1  507.74
  5479.6  509.73  5569.0  511.86  5585.8  512.74  5636.1  513.49  5666.8  514.73
#Mann=3,-1,0
  4252.7    0.05       0  5016.4    0.03       0  5020.4    0.05       0
Bank Sta=5016.4,5020.4
Exp/Cntr=0.3,0.1

Type RM Length L Ch R = 1,8421,469,469,469
BEGIN DESCRIPTION:
High Point Creek Trib 1 17.0
END DESCRIPTION:
XS GIS Cut Line= 3
      2629425.96      6989811.04      2629176.00      6990061.00
      2628926.00      6990661.00
#Sta/Elev= 30
  4646.5  511.63  4650.0  511.63  4660.6  510.81  4703.0  509.05  4759.6  507.62
  4844.4  504.91  4957.6  502.09  4971.7  501.40  4985.9  500.12  4996.5  498.70
  5009.2  498.46  5012.6  497.71  5012.9  497.21  5016.4  497.21  5016.6  497.71
  5043.9  501.61  5054.2  501.87  5067.7  502.14  5120.8  501.93  5162.5  502.29
  5197.7  502.94  5260.0  503.42  5335.8  505.46  5505.4  508.54  5510.8  508.42
  5574.2  509.34  5611.5  510.27  5617.5  510.84  5635.4  511.60  5650.0  511.69
#Mann=3,-1,0
  4646.5    0.05       0  5012.6    0.03       0  5016.6    0.05       0
Bank Sta=5012.6,5016.6
Exp/Cntr=0.3,0.1

Type RM Length L Ch R = 1,7952,465,465,465
BEGIN DESCRIPTION:
High Point Creek Trib 1 16.0
END DESCRIPTION:
XS GIS Cut Line= 3
      2629276.02      6989310.98      2628876.00      6989711.00
      2628075.99      6990511.01
#Sta/Elev= 30
  4429.6  515.32  4457.9  515.12  4486.2  511.85  4514.5  510.36  4684.2  505.57
  4882.2  501.67  4924.6  503.82  4952.9  504.09  4981.2  502.28  4991.8  499.86
  4998.9  499.86  5009.5  497.70  5021.5  496.84  5021.8  496.34  5025.3  496.34
  5025.7  496.84  5037.7  499.51  5066.0  501.47  5101.4  502.06  5221.6  502.75
  5405.4  505.36  5645.9  510.74  5864.0  515.01  5886.3  515.51  5928.7  517.60
  5976.8  517.35  6027.7  517.68  6084.3  519.14  6112.5  521.37  6126.7  521.95
#Mann=5,-1,0
  4429.6    0.05       0  5021.5    0.03       0  5025.7    0.05       0
  5864.0   0.075       0  5976.8    0.05       0
Bank Sta=5021.5,5025.7
Exp/Cntr=0.3,0.1

Type RM Length L Ch R = 1,7487,469,469,469
BEGIN DESCRIPTION:
High Point Creek Trib 1 15.0
END DESCRIPTION:
XS GIS Cut Line= 3
      2629176.01      6989010.99      2628626.00      6989361.00
      2628026.02      6990160.97
#Sta/Elev= 30
  4348.1  522.08  4371.0  520.70  4383.7  519.18  4434.5  517.26  4449.7  516.30
  4470.9  516.01  4501.4  514.85  4522.5  515.01  4549.6  512.78  4608.9  511.54
  4631.7  510.12  4680.0  508.40  4731.6  507.32  4840.9  503.77  4977.2  501.29
  4986.5  500.62  5003.2  500.69  5013.6  499.54  5026.1  495.87  5026.4  495.37
  5030.0  495.37  5030.3  495.87  5036.5  496.26  5050.0  499.26  5063.6  500.39
  5078.2  499.45  5292.7  500.53  5478.2  504.27  5557.3  506.57  6000.0  516.66
#Mann=3,-1,0
  4348.1    0.05       0  5026.1    0.03       0  5030.3    0.05       0
Bank Sta=5026.1,5030.3
Exp/Cntr=0.3,0.1

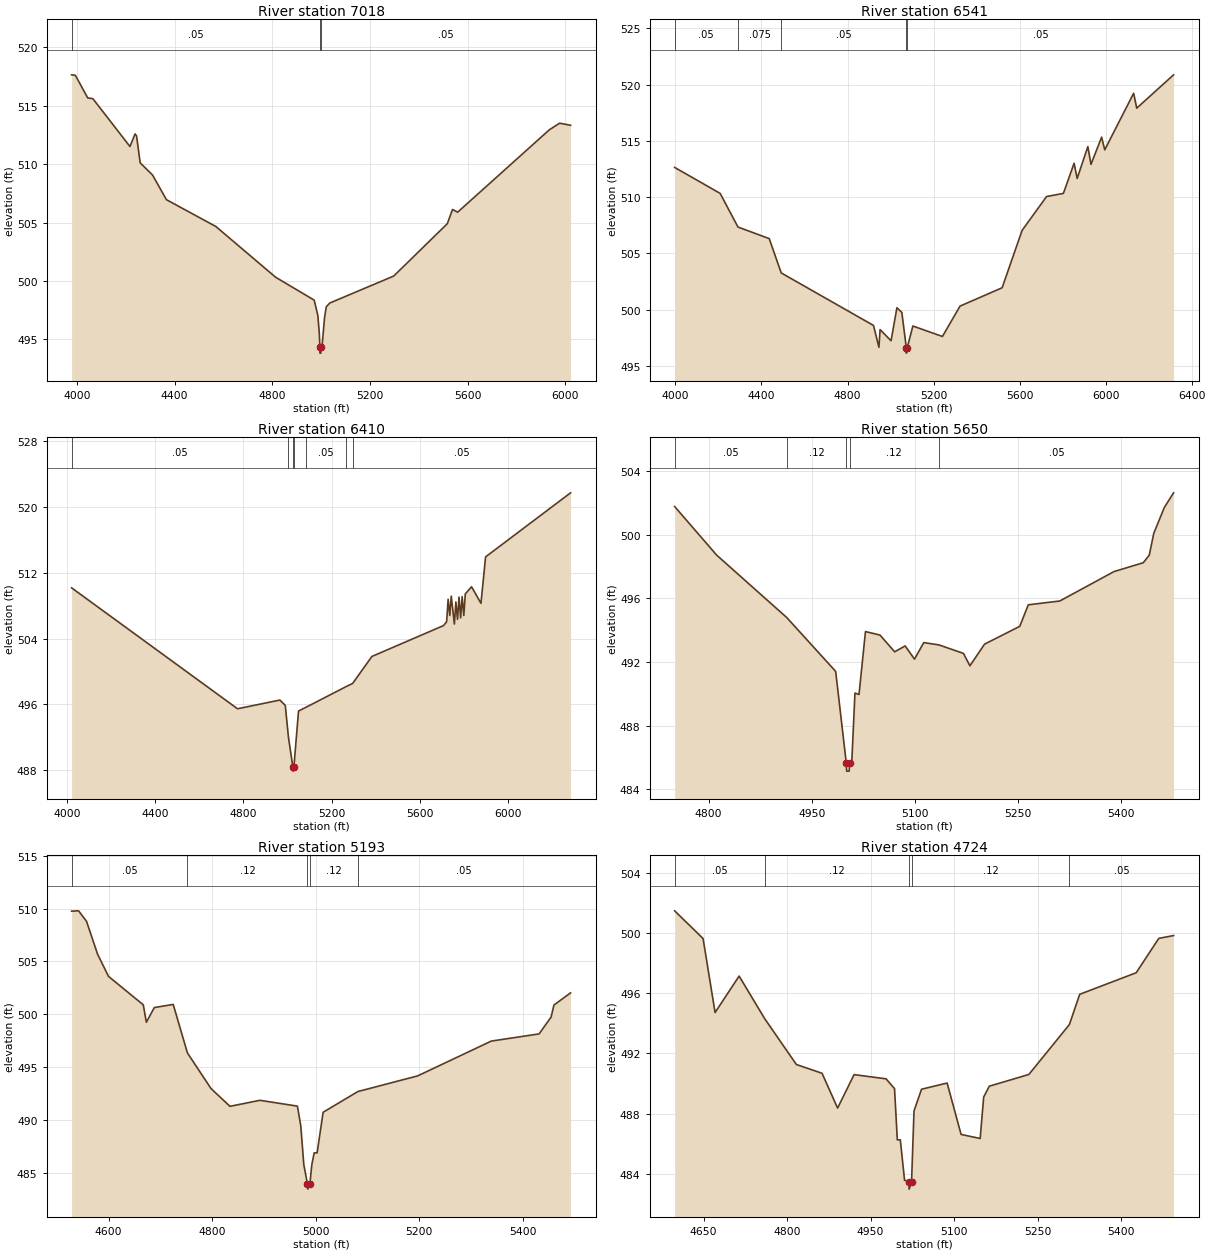
Type RM Length L Ch R = 1,7018,477,477,477
BEGIN DESCRIPTION:
High Point Creek Trib 1 14.0
END DESCRIPTION:
XS GIS Cut Line= 3
      2629163.86      6988427.36      2628326.00      6989011.00
      2627585.71      6989713.85
#Sta/Elev= 30
  3978.9  517.65  3994.3  517.61  4044.9  515.67  4065.8  515.61  4217.7  511.51
  4238.6  512.59  4244.7  512.42  4259.6  510.11  4310.2  509.07  4366.9  506.96
  4569.4  504.66  4813.7  500.32  4971.6  498.36  4986.5  497.06  4992.6  495.52
  4994.8  494.32  4995.2  493.82  4998.8  493.82  4999.2  494.32  5003.4  494.32
  5014.0  496.86  5021.2  497.79  5035.4  498.11  5297.1  500.42  5516.3  504.90
  5537.8  506.12  5558.8  505.89  5933.8  512.94  5976.2  513.51  6020.8  513.33
#Mann=3,-1,0
  3978.9    0.05       0  4994.8    0.03       0  4999.2    0.05       0
Bank Sta=4994.8,4999.2
Exp/Cntr=0.3,0.1

Type RM Length L Ch R = 1,6541,131,131,131
BEGIN DESCRIPTION:
Mapping XS fe47777b
END DESCRIPTION:
XS GIS Cut Line= 6
      2628340.95      6987677.37      2628167.36      6988324.41
      2628053.01      6988637.90      2627908.68      6988948.54
      2627829.64      6989069.23      2627311.58      6989716.68
#Sta/Elev= 30
  3996.3  512.64  4207.9  510.33  4290.7  507.34  4436.1  506.31  4491.8  503.26
  4920.9  498.59  4946.1  496.65  4951.5  498.22  5002.4  497.23  5029.7  500.16
  5052.6  499.75  5073.3  496.63  5073.7  496.13  5077.8  496.63  5103.9  498.54
  5241.3  497.61  5323.2  500.31  5518.9  501.94  5611.7  507.04  5725.4  510.05
  5803.8  510.33  5853.4  513.01  5867.8  511.66  5917.4  514.49  5931.9  512.91
  5981.5  515.33  5995.9  514.20  6130.3  519.23  6144.8  517.91  6316.0  520.87
#Mann=5,-1,0
  3996.3    0.05       0  4290.7   0.075       0  4491.8    0.05       0
  5073.3    0.05       0  5077.8    0.05       0
Bank Sta=5073.3,5077.8
Exp/Cntr=0.3,0.1

Type RM Length L Ch R = 1,6410,760,760,760
BEGIN DESCRIPTION:
Mapping XS 40dd9c3d
END DESCRIPTION:
XS GIS Cut Line= 5
      2628252.40      6987630.51      2628116.99      6988047.16
      2627951.03      6988560.92      2627736.78      6989052.36
      2627241.96      6989609.69
#Sta/Elev= 30
  4022.0  510.18  4773.3  495.48  4965.4  496.54  4989.6  495.89  5003.8  492.05
  5023.9  488.40  5024.4  487.90  5028.5  488.40  5049.6  495.21  5083.3  495.66
  5266.2  498.19  5294.6  498.56  5381.9  501.84  5706.0  505.59  5720.2  506.06
  5726.9  508.79  5734.4  506.82  5741.1  509.17  5755.3  505.78  5762.0  508.46
  5769.5  506.35  5776.2  509.05  5783.7  506.53  5790.4  509.11  5798.0  506.82
  5804.7  509.44  5833.1  510.31  5875.7  508.30  5896.6  513.94  6281.4  521.73
#Mann=7,-1,0
  4022.0    0.05       0  5003.8    0.12       0  5023.9    0.05       0
  5028.5    0.12       0  5083.3    0.05       0  5266.2    0.12       0
  5294.6    0.05       0
Bank Sta=5023.9,5028.5
Exp/Cntr=0.3,0.1

Type RM Length L Ch R = 1,5650,457,457,457
BEGIN DESCRIPTION:
High Point Creek Trib 1 11.0
END DESCRIPTION:
XS GIS Cut Line= 3
      2628125.98      6987861.00      2627876.00      6987911.00
      2627476.02      6988160.99
#Sta/Elev= 30
  4750.5  501.76  4811.7  498.71  4913.8  494.79  4985.0  491.41  5000.5  485.65
  5001.0  485.15  5004.7  485.15  5005.2  485.65  5008.4  485.65  5013.1  490.05
  5019.0  489.96  5028.4  493.91  5049.6  493.69  5070.9  492.64  5086.2  493.01
  5099.8  492.18  5113.3  493.22  5135.6  493.07  5171.1  492.54  5180.5  491.76
  5201.8  493.12  5253.1  494.24  5265.5  495.59  5311.4  495.83  5390.5  497.68
  5432.9  498.23  5441.7  498.71  5448.2  500.07  5463.6  501.70  5477.1  502.62
#Mann=5,-1,0
  4750.5    0.05       0  4913.8    0.12       0  5000.5    0.07       0
  5005.2    0.12       0  5135.6    0.05       0
Bank Sta=5000.5,5005.2
Exp/Cntr=0.3,0.1

Type RM Length L Ch R = 1,5193,469,469,469
BEGIN DESCRIPTION:
High Point Creek Trib 1 10.0
END DESCRIPTION:
XS GIS Cut Line= 3
      2628025.99      6987361.01      2627626.00      6987611.00
      2627426.01      6988060.98
#Sta/Elev= 30
  4528.6  509.76  4542.1  509.79  4557.5  508.79  4578.7  505.70  4599.9  503.59
  4667.1  500.90  4673.0  499.25  4688.4  500.64  4724.9  500.94  4752.4  496.35
  4798.0  492.98  4834.6  491.30  4892.4  491.87  4964.9  491.32  4971.4  489.47
  4977.3  485.77  4984.3  483.97  4984.9  483.47  4989.1  483.97  4992.6  485.74
  4997.3  486.90  5003.0  486.90  5014.6  490.74  5081.8  492.70  5197.3  494.18
  5339.5  497.47  5431.9  498.15  5455.1  499.74  5460.6  500.88  5492.7  502.03
#Mann=5,-1,0
  4528.6    0.05       0  4752.4    0.12       0  4984.3    0.07       0
  4989.1    0.12       0  5081.8    0.05       0
Bank Sta=4984.3,4989.1
Exp/Cntr=0.3,0.1

Type RM Length L Ch R = 1,4724,589,589,589
BEGIN DESCRIPTION:
High Point Creek Trib 1 9.0
END DESCRIPTION:
XS GIS Cut Line= 3
      2627725.97      6987161.02      2627376.00      6987361.00
      2626889.79      6987446.21
#Sta/Elev= 30
  4597.8  501.46  4648.9  499.62  4670.5  494.71  4713.7  497.13  4759.7  494.30
  4816.6  491.26  4862.7  490.68  4890.7  488.37  4920.3  490.59  4977.8  490.31
  4993.0  489.66  4998.0  486.26  5003.4  486.26  5011.0  483.58  5018.8  483.49
  5019.3  482.99  5023.6  483.49  5028.0  488.18  5041.5  489.62  5087.5  490.03
  5112.6  486.62  5146.9  486.35  5153.2  489.10  5163.3  489.82  5234.4  490.60
  5307.2  493.91  5325.8  495.92  5427.3  497.35  5467.9  499.63  5494.5  499.82
#Mann=5,-1,0
  4597.8    0.05       0  4759.7    0.12       0  5018.8    0.07       0
  5023.6    0.12       0  5307.2    0.05       0
Bank Sta=5018.8,5023.6
Exp/Cntr=0.3,0.1

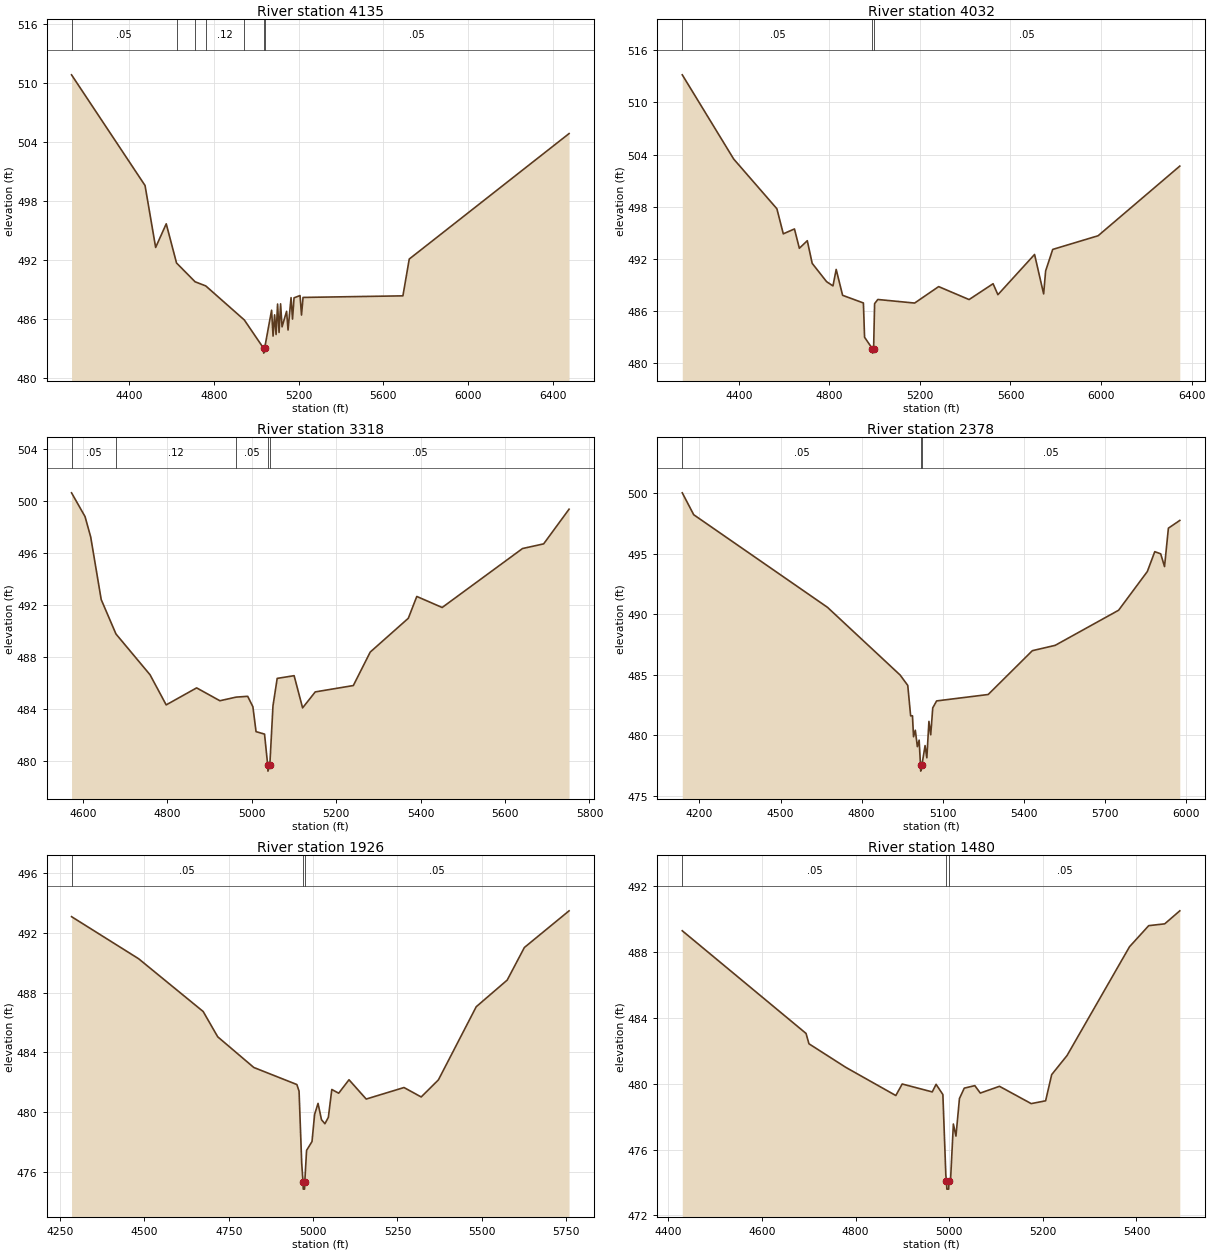
Type RM Length L Ch R = 1,4135,103,103,103
BEGIN DESCRIPTION:
Mapping XS 3f69ee00
END DESCRIPTION:
XS GIS Cut Line= 5
      2627982.89      6987110.96      2627493.29      6987126.58
      2627222.46      6986850.54      2626758.32      6986373.52
      2625951.66      6986392.21
#Sta/Elev= 30
  4128.0  510.85  4475.1  499.60  4525.1  493.31  4575.1  495.71  4623.7  491.73
  4711.3  489.82  4761.7  489.40  4943.8  485.94  5034.5  483.07  5035.2  482.57
  5039.7  483.07  5072.5  486.93  5079.5  484.30  5086.7  486.46  5093.7  484.46
  5100.8  487.56  5107.8  484.67  5115.0  487.58  5121.9  485.24  5143.3  486.82
  5150.2  484.92  5164.4  488.21  5171.4  486.03  5178.5  488.19  5206.8  488.42
  5213.8  486.44  5221.0  488.23  5692.5  488.39  5722.5  492.13  6477.0  504.88
#Mann=7,-1,0
  4128.0    0.05       0  4623.7    0.12       0  4711.3    0.05       0
  4761.7    0.12       0  4943.8    0.05       0  5034.5    0.03       0
  5039.7    0.05       0
Bank Sta=5034.5,5039.7
Exp/Cntr=0.3,0.1

Type RM Length L Ch R = 1,4032,714,714,714
BEGIN DESCRIPTION:
Mapping XS 4a2155db
END DESCRIPTION:
XS GIS Cut Line= 5
      2627962.01      6986992.47      2627529.75      6987034.13
      2627253.71      6986778.93      2626786.96      6986305.81
      2626066.20      6986252.88
#Sta/Elev= 30
  4150.3  513.15  4377.4  503.48  4568.2  497.77  4596.5  494.89  4645.8  495.45
  4667.4  493.23  4702.5  494.10  4724.1  491.50  4787.6  489.40  4815.9  488.91
  4830.1  490.80  4858.5  487.83  4950.3  486.95  4955.5  483.01  4990.2  481.69
  4990.9  481.19  4995.4  481.69  4999.8  486.87  5013.9  487.35  5176.6  486.94
  5282.7  488.83  5417.1  487.34  5523.1  489.16  5544.4  487.90  5706.3  492.52
  5746.4  487.99  5755.2  490.63  5786.5  493.10  5987.0  494.67  6347.8  502.67
#Mann=3,-1,0
  4150.3    0.05       0  4990.2    0.03       0  4995.4    0.05       0
Bank Sta=4990.2,4995.4
Exp/Cntr=0.3,0.1

Type RM Length L Ch R = 1,3318,940,940,940
BEGIN DESCRIPTION:
High Point Creek Trib 1 6.0
END DESCRIPTION:
XS GIS Cut Line= 3
      2627425.99      6986311.00      2627026.00      6986161.00
      2626275.96      6986211.00
#Sta/Elev= 30
  4572.8  500.65  4604.8  498.82  4618.2  497.25  4643.1  492.43  4678.1  489.78
  4758.8  486.64  4797.1  484.32  4869.2  485.63  4924.3  484.64  4963.0  484.92
  4990.2  484.98  5002.5  484.18  5010.0  482.26  5030.1  482.07  5037.5  479.72
  5038.2  479.22  5042.7  479.72  5050.1  484.24  5060.1  486.36  5100.2  486.57
  5120.3  484.09  5150.3  485.32  5240.5  485.81  5280.6  488.39  5370.8  490.99
  5390.9  492.67  5451.0  491.82  5641.4  496.36  5691.5  496.72  5751.7  499.39
#Mann=5,-1,0
  4572.8    0.05       0  4678.1    0.12       0  4963.0    0.05       0
  5037.5    0.04       0  5042.7    0.05       0
Bank Sta=5037.5,5042.7
Exp/Cntr=0.3,0.1

Type RM Length L Ch R = 1,2378,452,452,452
BEGIN DESCRIPTION:
High Point Creek Trib 1 5.0
END DESCRIPTION:
XS GIS Cut Line= 3
      2627676.00      6985961.00      2627076.00      6985361.00
      2626326.00      6986011.00
#Sta/Elev= 30
  4136.5  500.03  4178.9  498.22  4673.9  490.57  4942.6  484.98  4970.9  484.12
  4981.5  481.61  4988.3  481.61  4992.2  479.88  4998.8  480.42  5006.4  479.06
  5013.0  479.60  5018.0  477.54  5018.8  477.04  5023.3  477.54  5034.9  479.15
  5041.5  478.14  5049.2  481.15  5055.8  480.04  5063.4  482.27  5077.7  482.84
  5268.5  483.37  5431.9  486.99  5516.4  487.43  5751.0  490.33  5857.4  493.53
  5884.9  495.17  5906.8  494.99  5921.0  493.94  5935.3  497.11  5977.5  497.75
#Mann=3,-1,0
  4136.5    0.05       0  5018.0    0.04       0  5023.3    0.05       0
Bank Sta=5018,5023.3
Exp/Cntr=0.3,0.1

Type RM Length L Ch R = 1,1926,446,446,446
BEGIN DESCRIPTION:
High Point Creek Trib 1 4.0
END DESCRIPTION:
XS GIS Cut Line= 3
      2627575.97      6985560.97      2627126.00      6985011.00
      2626376.04      6985160.99
#Sta/Elev= 30
  4283.7  493.07  4482.5  490.26  4674.1  486.73  4717.2  485.04  4824.2  482.99
  4951.9  481.85  4958.4  481.41  4966.3  476.57  4970.1  475.36  4970.9  474.86
  4974.7  474.86  4975.4  475.36  4980.7  477.45  4996.8  478.04  5004.5  479.85
  5014.7  480.59  5024.9  479.50  5035.1  479.23  5045.3  479.66  5055.5  481.52
  5075.9  481.27  5106.5  482.17  5157.5  480.88  5269.6  481.65  5320.6  481.02
  5371.6  482.16  5483.8  487.05  5575.6  488.83  5626.6  491.01  5759.1  493.46
#Mann=3,-1,0
  4283.7    0.05       0  4970.1    0.04       0  4975.4    0.05       0
Bank Sta=4970.1,4975.4
Exp/Cntr=0.3,0.1

Type RM Length L Ch R = 1,1480,466,466,466
BEGIN DESCRIPTION:
High Point Creek Trib 1 3.0
END DESCRIPTION:
XS GIS Cut Line= 3
      2627726.03      6985161.03      2627376.00      6984711.00
      2626925.98      6984510.99
#Sta/Elev= 30
  4430.0  489.28  4694.3  483.05  4700.6  482.42  4779.3  480.99  4886.1  479.28
  4899.7  479.98  4963.9  479.50  4972.1  479.96  4986.6  479.34  4992.9  474.45
  4994.3  474.10  4995.1  473.60  4998.9  473.60  4999.6  474.10  5002.9  474.10
  5009.0  477.55  5014.5  476.82  5022.0  479.10  5032.3  479.73  5054.8  479.88
  5066.5  479.43  5107.5  479.84  5175.2  478.79  5206.0  478.96  5219.0  480.55
  5251.8  481.71  5385.2  488.31  5426.2  489.59  5460.4  489.70  5492.6  490.49
#Mann=3,-1,0
  4430.0    0.05       0  4994.3    0.04       0  4999.6    0.05       0
Bank Sta=4994.3,4999.6
Exp/Cntr=0.3,0.1

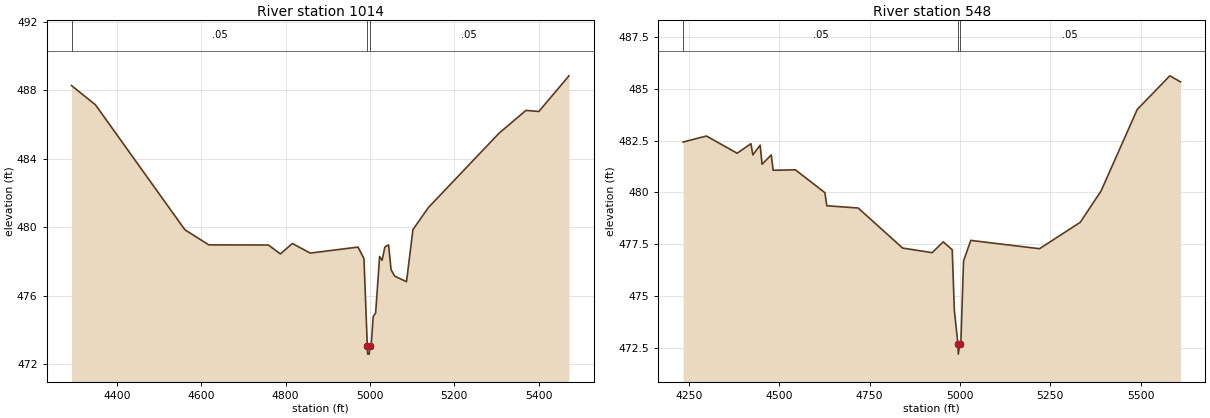
Type RM Length L Ch R = 1,1014,466,466,466
BEGIN DESCRIPTION:
High Point Creek Trib 1 2.0
END DESCRIPTION:
XS GIS Cut Line= 3
      2627926.02      6984761.02      2627426.00      6984261.00
      2627026.03      6984510.98
#Sta/Elev= 30
  4292.9  488.26  4349.5  487.14  4561.6  479.84  4618.2  478.96  4759.6  478.95
  4787.9  478.43  4816.2  479.04  4858.6  478.48  4971.8  478.83  4985.9  478.16
  4993.8  473.08  4994.6  472.58  4998.5  472.58  4999.3  473.08  5003.0  473.08
  5007.7  474.76  5013.6  474.99  5023.0  478.28  5028.9  478.06  5035.4  478.83
  5044.3  478.96  5050.2  477.50  5059.0  477.13  5086.7  476.81  5102.0  479.85
  5138.6  481.14  5306.1  485.48  5369.7  486.81  5400.4  486.75  5471.7  488.83
#Mann=3,-1,0
  4292.9    0.05       0  4993.8    0.04       0  4999.3    0.05       0
Bank Sta=4993.8,4999.3
Exp/Cntr=0.3,0.1

Type RM Length L Ch R = 1,548,0,0,0
BEGIN DESCRIPTION:
High Point Creek Trib 1 1.0
END DESCRIPTION:
XS GIS Cut Line= 3
      2628196.65      6984069.75      2627476.00      6983811.00
      2626866.32      6983783.29
#Sta/Elev= 30
  4234.3  482.43  4298.7  482.72  4383.7  481.89  4421.9  482.35  4427.2  481.81
  4447.4  482.28  4452.7  481.36  4478.1  481.81  4483.4  481.07  4544.9  481.09
  4626.4  479.99  4631.8  479.36  4718.6  479.25  4841.6  477.32  4923.2  477.10
  4953.9  477.62  4978.7  477.24  4984.6  474.32  4994.5  472.71  4995.4  472.21
  5000.1  472.71  5002.5  472.71  5010.0  476.70  5030.0  477.69  5220.2  477.29
  5332.8  478.56  5390.4  480.07  5490.5  484.00  5580.6  485.62  5610.3  485.33
#Mann=3,-1,0
  4234.3    0.05       0  4994.5    0.04       0  5000.1    0.05       0
Bank Sta=4994.5,5000.1
Exp/Cntr=0.3,0.1

Chan Stop Cuts=-1