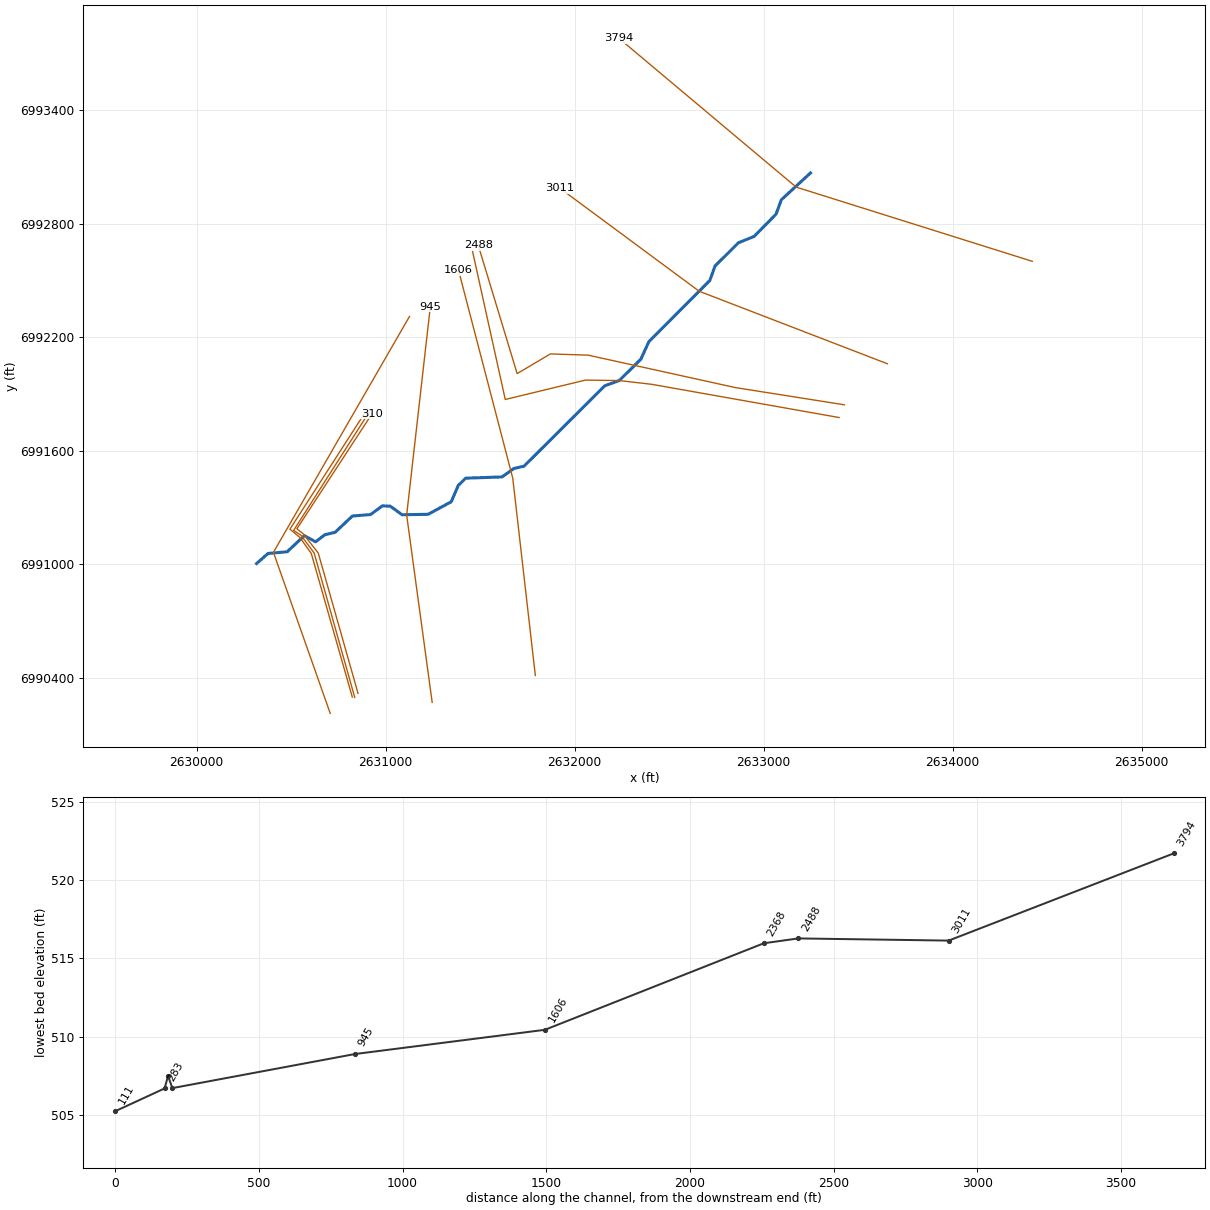
--- High Point Creek Trib 1_1.prj (project) ---

Proj Title=High Point Creek Trib 1_1 Base Level Engineering
Current Plan=p01
Default Exp/Contr=0.3,0.1
English Units
Geom File=g01
Flow File=f01
Plan File=p01
BEGIN DESCRIPTION:
High Point Creek Trib 1_1
END DESCRIPTION:

--- High Point Creek Trib 1_1.p01 (plan) ---

Plan Title=Multiple Run
Short Identifier=Multiple
Geom File=g01
Flow File=f01
Subcritical Flow
K Sum by GR= 0
Std Step Tol= 0.01
Critical Tol= 0.01
Num of Std Step Trials= 20
Max Error Tol= 0.3
Flow Tol Ratio= 0.001
Split Flow NTrial= 30
Split Flow Tol= 0.02
Split Flow Ratio= 0.02
Log Output Level= 0
Friction Slope Method= 1
Unsteady Friction Slope Method= 2
Unsteady Bridges Friction Slope Method= 1
Parabolic Critical Depth
Global Vel Dist=  1 , 1 , 1
Global Log Level= 0
CheckData=True
Encroach Param= -1, 0, 0, 0
BEGIN DESCRIPTION:
Multiple Run
END DESCRIPTION:

--- High Point Creek Trib 1_1.f01 (steady flow) ---

Flow Title=Multiple
Number of Profiles=7
Profile Names=10-year,25-year,50-year,1pct_min,100-year,1pct_plu,500-year
River Rch & RM= High Point Creek,Reach-1,3794
     356     461     543     318     635    1266     864
Boundary for River Rch & Prof#=High Point Creek,Reach-1,1
Up Type=0
Dn Type=3
Dn Slope=0.005
Boundary for River Rch & Prof#=High Point Creek,Reach-1,2
Up Type=0
Dn Type=3
Dn Slope=0.005
Boundary for River Rch & Prof#=High Point Creek,Reach-1,3
Up Type=0
Dn Type=3
Dn Slope=0.005
Boundary for River Rch & Prof#=High Point Creek,Reach-1,4
Up Type=0
Dn Type=3
Dn Slope=0.005
Boundary for River Rch & Prof#=High Point Creek,Reach-1,5
Up Type=0
Dn Type=3
Dn Slope=0.005
Boundary for River Rch & Prof#=High Point Creek,Reach-1,6
Up Type=0
Dn Type=3
Dn Slope=0.005
Boundary for River Rch & Prof#=High Point Creek,Reach-1,7
Up Type=0
Dn Type=3
Dn Slope=0.005

--- High Point Creek Trib 1_1.g01 (geometry) ---

Geom Title=Existing Conditions

River Reach=High Point Creek,Reach-1
Reach XY= 30
      2633247.75      6993069.56      2633093.34      6992927.71
      2633065.26      6992851.32      2632949.47      6992734.01
      2632866.32      6992700.22      2632742.65      6992577.67
      2632715.22      6992501.32      2632392.65      6992177.67
      2632349.70      6992084.18      2632235.68      6991971.78
      2632159.33      6991944.35      2631732.06      6991519.14
      2631677.75      6991506.78      2631615.50      6991462.20
      2631423.30      6991455.64      2631384.03      6991417.36
      2631346.47      6991330.63      2631224.44      6991264.74
      2631086.50      6991262.23      2631024.26      6991307.63
      2630982.12      6991309.18      2630920.03      6991263.38
      2630823.58      6991255.46      2630732.04      6991169.14
      2630677.65      6991156.56      2630629.23      6991119.25
      2630569.34      6991151.68      2630478.44      6991066.53
      2630377.41      6991057.61      2630316.78      6991004.40

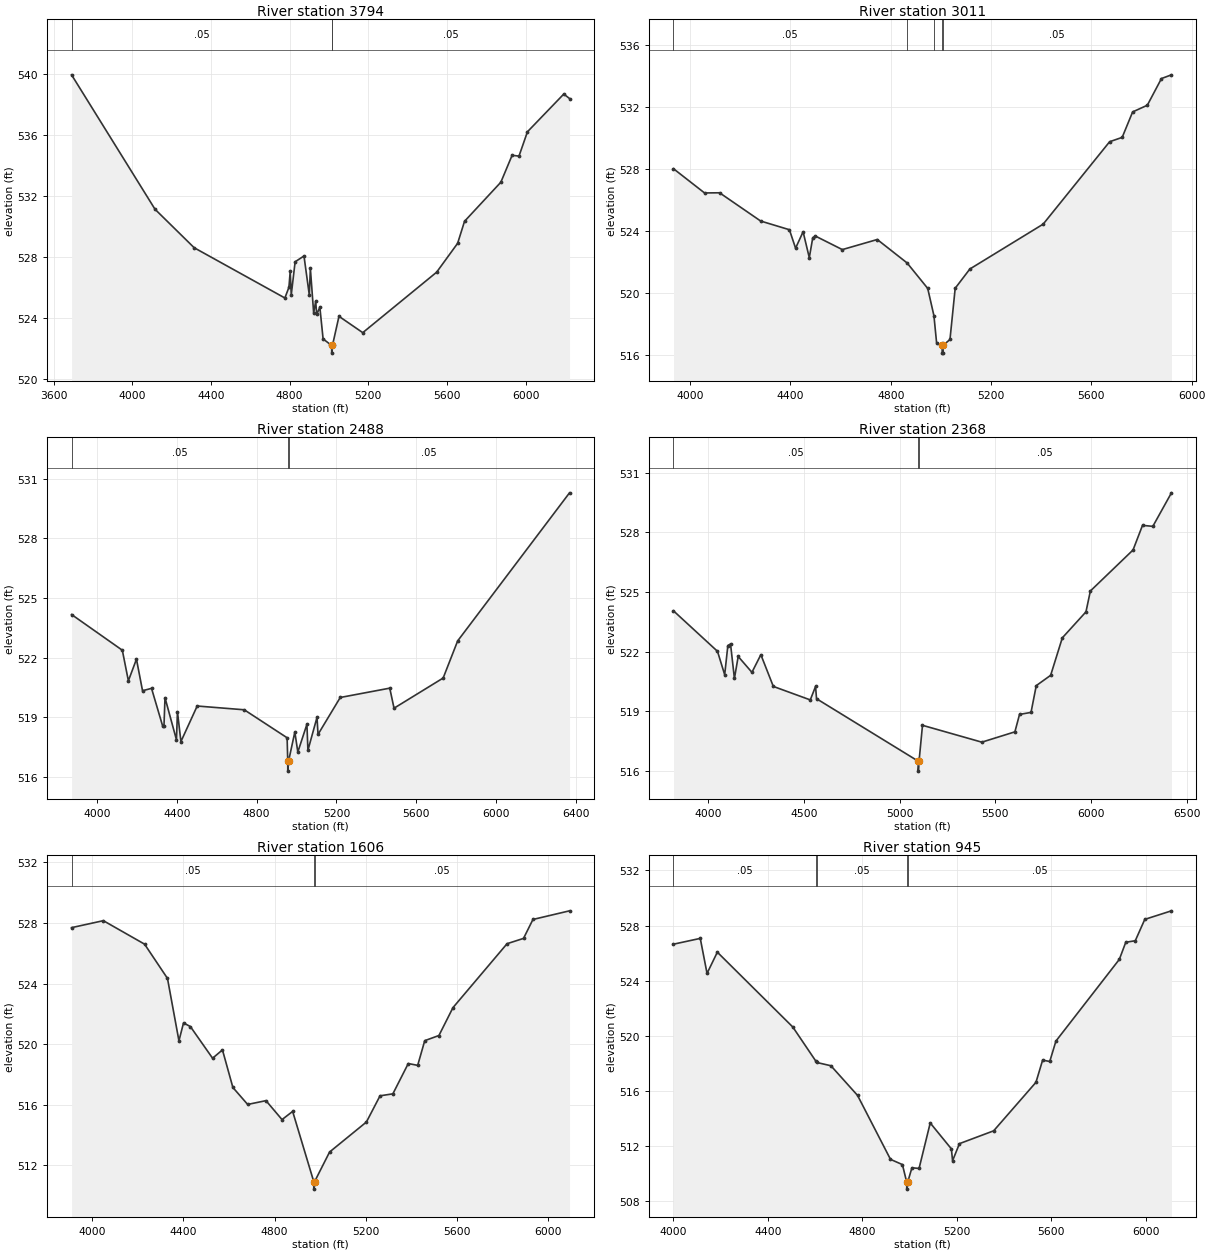
Type RM Length L Ch R = 1,3794,783,783,783
BEGIN DESCRIPTION:
High Point Creek Trib 1_1 7.0
END DESCRIPTION:
XS GIS Cut Line= 3
      2634421.02      6992602.31      2633171.80      6992994.69
      2632234.26      6993781.27
#Sta/Elev= 30
  3690.6  539.94  4115.1  531.14  4314.3  528.62  4775.8  525.33  4796.4  526.03
  4802.9  527.08  4808.2  525.53  4827.9  527.70  4873.0  528.08  4900.1  525.52
  4905.4  527.27  4922.2  524.35  4932.5  525.12  4937.8  524.25  4953.7  524.73
  4970.2  522.65  5013.8  522.22  5014.1  521.72  5017.8  522.22  5051.0  524.13
  5172.0  523.06  5547.9  527.02  5654.6  528.91  5689.7  530.35  5874.5  532.91
  5931.7  534.67  5966.8  534.62  6009.7  536.21  6194.5  538.68  6223.8  538.39
#Mann=3,-1,0
  3690.6    0.05       0  5013.8    0.03       0  5017.8    0.05       0
Bank Sta=5013.8,5017.8
Exp/Cntr=0.3,0.1

Type RM Length L Ch R = 1,3011,523,523,523
BEGIN DESCRIPTION:
High Point Creek Trib 1_1 6.0
END DESCRIPTION:
XS GIS Cut Line= 3
      2633654.42      6992060.69      2632659.00      6992443.82
      2631919.63      6992990.28
#Sta/Elev= 30
  3933.4  528.02  4057.2  526.46  4117.2  526.47  4281.1  524.65  4395.7  524.09
  4420.3  522.90  4450.3  523.96  4475.0  522.29  4488.9  523.58  4499.6  523.68
  4606.8  522.81  4746.1  523.46  4865.1  521.95  4947.3  520.31  4972.1  518.55
  4982.7  516.81  5004.8  516.64  5005.1  516.14  5008.6  516.14  5008.8  516.64
  5036.1  517.02  5056.9  520.32  5115.4  521.56  5407.7  524.45  5672.8  529.76
  5722.9  530.04  5764.6  531.68  5823.1  532.11  5879.5  533.83  5919.4  534.07
#Mann=5,-1,0
  3933.4    0.05       0  4865.1    0.12       0  4972.1    0.05       0
  5004.8    0.03       0  5008.8    0.05       0
Bank Sta=5004.8,5008.8
Exp/Cntr=0.3,0.1

Type RM Length L Ch R = 1,2488,120,120,120
BEGIN DESCRIPTION:
Mapping XS 27cbc28b
END DESCRIPTION:
XS GIS Cut Line= 6
      2633427.25      6991843.57      2632850.01      6991934.71
      2632070.93      6992106.16      2631871.28      6992112.67
      2631695.50      6992008.50      2631489.59      6992686.90
#Sta/Elev= 30
  3872.7  524.17  4127.1  522.37  4157.4  520.83  4197.9  521.92  4228.3  520.33
  4273.4  520.45  4329.5  518.54  4335.8  518.57  4340.9  519.98  4398.3  517.86
  4403.3  519.27  4420.7  517.77  4502.2  519.56  4738.1  519.37  4952.8  517.96
  4956.0  516.78  4956.2  516.28  4960.0  516.78  4991.5  518.25  5006.5  517.24
  5052.0  518.64  5057.1  517.33  5102.6  518.99  5107.7  518.13  5219.1  519.99
  5467.1  520.46  5488.6  519.45  5734.7  520.97  5807.4  522.84  6367.9  530.30
#Mann=3,-1,0
  3872.7    0.05       0  4956.0    0.04       0  4960.0    0.05       0
Bank Sta=4956,4960
Exp/Cntr=0.3,0.1

Type RM Length L Ch R = 1,2368,762,762,762
BEGIN DESCRIPTION:
Mapping XS d4ae6239
END DESCRIPTION:
XS GIS Cut Line= 6
      2633399.10      6991776.29      2632408.78      6991951.74
      2632235.68      6991971.78      2632057.22      6991974.31
      2631632.56      6991871.78      2631459.10      6992656.70
#Sta/Elev= 30
  3820.0  524.05  4049.6  522.01  4087.2  520.83  4103.7  522.30  4117.7  522.38
  4138.0  520.64  4157.7  521.75  4229.4  520.95  4276.0  521.84  4341.1  520.24
  4534.0  519.56  4561.5  520.24  4566.6  519.62  5097.7  516.47  5097.9  515.97
  5101.7  516.47  5119.7  518.28  5429.4  517.43  5602.0  517.95  5626.2  518.83
  5686.2  518.93  5713.5  520.28  5788.6  520.80  5849.6  522.69  5973.0  524.00
  5995.9  525.05  6218.8  527.12  6268.1  528.36  6322.0  528.31  6419.2  530.00
#Mann=3,-1,0
  3820.0    0.05       0  5097.7    0.04       0  5101.7    0.05       0
Bank Sta=5097.7,5101.7
Exp/Cntr=0.3,0.1

Type RM Length L Ch R = 1,1606,661,661,661
BEGIN DESCRIPTION:
High Point Creek Trib 1_1 3.0
END DESCRIPTION:
XS GIS Cut Line= 3
      2631791.72      6990412.31      2631672.21      6991455.64
      2631384.88      6992556.50
#Sta/Elev= 30
  3908.3  527.69  4047.9  528.15  4229.1  526.60  4329.7  524.34  4380.1  520.22
  4400.2  521.40  4430.4  521.16  4527.9  519.07  4571.3  519.62  4617.1  517.14
  4682.0  516.02  4762.5  516.27  4833.0  515.02  4879.7  515.56  4972.3  510.93
  4972.6  510.43  4976.3  510.93  5042.0  512.88  5203.8  514.86  5263.7  516.59
  5320.1  516.72  5387.7  518.72  5429.1  518.60  5460.1  520.23  5522.4  520.57
  5584.1  522.41  5821.8  526.63  5894.1  526.98  5935.5  528.23  6096.2  528.80
#Mann=3,-1,0
  3908.3    0.05       0  4972.3    0.04       0  4976.3    0.05       0
Bank Sta=4972.3,4976.3
Exp/Cntr=0.3,0.1

Type RM Length L Ch R = 1,945,635,635,635
BEGIN DESCRIPTION:
High Point Creek Trib 1_1 2.0
END DESCRIPTION:
XS GIS Cut Line= 3
      2631245.84      6990270.20      2631110.84      6991260.54
      2631236.14      6992363.24
#Sta/Elev= 30
  4000.5  526.65  4113.9  527.07  4142.6  524.53  4186.2  526.07  4505.9  520.64
  4604.1  518.15  4607.1  518.07  4667.4  517.83  4780.1  515.68  4919.7  511.04
  4970.2  510.66  4988.4  509.38  4988.6  508.88  4992.4  509.38  5010.5  510.43
  5040.7  510.38  5088.0  513.68  5177.6  511.80  5182.6  510.94  5211.8  512.18
  5356.7  513.11  5535.9  516.63  5564.1  518.24  5594.3  518.14  5620.4  519.62
  5889.1  525.55  5916.3  526.79  5956.6  526.90  5996.8  528.45  6109.8  529.07
#Mann=5,-1,0
  4000.5    0.05       0  4604.1    0.12       0  4607.1    0.05       0
  4988.4    0.04       0  4992.4    0.05       0
Bank Sta=4988.4,4992.4
Exp/Cntr=0.3,0.1

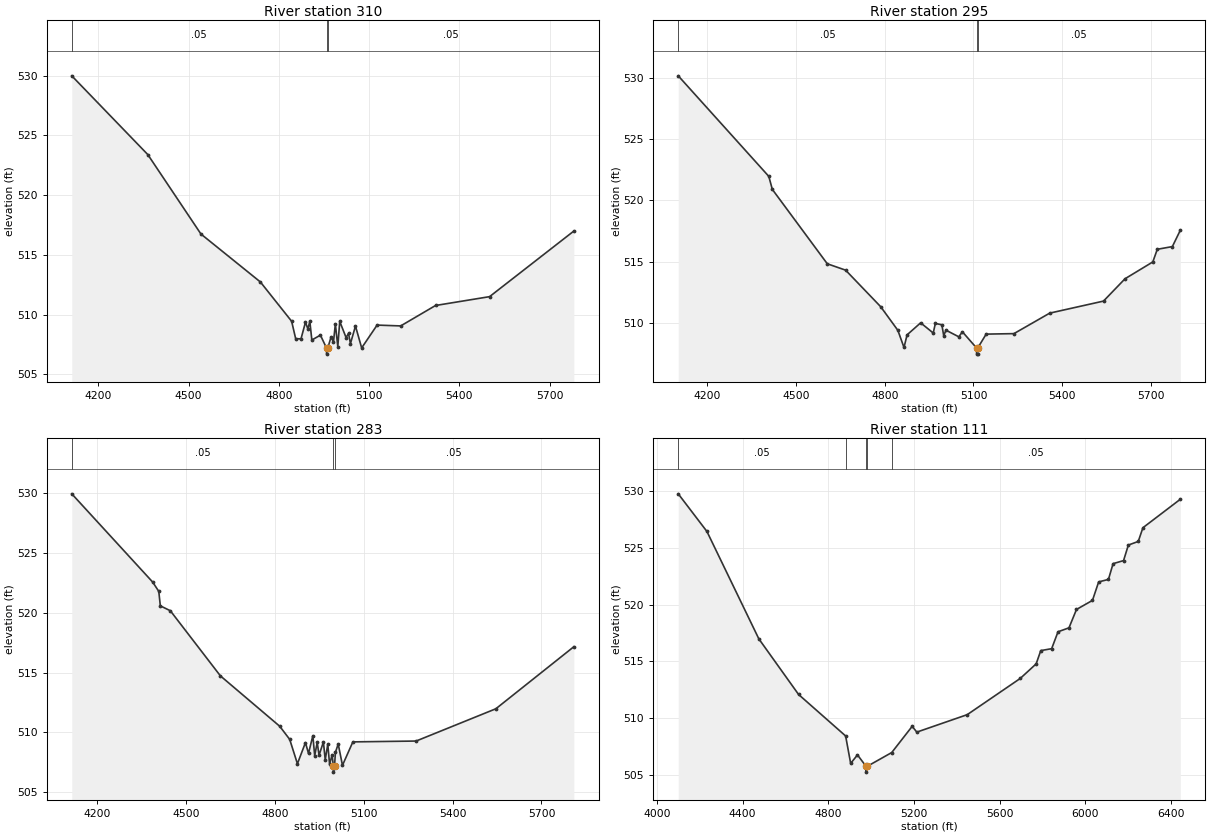
Type RM Length L Ch R = 1,310,15,15,15
BEGIN DESCRIPTION:
Mapping XS 35b57c0b
END DESCRIPTION:
XS GIS Cut Line= 5
      2630853.49      6990317.92      2630642.98      6991060.15
      2630562.68      6991162.15      2630530.13      6991188.19
      2630927.26      6991795.82
#Sta/Elev= 30
  4111.4  529.99  4364.1  523.40  4540.8  516.75  4738.3  512.74  4842.2  509.45
  4855.7  507.99  4873.4  507.98  4888.2  509.37  4896.3  508.81  4902.7  509.45
  4909.4  507.88  4937.9  508.29  4958.3  507.20  4958.6  506.70  4962.3  507.20
  4973.2  508.13  4981.3  507.71  4987.6  509.23  4995.7  507.33  5002.1  509.44
  5023.3  508.08  5031.3  508.44  5037.7  507.58  5054.4  509.05  5075.0  507.22
  5126.3  509.13  5204.7  509.06  5320.6  510.77  5500.2  511.51  5780.3  517.00
#Mann=3,-1,0
  4111.4    0.05       0  4958.3    0.03       0  4962.3    0.05       0
Bank Sta=4958.3,4962.3
Exp/Cntr=0.3,0.1

Type RM Length L Ch R = 1,295,12,12,12
BEGIN DESCRIPTION:
Mapping XS 9de0c5da
END DESCRIPTION:
XS GIS Cut Line= 5
      2630836.13      6990296.22      2630621.28      6991060.15
      2630551.83      6991153.46      2630512.77      6991179.51
      2630911.54      6991803.67
#Sta/Elev= 30
  4101.8  530.15  4408.0  521.96  4419.9  520.90  4605.7  514.84  4667.7  514.32
  4786.4  511.34  4844.3  509.42  4865.1  508.02  4875.5  509.05  4921.4  510.03
  4963.9  509.20  4971.2  509.98  4993.1  509.87  4999.4  508.98  5007.0  509.43
  5050.5  508.89  5062.5  509.30  5110.4  507.98  5110.7  507.48  5114.2  507.48
  5114.4  507.98  5142.9  509.11  5236.8  509.15  5357.8  510.82  5539.6  511.80
  5612.4  513.62  5706.3  514.99  5721.5  516.02  5772.4  516.24  5799.3  517.57
#Mann=3,-1,0
  4101.8    0.05       0  5110.4    0.03       0  5114.4    0.05       0
Bank Sta=5110.4,5114.4
Exp/Cntr=0.3,0.1

Type RM Length L Ch R = 1,283,172,172,172
BEGIN DESCRIPTION:
Mapping XS 26920099
END DESCRIPTION:
XS GIS Cut Line= 5
      2630823.11      6990298.38      2630606.09      6991057.98
      2630545.32      6991142.61      2630493.24      6991186.02
      2630890.39      6991802.36
#Sta/Elev= 30
  4114.1  529.96  4387.2  522.58  4407.9  521.80  4413.1  520.59  4446.9  520.18
  4616.0  514.73  4816.1  510.52  4849.9  509.42  4876.0  507.38  4903.1  509.15
  4913.4  508.24  4928.1  509.73  4934.3  508.05  4942.8  509.17  4949.0  508.09
  4963.7  509.20  4969.9  507.71  4978.5  509.02  4984.6  507.34  4993.2  508.14
  4997.3  507.18  4997.6  506.68  5001.3  507.18  5004.2  508.33  5013.7  509.03
  5028.1  507.25  5063.2  509.21  5276.7  509.28  5546.0  511.98  5809.3  517.17
#Mann=3,-1,0
  4114.1    0.05       0  4997.3    0.03       0  5001.3    0.05       0
Bank Sta=4997.3,5001.3
Exp/Cntr=0.3,0.1

Type RM Length L Ch R = 1,111,0,0,0
BEGIN DESCRIPTION:
High Point Creek Trib 1_1 1.0
END DESCRIPTION:
XS GIS Cut Line= 3
      2630706.41      6990212.06      2630405.87      6991063.60
      2631126.02      6992311.03
#Sta/Elev= 30
  4099.7  529.77  4233.6  526.45  4475.8  516.98  4661.4  512.07  4881.0  508.41
  4904.5  505.99  4936.3  506.74  4976.8  505.72  4977.0  505.22  4980.8  505.72
  5096.3  506.95  5191.6  509.26  5213.2  508.75  5448.6  510.29  5695.7  513.48
  5770.3  514.77  5791.8  515.94  5842.6  516.11  5872.3  517.60  5923.5  517.95
  5958.5  519.57  6033.1  520.37  6062.0  522.00  6107.7  522.22  6129.3  523.61
  6178.2  523.88  6200.6  525.25  6246.8  525.57  6268.6  526.78  6443.1  529.29
#Mann=5,-1,0
  4099.7    0.05       0  4881.0    0.12       0  4976.8    0.07       0
  4980.8    0.12       0  5096.3    0.05       0
Bank Sta=4976.8,4980.8
Exp/Cntr=0.3,0.1

Chan Stop Cuts=-1