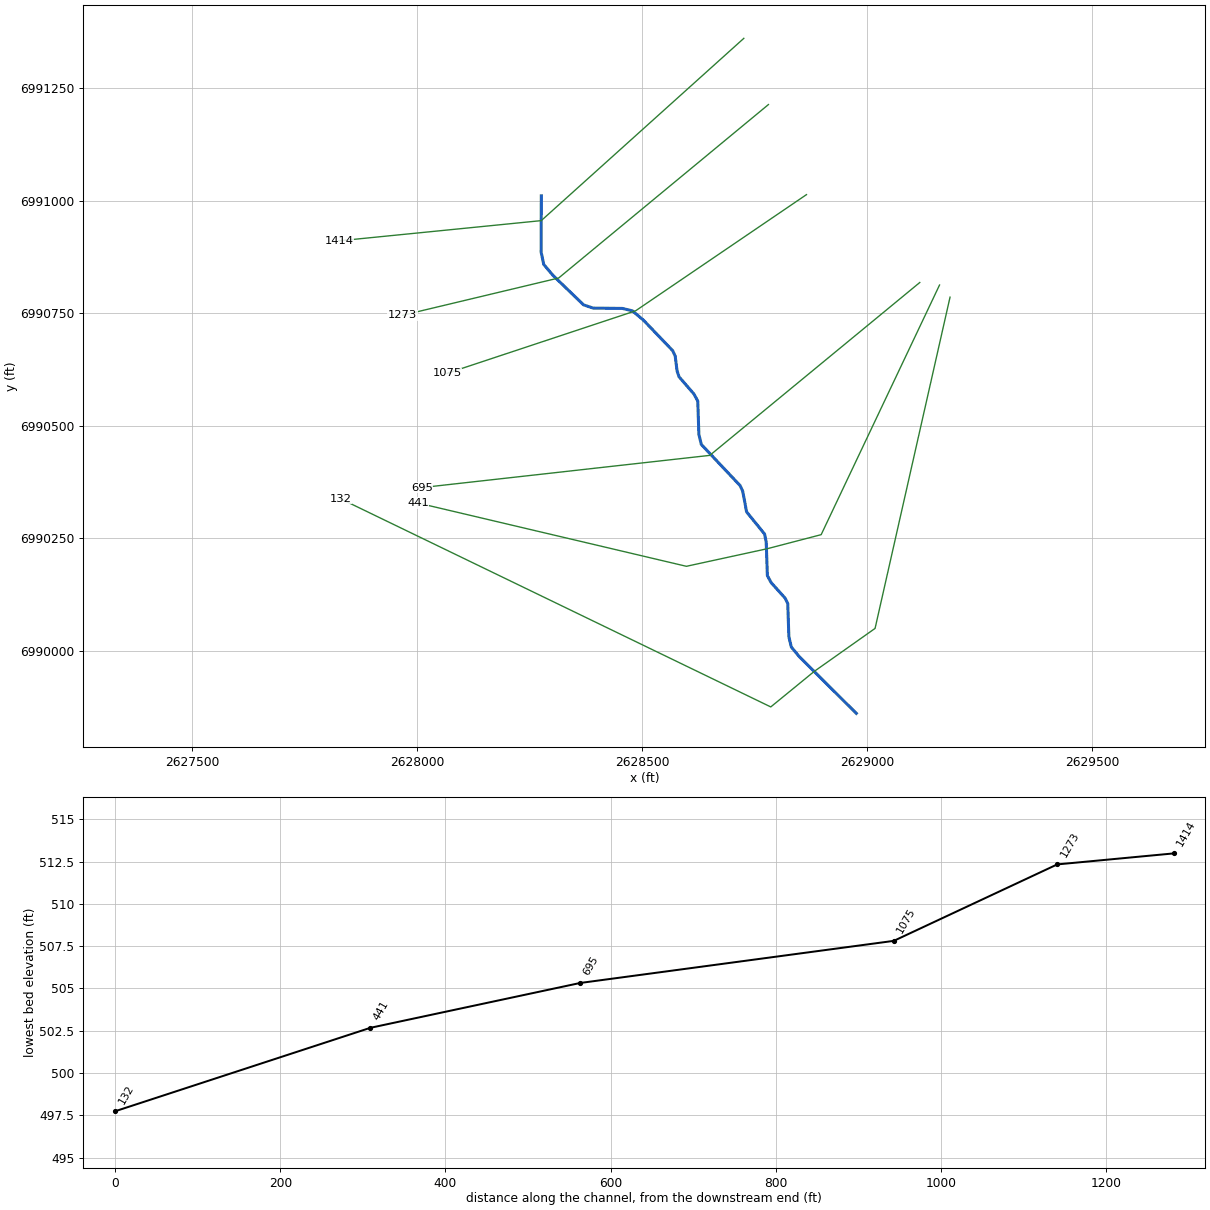
--- High Point Creek Trib 1_2.prj (project) ---

Proj Title=High Point Creek Trib 1_2 Base Level Engineering
Current Plan=p01
Default Exp/Contr=0.3,0.1
English Units
Geom File=g01
Flow File=f01
Plan File=p01
BEGIN DESCRIPTION:
High Point Creek Trib 1_2
END DESCRIPTION:

--- High Point Creek Trib 1_2.p01 (plan) ---

Plan Title=Multiple Run
Short Identifier=Multiple
Geom File=g01
Flow File=f01
Subcritical Flow
K Sum by GR= 0
Std Step Tol= 0.01
Critical Tol= 0.01
Num of Std Step Trials= 20
Max Error Tol= 0.3
Flow Tol Ratio= 0.001
Split Flow NTrial= 30
Split Flow Tol= 0.02
Split Flow Ratio= 0.02
Log Output Level= 0
Friction Slope Method= 1
Unsteady Friction Slope Method= 2
Unsteady Bridges Friction Slope Method= 1
Parabolic Critical Depth
Global Vel Dist=  1 , 1 , 1
Global Log Level= 0
CheckData=True
Encroach Param= -1, 0, 0, 0
BEGIN DESCRIPTION:
Multiple Run
END DESCRIPTION:

--- High Point Creek Trib 1_2.f01 (steady flow) ---

Flow Title=Multiple
Number of Profiles=7
Profile Names=10-year,25-year,50-year,1pct_min,100-year,1pct_plu,500-year
River Rch & RM= High Point Creek,Reach-1,1414
     169     207     236     134     268     534     342
Boundary for River Rch & Prof#=High Point Creek,Reach-1,1
Up Type=0
Dn Type=3
Dn Slope=0.005
Boundary for River Rch & Prof#=High Point Creek,Reach-1,2
Up Type=0
Dn Type=3
Dn Slope=0.005
Boundary for River Rch & Prof#=High Point Creek,Reach-1,3
Up Type=0
Dn Type=3
Dn Slope=0.005
Boundary for River Rch & Prof#=High Point Creek,Reach-1,4
Up Type=0
Dn Type=3
Dn Slope=0.005
Boundary for River Rch & Prof#=High Point Creek,Reach-1,5
Up Type=0
Dn Type=3
Dn Slope=0.005
Boundary for River Rch & Prof#=High Point Creek,Reach-1,6
Up Type=0
Dn Type=3
Dn Slope=0.005
Boundary for River Rch & Prof#=High Point Creek,Reach-1,7
Up Type=0
Dn Type=3
Dn Slope=0.005

--- High Point Creek Trib 1_2.g01 (geometry) ---

Geom Title=Existing Conditions

River Reach=High Point Creek,Reach-1
Reach XY= 30
      2628276.00      6991011.00      2628275.62      6990885.84
      2628281.42      6990858.52      2628302.14      6990834.06
      2628369.81      6990768.85      2628391.21      6990761.52
      2628455.95      6990760.87      2628478.44      6990755.48
      2628502.93      6990734.85      2628567.87      6990667.08
      2628573.51      6990654.98      2628577.72      6990621.71
      2628582.14      6990608.83      2628615.16      6990570.65
      2628623.67      6990555.03      2628626.13      6990481.05
      2628631.54      6990458.58      2628717.84      6990367.05
      2628723.50      6990354.96      2628732.14      6990308.83
      2628772.17      6990259.42      2628775.77      6990240.91
      2628778.35      6990166.97      2628786.89      6990151.37
      2628817.81      6990117.04      2628823.64      6990105.02
      2628826.12      6990031.05      2628831.52      6990008.57
      2628848.87      6989987.47      2628976.00      6989861.00

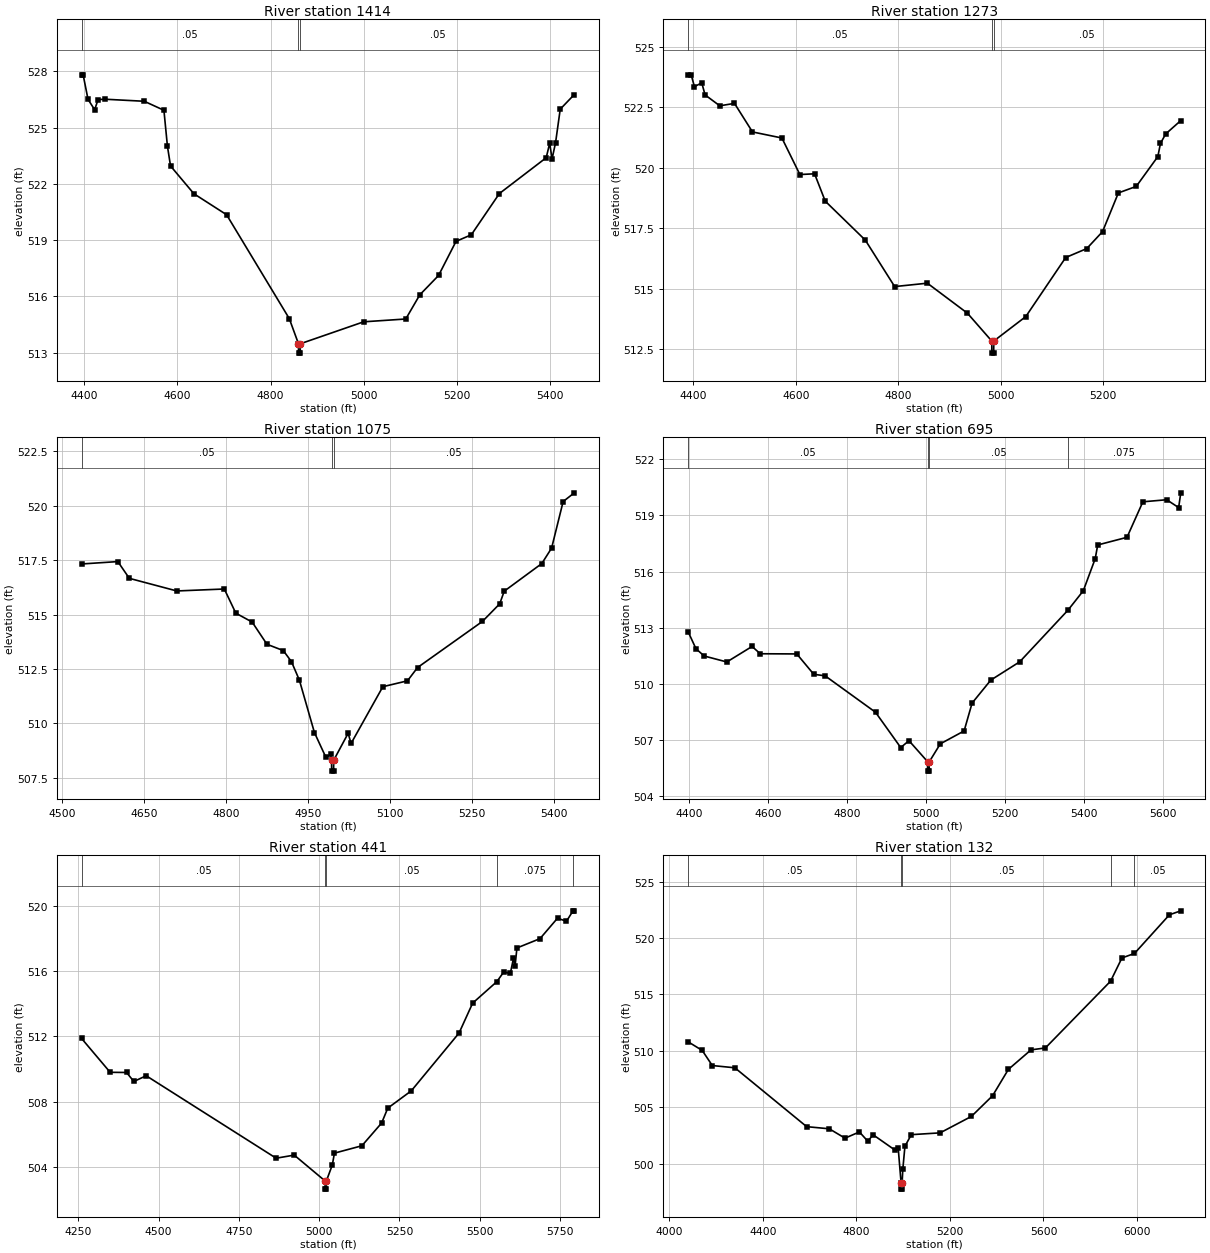
Type RM Length L Ch R = 1,1414,141,141,141
BEGIN DESCRIPTION:
High Point Creek Trib 1_2 2.0
END DESCRIPTION:
XS GIS Cut Line= 3
      2628726.03      6991361.03      2628275.86      6990955.94
      2627826.00      6990911.00
#Sta/Elev= 30
  4394.4  527.82  4397.8  527.82  4408.3  526.51  4422.5  525.96  4429.9  526.50
  4444.1  526.52  4529.0  526.41  4571.2  525.93  4578.7  524.02  4585.4  522.96
  4635.5  521.48  4705.7  520.36  4840.3  514.82  4860.0  513.48  4860.2  512.98
  4863.7  512.98  4864.0  513.48  5000.0  514.65  5090.3  514.80  5120.5  516.09
  5160.7  517.12  5198.2  518.94  5231.0  519.29  5291.3  521.49  5391.8  523.40
  5399.3  524.18  5404.3  523.33  5411.9  524.21  5421.9  525.99  5452.1  526.77
#Mann=3,-1,0
  4394.4    0.05       0  4860.0   0.035       0  4864.0    0.05       0
Bank Sta=4860,4864
Exp/Cntr=0.3,0.1

Type RM Length L Ch R = 1,1273,198,198,198
BEGIN DESCRIPTION:
Mapping XS 9ba68572
END DESCRIPTION:
XS GIS Cut Line= 3
      2628780.73      6991213.89      2628314.55      6990828.45
      2627967.49      6990745.57
#Sta/Elev= 30
  4389.5  523.83  4395.7  523.83  4402.0  523.34  4416.3  523.50  4422.8  523.00
  4451.5  522.55  4480.2  522.65  4515.3  521.47  4572.7  521.22  4607.8  519.71
  4636.5  519.74  4657.3  518.61  4735.5  517.00  4792.8  515.08  4856.6  515.22
  4934.8  513.98  4982.3  512.83  4982.5  512.33  4986.0  512.33  4986.3  512.83
  5048.7  513.84  5126.6  516.28  5167.7  516.65  5198.5  517.35  5229.4  518.95
  5264.3  519.22  5306.4  520.45  5311.6  521.00  5321.9  521.39  5351.2  521.94
#Mann=3,-1,0
  4389.5    0.05       0  4982.3   0.035       0  4986.3    0.05       0
Bank Sta=4982.3,4986.3
Exp/Cntr=0.3,0.1

Type RM Length L Ch R = 1,1075,380,380,380
BEGIN DESCRIPTION:
Mapping XS 869e49b0
END DESCRIPTION:
XS GIS Cut Line= 3
      2628865.23      6991013.74      2628485.46      6990755.50
      2628066.64      6990616.61
#Sta/Elev= 30
  4535.9  517.33  4602.2  517.44  4623.2  516.67  4710.0  516.09  4796.8  516.18
  4817.8  515.07  4847.7  514.66  4874.7  513.64  4904.6  513.35  4919.5  512.84
  4934.0  511.99  4961.5  509.58  4982.5  508.44  4991.4  508.58  4992.7  508.31
  4993.0  507.81  4996.5  507.81  4996.7  508.31  5023.1  509.55  5028.4  509.08
  5086.5  511.69  5131.5  511.96  5149.9  512.57  5268.5  514.69  5300.1  515.50
  5308.3  516.08  5377.0  517.35  5394.9  518.06  5416.0  520.20  5436.4  520.60
#Mann=3,-1,0
  4535.9    0.05       0  4992.7    0.03       0  4996.7    0.05       0
Bank Sta=4992.7,4996.7
Exp/Cntr=0.3,0.1

Type RM Length L Ch R = 1,695,254,254,254
BEGIN DESCRIPTION:
Mapping XS a4d3d110
END DESCRIPTION:
XS GIS Cut Line= 3
      2629116.97      6990818.43      2628650.40      6990434.32
      2628010.63      6990362.75
#Sta/Elev= 30
  4396.9  512.79  4417.0  511.87  4437.8  511.48  4495.2  511.16  4559.1  511.99
  4579.9  511.60  4672.4  511.59  4715.4  510.50  4744.1  510.42  4871.8  508.47
  4935.7  506.58  4956.5  506.95  5004.0  505.82  5004.2  505.32  5007.7  505.32
  5008.0  505.82  5035.9  506.78  5096.2  507.47  5116.4  508.96  5163.8  510.19
  5237.1  511.17  5359.2  513.93  5398.1  514.97  5428.3  516.69  5434.6  517.42
  5508.8  517.83  5549.0  519.73  5609.4  519.84  5639.6  519.42  5645.0  520.21
#Mann=4,-1,0
  4396.9    0.05       0  5004.0   0.035       0  5008.0    0.05       0
  5359.2   0.075       0
Bank Sta=5004,5008
Exp/Cntr=0.3,0.1

Type RM Length L Ch R = 1,441,309,309,309
BEGIN DESCRIPTION:
Mapping XS 60fbfc44
END DESCRIPTION:
XS GIS Cut Line= 5
      2629160.91      6990812.85      2628897.88      6990258.13
      2628778.09      6990226.88      2628598.40      6990187.82
      2628002.06      6990328.44
#Sta/Elev= 30
  4260.3  511.88  4349.4  509.81  4400.4  509.80  4423.1  509.25  4461.6  509.60
  4866.2  504.56  4922.5  504.75  5018.6  503.17  5018.9  502.67  5022.4  502.67
  5022.6  503.17  5041.1  504.15  5047.7  504.87  5133.2  505.32  5194.6  506.71
  5213.8  507.62  5287.1  508.68  5435.7  512.21  5478.1  514.04  5553.3  515.35
  5574.8  515.94  5595.3  515.85  5605.1  516.77  5610.2  516.31  5615.9  517.41
  5687.8  517.98  5742.3  519.23  5770.0  519.04  5790.7  519.68  5794.6  519.68
#Mann=5,-1,0
  4260.3    0.05       0  5018.6    0.03       0  5022.6    0.05       0
  5553.3   0.075       0  5790.7    0.05       0
Bank Sta=5018.6,5022.6
Exp/Cntr=0.3,0.1

Type RM Length L Ch R = 1,132,0,0,0
BEGIN DESCRIPTION:
High Point Creek Trib 1_2 1.0
END DESCRIPTION:
XS GIS Cut Line= 5
      2629184.24      6990785.85      2629017.67      6990049.80
      2628882.48      6989954.26      2628785.90      6989875.32
      2627829.41      6990338.11
#Sta/Elev= 30
  4079.8  510.81  4140.5  510.04  4183.6  508.70  4280.2  508.50  4587.2  503.28
  4684.0  503.09  4751.2  502.26  4812.7  502.81  4848.7  501.99  4871.4  502.56
  4963.7  501.22  4978.5  501.43  4991.3  498.24  4991.5  497.74  4995.0  497.74
  4995.3  498.24  4998.5  499.51  5007.5  501.54  5034.8  502.57  5158.0  502.73
  5291.9  504.19  5382.3  506.02  5450.0  508.36  5546.8  510.09  5608.2  510.26
  5887.0  516.18  5935.6  518.24  5989.2  518.64  6138.8  522.07  6187.3  522.42
#Mann=5,-1,0
  4079.8    0.05       0  4991.3   0.035       0  4995.3    0.05       0
  5887.0   0.075       0  5989.2    0.05       0
Bank Sta=4991.3,4995.3
Exp/Cntr=0.3,0.1

Chan Stop Cuts=-1