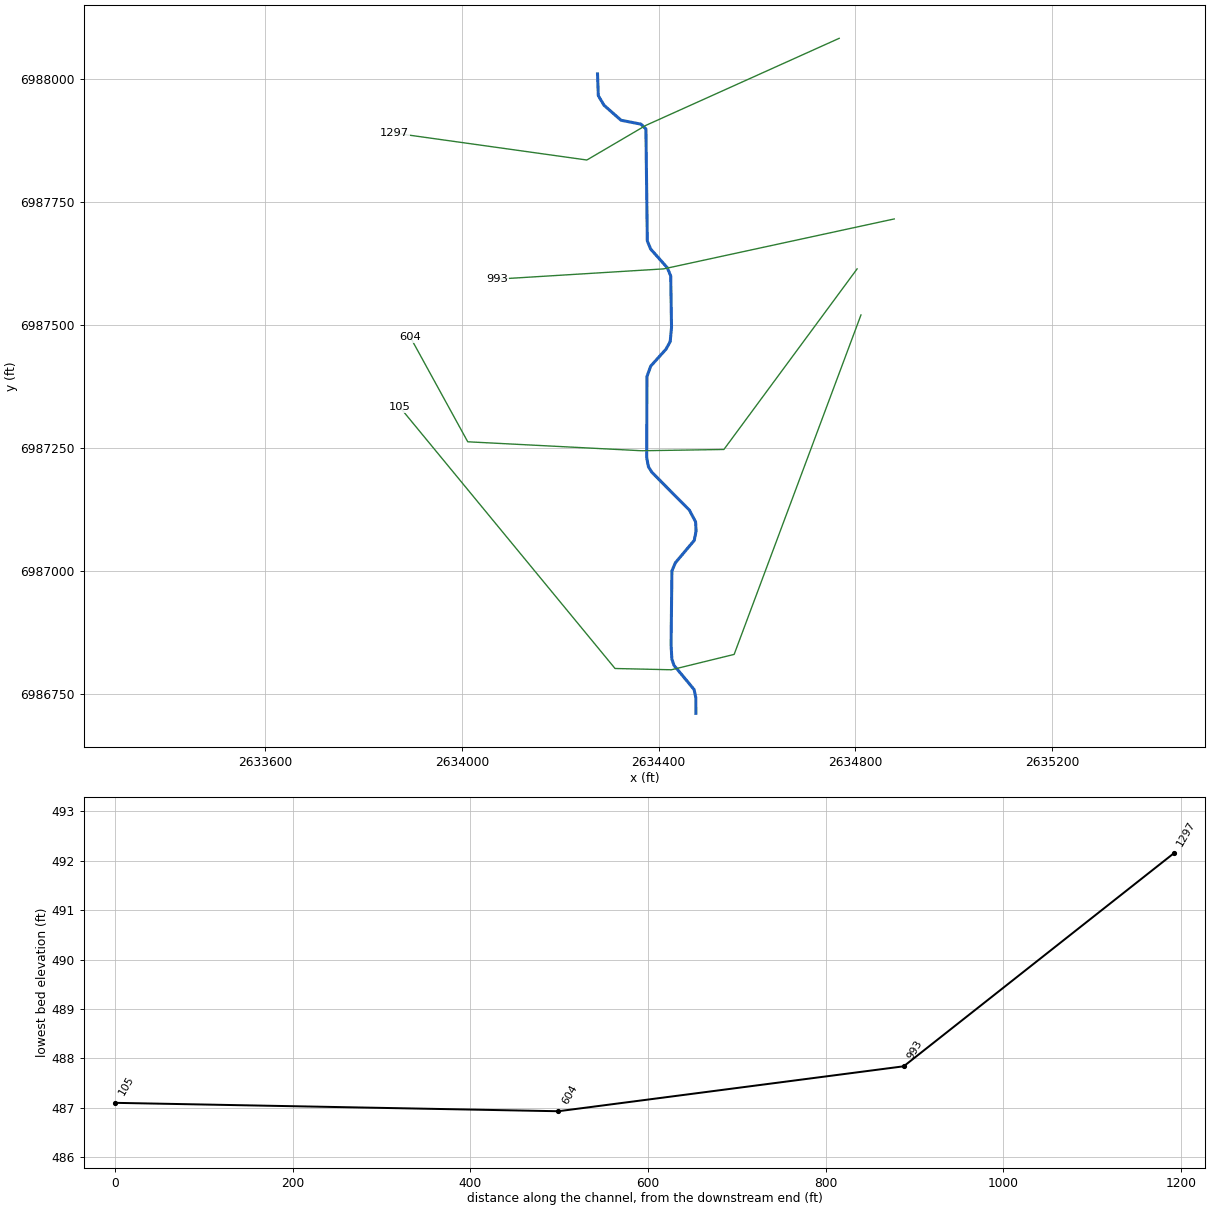
--- High Point Creek Trib 2.prj (project) ---

Proj Title=High Point Creek Trib 2 Base Level Engineering
Current Plan=p01
Default Exp/Contr=0.3,0.1
English Units
Geom File=g01
Flow File=f01
Plan File=p01
BEGIN DESCRIPTION:
High Point Creek Trib 2
END DESCRIPTION:

--- High Point Creek Trib 2.p01 (plan) ---

Plan Title=Multiple Run
Short Identifier=Multiple
Geom File=g01
Flow File=f01
Subcritical Flow
K Sum by GR= 0
Std Step Tol= 0.01
Critical Tol= 0.01
Num of Std Step Trials= 20
Max Error Tol= 0.3
Flow Tol Ratio= 0.001
Split Flow NTrial= 30
Split Flow Tol= 0.02
Split Flow Ratio= 0.02
Log Output Level= 0
Friction Slope Method= 1
Unsteady Friction Slope Method= 2
Unsteady Bridges Friction Slope Method= 1
Parabolic Critical Depth
Global Vel Dist=  1 , 1 , 1
Global Log Level= 0
CheckData=True
Encroach Param= -1, 0, 0, 0
BEGIN DESCRIPTION:
Multiple Run
END DESCRIPTION:

--- High Point Creek Trib 2.f01 (steady flow) ---

Flow Title=Multiple
Number of Profiles=7
Profile Names=10-year,25-year,50-year,1pct_min,100-year,1pct_plu,500-year
River Rch & RM= High Point Creek,Reach-1,1297
      58      65      69      37      74     148      84
Boundary for River Rch & Prof#=High Point Creek,Reach-1,1
Up Type=0
Dn Type=3
Dn Slope=0.005
Boundary for River Rch & Prof#=High Point Creek,Reach-1,2
Up Type=0
Dn Type=3
Dn Slope=0.005
Boundary for River Rch & Prof#=High Point Creek,Reach-1,3
Up Type=0
Dn Type=3
Dn Slope=0.005
Boundary for River Rch & Prof#=High Point Creek,Reach-1,4
Up Type=0
Dn Type=3
Dn Slope=0.005
Boundary for River Rch & Prof#=High Point Creek,Reach-1,5
Up Type=0
Dn Type=3
Dn Slope=0.005
Boundary for River Rch & Prof#=High Point Creek,Reach-1,6
Up Type=0
Dn Type=3
Dn Slope=0.005
Boundary for River Rch & Prof#=High Point Creek,Reach-1,7
Up Type=0
Dn Type=3
Dn Slope=0.005

--- High Point Creek Trib 2.g01 (geometry) ---

Geom Title=Existing Conditions

River Reach=High Point Creek,Reach-1
Reach XY= 30
      2634276.00      6988011.00      2634277.60      6987966.88
      2634289.37      6987947.26      2634323.94      6987916.89
      2634364.32      6987909.05      2634374.38      6987899.19
      2634377.22      6987671.50      2634384.14      6987654.94
      2634417.86      6987617.05      2634424.79      6987600.49
      2634426.47      6987495.84      2634423.75      6987466.94
      2634415.15      6987451.36      2634384.14      6987417.06
      2634376.52      6987395.78      2634375.96      6987230.98
      2634379.55      6987212.47      2634386.50      6987201.21
      2634462.85      6987124.20      2634475.40      6987100.38
      2634476.36      6987081.21      2634472.66      6987062.75
      2634434.19      6987017.08      2634427.24      6987000.50
      2634425.54      6986850.81      2634427.12      6986821.46
      2634431.53      6986808.58      2634472.35      6986759.49
      2634475.88      6986742.80      2634476.00      6986711.00

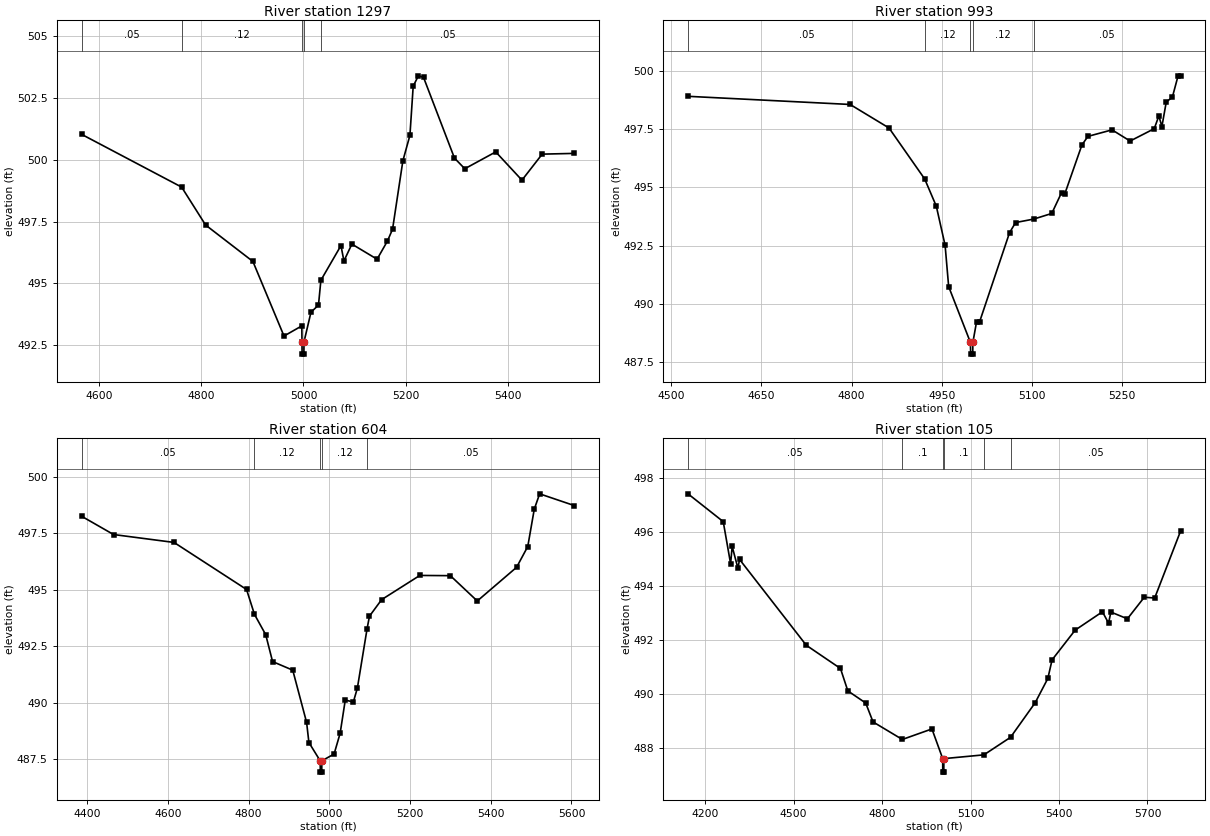
Type RM Length L Ch R = 1,1297,304,304,304
BEGIN DESCRIPTION:
Mapping XS 70725e94
END DESCRIPTION:
XS GIS Cut Line= 4
      2634767.32      6988083.50      2634374.10      6987906.43
      2634254.31      6987836.11      2633863.67      6987890.80
#Sta/Elev= 30
  4565.6  501.02  4761.5  498.89  4808.4  497.36  4901.0  495.89  4961.9  492.88
  4996.8  493.29  4997.1  492.65  4997.3  492.15  5000.8  492.15  5001.1  492.65
  5014.7  493.84  5029.4  494.13  5034.1  495.13  5073.4  496.53  5079.2  495.91
  5094.8  496.59  5144.1  495.98  5164.3  496.71  5174.4  497.19  5194.6  499.95
  5208.4  500.98  5214.8  502.96  5224.9  503.38  5235.0  503.32  5295.6  500.06
  5315.8  499.63  5376.4  500.31  5427.7  499.17  5467.3  500.22  5530.2  500.25
#Mann=5,-1,0
  4565.6    0.05       0  4761.5    0.12       0  4997.1    0.07       0
  5001.1    0.12       0  5034.1    0.05       0
Bank Sta=4997.1,5001.1
Exp/Cntr=0.3,0.1

Type RM Length L Ch R = 1,993,389,389,389
BEGIN DESCRIPTION:
Mapping XS 9cdcb99b
END DESCRIPTION:
XS GIS Cut Line= 3
      2634879.27      6987716.31      2634410.56      6987614.76
      2634071.98      6987593.92
#Sta/Elev= 30
  4528.3  498.91  4797.7  498.56  4862.3  497.55  4921.6  495.36  4940.9  494.19
  4955.5  492.51  4961.4  490.74  4997.6  488.34  4997.9  487.84  5001.4  487.84
  5001.6  488.34  5007.7  489.22  5012.7  489.22  5062.5  493.05  5072.6  493.49
  5102.9  493.64  5132.7  493.88  5149.1  494.78  5154.1  494.70  5182.8  496.82
  5192.8  497.19  5232.9  497.47  5262.9  496.99  5303.0  497.52  5310.7  498.07
  5315.7  497.61  5323.0  498.67  5333.1  498.87  5342.6  499.79  5347.1  499.79
#Mann=5,-1,0
  4528.3    0.05       0  4921.6    0.12       0  4997.6    0.07       0
  5001.6    0.12       0  5102.9    0.05       0
Bank Sta=4997.6,5001.6
Exp/Cntr=0.3,0.1

Type RM Length L Ch R = 1,604,499,499,499
BEGIN DESCRIPTION:
Mapping XS 7e922d81
END DESCRIPTION:
XS GIS Cut Line= 5
      2634803.78      6987614.74      2634532.95      6987247.57
      2634366.29      6987244.97      2634012.12      6987263.20
      2633895.15      6987476.34
#Sta/Elev= 30
  4386.3  498.25  4465.5  497.44  4615.4  497.09  4795.0  495.01  4814.6  493.91
  4842.5  493.01  4859.5  491.82  4909.5  491.44  4943.8  489.13  4949.5  488.24
  4977.5  487.43  4977.8  486.93  4981.3  486.93  4981.5  487.43  5011.9  487.73
  5026.9  488.65  5039.6  490.12  5059.6  490.03  5069.6  490.65  5093.7  493.28
  5099.6  493.83  5129.7  494.56  5224.3  495.63  5299.9  495.62  5366.6  494.50
  5464.0  495.99  5491.7  496.91  5507.8  498.56  5521.1  499.24  5607.0  498.72
#Mann=5,-1,0
  4386.3    0.05       0  4814.6    0.12       0  4977.5    0.07       0
  4981.5    0.12       0  5093.7    0.05       0
Bank Sta=4977.5,4981.5
Exp/Cntr=0.3,0.1

Type RM Length L Ch R = 1,105,0,0,0
BEGIN DESCRIPTION:
Mapping XS bcec6b11
END DESCRIPTION:
XS GIS Cut Line= 5
      2634811.60      6987521.01      2634553.79      6986830.90
      2634426.18      6986799.65      2634311.60      6986802.26
      2633874.09      6987333.52
#Sta/Elev= 30
  4142.0  497.41  4261.4  496.38  4286.4  494.82  4291.7  495.46  4311.3  494.65
  4316.7  494.98  4543.0  491.80  4658.9  490.94  4683.9  490.11  4744.5  489.66
  4769.4  488.96  4868.7  488.31  4969.1  488.70  5005.6  487.60  5005.8  487.10
  5009.3  487.10  5009.6  487.60  5145.3  487.74  5235.6  488.39  5319.1  489.67
  5362.1  490.57  5376.5  491.26  5454.7  492.36  5547.2  493.04  5568.0  492.62
  5575.9  493.03  5631.9  492.78  5689.2  493.58  5724.4  493.55  5812.9  496.05
#Mann=6,-1,0
  4142.0    0.05       0  4868.7     0.1       0  5005.6    0.07       0
  5009.6     0.1       0  5145.3    0.12       0  5235.6    0.05       0
Bank Sta=5005.6,5009.6
Exp/Cntr=0.3,0.1

Chan Stop Cuts=-1