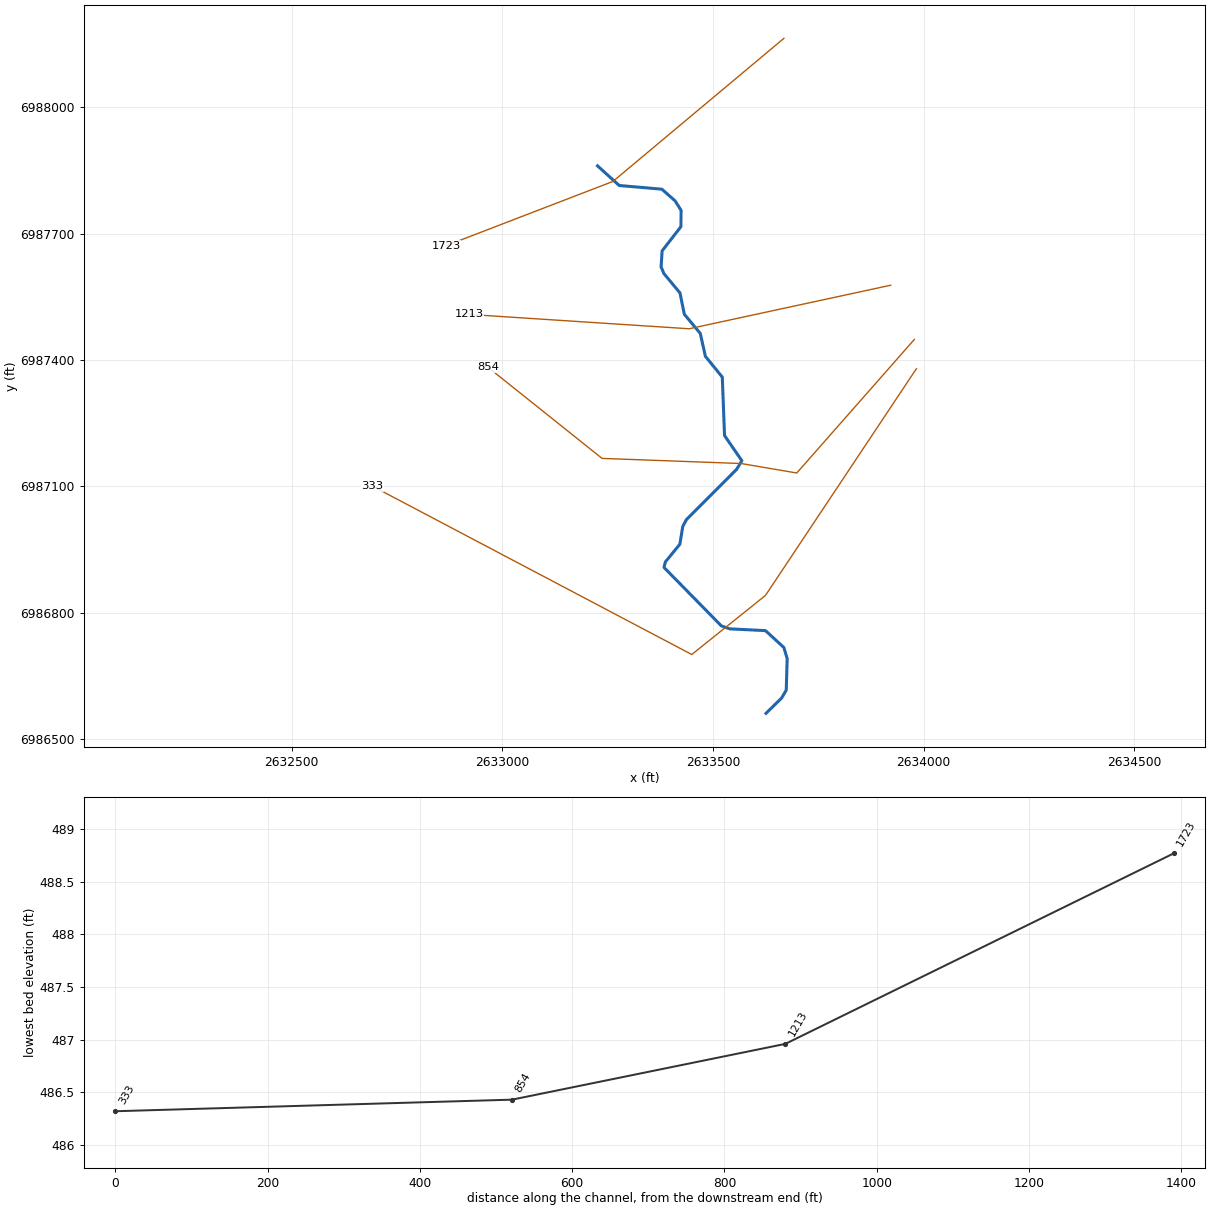
--- High Point Creek Trib 3.prj (project) ---

Proj Title=High Point Creek Trib 3 Base Level Engineering
Current Plan=p01
Default Exp/Contr=0.3,0.1
English Units
Geom File=g01
Flow File=f01
Plan File=p01
BEGIN DESCRIPTION:
High Point Creek Trib 3
END DESCRIPTION:

--- High Point Creek Trib 3.p01 (plan) ---

Plan Title=Multiple Run
Short Identifier=Multiple
Geom File=g01
Flow File=f01
Subcritical Flow
K Sum by GR= 0
Std Step Tol= 0.01
Critical Tol= 0.01
Num of Std Step Trials= 20
Max Error Tol= 0.3
Flow Tol Ratio= 0.001
Split Flow NTrial= 30
Split Flow Tol= 0.02
Split Flow Ratio= 0.02
Log Output Level= 0
Friction Slope Method= 1
Unsteady Friction Slope Method= 2
Unsteady Bridges Friction Slope Method= 1
Parabolic Critical Depth
Global Vel Dist=  1 , 1 , 1
Global Log Level= 0
CheckData=True
Encroach Param= -1, 0, 0, 0
BEGIN DESCRIPTION:
Multiple Run
END DESCRIPTION:

--- High Point Creek Trib 3.f01 (steady flow) ---

Flow Title=Multiple
Number of Profiles=7
Profile Names=10-year,25-year,50-year,1pct_min,100-year,1pct_plu,500-year
River Rch & RM= High Point Creek,Reach-1,1723
     302     385     450     261     521    1040     698
Boundary for River Rch & Prof#=High Point Creek,Reach-1,1
Up Type=0
Dn Type=3
Dn Slope=0.005
Boundary for River Rch & Prof#=High Point Creek,Reach-1,2
Up Type=0
Dn Type=3
Dn Slope=0.005
Boundary for River Rch & Prof#=High Point Creek,Reach-1,3
Up Type=0
Dn Type=3
Dn Slope=0.005
Boundary for River Rch & Prof#=High Point Creek,Reach-1,4
Up Type=0
Dn Type=3
Dn Slope=0.005
Boundary for River Rch & Prof#=High Point Creek,Reach-1,5
Up Type=0
Dn Type=3
Dn Slope=0.005
Boundary for River Rch & Prof#=High Point Creek,Reach-1,6
Up Type=0
Dn Type=3
Dn Slope=0.005
Boundary for River Rch & Prof#=High Point Creek,Reach-1,7
Up Type=0
Dn Type=3
Dn Slope=0.005

--- High Point Creek Trib 3.g01 (geometry) ---

Geom Title=Existing Conditions

River Reach=High Point Creek,Reach-1
Reach XY= 30
      2633226.00      6987861.00      2633277.41      6987814.39
      2633378.76      6987805.60      2633409.97      6987778.13
      2633424.35      6987755.58      2633424.09      6987716.76
      2633379.40      6987659.28      2633376.91      6987620.84
      2633383.77      6987605.06      2633421.78      6987559.28
      2633432.08      6987508.80      2633469.92      6987463.20
      2633482.12      6987408.82      2633522.24      6987359.44
      2633527.57      6987220.59      2633568.68      6987160.90
      2633556.71      6987140.97      2633436.75      6987020.68
      2633428.46      6987004.95      2633421.53      6986962.65
      2633387.27      6986920.87      2633383.77      6986907.59
      2633519.83      6986768.86      2633539.92      6986761.68
      2633624.75      6986757.49      2633668.38      6986717.51
      2633676.28      6986691.09      2633674.13      6986616.43
      2633663.13      6986597.52      2633626.00      6986561.00

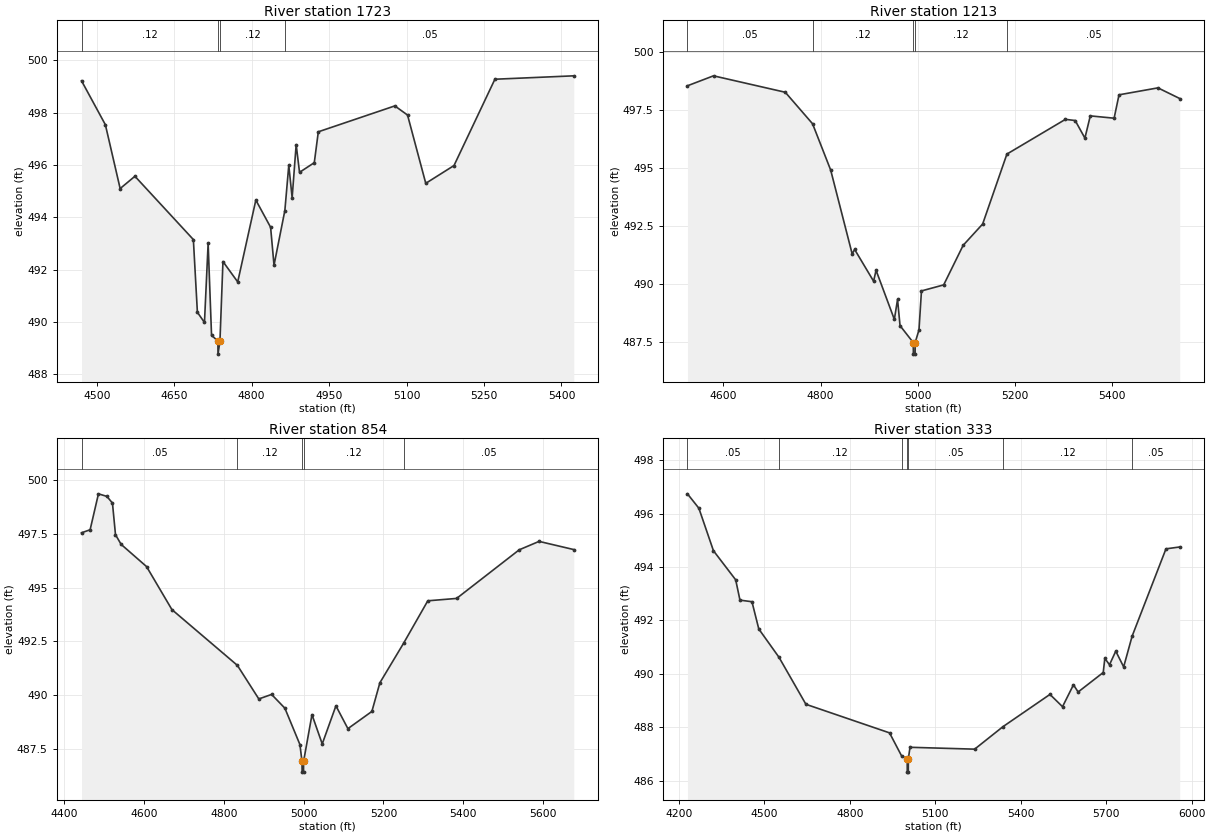
Type RM Length L Ch R = 1,1723,510,510,510
BEGIN DESCRIPTION:
High Point Creek Trib 3 4.0
END DESCRIPTION:
XS GIS Cut Line= 3
      2633668.58      6988163.79      2633262.52      6987823.97
      2632866.91      6987671.71
#Sta/Elev= 30
  4470.5  499.22  4516.7  497.54  4545.3  495.10  4573.9  495.57  4687.1  493.15
  4694.9  490.37  4708.6  489.98  4715.7  493.00  4722.3  489.49  4734.6  489.27
  4734.8  488.77  4738.6  489.27  4744.4  492.31  4773.0  491.53  4808.1  494.66
  4836.7  493.62  4843.3  492.17  4864.3  494.26  4871.9  495.99  4878.4  494.75
  4886.2  496.78  4892.7  495.72  4921.3  496.09  4929.1  497.27  5077.3  498.26
  5101.9  497.91  5137.2  495.30  5191.9  495.98  5271.1  499.28  5423.9  499.41
#Mann=4,-1,0
  4470.5    0.12       0  4734.6    0.03       0  4738.6    0.12       0
  4864.3    0.05       0
Bank Sta=4734.6,4738.6
Exp/Cntr=0.3,0.1

Type RM Length L Ch R = 1,1213,359,359,359
BEGIN DESCRIPTION:
High Point Creek Trib 3 1.0
END DESCRIPTION:
XS GIS Cut Line= 3
      2633922.08      6987577.59      2633443.45      6987474.19
      2632921.33      6987508.23
#Sta/Elev= 30
  4526.2  498.55  4579.8  498.98  4727.5  498.27  4783.6  496.91  4820.9  494.91
  4865.1  491.29  4870.2  491.48  4909.2  490.11  4914.3  490.58  4951.9  488.46
  4958.5  489.32  4963.6  488.19  4990.8  487.46  4991.1  486.96  4994.6  486.96
  4994.8  487.46  5002.6  488.01  5007.7  489.69  5053.4  489.95  5093.5  491.66
  5133.6  492.58  5183.5  495.60  5303.9  497.10  5324.0  497.05  5344.0  496.29
  5355.1  497.25  5404.1  497.15  5414.2  498.16  5494.3  498.46  5539.1  498.00
#Mann=5,-1,0
  4526.2    0.05       0  4783.6    0.12       0  4990.8    0.07       0
  4994.8    0.12       0  5183.5    0.05       0
Bank Sta=4990.8,4994.8
Exp/Cntr=0.3,0.1

Type RM Length L Ch R = 1,854,521,521,521
BEGIN DESCRIPTION:
High Point Creek Trib 3 2.0
END DESCRIPTION:
XS GIS Cut Line= 5
      2633978.17      6987448.77      2633699.12      6987131.74
      2633566.87      6987154.26      2633236.76      6987166.42
      2632965.98      6987382.71
#Sta/Elev= 30
  4443.5  497.55  4465.0  497.69  4485.9  499.36  4507.1  499.24  4521.0  498.93
  4528.6  497.46  4542.8  497.01  4606.4  495.98  4670.0  493.98  4834.0  491.39
  4887.7  489.83  4919.7  490.04  4953.0  489.40  4990.7  487.71  4995.9  486.93
  4996.2  486.43  4999.7  486.43  4999.9  486.93  5020.9  489.10  5046.6  487.74
  5080.9  489.51  5110.9  488.45  5171.0  489.25  5191.0  490.58  5250.5  492.42
  5311.1  494.39  5383.3  494.50  5540.2  496.76  5589.9  497.15  5676.9  496.77
#Mann=5,-1,0
  4443.5    0.05       0  4834.0    0.12       0  4995.9    0.07       0
  4999.9    0.12       0  5250.5    0.05       0
Bank Sta=4995.9,4999.9
Exp/Cntr=0.3,0.1

Type RM Length L Ch R = 1,333,0,0,0
BEGIN DESCRIPTION:
High Point Creek Trib 3 3.0
END DESCRIPTION:
XS GIS Cut Line= 4
      2633983.15      6987379.45      2633624.81      6986841.12
      2633449.78      6986700.76      2632691.82      6987100.38
#Sta/Elev= 30
  4230.3  496.74  4270.4  496.20  4321.5  494.61  4399.6  493.52  4414.6  492.76
  4456.7  492.70  4480.7  491.68  4551.6  490.62  4646.1  488.86  4939.6  487.79
  4982.3  486.92  5001.6  486.82  5001.9  486.32  5005.4  486.32  5005.6  486.82
  5011.5  487.25  5238.4  487.18  5337.5  488.02  5502.7  489.23  5546.8  488.77
  5585.2  489.59  5601.6  489.32  5689.7  490.05  5695.3  490.58  5711.7  490.34
  5733.7  490.85  5761.4  490.26  5791.1  491.41  5909.9  494.68  5958.2  494.75
#Mann=7,-1,0
  4230.3    0.05       0  4551.6    0.12       0  4982.3    0.05       0
  5001.6    0.03       0  5005.6    0.05       0  5337.5    0.12       0
  5791.1    0.05       0
Bank Sta=5001.6,5005.6
Exp/Cntr=0.3,0.1

Chan Stop Cuts=-1