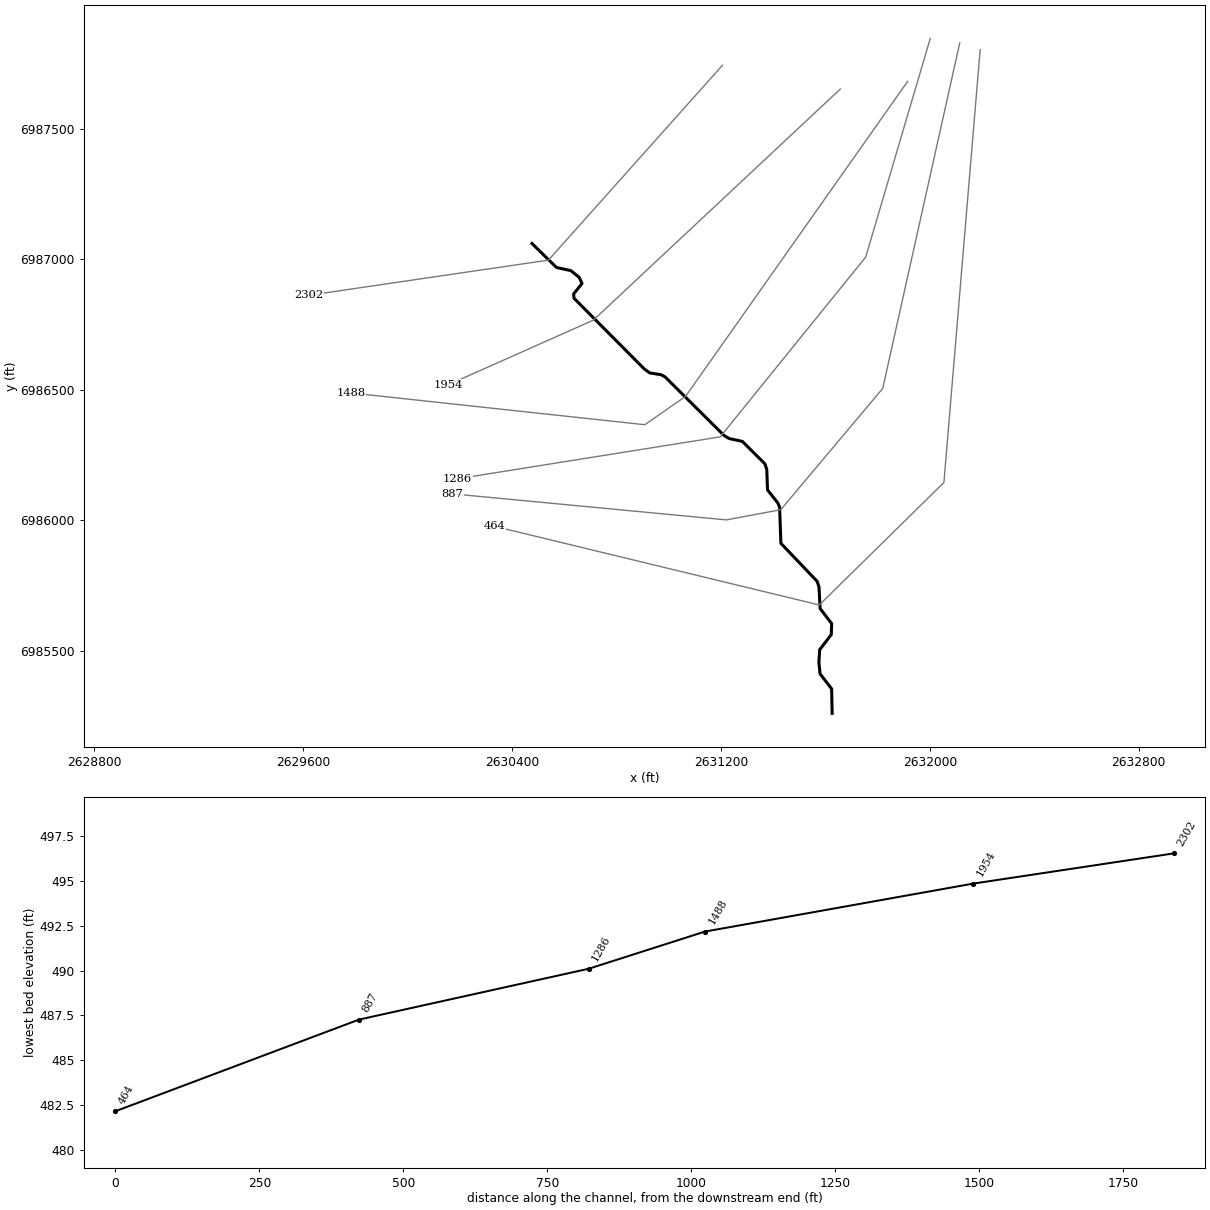
--- High Point Creek Trib 4.prj (project) ---

Proj Title=High Point Creek Trib 4 Base Level Engineering
Current Plan=p01
Default Exp/Contr=0.3,0.1
English Units
Geom File=g01
Flow File=f01
Plan File=p01
BEGIN DESCRIPTION:
High Point Creek Trib 4
END DESCRIPTION:

--- High Point Creek Trib 4.p01 (plan) ---

Plan Title=Multiple Run
Short Identifier=Multiple
Geom File=g01
Flow File=f01
Subcritical Flow
K Sum by GR= 0
Std Step Tol= 0.01
Critical Tol= 0.01
Num of Std Step Trials= 20
Max Error Tol= 0.3
Flow Tol Ratio= 0.001
Split Flow NTrial= 30
Split Flow Tol= 0.02
Split Flow Ratio= 0.02
Log Output Level= 0
Friction Slope Method= 1
Unsteady Friction Slope Method= 2
Unsteady Bridges Friction Slope Method= 1
Parabolic Critical Depth
Global Vel Dist=  1 , 1 , 1
Global Log Level= 0
CheckData=True
Encroach Param= -1, 0, 0, 0
BEGIN DESCRIPTION:
Multiple Run
END DESCRIPTION:

--- High Point Creek Trib 4.f01 (steady flow) ---

Flow Title=Multiple
Number of Profiles=7
Profile Names=10-year,25-year,50-year,1pct_min,100-year,1pct_plu,500-year
River Rch & RM= High Point Creek,Reach-1,2302
     190     236     270     154     307     612     396
Boundary for River Rch & Prof#=High Point Creek,Reach-1,1
Up Type=0
Dn Type=3
Dn Slope=0.005
Boundary for River Rch & Prof#=High Point Creek,Reach-1,2
Up Type=0
Dn Type=3
Dn Slope=0.005
Boundary for River Rch & Prof#=High Point Creek,Reach-1,3
Up Type=0
Dn Type=3
Dn Slope=0.005
Boundary for River Rch & Prof#=High Point Creek,Reach-1,4
Up Type=0
Dn Type=3
Dn Slope=0.005
Boundary for River Rch & Prof#=High Point Creek,Reach-1,5
Up Type=0
Dn Type=3
Dn Slope=0.005
Boundary for River Rch & Prof#=High Point Creek,Reach-1,6
Up Type=0
Dn Type=3
Dn Slope=0.005
Boundary for River Rch & Prof#=High Point Creek,Reach-1,7
Up Type=0
Dn Type=3
Dn Slope=0.005

--- High Point Creek Trib 4.g01 (geometry) ---

Geom Title=Existing Conditions

River Reach=High Point Creek,Reach-1
Reach XY= 30
      2630476.00      6987061.00      2630569.97      6986969.11
      2630624.83      6986957.04      2630656.79      6986931.39
      2630667.92      6986907.85      2630635.62      6986867.68
      2630637.25      6986851.01      2630905.91      6986580.79
      2630927.65      6986564.98      2630969.95      6986558.47
      2630985.68      6986550.22      2631212.79      6986324.63
      2631232.05      6986313.54      2631282.07      6986302.85
      2631368.15      6986217.19      2631375.48      6986195.79
      2631378.36      6986116.98      2631417.86      6986067.06
      2631424.77      6986050.49      2631429.54      6985912.47
      2631568.14      6985767.17      2631575.48      6985745.78
      2631579.89      6985662.59      2631624.18      6985604.88
      2631622.62      6985562.73      2631578.19      6985505.03
      2631575.19      6985455.97      2631579.67      6985412.58
      2631623.89      6985355.13      2631626.00      6985261.00

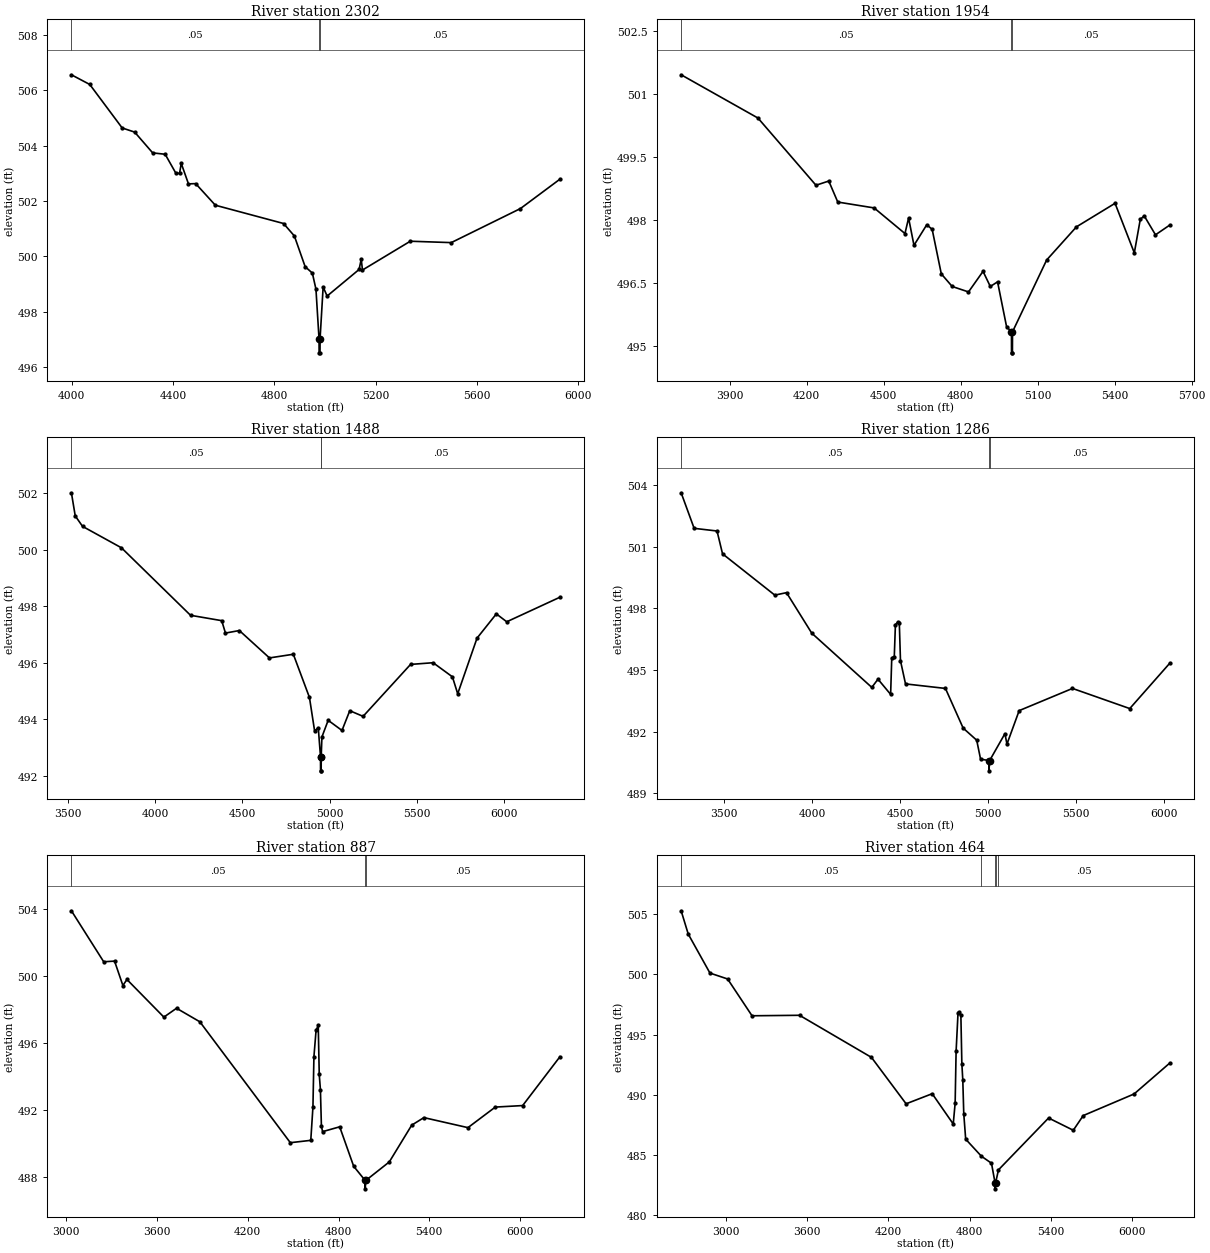
Type RM Length L Ch R = 1,2302,348,348,348
BEGIN DESCRIPTION:
High Point Creek Trib 4 4.0
END DESCRIPTION:
XS GIS Cut Line= 3
      2631205.93      6987743.83      2630539.16      6986997.22
      2629621.66      6986862.72
#Sta/Elev= 30
  3999.0  506.56  4071.5  506.21  4199.4  504.64  4248.7  504.49  4319.8  503.74
  4369.1  503.69  4411.7  503.00  4425.9  503.00  4432.6  503.36  4461.1  502.62
  4489.5  502.63  4567.2  501.85  4836.4  501.19  4879.1  500.74  4921.7  499.63
  4950.1  499.40  4964.3  498.82  4976.5  497.02  4976.8  496.52  4980.3  496.52
  4980.5  497.02  4992.7  498.90  5008.3  498.57  5134.6  499.53  5143.0  499.90
  5148.0  499.51  5336.7  500.55  5498.4  500.50  5771.6  501.73  5927.3  502.79
#Mann=3,-1,0
  3999.0    0.05       0  4976.5    0.03       0  4980.5    0.05       0
Bank Sta=4976.5,4980.5
Exp/Cntr=0.3,0.1

Type RM Length L Ch R = 1,1954,466,466,466
BEGIN DESCRIPTION:
Mapping XS 83cb8acd
END DESCRIPTION:
XS GIS Cut Line= 3
      2631657.31      6987652.67      2630711.12      6986767.24
      2630155.58      6986519.86
#Sta/Elev= 30
  3710.2  501.46  4009.6  500.43  4235.7  498.83  4285.6  498.93  4320.7  498.43
  4462.4  498.29  4582.6  497.68  4596.7  498.05  4617.7  497.40  4667.6  497.89
  4688.6  497.78  4724.2  496.72  4766.6  496.42  4830.2  496.29  4886.9  496.78
  4915.2  496.42  4943.5  496.53  4978.7  495.46  4997.7  495.34  4997.9  494.84
  5001.4  494.84  5001.7  495.34  5134.8  497.05  5251.0  497.84  5401.4  498.40
  5476.5  497.22  5499.8  498.02  5515.2  498.10  5559.0  497.65  5614.2  497.88
#Mann=3,-1,0
  3710.2    0.05       0  4997.7    0.03       0  5001.7    0.05       0
Bank Sta=4997.7,5001.7
Exp/Cntr=0.3,0.1

Type RM Length L Ch R = 1,1488,202,202,202
BEGIN DESCRIPTION:
Mapping XS b59d3ba4
END DESCRIPTION:
XS GIS Cut Line= 4
      2631915.19      6987681.90      2631064.46      6986475.26
      2630908.21      6986366.75      2629784.08      6986488.28
#Sta/Elev= 30
  3521.7  502.02  3543.7  501.20  3585.6  500.83  3808.5  500.07  4203.8  497.68
  4382.4  497.49  4403.8  497.05  4483.4  497.14  4655.8  496.17  4792.5  496.30
  4884.8  494.77  4914.4  493.58  4935.3  493.70  4948.1  492.67  4948.4  492.17
  4951.9  492.17  4952.1  492.67  4956.2  493.37  4992.0  493.96  5071.1  493.60
  5115.7  494.30  5191.9  494.10  5463.8  495.94  5592.9  496.00  5703.5  495.50
  5733.7  494.90  5844.3  496.87  5955.0  497.73  6014.5  497.45  6319.0  498.32
#Mann=3,-1,0
  3521.7    0.05       0  4948.1    0.03       0  4952.1    0.05       0
Bank Sta=4948.1,4952.1
Exp/Cntr=0.3,0.1

Type RM Length L Ch R = 1,1286,399,399,399
BEGIN DESCRIPTION:
Mapping XS 4088b89a
END DESCRIPTION:
XS GIS Cut Line= 4
      2632001.97      6987846.82      2631754.57      6987009.11
      2631197.23      6986320.20      2630190.66      6986159.66
#Sta/Elev= 30
  3254.1  503.63  3328.0  501.90  3458.3  501.77  3489.6  500.66  3786.9  498.65
  3853.5  498.77  3997.1  496.80  4338.7  494.16  4373.9  494.56  4445.8  493.82
  4452.2  495.59  4466.6  495.66  4473.0  497.21  4487.4  497.35  4495.3  497.27
  4501.8  495.46  4530.5  494.33  4757.6  494.11  4858.3  492.18  4935.5  491.59
  4957.4  490.67  5005.0  490.60  5005.2  490.10  5009.0  490.60  5096.0  491.91
  5107.5  491.40  5177.0  493.03  5480.3  494.11  5806.1  493.13  6033.0  495.33
#Mann=3,-1,0
  3254.1    0.05       0  5005.0    0.03       0  5009.0    0.05       0
Bank Sta=5005,5009
Exp/Cntr=0.3,0.1

Type RM Length L Ch R = 1,887,423,423,423
BEGIN DESCRIPTION:
Mapping XS c8821771
END DESCRIPTION:
XS GIS Cut Line= 5
      2632114.81      6987829.42      2631819.67      6986505.64
      2631429.05      6986041.23      2631220.71      6986002.17
      2630170.73      6986101.96
#Sta/Elev= 30
  3033.7  503.90  3247.2  500.85  3319.0  500.89  3374.1  499.43  3400.9  499.79
  3645.1  497.54  3728.8  498.07  3883.0  497.26  4481.1  490.03  4616.3  490.17
  4630.6  492.16  4637.1  495.17  4651.4  496.76  4665.7  497.04  4672.3  494.11
  4680.0  493.21  4686.6  491.03  4694.3  490.69  4807.5  490.98  4899.9  488.62
  4975.9  487.77  4976.1  487.27  4979.9  487.77  5135.5  488.88  5283.8  491.08
  5364.2  491.53  5655.5  490.93  5836.3  492.16  6017.1  492.25  6263.5  495.17
#Mann=3,-1,0
  3033.7    0.05       0  4975.9    0.03       0  4979.9    0.05       0
Bank Sta=4975.9,4979.9
Exp/Cntr=0.3,0.1

Type RM Length L Ch R = 1,464,0,0,0
BEGIN DESCRIPTION:
High Point Creek Trib 4 2.0
END DESCRIPTION:
XS GIS Cut Line= 4
      2632192.94      6987803.39      2632054.05      6986145.40
      2631576.68      6985676.27      2630333.51      6985977.31
#Sta/Elev= 30
  2666.9  505.29  2719.5  503.35  2880.0  500.11  3010.5  499.62  3191.1  496.56
  3542.4  496.60  4074.2  493.10  4330.4  489.24  4523.4  490.08  4678.9  487.56
  4693.0  489.29  4700.1  493.61  4714.3  496.80  4721.3  496.86  4735.4  496.59
  4742.6  492.58  4749.6  491.21  4756.7  488.42  4770.9  486.30  4887.3  484.88
  4961.7  484.30  4988.0  482.67  4988.3  482.17  4992.0  482.67  5013.5  483.75
  5383.9  488.06  5566.6  487.04  5640.0  488.26  6016.4  490.06  6279.1  492.62
#Mann=5,-1,0
  2666.9    0.05       0  4887.3    0.12       0  4988.0    0.07       0
  4992.0    0.12       0  5013.5    0.05       0
Bank Sta=4988,4992
Exp/Cntr=0.3,0.1

Chan Stop Cuts=-1