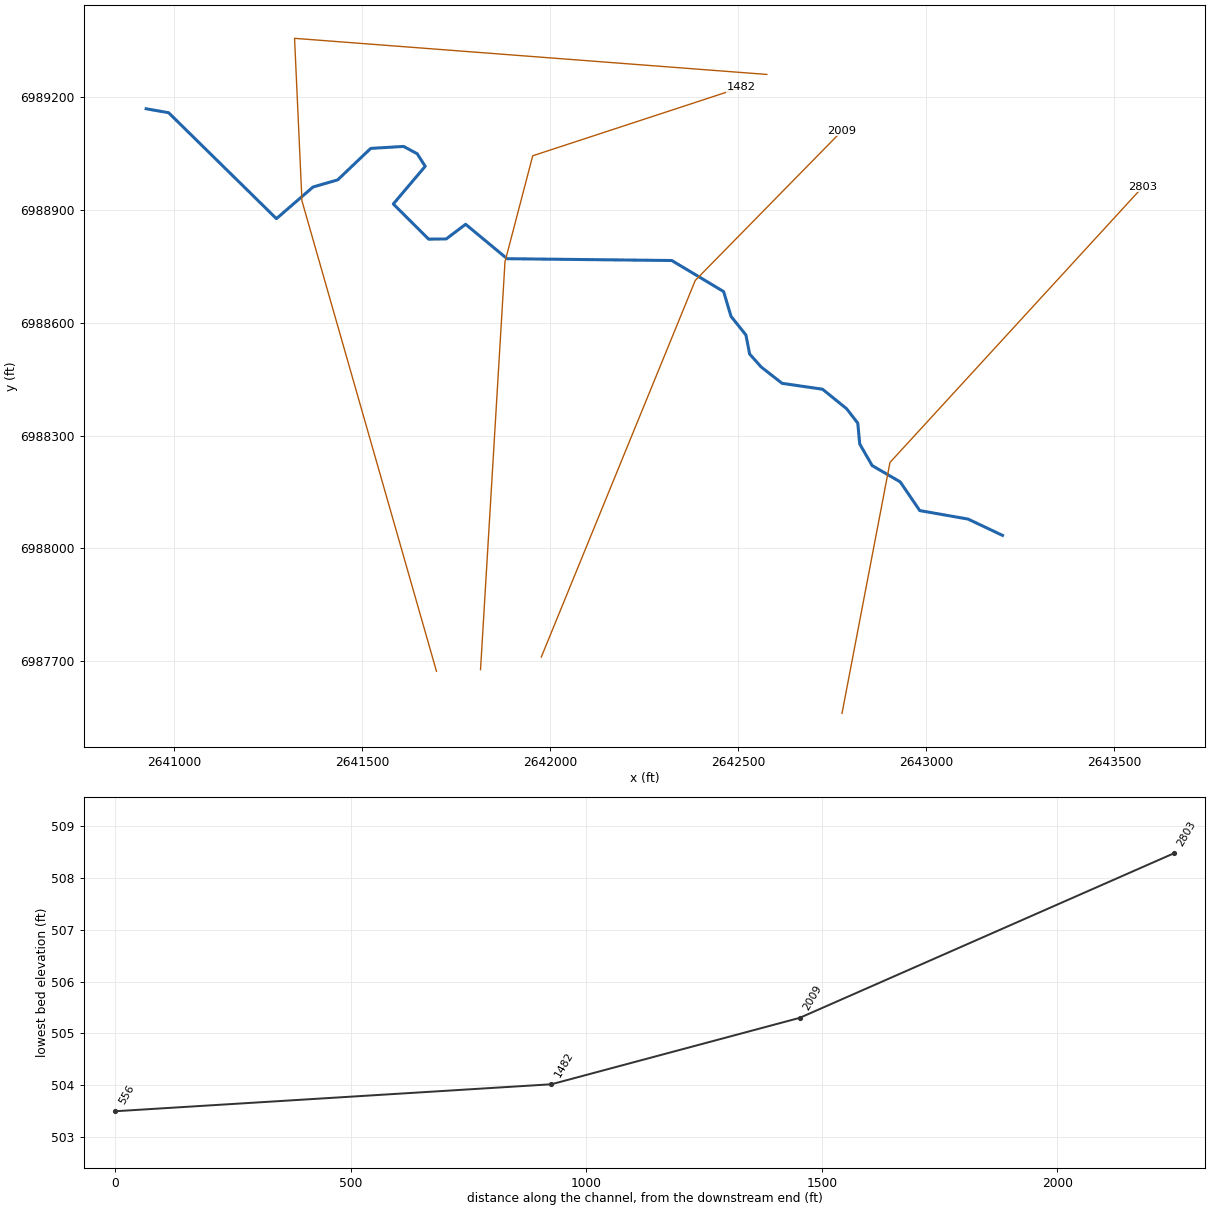
--- High Point Creek Trib 5.prj (project) ---

Proj Title=High Point Creek Trib 5 Base Level Engineering
Current Plan=p01
Default Exp/Contr=0.3,0.1
English Units
Geom File=g01
Flow File=f01
Plan File=p01
BEGIN DESCRIPTION:
High Point Creek Trib 5
END DESCRIPTION:

--- High Point Creek Trib 5.p01 (plan) ---

Plan Title=Multiple Run
Short Identifier=Multiple
Geom File=g01
Flow File=f01
Subcritical Flow
K Sum by GR= 0
Std Step Tol= 0.01
Critical Tol= 0.01
Num of Std Step Trials= 20
Max Error Tol= 0.3
Flow Tol Ratio= 0.001
Split Flow NTrial= 30
Split Flow Tol= 0.02
Split Flow Ratio= 0.02
Log Output Level= 0
Friction Slope Method= 1
Unsteady Friction Slope Method= 2
Unsteady Bridges Friction Slope Method= 1
Parabolic Critical Depth
Global Vel Dist=  1 , 1 , 1
Global Log Level= 0
CheckData=True
Encroach Param= -1, 0, 0, 0
BEGIN DESCRIPTION:
Multiple Run
END DESCRIPTION:

--- High Point Creek Trib 5.f01 (steady flow) ---

Flow Title=Multiple
Number of Profiles=7
Profile Names=10-year,25-year,50-year,1pct_min,100-year,1pct_plu,500-year
River Rch & RM= High Point Creek,Reach-1,2803
     335     432     508     298     594    1185     808
Boundary for River Rch & Prof#=High Point Creek,Reach-1,1
Up Type=0
Dn Type=3
Dn Slope=0.005
Boundary for River Rch & Prof#=High Point Creek,Reach-1,2
Up Type=0
Dn Type=3
Dn Slope=0.005
Boundary for River Rch & Prof#=High Point Creek,Reach-1,3
Up Type=0
Dn Type=3
Dn Slope=0.005
Boundary for River Rch & Prof#=High Point Creek,Reach-1,4
Up Type=0
Dn Type=3
Dn Slope=0.005
Boundary for River Rch & Prof#=High Point Creek,Reach-1,5
Up Type=0
Dn Type=3
Dn Slope=0.005
Boundary for River Rch & Prof#=High Point Creek,Reach-1,6
Up Type=0
Dn Type=3
Dn Slope=0.005
Boundary for River Rch & Prof#=High Point Creek,Reach-1,7
Up Type=0
Dn Type=3
Dn Slope=0.005

--- High Point Creek Trib 5.g01 (geometry) ---

Geom Title=Existing Conditions

River Reach=High Point Creek,Reach-1
Reach XY= 30
      2643203.13      6988034.60      2643111.42      6988078.01
      2642982.94      6988100.58      2642930.86      6988176.97
      2642856.21      6988220.38      2642823.22      6988277.67
      2642818.01      6988333.22      2642788.50      6988371.42
      2642724.26      6988423.50      2642616.63      6988439.13
      2642561.00      6988482.65      2642530.29      6988517.07
      2642520.36      6988567.92      2642480.67      6988617.53
      2642461.09      6988683.26      2642323.01      6988765.94
      2641885.00      6988770.75      2641774.64      6988862.33
      2641722.91      6988823.28      2641676.18      6988822.85
      2641582.16      6988916.34      2641667.03      6989016.57
      2641645.70      6989050.11      2641609.63      6989069.45
      2641522.15      6989064.28      2641434.23      6988980.49
      2641368.51      6988961.49      2641271.22      6988877.29
      2640984.35      6989159.18      2640924.56      6989169.69

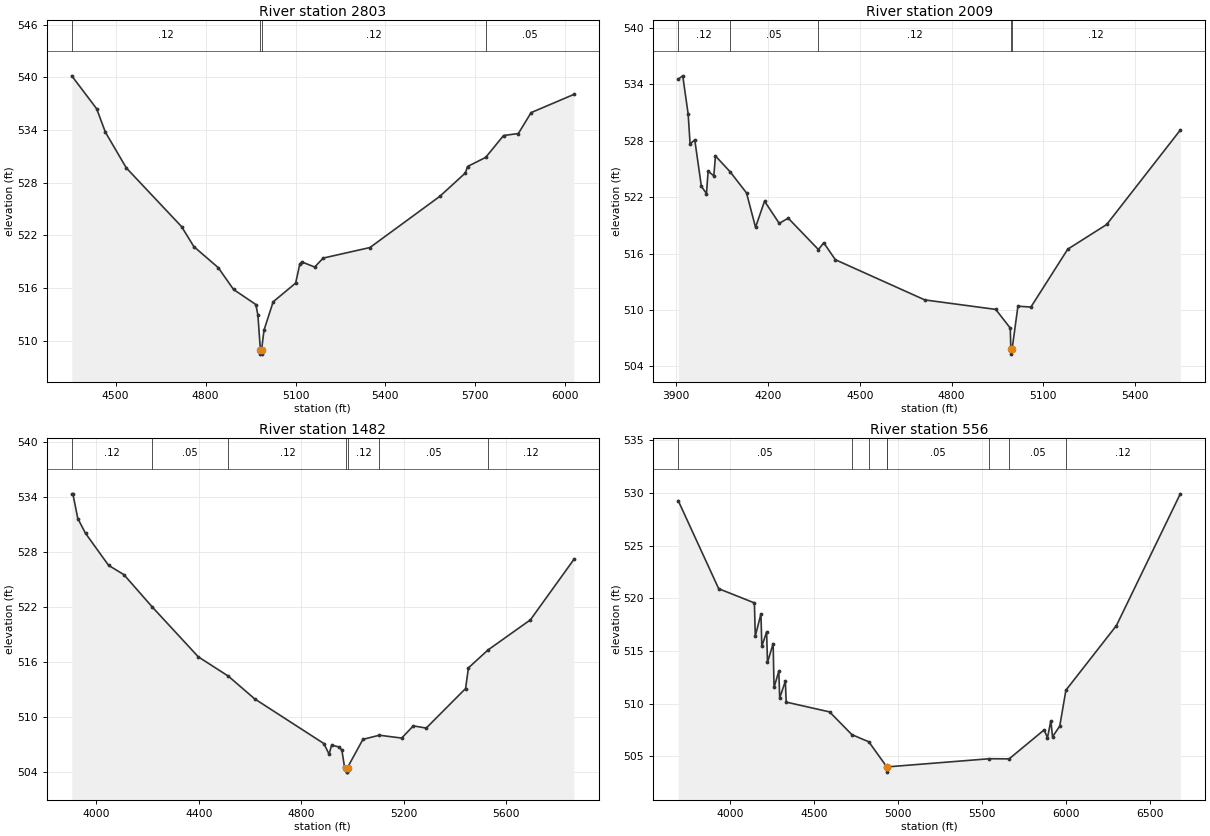
Type RM Length L Ch R = 1,2803,794,794,794
BEGIN DESCRIPTION:
High Point Creek Trib 5 4.0
END DESCRIPTION:
XS GIS Cut Line= 3
      2642776.01      6987561.03      2642903.65      6988228.61
      2643576.41      6988962.14
#Sta/Elev= 30
  4353.6  540.17  4436.8  536.41  4465.6  533.76  4535.8  529.67  4720.1  522.99
  4760.8  520.72  4842.3  518.32  4893.2  515.84  4967.7  514.12  4974.6  512.91
  4982.8  508.97  4983.1  508.47  4986.6  508.47  4986.8  508.97  4995.0  511.21
  5025.5  514.43  5100.5  516.56  5114.6  518.77  5121.4  518.97  5164.0  518.39
  5192.3  519.41  5348.3  520.61  5581.4  526.44  5666.5  529.10  5673.9  529.84
  5734.5  530.88  5794.1  533.37  5843.5  533.60  5886.0  535.98  6028.6  538.05
#Mann=4,-1,0
  4353.6    0.12       0  4982.8    0.07       0  4986.8    0.12       0
  5734.5    0.05       0
Bank Sta=4982.8,4986.8
Exp/Cntr=0.3,0.1

Type RM Length L Ch R = 1,2009,527,527,527
BEGIN DESCRIPTION:
High Point Creek Trib 5 3.0
END DESCRIPTION:
XS GIS Cut Line= 3
      2641976.00      6987711.01      2642385.64      6988712.99
      2642776.02      6989111.02
#Sta/Elev= 30
  3907.1  534.57  3921.8  534.92  3939.5  530.86  3945.8  527.67  3961.1  528.10
  3982.7  523.16  3999.3  522.39  4004.7  524.77  4023.3  524.28  4028.7  526.39
  4076.6  524.71  4130.1  522.46  4159.6  518.80  4189.0  521.58  4237.0  519.22
  4266.4  519.77  4365.0  516.43  4382.4  517.15  4420.3  515.35  4712.5  511.07
  4944.2  510.06  4991.7  508.07  4993.5  505.80  4993.8  505.30  4997.5  505.80
  5016.7  510.40  5059.1  510.31  5179.4  516.47  5306.7  519.10  5547.1  529.15
#Mann=5,-1,0
  3907.1    0.12       0  4076.6    0.05       0  4365.0    0.12       0
  4993.5    0.07       0  4997.5    0.12       0
Bank Sta=4993.5,4997.5
Exp/Cntr=0.3,0.1

Type RM Length L Ch R = 1,1482,926,926,926
BEGIN DESCRIPTION:
Mapping XS 093e4e52
END DESCRIPTION:
XS GIS Cut Line= 4
      2641814.25      6987677.43      2641879.35      6988762.47
      2641953.13      6989044.58      2642507.37      6989226.44
#Sta/Elev= 30
  3903.7  534.34  3908.0  534.34  3927.3  531.65  3957.4  530.04  4047.5  526.55
  4107.6  525.53  4218.0  522.02  4398.2  516.58  4515.4  514.48  4618.5  512.00
  4889.0  507.13  4909.1  505.97  4919.1  506.97  4949.1  506.75  4959.2  506.40
  4969.2  504.63  4977.2  504.52  4977.4  504.02  4980.9  504.02  4981.2  504.52
  5041.4  507.59  5105.5  508.04  5192.8  507.73  5238.4  509.06  5288.7  508.82
  5442.6  513.13  5453.7  515.38  5530.2  517.33  5695.8  520.61  5865.6  527.19
#Mann=7,-1,0
  3903.7    0.12       0  4218.0    0.05       0  4515.4    0.12       0
  4977.2    0.07       0  4981.2    0.12       0  5105.5    0.05       0
  5530.2    0.12       0
Bank Sta=4977.2,4981.2
Exp/Cntr=0.3,0.1

Type RM Length L Ch R = 1,556,0,0,0
BEGIN DESCRIPTION:
High Point Creek Trib 5 2.0
END DESCRIPTION:
XS GIS Cut Line= 4
      2641697.07      6987673.02      2641339.19      6988924.44
      2641319.45      6989357.08      2642576.01      6989261.00
#Sta/Elev= 30
  3688.7  529.28  3930.0  520.92  4143.1  519.57  4148.3  516.42  4182.1  518.53
  4187.3  515.46  4215.9  516.81  4221.1  513.92  4254.9  515.71  4260.1  511.54
  4288.7  513.09  4293.9  510.54  4327.6  512.14  4332.8  510.15  4591.5  509.22
  4724.5  507.06  4825.5  506.38  4932.7  504.00  4933.0  503.50  4936.7  504.00
  5543.4  504.77  5662.6  504.76  5871.2  507.51  5891.3  506.77  5911.3  508.37
  5921.4  506.86  5964.4  507.87  6001.2  511.28  6302.5  517.42  6683.6  529.93
#Mann=8,-1,0
  3688.7    0.05       0  4724.5     0.1       0  4825.5    0.05       0
  4932.7    0.03       0  4936.7    0.05       0  5543.4     0.1       0
  5662.6    0.05       0  6001.2    0.12       0
Bank Sta=4932.7,4936.7
Exp/Cntr=0.3,0.1

Chan Stop Cuts=-1