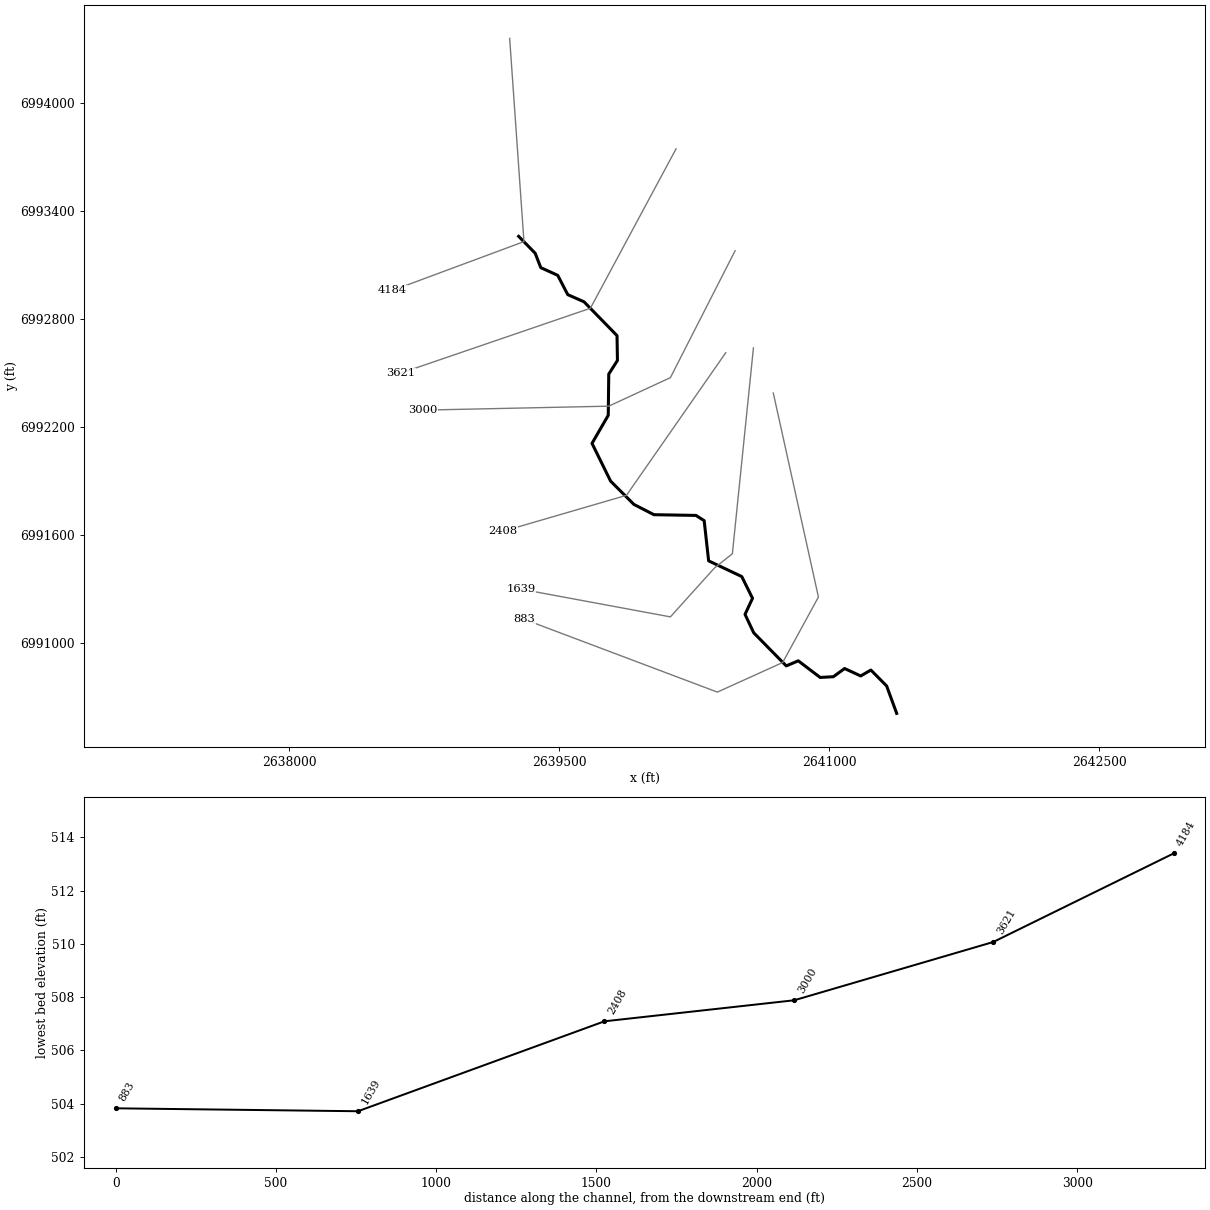
--- High Point Creek Trib 7.prj (project) ---

Proj Title=High Point Creek Trib 7 Base Level Engineering
Current Plan=p01
Default Exp/Contr=0.3,0.1
English Units
Geom File=g01
Flow File=f01
Plan File=p01
BEGIN DESCRIPTION:
High Point Creek Trib 7
END DESCRIPTION:

--- High Point Creek Trib 7.p01 (plan) ---

Plan Title=Multiple Run
Short Identifier=Multiple
Geom File=g01
Flow File=f01
Subcritical Flow
K Sum by GR= 0
Std Step Tol= 0.01
Critical Tol= 0.01
Num of Std Step Trials= 20
Max Error Tol= 0.3
Flow Tol Ratio= 0.001
Split Flow NTrial= 30
Split Flow Tol= 0.02
Split Flow Ratio= 0.02
Log Output Level= 0
Friction Slope Method= 1
Unsteady Friction Slope Method= 2
Unsteady Bridges Friction Slope Method= 1
Parabolic Critical Depth
Global Vel Dist=  1 , 1 , 1
Global Log Level= 0
CheckData=True
Encroach Param= -1, 0, 0, 0
BEGIN DESCRIPTION:
Multiple Run
END DESCRIPTION:

--- High Point Creek Trib 7.f01 (steady flow) ---

Flow Title=Multiple
Number of Profiles=7
Profile Names=10-year,25-year,50-year,1pct_min,100-year,1pct_plu,500-year
River Rch & RM= High Point Creek,Reach-1,4184
     350     450     527     307     612    1221     823
Boundary for River Rch & Prof#=High Point Creek,Reach-1,1
Up Type=0
Dn Type=3
Dn Slope=0.005
Boundary for River Rch & Prof#=High Point Creek,Reach-1,2
Up Type=0
Dn Type=3
Dn Slope=0.005
Boundary for River Rch & Prof#=High Point Creek,Reach-1,3
Up Type=0
Dn Type=3
Dn Slope=0.005
Boundary for River Rch & Prof#=High Point Creek,Reach-1,4
Up Type=0
Dn Type=3
Dn Slope=0.005
Boundary for River Rch & Prof#=High Point Creek,Reach-1,5
Up Type=0
Dn Type=3
Dn Slope=0.005
Boundary for River Rch & Prof#=High Point Creek,Reach-1,6
Up Type=0
Dn Type=3
Dn Slope=0.005
Boundary for River Rch & Prof#=High Point Creek,Reach-1,7
Up Type=0
Dn Type=3
Dn Slope=0.005

--- High Point Creek Trib 7.g01 (geometry) ---

Geom Title=Existing Conditions

River Reach=High Point Creek,Reach-1
Reach XY= 30
      2639276.00      6993261.00      2639367.88      6993167.05
      2639398.86      6993087.16      2639493.04      6993044.50
      2639548.86      6992937.17      2639639.20      6992897.36
      2639822.47      6992709.53      2639824.79      6992571.51
      2639776.52      6992495.78      2639773.76      6992266.93
      2639683.50      6992111.00      2639786.76      6991901.32
      2639916.32      6991771.76      2640027.55      6991714.75
      2640260.98      6991710.68      2640306.60      6991681.66
      2640331.34      6991458.26      2640515.39      6991371.06
      2640575.20      6991250.30      2640533.56      6991161.00
      2640581.81      6991058.71      2640762.67      6990874.65
      2640829.33      6990902.98      2640950.96      6990810.51
      2641024.41      6990814.73      2641086.71      6990860.18
      2641176.09      6990818.84      2641232.69      6990851.71
      2641320.18      6990763.34      2641376.00      6990611.00

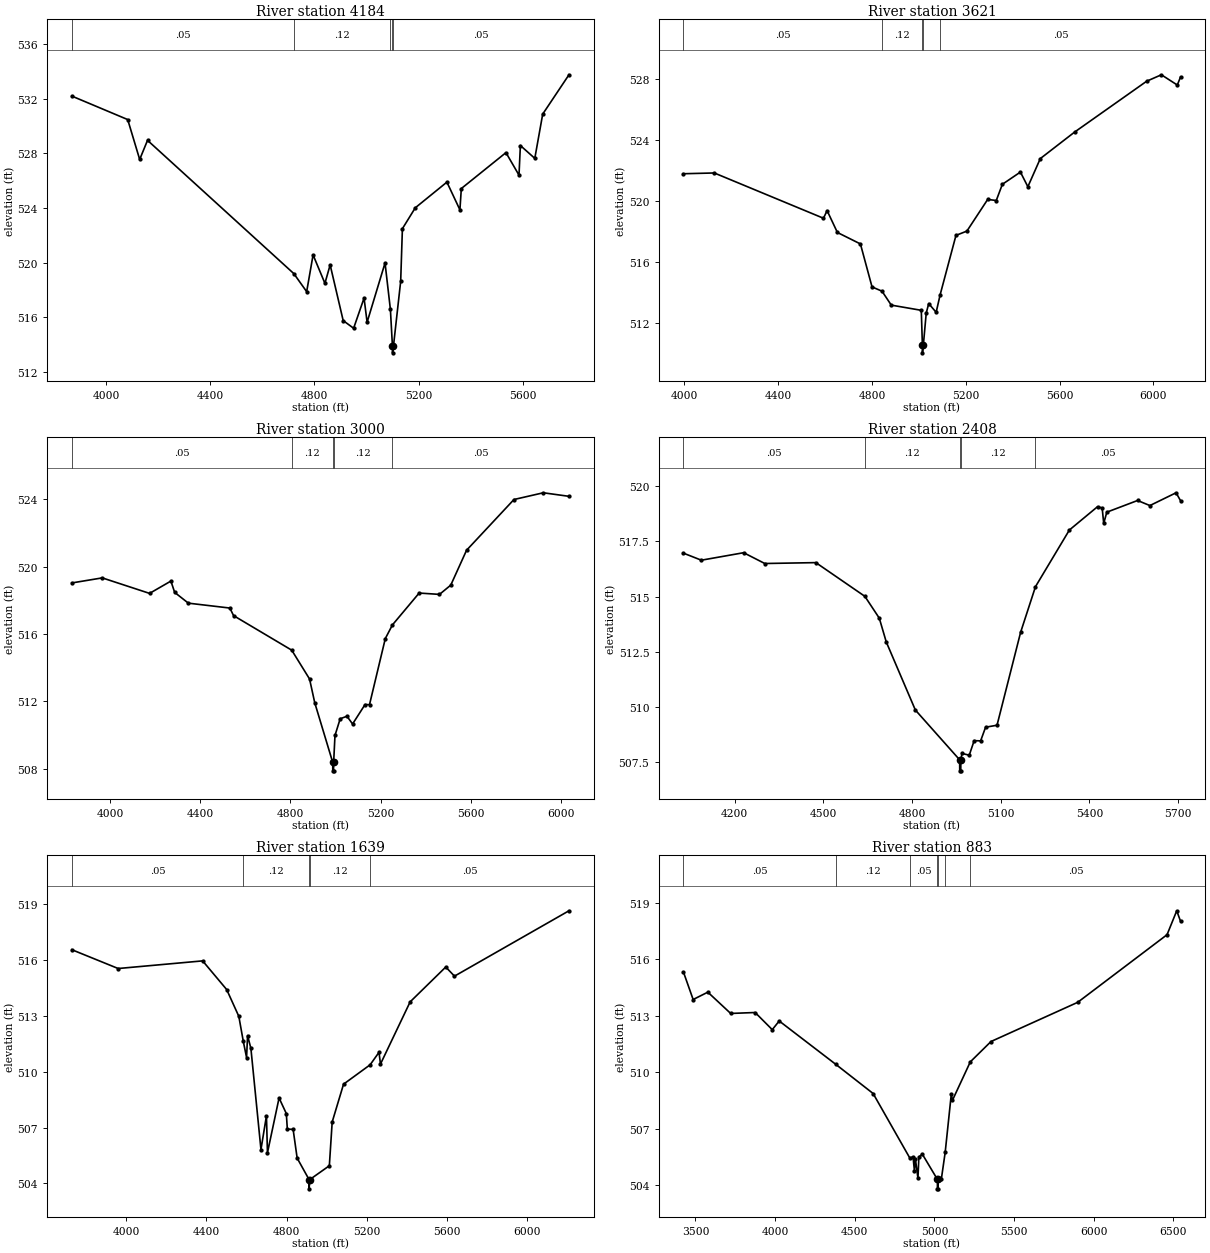
Type RM Length L Ch R = 1,4184,563,563,563
BEGIN DESCRIPTION:
High Point Creek Trib 7 8.0
END DESCRIPTION:
XS GIS Cut Line= 3
      2639226.00      6994361.04      2639305.42      6993231.73
      2638576.04      6992961.02
#Sta/Elev= 30
  3867.9  532.20  4082.6  530.48  4128.6  527.56  4158.7  528.96  4720.9  519.20
  4770.2  517.88  4794.8  520.57  4840.3  518.49  4860.4  519.84  4910.5  515.76
  4950.6  515.20  4990.7  517.41  5002.4  515.64  5071.3  519.98  5091.9  516.58
  5099.7  513.90  5100.0  513.40  5103.7  513.90  5131.4  518.64  5138.0  522.49
  5187.5  524.02  5309.0  525.90  5359.0  523.87  5364.4  525.43  5535.9  528.06
  5586.0  526.41  5591.3  528.58  5646.7  527.64  5677.1  530.88  5778.0  533.76
#Mann=5,-1,0
  3867.9    0.05       0  4720.9    0.12       0  5091.9    0.05       0
  5099.7    0.07       0  5103.7    0.05       0
Bank Sta=5099.7,5103.7
Exp/Cntr=0.3,0.1

Type RM Length L Ch R = 1,3621,621,621,621
BEGIN DESCRIPTION:
Mapping XS 70a773a2
END DESCRIPTION:
XS GIS Cut Line= 3
      2640150.26      6993746.97      2639674.58      6992861.57
      2638619.97      6992500.78
#Sta/Elev= 30
  3995.8  521.78  4127.4  521.83  4592.9  518.87  4608.4  519.37  4652.3  517.94
  4750.5  517.19  4800.0  514.38  4842.6  514.10  4882.0  513.19  5010.0  512.85
  5014.7  510.57  5014.9  510.07  5018.7  510.57  5031.1  512.67  5041.7  513.29
  5073.4  512.72  5090.6  513.88  5157.9  517.75  5204.5  518.03  5293.1  520.10
  5329.7  520.03  5355.7  521.09  5432.7  521.89  5464.4  520.93  5517.5  522.77
  5663.4  524.50  5971.1  527.83  6033.7  528.25  6101.6  527.58  6115.5  528.11
#Mann=5,-1,0
  3995.8    0.05       0  4842.6    0.12       0  5014.7    0.07       0
  5018.7    0.12       0  5090.6    0.05       0
Bank Sta=5014.7,5018.7
Exp/Cntr=0.3,0.1

Type RM Length L Ch R = 1,3000,592,592,592
BEGIN DESCRIPTION:
High Point Creek Trib 7 6.0
END DESCRIPTION:
XS GIS Cut Line= 4
      2640478.42      6993181.06      2640119.02      6992476.15
      2639776.36      6992317.61      2638742.29      6992295.60
#Sta/Elev= 30
  3831.2  519.03  3966.0  519.33  4175.7  518.41  4270.2  519.14  4286.9  518.47
  4347.6  517.83  4531.4  517.54  4548.0  517.09  4805.7  515.04  4884.7  513.33
  4907.7  511.92  4987.4  508.38  4987.6  507.88  4991.1  507.88  4991.4  508.38
  4997.4  509.98  5020.4  510.97  5050.4  511.12  5075.4  510.66  5130.4  511.81
  5150.4  511.81  5220.4  515.73  5252.0  516.54  5370.4  518.43  5460.5  518.35
  5510.5  518.90  5580.5  520.97  5790.5  523.98  5920.6  524.38  6034.3  524.17
#Mann=5,-1,0
  3831.2    0.05       0  4805.7    0.12       0  4987.4    0.07       0
  4991.4    0.12       0  5252.0    0.05       0
Bank Sta=4987.4,4991.4
Exp/Cntr=0.3,0.1

Type RM Length L Ch R = 1,2408,769,769,769
BEGIN DESCRIPTION:
Mapping XS 960cb47f
END DESCRIPTION:
XS GIS Cut Line= 3
      2640426.51      6992614.63      2639874.92      6991822.34
      2639186.32      6991621.78
#Sta/Elev= 30
  4026.1  516.97  4086.8  516.65  4229.9  516.99  4301.5  516.50  4474.3  516.54
  4640.2  515.01  4689.0  514.02  4712.6  512.94  4811.1  509.85  4961.0  507.59
  4961.3  507.09  4964.8  507.09  4965.0  507.59  4969.1  507.88  4993.5  507.80
  5010.1  508.46  5032.0  508.45  5048.8  509.07  5087.5  509.16  5167.4  513.38
  5217.7  515.45  5332.4  518.02  5427.8  519.08  5443.4  519.02  5448.6  518.32
  5459.1  518.83  5563.2  519.36  5604.9  519.13  5693.5  519.71  5708.7  519.35
#Mann=5,-1,0
  4026.1    0.05       0  4640.2    0.12       0  4961.0    0.07       0
  4965.0    0.12       0  5217.7    0.05       0
Bank Sta=4961,4965
Exp/Cntr=0.3,0.1

Type RM Length L Ch R = 1,1639,756,756,756
BEGIN DESCRIPTION:
Mapping XS bcdae45f
END DESCRIPTION:
XS GIS Cut Line= 5
      2640580.27      6992641.37      2640463.27      6991498.08
      2640362.98      6991417.85      2640118.95      6991147.08
      2639290.48      6991300.74
#Sta/Elev= 30
  3727.0  516.55  3958.6  515.54  4380.8  515.95  4501.0  514.41  4561.7  512.97
  4584.0  511.63  4600.4  510.76  4605.4  511.94  4622.0  511.25  4672.3  505.82
  4699.7  507.63  4704.8  505.65  4762.8  508.59  4799.1  507.75  4804.1  506.92
  4833.1  506.90  4853.2  505.36  4912.6  504.21  4912.8  503.71  4916.6  504.21
  5014.1  504.95  5028.3  507.30  5085.1  509.33  5217.9  510.37  5262.3  511.04
  5269.7  510.41  5418.0  513.75  5596.0  515.62  5639.6  515.13  6211.8  518.64
#Mann=5,-1,0
  3727.0    0.05       0  4584.0    0.12       0  4912.6    0.07       0
  4916.6    0.12       0  5217.9    0.05       0
Bank Sta=4912.6,4916.6
Exp/Cntr=0.3,0.1

Type RM Length L Ch R = 1,883,0,0,0
BEGIN DESCRIPTION:
High Point Creek Trib 7 5.0
END DESCRIPTION:
XS GIS Cut Line= 5
      2640690.59      6992390.60      2640941.30      6991257.39
      2640742.67      6990893.48      2640379.70      6990729.22
      2639306.61      6991133.71
#Sta/Elev= 30
  3424.8  515.33  3485.8  513.87  3578.0  514.26  3721.4  513.13  3875.0  513.18
  3982.4  512.27  4026.0  512.73  4379.4  510.44  4615.5  508.88  4845.5  505.46
  4866.1  505.51  4875.0  504.76  4880.7  505.42  4896.9  504.38  4902.6  505.51
  4924.4  505.66  5019.0  504.32  5019.2  503.82  5022.7  503.82  5023.0  504.32
  5044.1  504.36  5067.7  505.75  5106.1  508.84  5113.4  508.52  5225.5  510.56
  5355.4  511.64  5899.5  513.72  6460.4  517.31  6521.2  518.58  6545.2  518.02
#Mann=7,-1,0
  3424.8    0.05       0  4379.4    0.12       0  4845.5    0.05       0
  5019.0    0.03       0  5023.0    0.05       0  5067.7    0.12       0
  5225.5    0.05       0
Bank Sta=5019,5023
Exp/Cntr=0.3,0.1

Chan Stop Cuts=-1