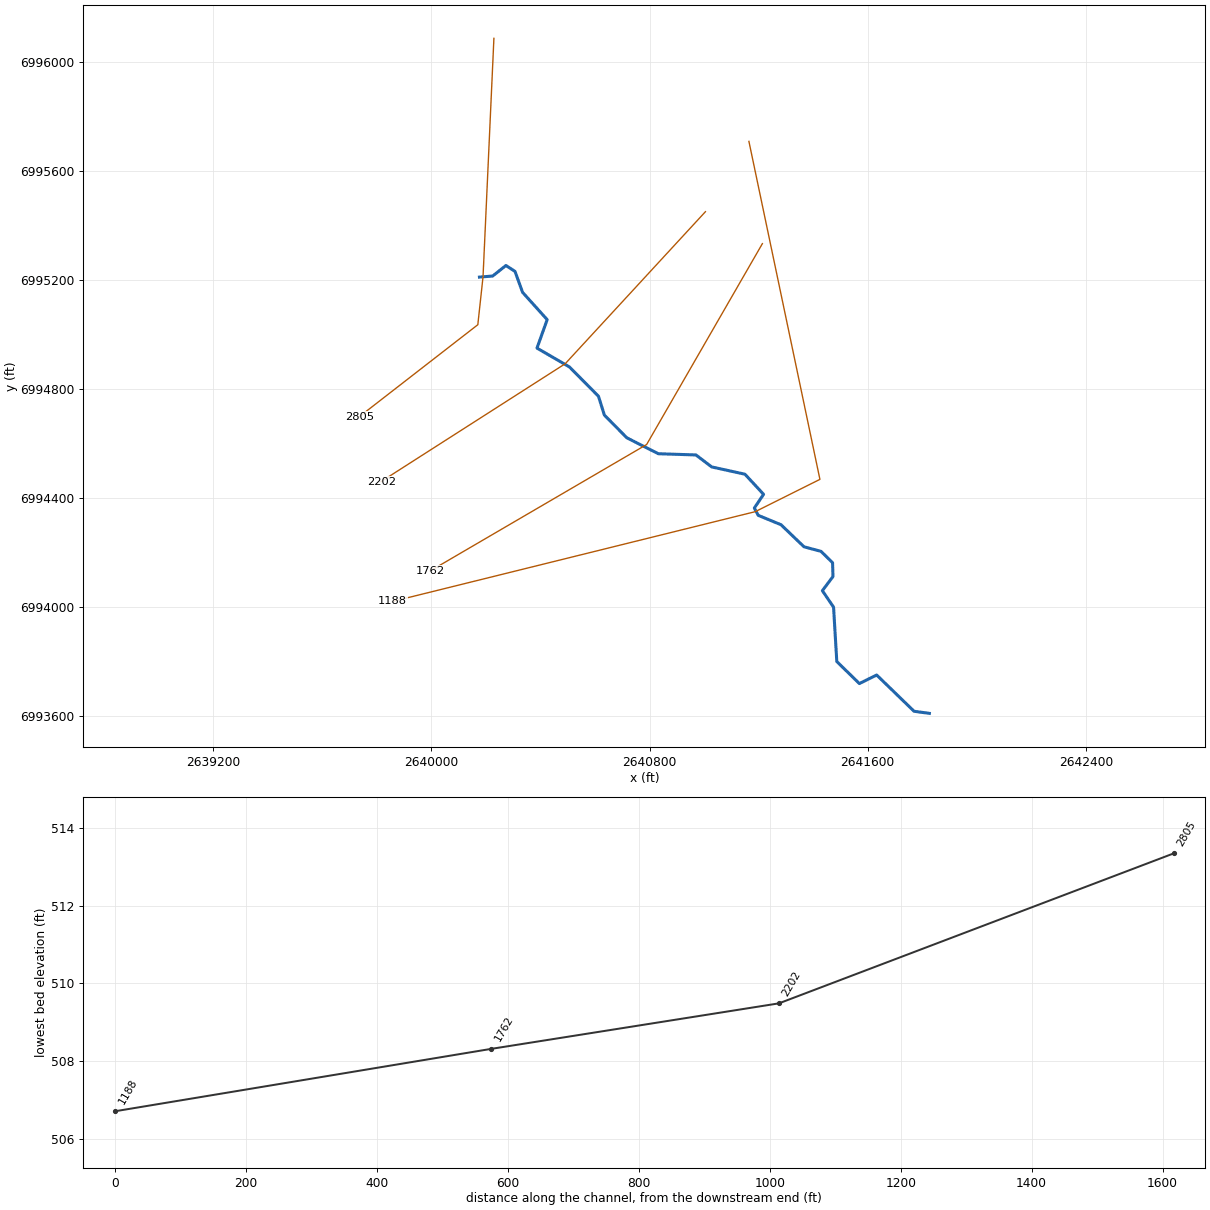
--- High Point Creek Trib 8.prj (project) ---

Proj Title=High Point Creek Trib 8 Base Level Engineering
Current Plan=p01
Default Exp/Contr=0.3,0.1
English Units
Geom File=g01
Flow File=f01
Plan File=p01
BEGIN DESCRIPTION:
High Point Creek Trib 8
END DESCRIPTION:

--- High Point Creek Trib 8.p01 (plan) ---

Plan Title=Multiple Run
Short Identifier=Multiple
Geom File=g01
Flow File=f01
Subcritical Flow
K Sum by GR= 0
Std Step Tol= 0.01
Critical Tol= 0.01
Num of Std Step Trials= 20
Max Error Tol= 0.3
Flow Tol Ratio= 0.001
Split Flow NTrial= 30
Split Flow Tol= 0.02
Split Flow Ratio= 0.02
Log Output Level= 0
Friction Slope Method= 1
Unsteady Friction Slope Method= 2
Unsteady Bridges Friction Slope Method= 1
Parabolic Critical Depth
Global Vel Dist=  1 , 1 , 1
Global Log Level= 0
CheckData=True
Encroach Param= -1, 0, 0, 0
BEGIN DESCRIPTION:
Multiple Run
END DESCRIPTION:

--- High Point Creek Trib 8.f01 (steady flow) ---

Flow Title=Multiple
Number of Profiles=7
Profile Names=10-year,25-year,50-year,1pct_min,100-year,1pct_plu,500-year
River Rch & RM= High Point Creek,Reach-1,2805
     380     493     580     339     677    1351     921
Boundary for River Rch & Prof#=High Point Creek,Reach-1,1
Up Type=0
Dn Type=3
Dn Slope=0.005
Boundary for River Rch & Prof#=High Point Creek,Reach-1,2
Up Type=0
Dn Type=3
Dn Slope=0.005
Boundary for River Rch & Prof#=High Point Creek,Reach-1,3
Up Type=0
Dn Type=3
Dn Slope=0.005
Boundary for River Rch & Prof#=High Point Creek,Reach-1,4
Up Type=0
Dn Type=3
Dn Slope=0.005
Boundary for River Rch & Prof#=High Point Creek,Reach-1,5
Up Type=0
Dn Type=3
Dn Slope=0.005
Boundary for River Rch & Prof#=High Point Creek,Reach-1,6
Up Type=0
Dn Type=3
Dn Slope=0.005
Boundary for River Rch & Prof#=High Point Creek,Reach-1,7
Up Type=0
Dn Type=3
Dn Slope=0.005

--- High Point Creek Trib 8.g01 (geometry) ---

Geom Title=Existing Conditions

River Reach=High Point Creek,Reach-1
Reach XY= 30
      2640176.00      6995211.00      2640224.66      6995215.03
      2640272.95      6995253.54      2640306.24      6995232.03
      2640334.18      6995155.00      2640424.33      6995054.95
      2640386.98      6994950.63      2640506.15      6994881.39
      2640612.37      6994774.21      2640634.15      6994704.93
      2640716.29      6994621.75      2640831.93      6994563.25
      2640970.06      6994558.73      2641027.60      6994514.86
      2641149.63      6994488.12      2641218.00      6994414.34
      2641184.08      6994364.15      2641198.36      6994337.30
      2641282.00      6994302.82      2641366.35      6994221.81
      2641428.61      6994205.25      2641470.99      6994163.54
      2641472.44      6994112.68      2641433.59      6994061.01
      2641474.62      6994000.56      2641486.48      6993801.15
      2641569.31      6993720.30      2641632.67      6993751.70
      2641769.79      6993618.76      2641826.00      6993611.00

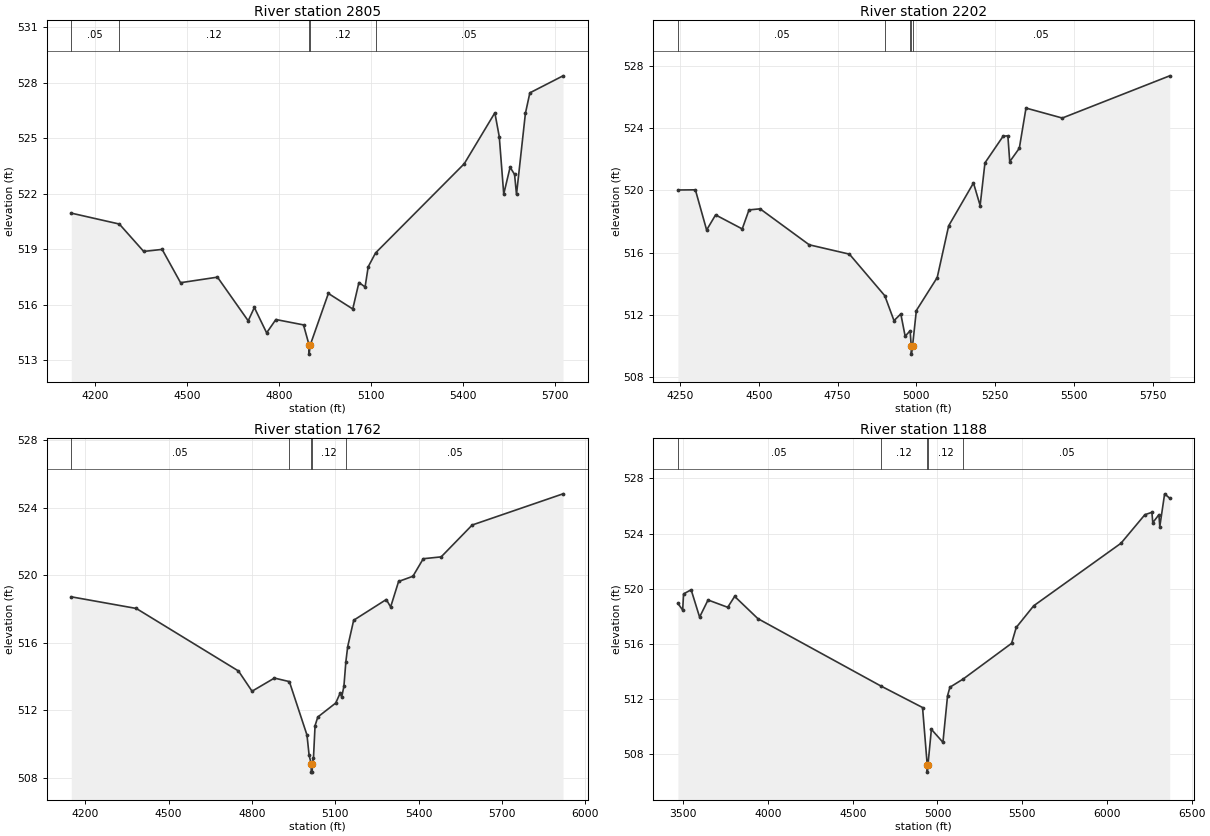
Type RM Length L Ch R = 1,2805,603,603,603
BEGIN DESCRIPTION:
Mapping XS 716138dc
END DESCRIPTION:
XS GIS Cut Line= 4
      2640228.99      6996086.66      2640189.06      6995211.68
      2640169.96      6995036.33      2639735.90      6994699.50
#Sta/Elev= 30
  4123.1  520.96  4279.7  520.37  4359.0  518.89  4419.1  519.00  4479.1  517.20
  4599.3  517.50  4699.4  515.14  4719.4  515.86  4759.4  514.49  4789.5  515.21
  4879.5  514.92  4897.6  513.84  4897.8  513.34  4901.6  513.84  4960.5  516.62
  5039.9  515.78  5060.0  517.21  5080.1  516.97  5090.2  518.06  5114.2  518.81
  5403.1  523.63  5502.7  526.38  5517.1  525.09  5531.6  521.99  5552.4  523.44
  5566.9  523.05  5573.2  521.97  5602.2  526.35  5616.7  527.46  5724.8  528.38
#Mann=5,-1,0
  4123.1    0.05       0  4279.7    0.12       0  4897.6    0.07       0
  4901.6    0.12       0  5114.2    0.05       0
Bank Sta=4897.6,4901.6
Exp/Cntr=0.3,0.1

Type RM Length L Ch R = 1,2202,440,440,440
BEGIN DESCRIPTION:
Mapping XS 4176ac72
END DESCRIPTION:
XS GIS Cut Line= 3
      2641004.71      6995450.90      2640490.37      6994893.17
      2639815.50      6994461.33
#Sta/Elev= 30
  4243.7  520.03  4299.1  520.04  4334.8  517.46  4363.2  518.43  4447.7  517.53
  4469.2  518.75  4504.4  518.82  4660.3  516.51  4787.7  515.91  4899.9  513.24
  4929.1  511.64  4950.7  512.07  4964.5  510.64  4980.3  510.99  4983.8  509.99
  4984.1  509.49  4987.8  509.99  5000.0  512.29  5066.2  514.41  5102.5  517.73
  5181.2  520.48  5202.3  519.03  5217.6  521.77  5275.1  523.48  5290.3  523.51
  5296.2  521.85  5326.6  522.71  5347.8  525.29  5462.8  524.65  5803.6  527.36
#Mann=5,-1,0
  4243.7    0.05       0  4899.9    0.12       0  4980.3    0.05       0
  4983.8    0.05       0  4987.8    0.05       0
Bank Sta=4983.8,4987.8
Exp/Cntr=0.3,0.1

Type RM Length L Ch R = 1,1762,574,574,574
BEGIN DESCRIPTION:
High Point Creek Trib 8 4.0
END DESCRIPTION:
XS GIS Cut Line= 3
      2641213.62      6995333.77      2640789.03      6994596.95
      2639994.89      6994133.27
#Sta/Elev= 30
  4149.6  518.72  4383.6  518.03  4751.4  514.32  4800.3  513.12  4880.8  513.90
  4934.6  513.69  4998.0  510.52  5005.6  509.33  5013.1  508.82  5013.3  508.32
  5016.8  508.32  5017.1  508.82  5021.3  509.14  5027.1  511.08  5037.0  511.59
  5101.5  512.42  5117.2  513.00  5123.0  512.78  5130.9  513.41  5138.0  514.88
  5144.5  515.76  5166.0  517.33  5283.4  518.56  5299.1  518.12  5327.7  519.63
  5379.3  519.94  5416.5  520.98  5481.0  521.09  5592.6  522.98  5919.6  524.83
#Mann=5,-1,0
  4149.6    0.05       0  4934.6    0.12       0  5013.1    0.07       0
  5017.1    0.12       0  5138.0    0.05       0
Bank Sta=5013.1,5017.1
Exp/Cntr=0.3,0.1

Type RM Length L Ch R = 1,1188,0,0,0
BEGIN DESCRIPTION:
High Point Creek Trib 8 3.0
END DESCRIPTION:
XS GIS Cut Line= 4
      2641164.17      6995708.75      2641424.58      6994469.21
      2641187.11      6994350.68      2639856.89      6994021.30
#Sta/Elev= 30
  3468.0  518.94  3496.2  518.46  3501.3  519.63  3546.1  519.93  3596.0  517.95
  3645.8  519.19  3762.0  518.66  3802.9  519.45  3939.9  517.84  4664.2  512.97
  4911.8  511.40  4939.5  507.22  4939.8  506.72  4943.5  507.22  4963.9  509.82
  5032.1  508.88  5059.4  512.26  5073.3  512.87  5152.2  513.47  5437.3  516.05
  5464.7  517.20  5567.8  518.77  6082.9  523.30  6224.0  525.37  6265.4  525.54
  6270.5  524.79  6306.8  525.37  6311.9  524.50  6340.4  526.88  6370.4  526.56
#Mann=5,-1,0
  3468.0    0.05       0  4664.2    0.12       0  4939.5    0.07       0
  4943.5    0.12       0  5152.2    0.05       0
Bank Sta=4939.5,4943.5
Exp/Cntr=0.3,0.1

Chan Stop Cuts=-1