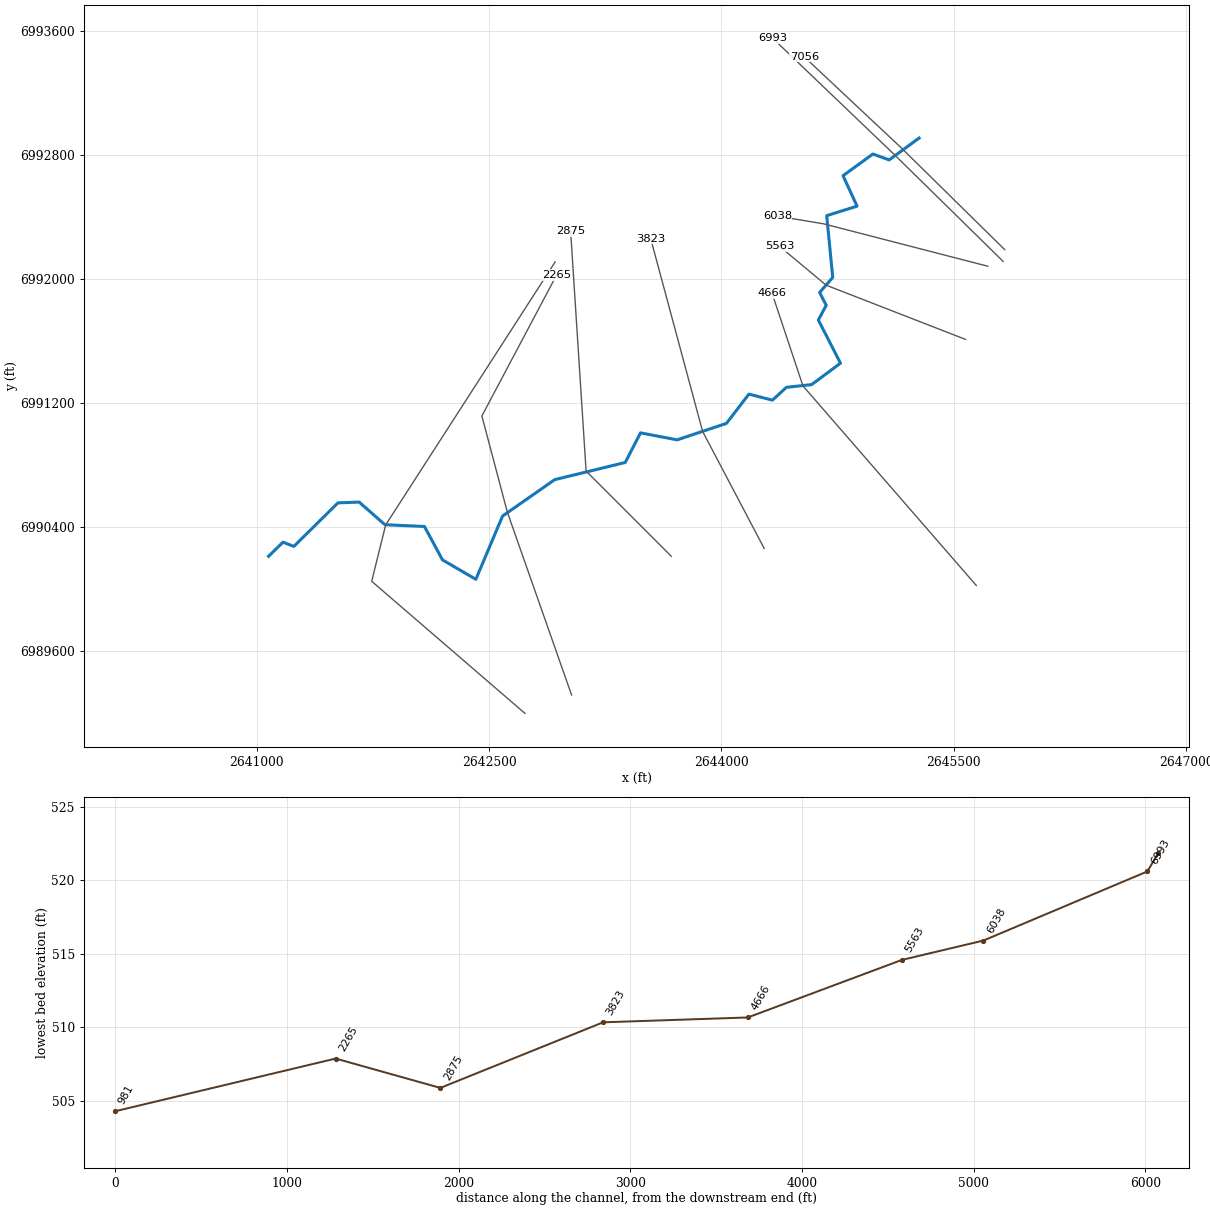
--- High Point Creek Tributary 10.prj (project) ---

Proj Title=High Point Creek Tributary 10 Base Level Engineering
Current Plan=p01
Default Exp/Contr=0.3,0.1
English Units
Geom File=g01
Flow File=f01
Plan File=p01
BEGIN DESCRIPTION:
High Point Creek Tributary 10
END DESCRIPTION:

--- High Point Creek Tributary 10.p01 (plan) ---

Plan Title=Multiple Run
Short Identifier=Multiple
Geom File=g01
Flow File=f01
Subcritical Flow
K Sum by GR= 0
Std Step Tol= 0.01
Critical Tol= 0.01
Num of Std Step Trials= 20
Max Error Tol= 0.3
Flow Tol Ratio= 0.001
Split Flow NTrial= 30
Split Flow Tol= 0.02
Split Flow Ratio= 0.02
Log Output Level= 0
Friction Slope Method= 1
Unsteady Friction Slope Method= 2
Unsteady Bridges Friction Slope Method= 1
Parabolic Critical Depth
Global Vel Dist=  1 , 1 , 1
Global Log Level= 0
CheckData=True
Encroach Param= -1, 0, 0, 0
BEGIN DESCRIPTION:
Multiple Run
END DESCRIPTION:

--- High Point Creek Tributary 10.f01 (steady flow) ---

Flow Title=Multiple
Number of Profiles=7
Profile Names=10-year,25-year,50-year,1pct_min,100-year,1pct_plu,500-year
River Rch & RM= High Point Creek,Reach-1,7056
     474     623     741     438     873    1743    1211
River Rch & RM= High Point Creek,Reach-1,4666
     717     963    1162     694    1385    2764    1969
Boundary for River Rch & Prof#=High Point Creek,Reach-1,1
Up Type=0
Dn Type=3
Dn Slope=0.005
Boundary for River Rch & Prof#=High Point Creek,Reach-1,2
Up Type=0
Dn Type=3
Dn Slope=0.005
Boundary for River Rch & Prof#=High Point Creek,Reach-1,3
Up Type=0
Dn Type=3
Dn Slope=0.005
Boundary for River Rch & Prof#=High Point Creek,Reach-1,4
Up Type=0
Dn Type=3
Dn Slope=0.005
Boundary for River Rch & Prof#=High Point Creek,Reach-1,5
Up Type=0
Dn Type=3
Dn Slope=0.005
Boundary for River Rch & Prof#=High Point Creek,Reach-1,6
Up Type=0
Dn Type=3
Dn Slope=0.005
Boundary for River Rch & Prof#=High Point Creek,Reach-1,7
Up Type=0
Dn Type=3
Dn Slope=0.005

--- High Point Creek Tributary 10.g01 (geometry) ---

Geom Title=Existing Conditions

River Reach=High Point Creek,Reach-1
Reach XY= 30
      2645276.00      6992911.00      2645082.73      6992770.15
      2644977.65      6992807.83      2644784.99      6992668.01
      2644875.47      6992471.43      2644679.46      6992409.98
      2644718.44      6992011.00      2644633.85      6991914.41
      2644676.19      6991831.20      2644625.61      6991736.00
      2644768.51      6991457.42      2644582.04      6991319.14
      2644419.33      6991301.67      2644329.42      6991218.83
      2644177.28      6991257.63      2644032.19      6991068.85
      2643713.85      6990962.52      2643477.23      6991007.57
      2643378.71      6990816.40      2642923.55      6990705.53
      2642586.75      6990470.71      2642414.28      6990062.05
      2642198.86      6990187.43      2642082.21      6990403.20
      2641827.46      6990414.54      2641660.84      6990560.64
      2641523.55      6990555.55      2641239.33      6990274.65
      2641169.33      6990301.83      2641076.00      6990211.00

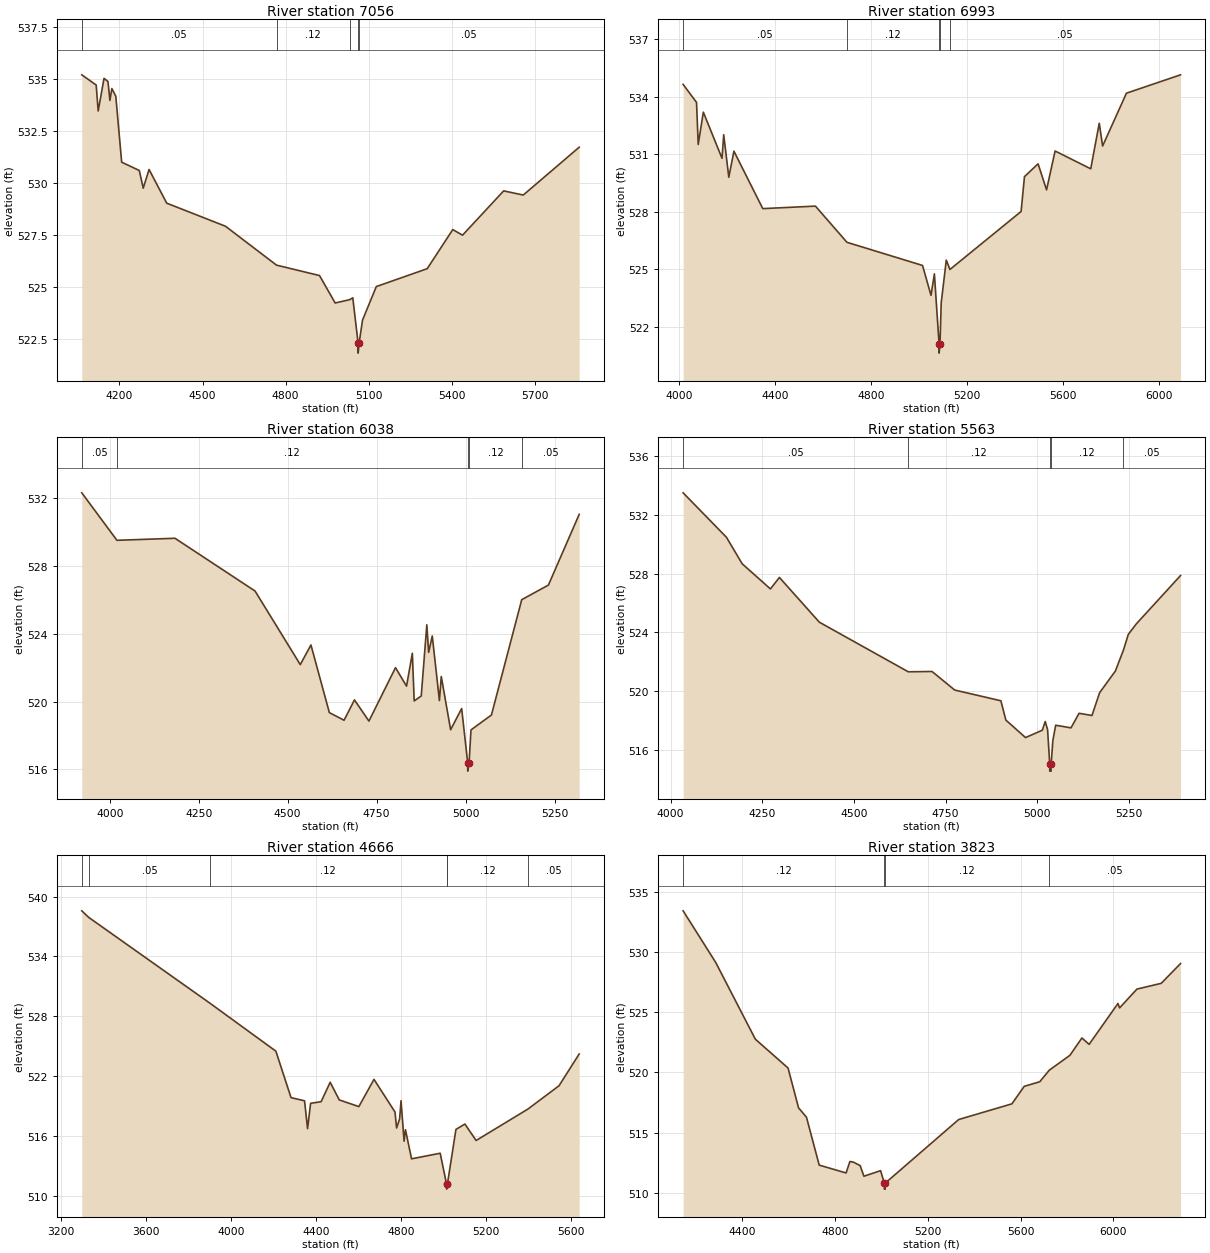
Type RM Length L Ch R = 1,7056,63,63,63
BEGIN DESCRIPTION:
High Point Creek Tributary 10 9.0
END DESCRIPTION:
XS GIS Cut Line= 3
      2645828.96      6992190.34      2645161.91      6992846.95
      2644534.73      6993435.09
#Sta/Elev= 30
  4064.0  535.22  4116.0  534.73  4123.2  533.48  4144.3  535.05  4158.5  534.90
  4165.6  533.99  4172.6  534.56  4186.8  534.19  4208.0  531.02  4271.6  530.62
  4285.8  529.77  4306.9  530.67  4370.6  529.05  4582.8  527.94  4767.1  526.07
  4922.2  525.57  4978.8  524.25  5031.2  524.41  5042.4  524.50  5061.4  522.34
  5061.7  521.84  5065.4  522.34  5077.6  523.43  5127.4  525.04  5311.1  525.90
  5403.4  527.78  5438.6  527.51  5587.1  529.64  5657.9  529.44  5859.8  531.74
#Mann=5,-1,0
  4064.0    0.05       0  4767.1    0.12       0  5031.2    0.05       0
  5061.4    0.07       0  5065.4    0.05       0
Bank Sta=5061.4,5065.4
Exp/Cntr=0.3,0.1

Type RM Length L Ch R = 1,6993,955,955,955
BEGIN DESCRIPTION:
Mapping XS bbddd763
END DESCRIPTION:
XS GIS Cut Line= 3
      2645818.60      6992114.76      2645115.45      6992804.89
      2644331.60      6993554.89
#Sta/Elev= 30
  4018.4  534.65  4074.2  533.71  4081.2  531.51  4102.5  533.20  4180.2  530.79
  4187.3  532.02  4208.5  529.80  4229.8  531.16  4349.9  528.16  4569.1  528.29
  4700.2  526.40  5014.8  525.19  5050.0  523.63  5064.1  524.75  5083.5  521.11
  5083.8  520.61  5087.5  521.11  5092.4  523.23  5113.6  525.47  5128.8  524.98
  5424.9  528.01  5439.0  529.83  5495.6  530.50  5530.9  529.14  5566.4  531.17
  5714.8  530.24  5750.2  532.62  5764.2  531.43  5863.3  534.19  6088.5  535.15
#Mann=5,-1,0
  4018.4    0.05       0  4700.2    0.12       0  5083.5    0.07       0
  5087.5    0.12       0  5128.8    0.05       0
Bank Sta=5083.5,5087.5
Exp/Cntr=0.3,0.1

Type RM Length L Ch R = 1,6038,475,475,475
BEGIN DESCRIPTION:
High Point Creek Tributary 10 8.0
END DESCRIPTION:
XS GIS Cut Line= 3
      2645719.59      6992083.55      2644660.28      6992357.08
      2644360.67      6992407.02
#Sta/Elev= 30
  3921.4  532.31  4020.2  529.51  4183.3  529.63  4408.3  526.52  4535.4  522.18
  4565.4  523.34  4617.1  519.35  4658.4  518.90  4687.7  520.10  4728.3  518.85
  4803.0  522.00  4834.0  520.91  4850.3  522.85  4855.5  520.04  4875.3  520.33
  4891.0  524.53  4896.1  522.90  4906.3  523.87  4926.4  520.06  4931.6  521.48
  4957.9  518.34  4988.9  519.59  5005.8  516.40  5006.0  515.90  5009.8  516.40
  5015.1  518.33  5072.6  519.21  5157.7  526.01  5232.7  526.87  5319.2  531.04
#Mann=5,-1,0
  3921.4    0.05       0  4020.2    0.12       0  5005.8    0.07       0
  5009.8    0.12       0  5157.7    0.05       0
Bank Sta=5005.8,5009.8
Exp/Cntr=0.3,0.1

Type RM Length L Ch R = 1,5563,897,897,897
BEGIN DESCRIPTION:
High Point Creek Tributary 10 7.0
END DESCRIPTION:
XS GIS Cut Line= 3
      2645576.04      6991610.99      2644676.00      6991961.00
      2644376.01      6992210.99
#Sta/Elev= 30
  4034.3  533.49  4152.4  530.47  4195.3  528.67  4272.3  526.96  4296.8  527.74
  4405.7  524.70  4648.1  521.33  4713.0  521.35  4774.7  520.09  4900.7  519.36
  4914.2  518.05  4967.8  516.86  5013.7  517.36  5021.5  517.95  5028.0  517.40
  5033.8  515.08  5034.0  514.58  5037.5  514.58  5037.8  515.08  5042.3  516.65
  5050.1  517.70  5091.8  517.52  5113.9  518.51  5149.0  518.36  5169.9  519.91
  5212.8  521.38  5234.9  522.81  5248.0  523.87  5270.1  524.59  5390.5  527.87
#Mann=5,-1,0
  4034.3    0.05       0  4648.1    0.12       0  5033.8    0.07       0
  5037.8    0.12       0  5234.9    0.05       0
Bank Sta=5033.8,5037.8
Exp/Cntr=0.3,0.1

Type RM Length L Ch R = 1,4666,843,843,843
BEGIN DESCRIPTION:
High Point Creek Tributary 10 5.0
END DESCRIPTION:
XS GIS Cut Line= 3
      2645645.63      6990021.94      2644526.00      6991311.00
      2644325.99      6991911.04
#Sta/Elev= 30
  3297.7  538.58  3330.4  537.92  3900.8  529.31  4210.8  524.50  4282.0  519.84
  4345.6  519.52  4359.8  516.73  4374.1  519.27  4423.5  519.43  4466.2  521.38
  4508.9  519.61  4601.1  518.94  4672.3  521.67  4771.0  518.40  4778.6  516.79
  4792.9  517.71  4799.5  519.53  4813.8  515.47  4820.4  516.62  4848.9  513.70
  4983.7  514.26  5013.6  511.16  5013.9  510.66  5017.6  511.16  5057.8  516.65
  5100.0  517.19  5152.7  515.54  5396.2  518.69  5542.7  521.03  5637.6  524.22
#Mann=6,-1,0
  3297.7    0.12       0  3330.4    0.05       0  3900.8    0.12       0
  5013.6    0.07       0  5017.6    0.12       0  5396.2    0.05       0
Bank Sta=5013.6,5017.6
Exp/Cntr=0.3,0.1

Type RM Length L Ch R = 1,3823,948,948,948
BEGIN DESCRIPTION:
High Point Creek Tributary 10 4.0
END DESCRIPTION:
XS GIS Cut Line= 3
      2644276.00      6990260.99      2643878.33      6991016.75
      2643543.13      6992261.30
#Sta/Elev= 30
  4146.0  533.40  4286.4  529.12  4457.1  522.76  4598.0  520.37  4643.2  517.07
  4677.4  516.29  4732.3  512.32  4848.1  511.67  4864.5  512.62  4880.5  512.56
  4908.6  512.28  4924.9  511.40  4996.7  511.86  5012.7  510.83  5013.0  510.33
  5016.5  510.33  5016.9  510.83  5333.2  516.10  5562.5  517.40  5615.4  518.85
  5682.3  519.23  5723.4  520.19  5812.2  521.42  5864.0  522.86  5895.0  522.33
  6019.3  525.72  6026.2  525.35  6100.9  526.91  6205.7  527.39  6288.9  529.03
#Mann=4,-1,0
  4146.0    0.12       0  5012.7    0.07       0  5016.9    0.12       0
  5723.4    0.05       0
Bank Sta=5012.7,5016.9
Exp/Cntr=0.3,0.1

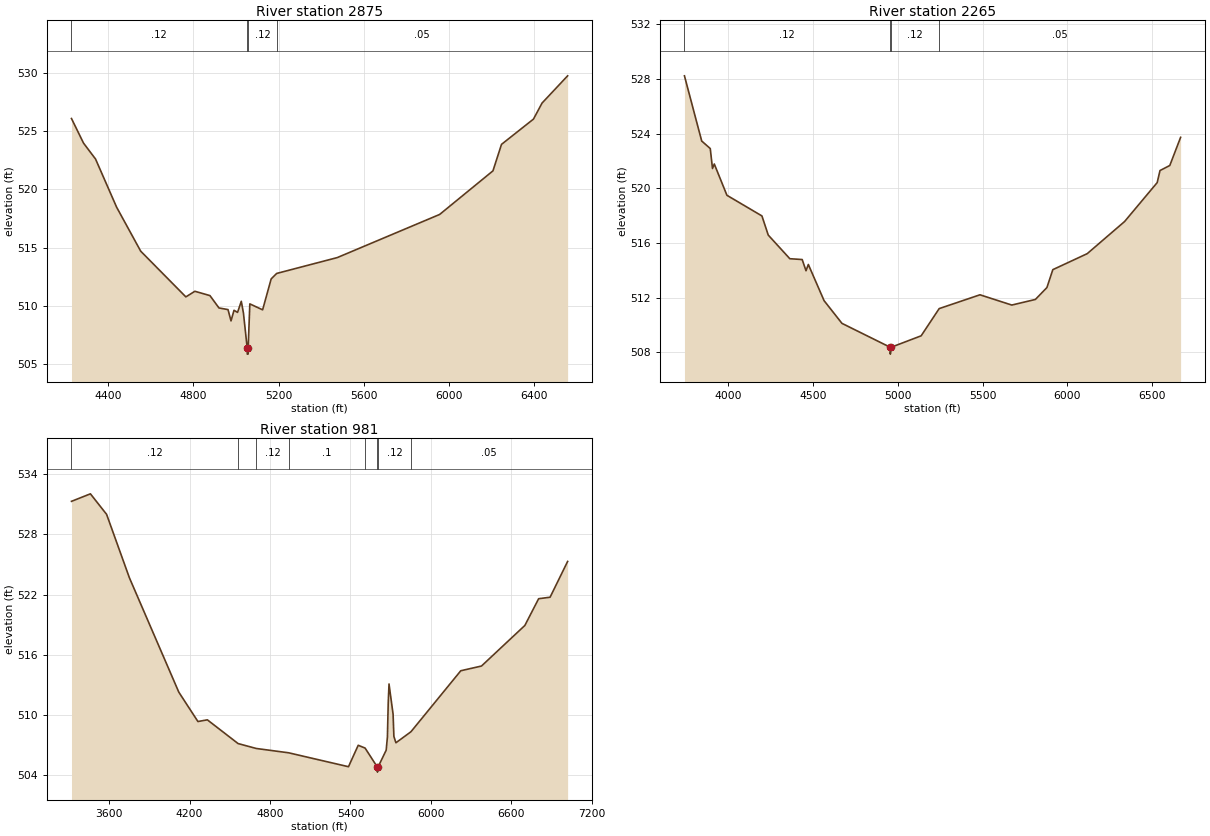
Type RM Length L Ch R = 1,2875,610,610,610
BEGIN DESCRIPTION:
High Point Creek Tributary 10 2.0
END DESCRIPTION:
XS GIS Cut Line= 3
      2643676.01      6990210.99      2643126.00      6990761.00
      2643026.00      6992311.04
#Sta/Elev= 30
  4226.8  526.07  4283.4  523.96  4340.0  522.59  4439.0  518.46  4552.1  514.69
  4764.2  510.77  4806.6  511.25  4877.4  510.88  4919.8  509.82  4962.2  509.68
  4976.4  508.71  4990.5  509.62  5007.1  509.44  5024.7  510.39  5034.7  509.39
  5052.6  506.36  5052.9  505.86  5056.5  505.86  5056.9  506.36  5064.8  510.17
  5124.9  509.66  5165.0  512.31  5190.9  512.78  5475.6  514.14  5956.6  517.84
  6207.1  521.58  6247.2  523.85  6397.5  526.02  6437.6  527.39  6557.9  529.73
#Mann=4,-1,0
  4226.8    0.12       0  5052.6    0.07       0  5056.9    0.12       0
  5190.9    0.05       0
Bank Sta=5052.6,5056.9
Exp/Cntr=0.3,0.1

Type RM Length L Ch R = 1,2265,1284,1284,1284
BEGIN DESCRIPTION:
Mapping XS 3bbd3a6f
END DESCRIPTION:
XS GIS Cut Line= 4
      2643032.33      6989315.05      2642617.31      6990496.27
      2642453.13      6991116.52      2642935.83      6992027.29
#Sta/Elev= 30
  3742.5  528.22  3844.2  523.45  3894.6  522.90  3907.8  521.44  3918.4  521.77
  3992.9  519.48  4199.2  517.97  4236.4  516.57  4363.6  514.84  4436.4  514.78
  4459.0  513.96  4472.7  514.42  4565.6  511.77  4670.9  510.11  4955.6  508.36
  4956.0  507.86  4960.1  508.36  5137.7  509.20  5243.9  511.19  5484.3  512.20
  5671.9  511.45  5811.0  511.86  5878.9  512.73  5913.8  514.04  6116.5  515.21
  6336.7  517.56  6529.0  520.41  6545.4  521.29  6603.2  521.66  6666.9  523.72
#Mann=4,-1,0
  3742.5    0.12       0  4955.6    0.07       0  4960.1    0.12       0
  5243.9    0.05       0
Bank Sta=4955.6,4960.1
Exp/Cntr=0.3,0.1

Type RM Length L Ch R = 1,981,0,0,0
BEGIN DESCRIPTION:
High Point Creek Tributary 10 1.0
END DESCRIPTION:
XS GIS Cut Line= 4
      2642731.33      6989196.47      2641741.66      6990049.32
      2641831.85      6990413.06      2642925.98      6992110.96
#Sta/Elev= 30
  3318.8  531.30  3460.2  532.05  3580.9  530.00  3750.9  523.67  4119.6  512.25
  4262.2  509.32  4332.4  509.49  4561.8  507.12  4697.6  506.63  4938.3  506.20
  5385.2  504.81  5457.8  506.95  5509.1  506.67  5600.7  504.77  5601.2  504.27
  5605.3  504.77  5666.4  506.46  5675.6  507.78  5681.5  511.13  5687.5  513.07
  5717.9  510.05  5723.8  507.84  5739.0  507.20  5851.1  508.30  6222.9  514.39
  6377.3  514.86  6700.8  518.91  6803.7  521.58  6889.1  521.73  7019.9  525.30
#Mann=8,-1,0
  3318.8    0.12       0  4561.8    0.05       0  4697.6    0.12       0
  4938.3     0.1       0  5509.1    0.12       0  5600.7    0.07       0
  5605.3    0.12       0  5851.1    0.05       0
Bank Sta=5600.7,5605.3
Exp/Cntr=0.3,0.1

Chan Stop Cuts=-1