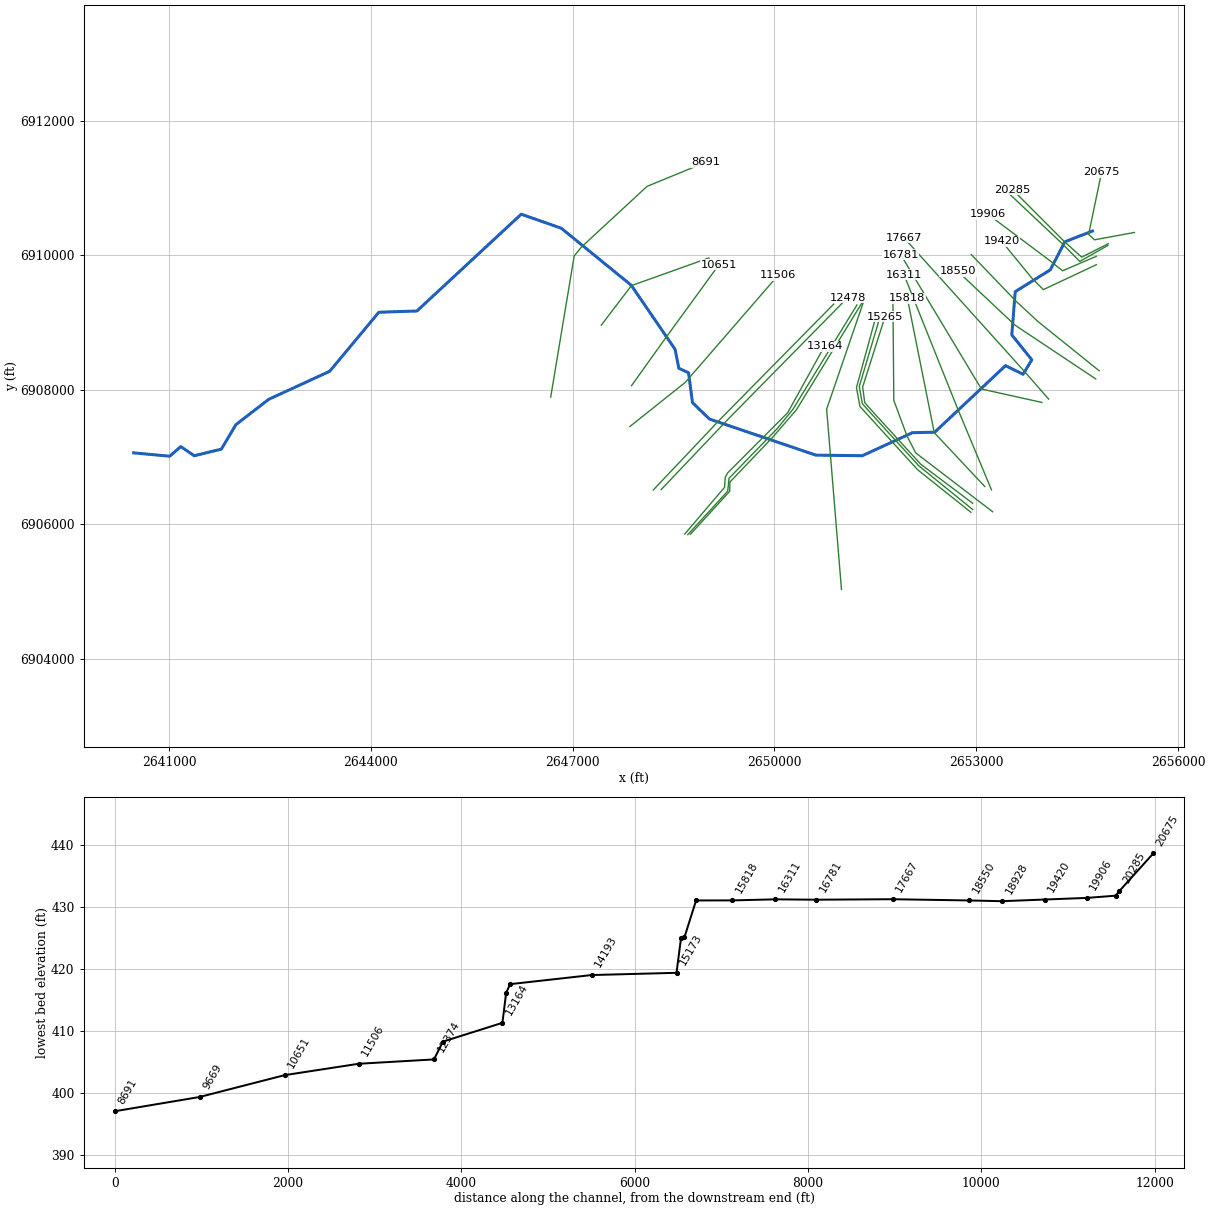
--- Kauffman Branch.prj (project) ---

Proj Title=Kauffman Branch Base Level Engineering
Current Plan=p01
Default Exp/Contr=0.3,0.1
English Units
Geom File=g01
Flow File=f01
Plan File=p01
BEGIN DESCRIPTION:
Kauffman Branch
END DESCRIPTION:

--- Kauffman Branch.p01 (plan) ---

Plan Title=Multiple Run
Short Identifier=Multiple
Geom File=g01
Flow File=f01
Subcritical Flow
K Sum by GR= 0
Std Step Tol= 0.01
Critical Tol= 0.01
Num of Std Step Trials= 20
Max Error Tol= 0.3
Flow Tol Ratio= 0.001
Split Flow NTrial= 30
Split Flow Tol= 0.02
Split Flow Ratio= 0.02
Log Output Level= 0
Friction Slope Method= 1
Unsteady Friction Slope Method= 2
Unsteady Bridges Friction Slope Method= 1
Parabolic Critical Depth
Global Vel Dist=  1 , 1 , 1
Global Log Level= 0
CheckData=True
Encroach Param= -1, 0, 0, 0
BEGIN DESCRIPTION:
Multiple Run
END DESCRIPTION:

--- Kauffman Branch.f01 (steady flow) ---

Flow Title=Multiple
Number of Profiles=7
Profile Names=10-year,25-year,50-year,1pct_min,100-year,1pct_plu,500-year
River Rch & RM= Kauffman Branch,Reach-1,20675
     313     402     470     273     544    1086     730
River Rch & RM= Kauffman Branch,Reach-1,19906
     347     447     524     305     608    1214     819
River Rch & RM= Kauffman Branch,Reach-1,17667
     596     794     952     566    1129    2253    1587
River Rch & RM= Kauffman Branch,Reach-1,13253
     607     811     973     578    1154    2303    1625
River Rch & RM= Kauffman Branch,Reach-1,12478
     872    1189    1448     872    1741    3473    2519
River Rch & RM= Kauffman Branch,Reach-1,10651
    1117    1541    1892    1148    2292    4572    3365
Boundary for River Rch & Prof#=Kauffman Branch,Reach-1,1
Up Type=0
Dn Type=3
Dn Slope=0.005
Boundary for River Rch & Prof#=Kauffman Branch,Reach-1,2
Up Type=0
Dn Type=3
Dn Slope=0.005
Boundary for River Rch & Prof#=Kauffman Branch,Reach-1,3
Up Type=0
Dn Type=3
Dn Slope=0.005
Boundary for River Rch & Prof#=Kauffman Branch,Reach-1,4
Up Type=0
Dn Type=3
Dn Slope=0.005
Boundary for River Rch & Prof#=Kauffman Branch,Reach-1,5
Up Type=0
Dn Type=3
Dn Slope=0.005
Boundary for River Rch & Prof#=Kauffman Branch,Reach-1,6
Up Type=0
Dn Type=3
Dn Slope=0.005
Boundary for River Rch & Prof#=Kauffman Branch,Reach-1,7
Up Type=0
Dn Type=3
Dn Slope=0.005

--- Kauffman Branch.g01 (geometry) ---

Geom Title=Existing Conditions

River Reach=Kauffman Branch,Reach-1
Reach XY= 30
      2654726.00      6910361.00      2654316.00      6910200.37
      2654100.47      6909783.84      2653579.15      6909459.36
      2653528.15      6908816.97      2653825.76      6908445.78
      2653696.09      6908230.42      2653434.50      6908358.41
      2652382.19      6907368.81      2652050.32      6907360.98
      2651305.97      6907018.62      2650615.86      6907027.30
      2649034.30      6907564.07      2648781.73      6907808.45
      2648723.37      6908252.54      2648579.06      6908319.28
      2648522.47      6908602.51      2647870.72      6909555.46
      2646832.06      6910402.86      2646236.17      6910611.50
      2644685.68      6909171.76      2644119.81      6909153.19
      2643389.24      6908274.61      2642483.98      6907858.05
      2641995.63      6907481.47      2641778.44      6907116.39
      2641376.09      6907018.28      2641176.00      6907153.92
      2641010.84      6907011.38      2640476.00      6907061.00

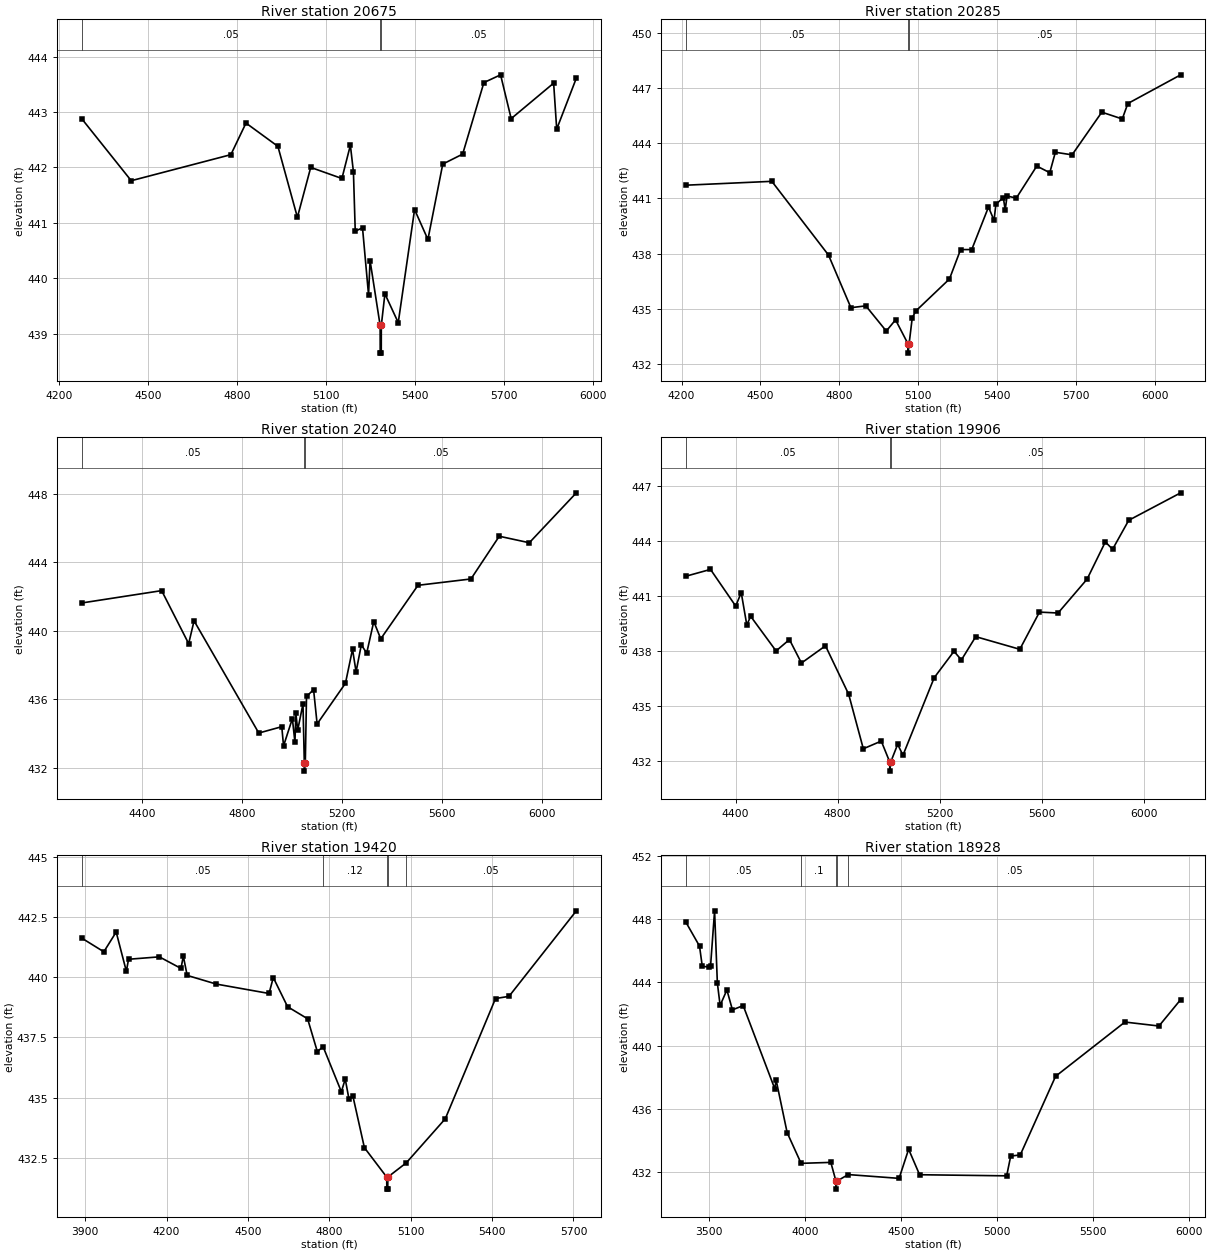
Type RM Length L Ch R = 1,20675,390,390,390
BEGIN DESCRIPTION:
Kauffman Branch 29.0
END DESCRIPTION:
XS GIS Cut Line= 4
      2655350.22      6910339.95      2654756.44      6910230.56
      2654670.21      6910312.91      2654863.21      6911235.74
#Sta/Elev= 30
  4277.0  442.88  4444.0  441.76  4779.5  442.23  4830.4  442.80  4937.8  442.38
  5003.5  441.10  5048.4  442.00  5153.4  441.80  5181.9  442.40  5192.2  441.92
  5198.3  440.85  5222.8  440.91  5243.1  439.70  5248.2  440.32  5282.1  439.15
  5282.4  438.65  5285.9  438.65  5286.1  439.15  5298.2  439.72  5343.1  439.20
  5398.1  441.24  5443.0  440.70  5493.0  442.06  5560.0  442.24  5631.5  443.53
  5687.7  443.67  5723.4  442.88  5866.4  443.52  5876.7  442.69  5942.8  443.61
#Mann=3,-1,0
  4277.0    0.05       0  5282.1    0.03       0  5286.1    0.05       0
Bank Sta=5282.1,5286.1
Exp/Cntr=0.3,0.1

Type RM Length L Ch R = 1,20285,45,45,45
BEGIN DESCRIPTION:
Mapping XS 58329ff6
END DESCRIPTION:
XS GIS Cut Line= 4
      2654963.03      6910173.27      2654567.20      6909972.75
      2654317.20      6910196.71      2653538.55      6910977.97
#Sta/Elev= 30
  4217.0  441.72  4543.6  441.93  4759.3  437.92  4844.5  435.06  4901.3  435.16
  4979.1  433.79  5014.4  434.40  5061.9  433.09  5062.1  432.59  5065.9  433.09
  5078.0  434.52  5092.2  434.89  5219.5  436.62  5261.9  438.22  5304.3  438.22
  5368.0  440.53  5389.2  439.81  5396.2  440.68  5424.5  441.05  5431.6  440.37
  5438.7  441.13  5474.0  441.02  5551.8  442.76  5601.3  442.40  5622.5  443.51
  5686.1  443.37  5799.3  445.69  5877.1  445.32  5898.3  446.16  6099.4  447.72
#Mann=3,-1,0
  4217.0    0.05       0  5061.9    0.04       0  5065.9    0.05       0
Bank Sta=5061.9,5065.9
Exp/Cntr=0.3,0.1

Type RM Length L Ch R = 1,20240,334,334,334
BEGIN DESCRIPTION:
Mapping XS 29a8ebb2
END DESCRIPTION:
XS GIS Cut Line= 4
      2654955.26      6910146.38      2654538.56      6909909.38
      2654275.54      6910175.01      2653456.49      6910947.25
#Sta/Elev= 30
  4158.4  441.62  4478.4  442.34  4586.5  439.25  4608.1  440.58  4867.0  434.04
  4959.0  434.41  4966.0  433.29  5001.4  434.88  5011.6  433.50  5015.4  435.18
  5022.7  434.21  5043.8  435.74  5049.1  432.32  5049.3  431.82  5053.1  432.32
  5057.9  436.17  5086.2  436.57  5100.4  434.57  5213.7  436.94  5242.0  438.92
  5256.2  437.61  5277.2  439.18  5298.7  438.70  5327.0  440.54  5354.9  439.53
  5503.8  442.65  5715.8  443.02  5829.0  445.51  5949.2  445.13  6137.3  448.04
#Mann=3,-1,0
  4158.4    0.05       0  5049.1    0.04       0  5053.1    0.05       0
Bank Sta=5049.1,5053.1
Exp/Cntr=0.3,0.1

Type RM Length L Ch R = 1,19906,486,486,486
BEGIN DESCRIPTION:
Kauffman Branch 27.0
END DESCRIPTION:
XS GIS Cut Line= 4
      2654785.07      6909985.77      2654282.48      6909769.63
      2654089.06      6909924.53      2653172.25      6910611.63
#Sta/Elev= 30
  4205.1  442.10  4301.2  442.47  4400.0  440.47  4421.8  441.20  4443.6  439.44
  4458.8  439.91  4558.4  438.02  4610.9  438.64  4658.0  437.36  4752.2  438.30
  4843.1  435.66  4900.7  432.68  4971.1  433.10  5004.3  431.96  5004.5  431.46
  5008.3  431.96  5035.4  432.92  5056.3  432.33  5178.8  436.56  5256.3  438.00
  5285.5  437.53  5341.7  438.80  5514.6  438.11  5591.7  440.14  5664.7  440.09
  5778.6  441.94  5850.1  443.97  5878.6  443.57  5941.8  445.15  6145.7  446.65
#Mann=3,-1,0
  4205.1    0.05       0  5004.3    0.03       0  5008.3    0.05       0
Bank Sta=5004.3,5008.3
Exp/Cntr=0.3,0.1

Type RM Length L Ch R = 1,19420,492,492,492
BEGIN DESCRIPTION:
Kauffman Branch 26.0
END DESCRIPTION:
XS GIS Cut Line= 4
      2654785.09      6909860.78      2653997.32      6909489.68
      2653826.00      6909661.00      2653376.02      6910210.98
#Sta/Elev= 30
  3886.9  441.62  3968.7  441.05  4014.2  441.87  4051.7  440.24  4059.8  440.74
  4173.3  440.84  4253.1  440.36  4261.7  440.87  4275.9  440.07  4383.3  439.71
  4577.7  439.32  4593.4  439.98  4646.1  438.77  4719.9  438.27  4755.7  436.91
  4777.1  437.11  4844.4  435.24  4858.6  435.77  4872.7  434.92  4886.9  435.06
  4929.3  432.92  5011.6  431.70  5011.9  431.20  5015.4  431.20  5015.6  431.70
  5083.6  432.29  5227.5  434.12  5412.7  439.11  5462.3  439.20  5710.6  442.75
#Mann=5,-1,0
  3886.9    0.05       0  4777.1    0.12       0  5011.6    0.07       0
  5015.6    0.12       0  5083.6    0.05       0
Bank Sta=5011.6,5015.6
Exp/Cntr=0.3,0.1

Type RM Length L Ch R = 1,18928,378,378,378
BEGIN DESCRIPTION:
Kauffman Branch 25.0
END DESCRIPTION:
XS GIS Cut Line= 4
      2654826.72      6908282.68      2653919.68      6909012.65
      2653587.21      6909320.79      2652926.01      6910010.99
#Sta/Elev= 30
  3382.4  447.79  3452.7  446.29  3467.1  445.01  3502.3  444.97  3510.3  445.06
  3531.1  448.52  3545.5  443.96  3559.9  442.54  3595.1  443.52  3623.9  442.26
  3679.9  442.53  3844.6  437.26  3851.0  437.84  3908.6  434.50  3981.1  432.56
  4135.8  432.62  4162.6  431.43  4162.8  430.93  4166.6  431.43  4226.2  431.85
  4490.9  431.61  4540.5  433.45  4597.6  431.84  5050.5  431.77  5071.6  433.02
  5121.3  433.09  5305.0  438.06  5665.7  441.49  5842.8  441.24  5955.8  442.91
#Mann=5,-1,0
  3382.4    0.05       0  3981.1     0.1       0  4162.6    0.03       0
  4166.6     0.1       0  4226.2    0.05       0
Bank Sta=4162.6,4166.6
Exp/Cntr=0.3,0.1

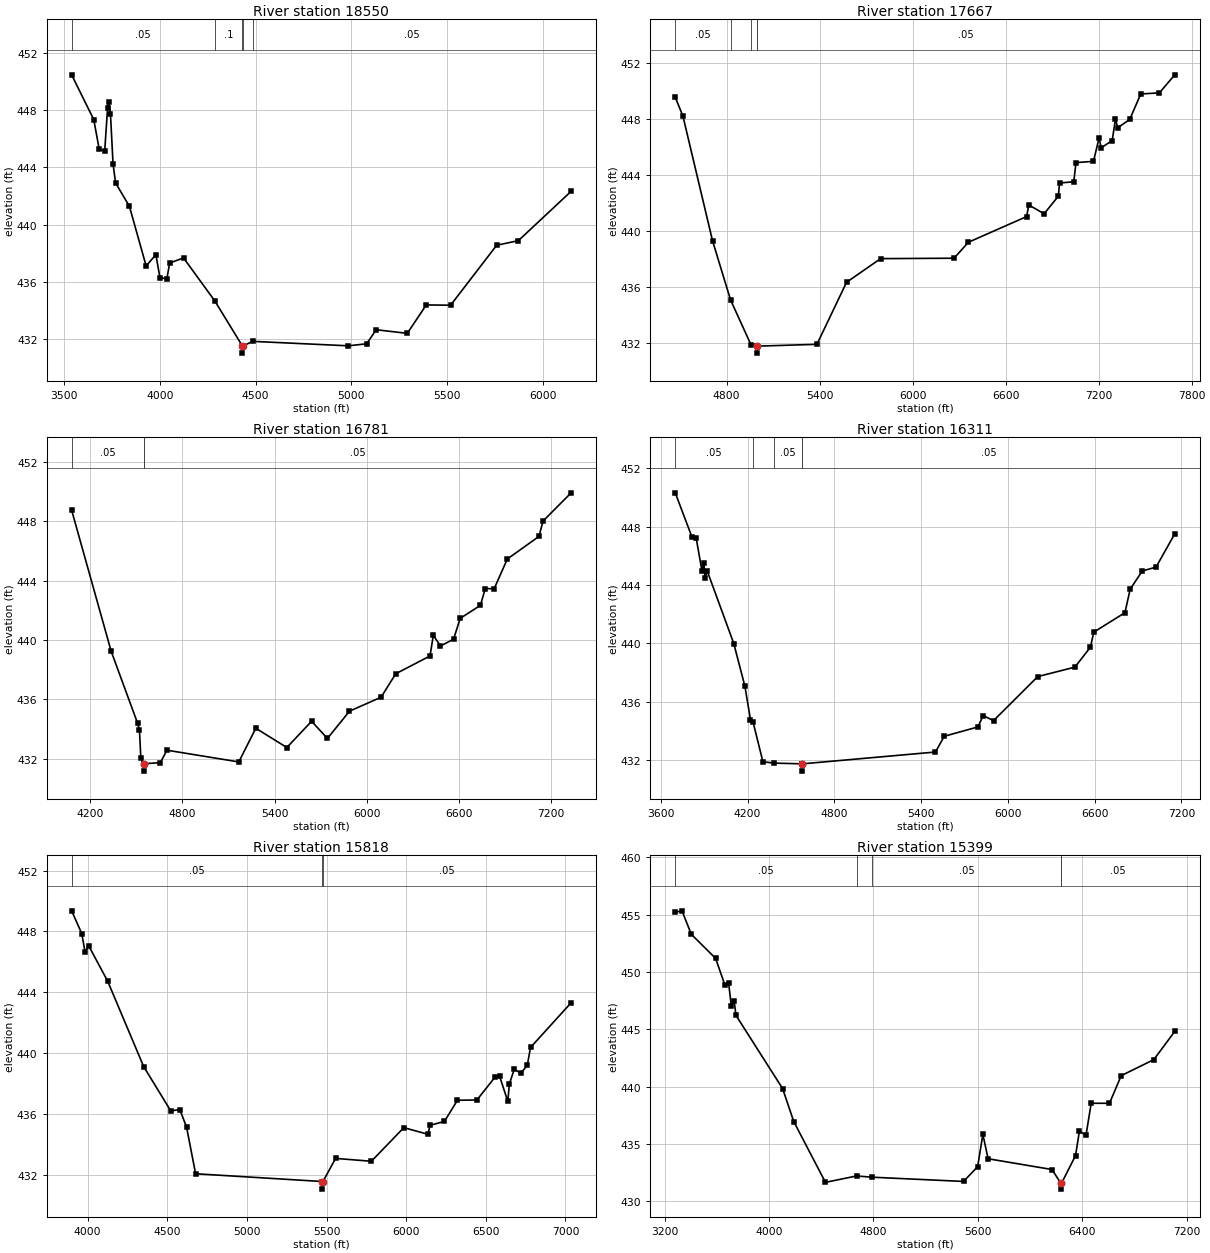
Type RM Length L Ch R = 1,18550,883,883,883
BEGIN DESCRIPTION:
Kauffman Branch 24.0
END DESCRIPTION:
XS GIS Cut Line= 3
      2654775.97      6908161.02      2653576.00      6908961.00
      2652726.03      6909760.97
#Sta/Elev= 30
  3538.9  450.45  3654.5  447.33  3683.1  445.25  3711.6  445.14  3726.6  448.11
  3732.7  448.56  3741.7  447.74  3755.2  444.23  3768.7  442.91  3840.8  441.28
  3928.0  437.13  3979.0  437.91  4000.1  436.32  4036.1  436.22  4051.1  437.33
  4123.3  437.69  4286.8  434.69  4430.7  431.55  4431.0  431.05  4434.7  431.55
  4484.3  431.87  4984.5  431.56  5080.0  431.70  5129.8  432.68  5292.4  432.43
  5391.6  434.41  5518.6  434.39  5759.3  438.57  5872.6  438.89  6148.3  442.33
#Mann=5,-1,0
  3538.9    0.05       0  4286.8     0.1       0  4430.7    0.03       0
  4434.7     0.1       0  4484.3    0.05       0
Bank Sta=4430.7,4434.7
Exp/Cntr=0.3,0.1

Type RM Length L Ch R = 1,17667,886,886,886
BEGIN DESCRIPTION:
Kauffman Branch 23.0
END DESCRIPTION:
XS GIS Cut Line= 3
      2654075.98      6907861.02      2653726.00      6908261.00
      2651926.00      6910261.00
#Sta/Elev= 30
  4468.8  449.56  4518.6  448.19  4709.4  439.28  4825.7  435.05  4957.2  431.85
  4994.9  431.75  4995.2  431.25  4999.0  431.75  5382.6  431.88  5573.9  436.32
  5793.7  438.01  6267.5  438.04  6359.5  439.18  6735.4  441.02  6749.3  441.85
  6848.3  441.22  6940.2  442.48  6947.7  443.42  7039.6  443.51  7053.8  444.88
  7166.7  444.97  7202.6  446.64  7216.8  445.94  7287.4  446.46  7308.7  447.99
  7322.9  447.37  7400.6  447.97  7471.6  449.79  7592.0  449.87  7691.0  451.16
#Mann=5,-1,0
  4468.8    0.05       0  4825.7     0.1       0  4957.2    0.05       0
  4994.9    0.03       0  4999.0    0.05       0
Bank Sta=4994.9,4999
Exp/Cntr=0.3,0.1

Type RM Length L Ch R = 1,16781,470,470,470
BEGIN DESCRIPTION:
Kauffman Branch 22.0
END DESCRIPTION:
XS GIS Cut Line= 3
      2653976.00      6907811.00      2653076.00      6908011.00
      2651876.02      6910010.97
#Sta/Elev= 30
  4077.8  448.75  4335.2  439.25  4508.0  434.38  4519.6  433.94  4528.5  432.07
  4546.9  431.67  4547.3  431.17  4551.1  431.67  4655.3  431.74  4698.8  432.58
  5166.9  431.79  5277.7  434.06  5479.8  432.76  5641.2  434.53  5744.2  433.37
  5888.0  435.21  6094.0  436.15  6189.3  437.73  6412.8  438.93  6434.2  440.32
  6480.8  439.60  6566.3  440.06  6609.1  441.46  6741.3  442.34  6772.4  443.47
  6830.7  443.46  6916.2  445.46  7122.2  446.98  7149.4  448.02  7332.1  449.92
#Mann=3,-1,0
  4077.8    0.05       0  4546.9    0.03       0  4551.1    0.05       0
Bank Sta=4546.9,4551.1
Exp/Cntr=0.3,0.1

Type RM Length L Ch R = 1,16311,493,493,493
BEGIN DESCRIPTION:
Kauffman Branch 21.0
END DESCRIPTION:
XS GIS Cut Line= 3
      2653225.99      6906511.02      2652726.00      6907711.00
      2651926.02      6909710.96
#Sta/Elev= 30
  3700.0  450.31  3815.4  447.28  3844.6  447.21  3884.1  444.98  3897.7  445.50
  3905.8  444.48  3921.5  444.94  4104.6  439.98  4181.5  437.05  4220.0  434.76
  4237.5  434.61  4306.1  431.87  4383.7  431.78  4575.4  431.73  4575.7  431.23
  4579.6  431.73  5499.5  432.54  5560.0  433.62  5792.9  434.26  5829.3  435.04
  5900.7  434.69  6206.3  437.71  6463.4  438.36  6571.1  439.73  6594.0  440.76
  6809.4  442.09  6845.7  443.70  6929.2  444.95  7024.8  445.22  7154.0  447.50
#Mann=5,-1,0
  3700.0    0.05       0  4237.5     0.1       0  4383.7    0.05       0
  4575.4    0.03       0  4579.6    0.05       0
Bank Sta=4575.4,4579.6
Exp/Cntr=0.3,0.1

Type RM Length L Ch R = 1,15818,419,419,419
BEGIN DESCRIPTION:
Kauffman Branch 20.0
END DESCRIPTION:
XS GIS Cut Line= 3
      2653125.97      6906561.03      2652376.00      6907361.00
      2651975.99      6909361.04
#Sta/Elev= 30
  3899.5  449.35  3963.2  447.85  3984.2  446.62  4005.7  447.07  4125.9  444.72
  4352.0  439.11  4522.0  436.20  4578.7  436.29  4621.2  435.13  4677.8  432.07
  5473.1  431.56  5473.6  431.06  5477.6  431.56  5556.9  433.08  5781.3  432.89
  5985.3  435.10  6138.2  434.66  6148.4  435.25  6240.2  435.51  6321.8  436.90
  6444.2  436.92  6556.3  438.40  6586.9  438.47  6637.9  436.83  6648.1  437.98
  6678.7  438.94  6719.5  438.68  6760.3  439.19  6780.7  440.37  7035.7  443.31
#Mann=3,-1,0
  3899.5    0.05       0  5473.1    0.03       0  5477.6    0.05       0
Bank Sta=5473.1,5477.6
Exp/Cntr=0.3,0.1

Type RM Length L Ch R = 1,15399,134,134,134
BEGIN DESCRIPTION:
Mapping XS 8a896e78
END DESCRIPTION:
XS GIS Cut Line= 5
      2653243.08      6906185.33      2652099.87      6907060.32
      2651972.34      6907308.43      2651774.34      6907841.57
      2651760.72      6909381.19
#Sta/Elev= 30
  3281.4  455.20  3333.1  455.33  3403.8  453.29  3590.7  451.18  3661.4  448.86
  3690.4  449.01  3711.2  446.99  3732.1  447.49  3746.6  446.21  4103.9  439.82
  4189.1  436.95  4432.1  431.64  4670.3  432.20  4790.2  432.09  5490.1  431.72
  5598.2  433.01  5638.2  435.83  5678.2  433.70  6168.2  432.76  6235.8  431.55
  6236.3  431.05  6240.5  431.55  6348.2  433.98  6378.2  436.12  6428.2  435.74
  6468.2  438.54  6608.2  438.54  6698.2  440.95  6948.2  442.35  7108.4  444.81
#Mann=5,-1,0
  3281.4    0.05       0  4670.3     0.1       0  4790.2    0.05       0
  6235.8    0.03       0  6240.5    0.05       0
Bank Sta=6235.8,6240.5
Exp/Cntr=0.3,0.1

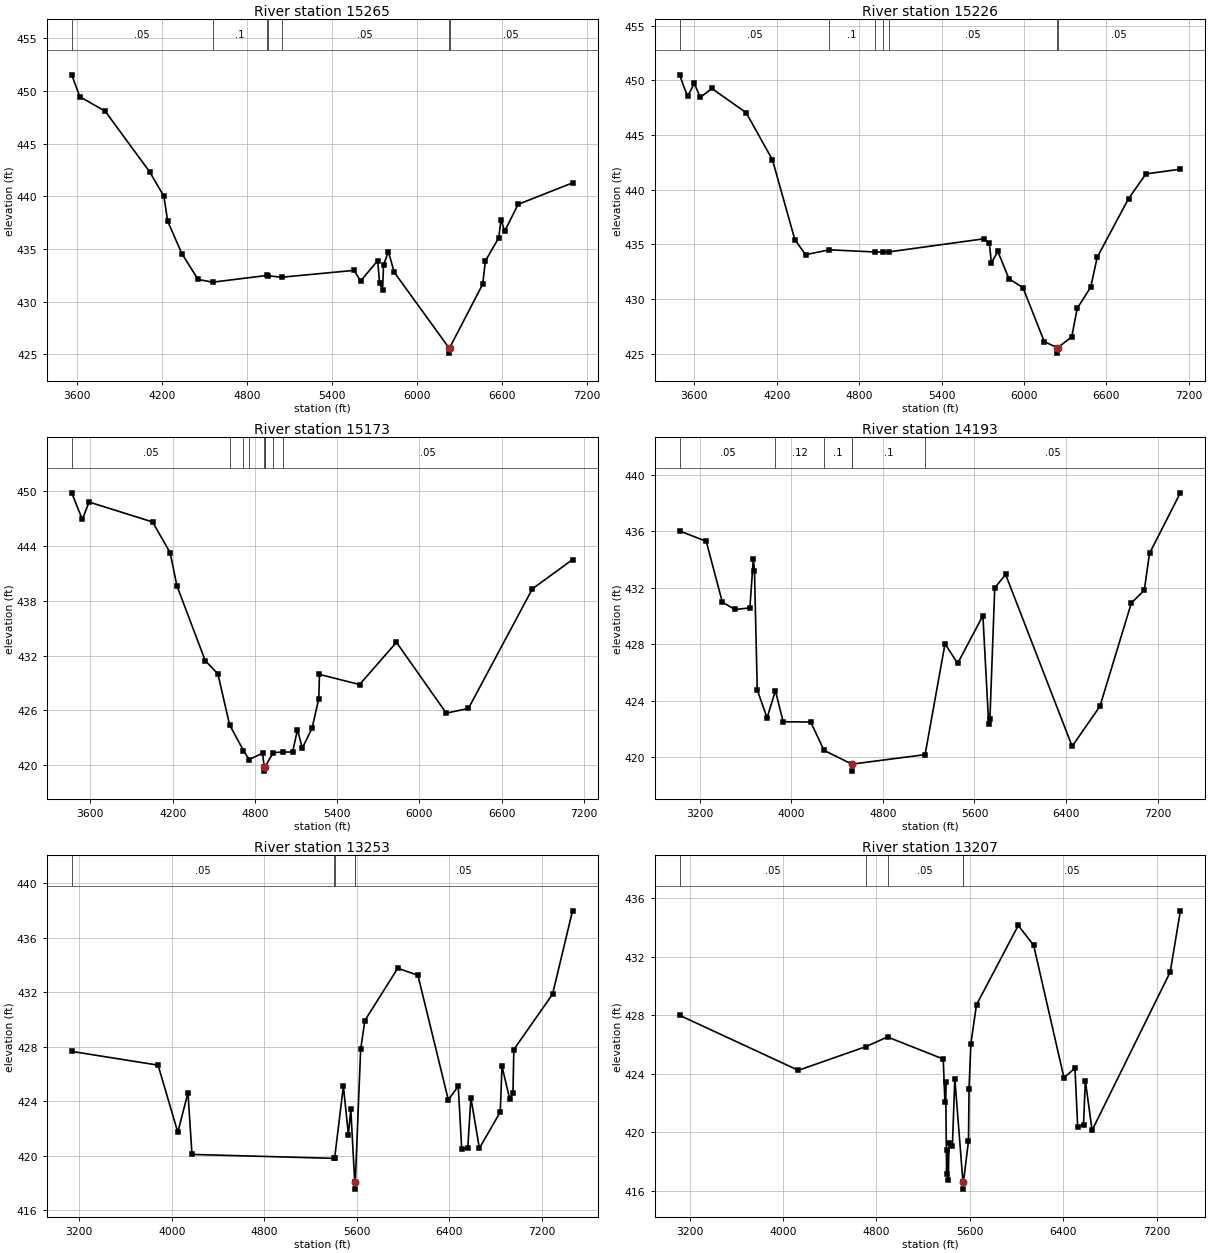
Type RM Length L Ch R = 1,15265,39,39,39
BEGIN DESCRIPTION:
Mapping XS f5b7516a
END DESCRIPTION:
XS GIS Cut Line= 6
      2652946.54      6906311.29      2652175.71      6906891.16
      2651481.27      6907651.57      2651342.38      6907807.82
      2651311.13      6908040.46      2651643.98      6909087.56
#Sta/Elev= 30
  3563.5  451.52  3620.9  449.44  3799.9  448.07  4114.4  442.31  4214.4  440.01
  4241.4  437.63  4341.4  434.56  4455.9  432.11  4559.6  431.85  4942.5  432.49
  4948.7  432.46  5046.2  432.32  5557.9  432.97  5603.7  431.96  5724.1  433.89
  5738.3  431.74  5759.2  431.14  5765.7  433.49  5800.4  434.74  5840.8  432.80
  6227.7  425.62  6228.2  425.12  6232.4  425.62  6466.3  431.67  6484.9  433.86
  6579.4  436.06  6595.3  437.79  6621.3  436.69  6715.8  439.23  7100.4  441.27
#Mann=7,-1,0
  3563.5    0.05       0  4559.6     0.1       0  4942.5    0.05       0
  4948.7     0.1       0  5046.2    0.05       0  6227.7    0.07       0
  6232.4    0.05       0
Bank Sta=6227.7,6232.4
Exp/Cntr=0.3,0.1

Type RM Length L Ch R = 1,15226,53,53,53
BEGIN DESCRIPTION:
Mapping XS f41f0407
END DESCRIPTION:
XS GIS Cut Line= 6
      2652945.40      6906218.99      2652150.28      6906864.82
      2651653.75      6907406.48      2651306.53      6907791.90
      2651261.39      6908048.84      2651577.37      6909111.35
#Sta/Elev= 30
  3492.1  450.51  3550.1  448.53  3599.6  449.73  3642.7  448.44  3727.5  449.26
  3976.7  447.05  4168.5  442.74  4331.6  435.44  4409.9  434.06  4582.2  434.51
  4913.8  434.31  4971.9  434.31  5017.4  434.32  5705.9  435.51  5748.5  435.13
  5762.7  433.30  5809.7  434.37  5890.9  431.86  5992.5  431.06  6147.9  426.12
  6241.2  425.56  6241.7  425.06  6245.9  425.56  6348.3  426.54  6387.9  429.15
  6486.3  431.09  6533.9  433.83  6762.2  439.19  6888.6  441.45  7139.4  441.88
#Mann=7,-1,0
  3492.1    0.05       0  4582.2     0.1       0  4913.8    0.05       0
  4971.9     0.1       0  5017.4    0.05       0  6241.2    0.07       0
  6245.9    0.05       0
Bank Sta=6241.2,6245.9
Exp/Cntr=0.3,0.1

Type RM Length L Ch R = 1,15173,980,980,980
BEGIN DESCRIPTION:
Mapping XS 334406ec
END DESCRIPTION:
XS GIS Cut Line= 6
      2652920.71      6906177.40      2652129.05      6906809.34
      2651594.33      6907396.15      2651271.42      6907750.31
      2651219.33      6908031.56      2651504.04      6909073.19
#Sta/Elev= 30
  3464.0  449.83  3541.2  446.91  3590.8  448.82  4053.5  446.64  4181.6  443.28
  4231.3  439.65  4437.8  431.45  4530.0  430.01  4615.3  424.43  4716.6  421.61
  4757.1  420.63  4855.7  421.32  4867.5  419.86  4868.0  419.36  4872.2  419.86
  4874.0  419.86  4934.0  421.38  5004.0  421.46  5074.6  421.44  5110.4  423.91
  5145.5  421.88  5216.5  424.05  5265.8  427.30  5270.7  429.95  5563.1  428.84
  5832.2  433.46  6195.2  425.71  6356.9  426.22  6823.5  439.32  7116.0  442.52
#Mann=9,-1,0
  3464.0    0.05       0  4615.3     0.1       0  4716.6    0.12       0
  4757.1     0.1       0  4867.5    0.07       0  4872.2     0.1       0
  4874.0    0.05       0  4934.0     0.1       0  5004.0    0.05       0
Bank Sta=4867.5,4872.2
Exp/Cntr=0.3,0.1

Type RM Length L Ch R = 1,14193,940,940,940
BEGIN DESCRIPTION:
Kauffman Branch 18.0
END DESCRIPTION:
XS GIS Cut Line= 3
      2650996.60      6905028.34      2650776.00      6907711.00
      2651322.97      6909306.01
#Sta/Elev= 30
  3021.9  436.03  3255.3  435.29  3395.8  430.98  3506.2  430.46  3636.6  430.57
  3666.7  434.04  3676.8  433.20  3701.1  424.75  3787.1  422.78  3859.8  424.70
  3927.6  422.50  4168.4  422.48  4284.7  420.47  4527.3  419.50  4527.8  419.00
  4532.0  419.50  5168.2  420.17  5342.4  428.03  5452.7  426.64  5673.5  430.02
  5724.0  422.35  5734.8  422.70  5777.0  431.99  5872.2  432.94  6453.6  420.76
  6696.8  423.60  6971.6  430.93  7084.0  431.81  7130.2  434.44  7399.8  438.73
#Mann=6,-1,0
  3021.9    0.05       0  3859.8    0.12       0  4284.7     0.1       0
  4527.3    0.07       0  4532.0     0.1       0  5168.2    0.05       0
Bank Sta=4527.3,4532
Exp/Cntr=0.3,0.1

Type RM Length L Ch R = 1,13253,46,46,46
BEGIN DESCRIPTION:
Mapping XS 32876de1
END DESCRIPTION:
XS GIS Cut Line= 6
      2648751.15      6905849.99      2649334.93      6906489.12
      2649338.06      6906626.95      2649968.57      6907287.47
      2650325.16      6907699.75      2651301.03      6909293.81
#Sta/Elev= 30
  3135.2  427.65  3882.2  426.64  4052.7  421.71  4140.8  424.61  4175.4  420.08
  5404.5  419.79  5409.0  419.80  5484.9  425.10  5528.2  421.53  5549.0  423.39
  5583.0  418.03  5583.5  417.53  5587.7  418.03  5634.2  427.80  5670.7  429.92
  5955.1  433.76  6129.2  433.25  6392.2  424.10  6478.4  425.09  6508.3  420.47
  6560.5  420.54  6587.7  424.24  6661.1  420.53  6841.9  423.20  6856.6  426.56
  6923.9  424.13  6951.3  424.61  6959.1  427.79  7293.7  431.85  7466.6  437.98
#Mann=5,-1,0
  3135.2    0.05       0  5404.5     0.1       0  5409.0    0.05       0
  5583.0    0.03       0  5587.7    0.05       0
Bank Sta=5583,5587.7
Exp/Cntr=0.3,0.1

Type RM Length L Ch R = 1,13207,43,43,43
BEGIN DESCRIPTION:
Kauffman Branch 17.0
END DESCRIPTION:
XS GIS Cut Line= 6
      2648712.10      6905844.58      2649305.64      6906491.29
      2649325.02      6906683.00      2650042.61      6907423.27
      2650276.00      6907711.00      2651226.00      6909261.01
#Sta/Elev= 30
  3114.4  428.00  4131.5  424.24  4711.5  425.86  4895.6  426.52  5373.0  425.01
  5387.4  422.08  5393.9  423.45  5401.8  417.16  5408.2  418.82  5416.2  416.71
  5422.6  419.24  5451.4  419.05  5472.2  423.68  5541.7  416.62  5542.2  416.12
  5546.4  416.62  5589.4  419.41  5594.1  422.99  5609.6  426.06  5658.0  428.72
  6015.8  434.14  6147.2  432.79  6407.4  423.73  6501.3  424.39  6524.7  420.39
  6574.7  420.52  6590.2  423.53  6648.2  420.14  7317.4  430.96  7404.4  435.14
#Mann=5,-1,0
  3114.4    0.05       0  4711.5    0.12       0  4895.6    0.05       0
  5541.7    0.03       0  5546.4    0.05       0
Bank Sta=5541.7,5546.4
Exp/Cntr=0.3,0.1

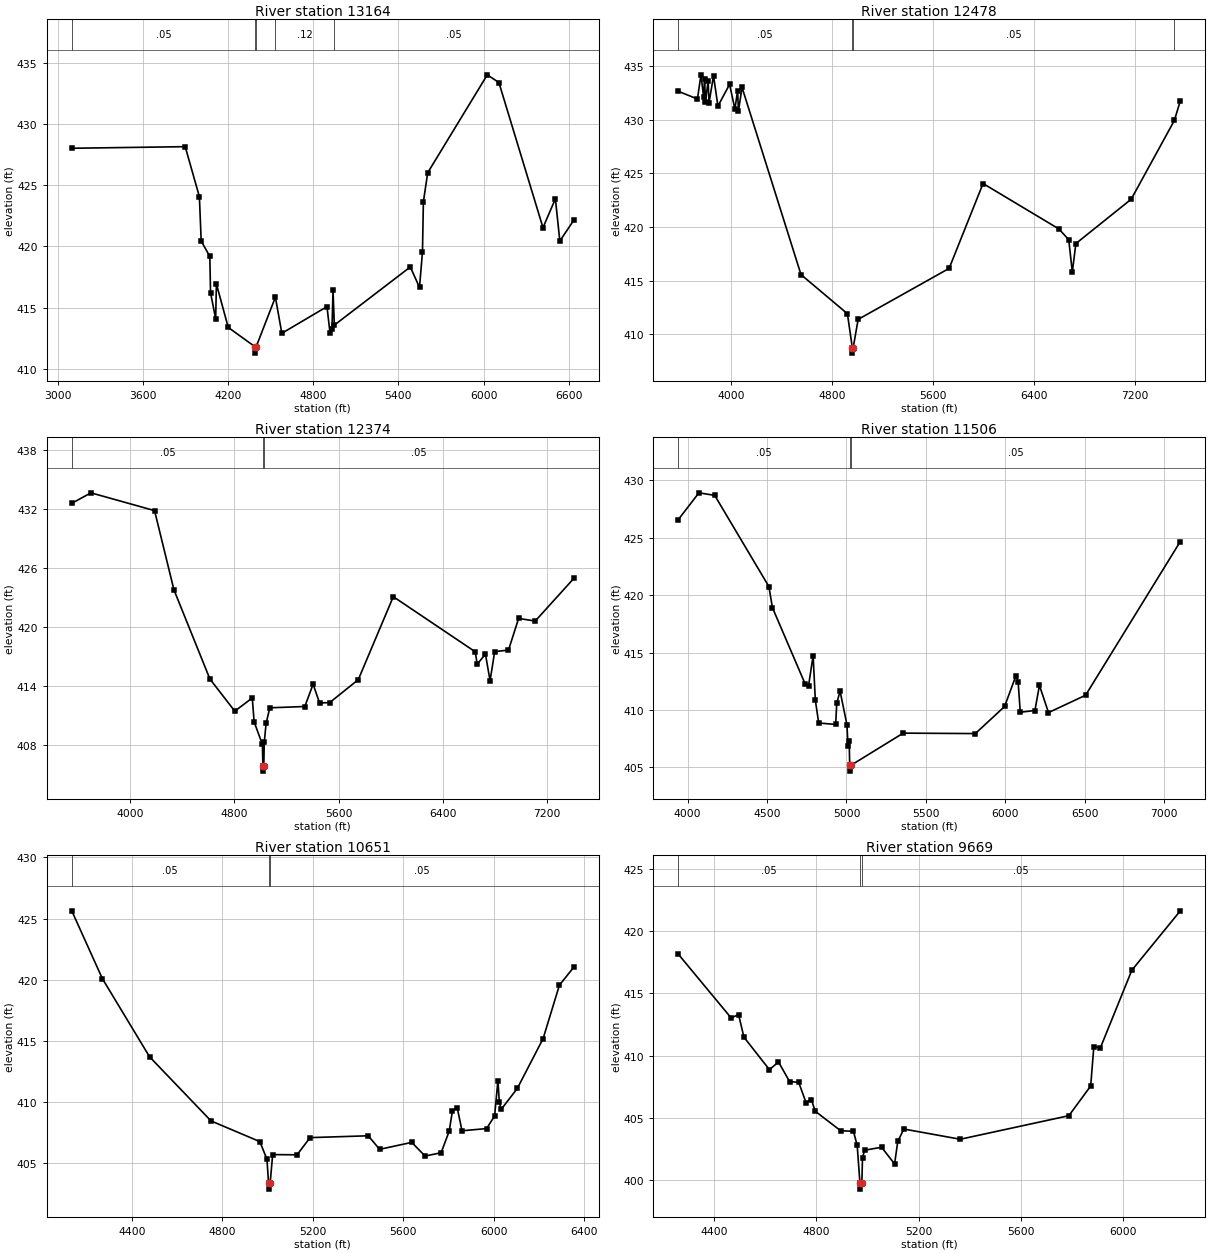
Type RM Length L Ch R = 1,13164,686,686,686
BEGIN DESCRIPTION:
Mapping XS fd651ba2
END DESCRIPTION:
XS GIS Cut Line= 6
      2648666.51      6905853.24      2649258.98      6906548.80
      2649267.93      6906696.00      2649303.47      6906761.47
      2650196.69      6907658.08      2650744.40      6908647.74
#Sta/Elev= 30
  3099.2  428.02  3898.4  428.15  3998.3  424.06  4011.0  420.44  4071.8  419.18
  4076.9  416.21  4113.1  414.07  4118.1  416.94  4201.5  413.38  4392.9  411.78
  4393.4  411.28  4397.6  411.78  4533.8  415.85  4579.1  412.90  4897.2  415.08
  4918.5  412.94  4932.6  413.25  4939.7  416.40  4949.1  413.57  5484.2  418.32
  5549.1  416.65  5570.0  419.57  5576.4  423.65  5606.8  426.02  6026.7  434.02
  6108.4  433.39  6419.0  421.53  6506.4  423.89  6537.7  420.44  6636.4  422.15
#Mann=5,-1,0
  3099.2    0.05       0  4392.9    0.03       0  4397.6    0.05       0
  4533.8    0.12       0  4949.1    0.05       0
Bank Sta=4392.9,4397.6
Exp/Cntr=0.3,0.1

Type RM Length L Ch R = 1,12478,104,104,104
BEGIN DESCRIPTION:
Mapping XS 49a841c5
END DESCRIPTION:
XS GIS Cut Line= 3
      2648316.67      6906515.48      2649301.07      6907551.96
      2651087.54      6909369.68
#Sta/Elev= 30
  3582.0  432.63  3734.0  431.91  3762.3  434.16  3783.3  432.05  3790.6  433.80
  3797.5  431.64  3818.9  433.60  3825.8  431.53  3861.4  434.07  3896.6  431.25
  3988.8  433.27  4030.9  430.98  4052.3  432.67  4059.2  430.80  4087.5  432.99
  4554.7  415.56  4922.4  411.92  4961.4  408.75  4962.5  408.25  4968.2  408.75
  5007.3  411.39  5728.4  416.14  5997.2  424.04  6598.2  419.81  6676.1  418.81
  6704.4  415.80  6732.6  418.45  7171.0  422.58  7512.9  429.91  7560.1  431.74
#Mann=4,-1,0
  3582.0    0.05       0  4961.4    0.03       0  4968.2    0.05       0
  7512.9   0.075       0
Bank Sta=4961.4,4968.2
Exp/Cntr=0.3,0.1

Type RM Length L Ch R = 1,12374,868,868,868
BEGIN DESCRIPTION:
Mapping XS 9509eb50
END DESCRIPTION:
XS GIS Cut Line= 3
      2648199.66      6906509.46      2649194.42      6907561.51
      2650881.46      6909274.59
#Sta/Elev= 30
  3552.6  432.60  3699.7  433.67  4187.8  431.86  4336.4  423.81  4612.3  414.74
  4803.3  411.47  4937.6  412.81  4951.7  410.38  5015.3  408.09  5019.1  405.87
  5020.2  405.37  5025.9  405.87  5029.5  408.30  5043.6  410.22  5071.9  411.81
  5340.6  411.94  5404.3  414.21  5453.8  412.30  5531.6  412.34  5750.8  414.67
  6019.5  423.11  6648.8  417.50  6663.0  416.24  6726.6  417.27  6762.0  414.56
  6797.3  417.52  6903.4  417.68  6981.2  420.90  7108.4  420.63  7404.8  424.97
#Mann=3,-1,0
  3552.6    0.05       0  5019.1    0.03       0  5025.9    0.05       0
Bank Sta=5019.1,5025.9
Exp/Cntr=0.3,0.1

Type RM Length L Ch R = 1,11506,855,855,855
BEGIN DESCRIPTION:
Kauffman Branch 14.0
END DESCRIPTION:
XS GIS Cut Line= 3
      2647851.39      6907452.98      2648676.00      6908111.00
      2650054.56      6909703.02
#Sta/Elev= 30
  3940.7  426.57  4071.0  428.91  4170.2  428.69  4511.3  420.75  4533.7  418.91
  4739.8  412.26  4761.1  412.11  4789.9  414.73  4803.8  410.85  4825.1  408.86
  4931.7  408.74  4938.8  410.60  4959.6  411.63  5002.8  408.72  5009.4  406.84
  5017.0  407.26  5020.2  405.17  5021.3  404.67  5027.1  405.17  5357.1  407.98
  5811.1  407.94  5995.3  410.30  6066.6  412.98  6080.4  412.47  6094.1  409.80
  6186.2  409.95  6214.7  412.14  6271.7  409.77  6505.3  411.28  7101.6  424.67
#Mann=3,-1,0
  3940.7    0.05       0  5020.2    0.03       0  5027.1    0.05       0
Bank Sta=5020.2,5027.1
Exp/Cntr=0.3,0.1

Type RM Length L Ch R = 1,10651,982,982,982
BEGIN DESCRIPTION:
Kauffman Branch 12.0
END DESCRIPTION:
XS GIS Cut Line= 3
      2647875.99      6908060.98      2648376.00      6908761.00
      2649176.00      6909861.00
#Sta/Elev= 30
  4134.2  425.63  4269.4  420.08  4478.3  413.67  4749.9  408.42  4966.2  406.72
  4997.5  405.26  5004.4  403.33  5005.6  402.83  5011.5  403.33  5022.7  405.66
  5130.5  405.64  5188.0  407.05  5445.4  407.20  5495.6  406.09  5637.8  406.66
  5696.6  405.54  5767.6  405.81  5803.2  407.57  5817.9  409.26  5838.7  409.51
  5860.0  407.61  5968.6  407.79  6004.1  408.82  6018.8  411.72  6025.0  409.98
  6033.1  409.36  6104.6  411.08  6218.6  415.16  6290.8  419.54  6354.6  421.02
#Mann=3,-1,0
  4134.2    0.05       0  5004.4    0.04       0  5011.5    0.05       0
Bank Sta=5004.4,5011.5
Exp/Cntr=0.3,0.1

Type RM Length L Ch R = 1,9669,978,978,978
BEGIN DESCRIPTION:
Kauffman Branch 10.0
END DESCRIPTION:
XS GIS Cut Line= 3
      2647425.99      6908960.98      2647874.22      6909549.02
      2649025.96      6909960.99
#Sta/Elev= 30
  4260.6  418.15  4467.5  413.03  4496.5  413.30  4517.3  411.49  4617.1  408.88
  4652.5  409.50  4696.1  407.92  4731.4  407.87  4760.5  406.22  4781.3  406.48
  4795.9  405.55  4895.7  403.98  4945.5  403.94  4960.1  402.81  4970.8  399.80
  4972.0  399.30  4978.4  399.80  4980.9  401.83  4989.2  402.42  5055.4  402.66
  5106.3  401.32  5118.7  403.12  5142.4  404.12  5363.0  403.30  5787.6  405.19
  5872.8  407.57  5885.2  410.73  5910.7  410.63  6033.8  416.86  6223.2  421.62
#Mann=3,-1,0
  4260.6    0.05       0  4970.8    0.04       0  4978.4    0.05       0
Bank Sta=4970.8,4978.4
Exp/Cntr=0.3,0.1

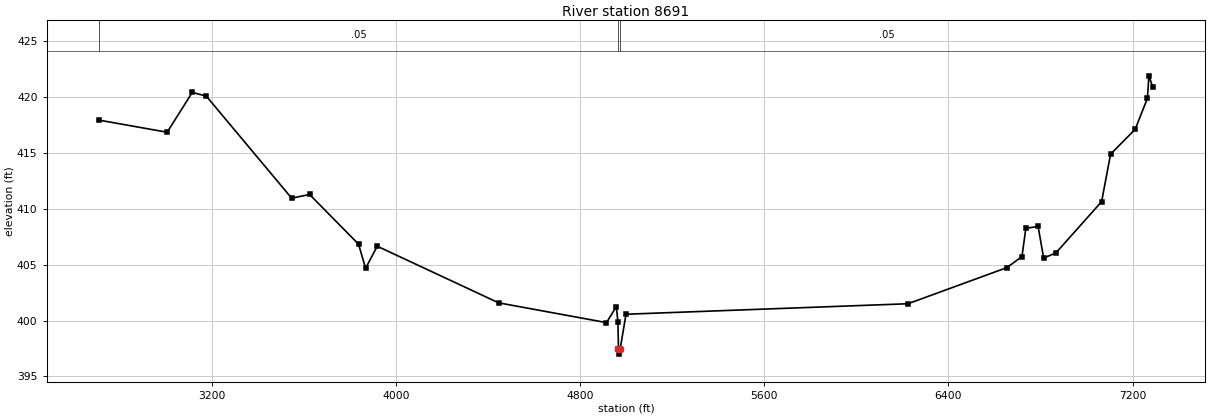
Type RM Length L Ch R = 1,8691,0,0,0
BEGIN DESCRIPTION:
Mapping XS da72169e
END DESCRIPTION:
XS GIS Cut Line= 5
      2646674.34      6907890.50      2647023.30      6909989.46
      2647127.46      6910119.67      2648106.63      6911025.92
      2648981.32      6911385.17
#Sta/Elev= 30
  2712.7  417.94  3007.2  416.86  3116.4  420.43  3177.3  420.09  3547.8  410.96
  3625.6  411.29  3838.4  406.84  3868.9  404.68  3919.5  406.66  4446.7  401.59
  4914.9  399.82  4957.7  401.25  4964.5  399.91  4967.0  397.50  4968.2  397.00
  4974.7  397.50  4999.7  400.57  6224.2  401.51  6653.1  404.74  6719.1  405.73
  6735.9  408.26  6789.2  408.43  6813.2  405.60  6866.5  406.06  7065.0  410.65
  7103.9  414.90  7210.6  417.12  7263.9  419.90  7270.4  421.91  7287.0  420.90
#Mann=3,-1,0
  2712.7    0.05       0  4967.0    0.04       0  4974.7    0.05       0
Bank Sta=4967,4974.7
Exp/Cntr=0.3,0.1

Chan Stop Cuts=-1