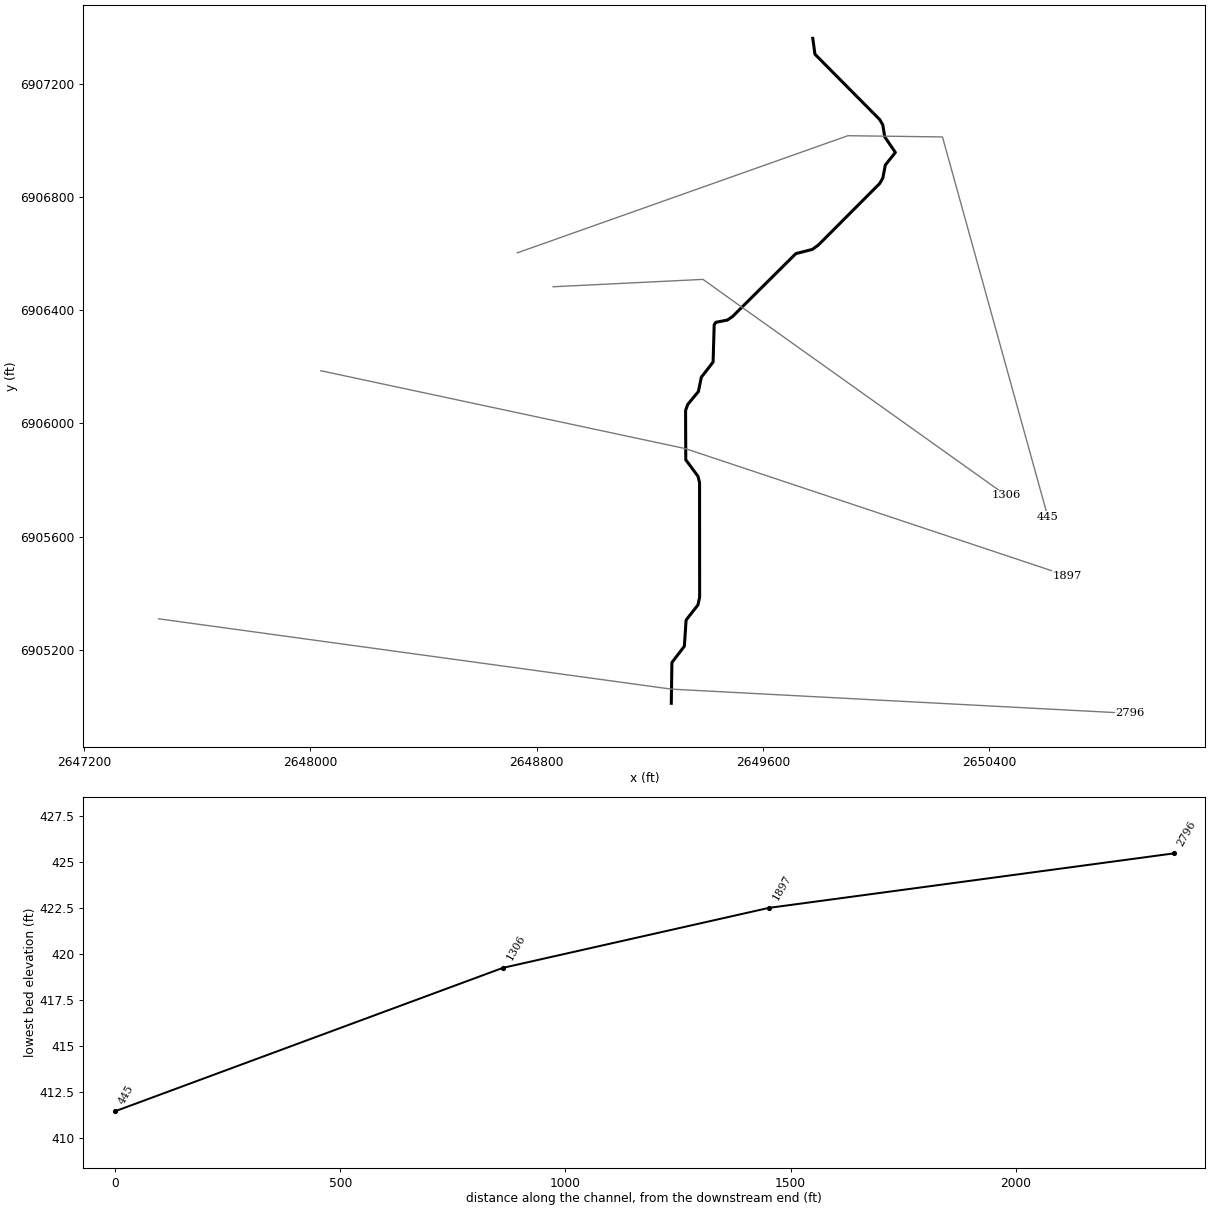
--- Kauffman Branch Trib 1.prj (project) ---

Proj Title=Kauffman Branch Trib 1 Base Level Engineering
Current Plan=p01
Default Exp/Contr=0.3,0.1
English Units
Geom File=g01
Flow File=f01
Plan File=p01
BEGIN DESCRIPTION:
Kauffman Branch Trib 1
END DESCRIPTION:

--- Kauffman Branch Trib 1.p01 (plan) ---

Plan Title=Multiple Run
Short Identifier=Multiple
Geom File=g01
Flow File=f01
Subcritical Flow
K Sum by GR= 0
Std Step Tol= 0.01
Critical Tol= 0.01
Num of Std Step Trials= 20
Max Error Tol= 0.3
Flow Tol Ratio= 0.001
Split Flow NTrial= 30
Split Flow Tol= 0.02
Split Flow Ratio= 0.02
Log Output Level= 0
Friction Slope Method= 1
Unsteady Friction Slope Method= 2
Unsteady Bridges Friction Slope Method= 1
Parabolic Critical Depth
Global Vel Dist=  1 , 1 , 1
Global Log Level= 0
CheckData=True
Encroach Param= -1, 0, 0, 0
BEGIN DESCRIPTION:
Multiple Run
END DESCRIPTION:

--- Kauffman Branch Trib 1.f01 (steady flow) ---

Flow Title=Multiple
Number of Profiles=7
Profile Names=10-year,25-year,50-year,1pct_min,100-year,1pct_plu,500-year
River Rch & RM= Kauffman Branch ,Reach-1,2796
     371     481     567     332     663    1322     903
Boundary for River Rch & Prof#=Kauffman Branch ,Reach-1,1
Up Type=0
Dn Type=3
Dn Slope=0.005
Boundary for River Rch & Prof#=Kauffman Branch ,Reach-1,2
Up Type=0
Dn Type=3
Dn Slope=0.005
Boundary for River Rch & Prof#=Kauffman Branch ,Reach-1,3
Up Type=0
Dn Type=3
Dn Slope=0.005
Boundary for River Rch & Prof#=Kauffman Branch ,Reach-1,4
Up Type=0
Dn Type=3
Dn Slope=0.005
Boundary for River Rch & Prof#=Kauffman Branch ,Reach-1,5
Up Type=0
Dn Type=3
Dn Slope=0.005
Boundary for River Rch & Prof#=Kauffman Branch ,Reach-1,6
Up Type=0
Dn Type=3
Dn Slope=0.005
Boundary for River Rch & Prof#=Kauffman Branch ,Reach-1,7
Up Type=0
Dn Type=3
Dn Slope=0.005

--- Kauffman Branch Trib 1.g01 (geometry) ---

Geom Title=Existing Conditions

River Reach=Kauffman Branch ,Reach-1
Reach XY= 30
      2649276.00      6905011.00      2649278.22      6905155.08
      2649322.15      6905212.60      2649328.36      6905305.02
      2649370.26      6905358.66      2649376.20      6905385.92
      2649375.93      6905790.97      2649370.25      6905813.33
      2649327.22      6905871.51      2649326.51      6906045.79
      2649334.09      6906067.07      2649371.81      6906112.74
      2649382.12      6906163.18      2649423.75      6906216.94
      2649427.64      6906349.17      2649434.11      6906357.61
      2649473.91      6906365.16      2649492.45      6906377.74
      2649716.32      6906600.22      2649774.35      6906614.98
      2649796.09      6906630.79      2650012.39      6906847.79
      2650023.54      6906867.05      2650032.42      6906913.28
      2650067.98      6906957.69      2650030.46      6907012.65
      2650023.54      6907054.95      2650012.39      6907074.21
      2649783.76      6907304.79      2649776.00      6907361.00

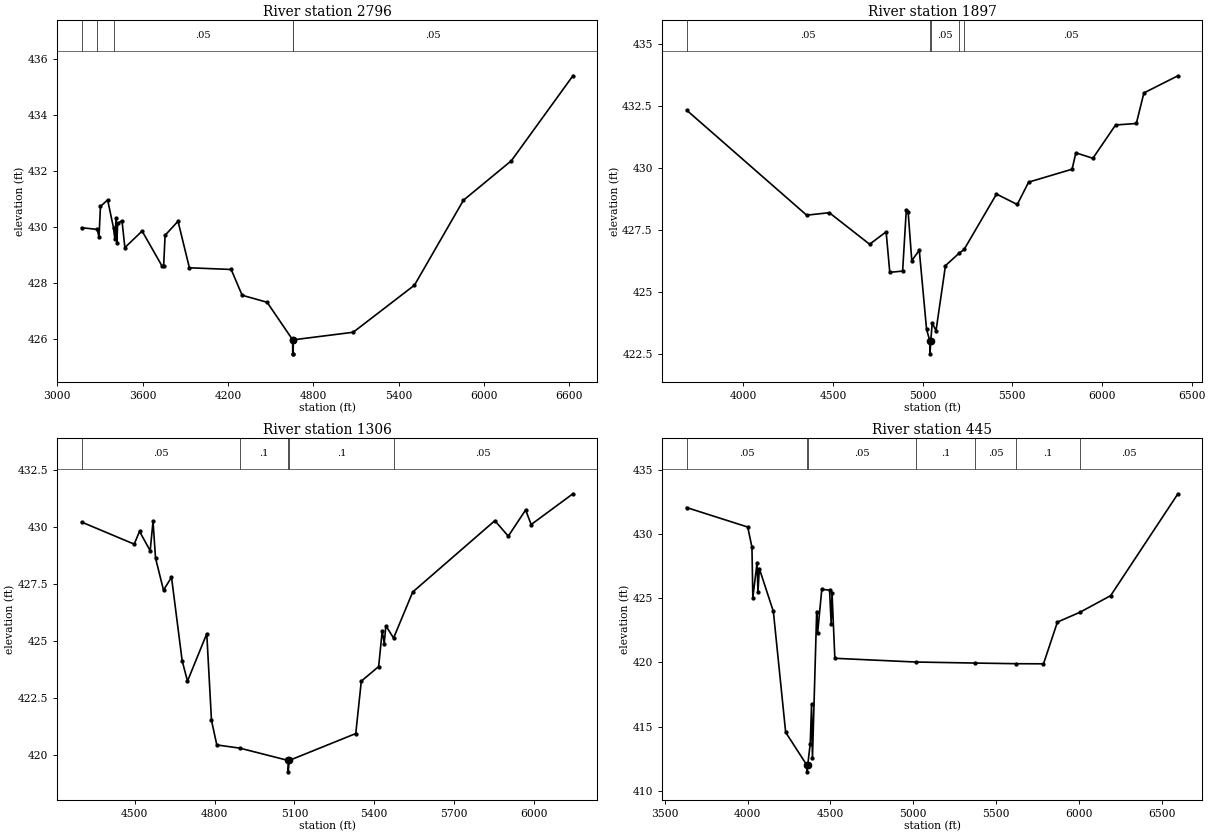
Type RM Length L Ch R = 1,2796,899,899,899
BEGIN DESCRIPTION:
Kaufman Branch 4.0
END DESCRIPTION:
XS GIS Cut Line= 3
      2647464.45      6905309.52      2649275.89      6905061.05
      2650897.62      6904975.32
#Sta/Elev= 30
  3171.6  429.98  3282.1  429.92  3294.3  429.64  3304.4  430.74  3354.9  430.97
  3396.4  429.97  3405.3  429.59  3414.3  430.32  3419.4  429.45  3425.5  430.13
  3455.8  430.23  3476.0  429.27  3597.1  429.86  3738.4  428.60  3748.5  428.62
  3758.6  429.71  3849.4  430.21  3929.3  428.55  4222.8  428.49  4300.0  427.57
  4475.2  427.32  4654.9  425.98  4655.2  425.48  4658.7  425.48  4658.9  425.98
  5080.2  426.25  5510.8  427.93  5854.8  430.96  6191.8  432.37  6624.0  435.40
#Mann=5,-1,0
  3171.6    0.05       0  3282.1   0.075       0  3396.4    0.05       0
  4654.9    0.03       0  4658.9    0.05       0
Bank Sta=4654.9,4658.9
Exp/Cntr=0.3,0.1

Type RM Length L Ch R = 1,1897,591,591,591
BEGIN DESCRIPTION:
Kaufman Branch 3.0
END DESCRIPTION:
XS GIS Cut Line= 3
      2648037.37      6906186.26      2649326.00      6905911.00
      2650675.98      6905461.01
#Sta/Elev= 30
  3682.7  432.33  4352.6  428.10  4478.9  428.20  4703.9  426.93  4795.9  427.43
  4816.3  425.80  4887.9  425.85  4908.4  428.31  4918.6  428.24  4939.0  426.27
  4980.8  426.69  5021.5  423.50  5040.6  423.02  5040.8  422.52  5044.6  423.02
  5053.1  423.76  5074.2  423.45  5126.9  426.07  5204.8  426.58  5230.8  426.72
  5411.5  428.95  5527.4  428.53  5590.7  429.43  5833.1  429.95  5854.2  430.61
  5949.1  430.39  6075.6  431.73  6191.5  431.79  6233.7  433.02  6423.4  433.71
#Mann=5,-1,0
  3682.7    0.05       0  5040.6    0.03       0  5044.6    0.05       0
  5204.8    0.12       0  5230.8    0.05       0
Bank Sta=5040.6,5044.6
Exp/Cntr=0.3,0.1

Type RM Length L Ch R = 1,1306,861,861,861
BEGIN DESCRIPTION:
Mapping XS 8ca2126a
END DESCRIPTION:
XS GIS Cut Line= 4
      2648858.47      6906483.03      2649388.00      6906509.07
      2649539.91      6906400.56      2650459.45      6905745.61
#Sta/Elev= 30
  4300.4  430.22  4498.2  429.25  4518.2  429.81  4558.2  428.96  4568.9  430.25
  4578.3  428.64  4608.3  427.23  4638.3  427.80  4678.4  424.13  4698.4  423.24
  4770.8  425.32  4788.5  421.52  4808.5  420.44  4895.0  420.30  5076.4  419.76
  5076.7  419.26  5080.4  419.76  5330.5  420.94  5351.3  423.24  5416.5  423.88
  5429.9  425.45  5437.4  424.89  5443.6  425.67  5472.5  425.13  5544.4  427.15
  5853.0  430.28  5903.4  429.60  5968.5  430.75  5989.4  430.11  6146.2  431.46
#Mann=5,-1,0
  4300.4    0.05       0  4895.0     0.1       0  5076.4    0.07       0
  5080.4     0.1       0  5472.5    0.05       0
Bank Sta=5076.4,5080.4
Exp/Cntr=0.3,0.1

Type RM Length L Ch R = 1,445,0,0,0
BEGIN DESCRIPTION:
Mapping XS 5ffe4987
END DESCRIPTION:
XS GIS Cut Line= 4
      2648731.85      6906602.93      2649900.15      6907016.88
      2650234.35      6907012.54      2650606.84      6905669.74
#Sta/Elev= 30
  3631.1  432.05  4000.6  430.53  4026.1  428.96  4031.4  425.04  4057.0  427.75
  4062.3  425.45  4070.5  427.30  4155.3  423.96  4229.6  414.55  4358.6  411.97
  4358.8  411.47  4362.6  411.97  4378.1  413.67  4386.1  416.73  4391.4  412.53
  4417.0  423.95  4422.3  422.26  4447.9  425.68  4494.8  425.62  4504.4  423.01
  4509.7  425.39  4526.7  420.31  5014.9  420.02  5375.1  419.94  5621.1  419.89
  5786.6  419.88  5870.7  423.13  6007.6  423.90  6192.3  425.19  6598.3  433.12
#Mann=7,-1,0
  3631.1    0.05       0  4358.6    0.03       0  4362.6    0.05       0
  5014.9     0.1       0  5375.1    0.05       0  5621.1     0.1       0
  6007.6    0.05       0
Bank Sta=4358.6,4362.6
Exp/Cntr=0.3,0.1

Chan Stop Cuts=-1