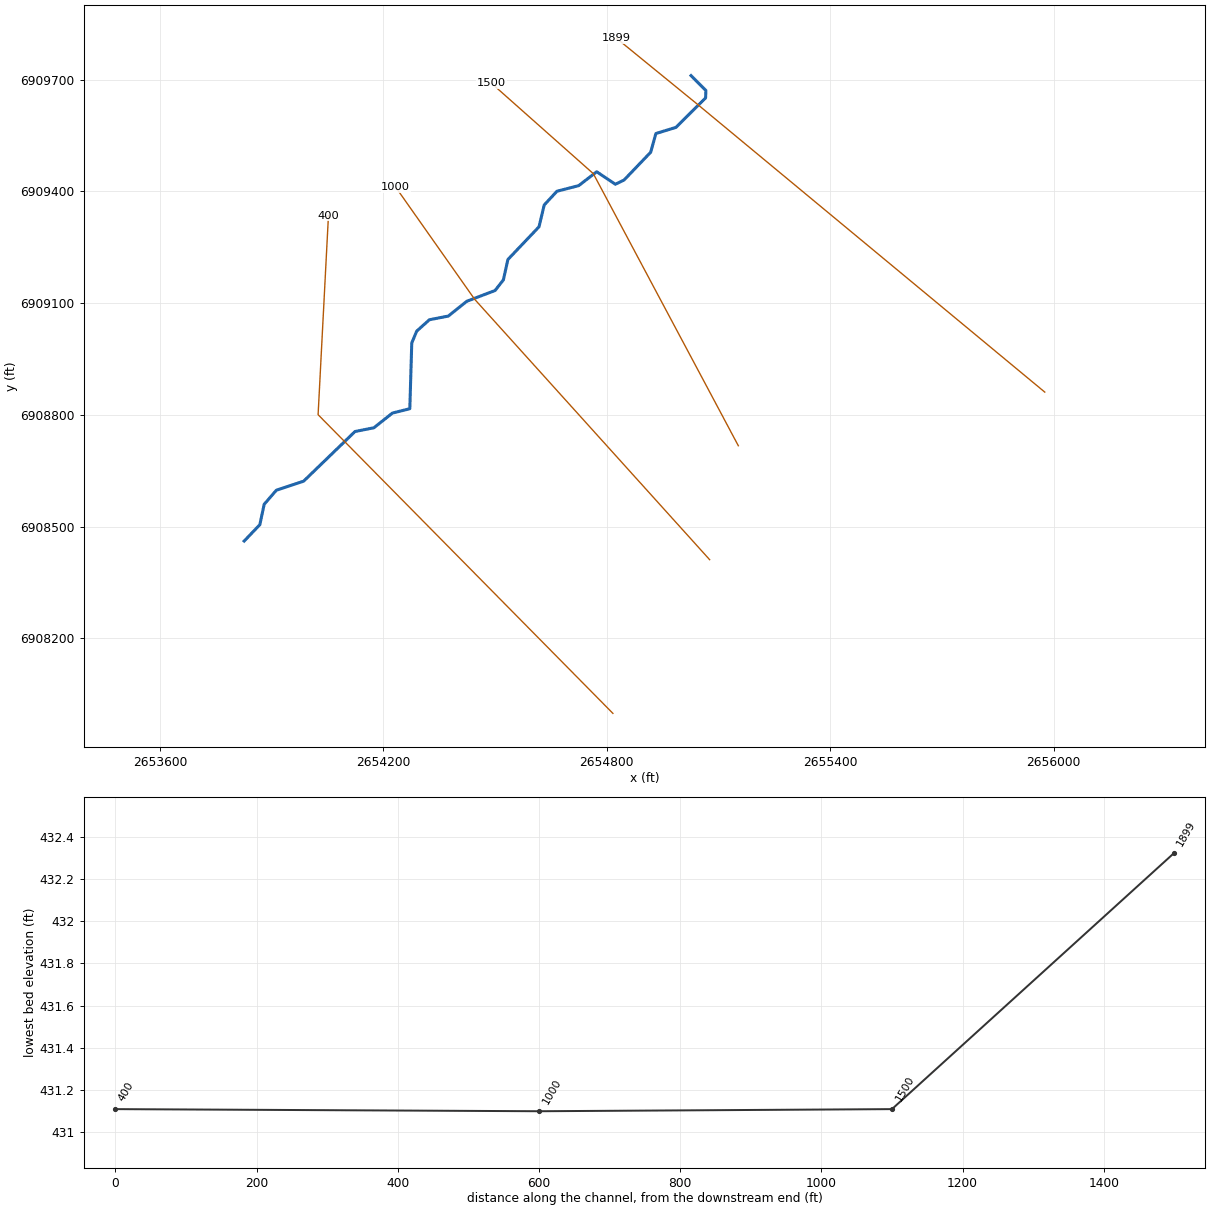
--- Kauffman Branch Trib 2.prj (project) ---

Proj Title=Kauffman Branch Trib 2 Base Level Engineering
Current Plan=p01
Default Exp/Contr=0.3,0.1
English Units
Geom File=g01
Flow File=f01
Plan File=p01
BEGIN DESCRIPTION:
Kauffman Branch Trib 2
END DESCRIPTION:

--- Kauffman Branch Trib 2.p01 (plan) ---

Plan Title=Multiple Run
Short Identifier=Multiple
Geom File=g01
Flow File=f01
Subcritical Flow
K Sum by GR= 0
Std Step Tol= 0.01
Critical Tol= 0.01
Num of Std Step Trials= 20
Max Error Tol= 0.3
Flow Tol Ratio= 0.001
Split Flow NTrial= 30
Split Flow Tol= 0.02
Split Flow Ratio= 0.02
Log Output Level= 0
Friction Slope Method= 1
Unsteady Friction Slope Method= 2
Unsteady Bridges Friction Slope Method= 1
Parabolic Critical Depth
Global Vel Dist=  1 , 1 , 1
Global Log Level= 0
CheckData=True
Encroach Param= -1, 0, 0, 0
BEGIN DESCRIPTION:
Multiple Run
END DESCRIPTION:

--- Kauffman Branch Trib 2.f01 (steady flow) ---

Flow Title=Multiple
Number of Profiles=7
Profile Names=10-year,25-year,50-year,1pct_min,100-year,1pct_plu,500-year
River Rch & RM= Kauffman Branch ,Reach-1,1899
     259     328     379     218     436     869     573
Boundary for River Rch & Prof#=Kauffman Branch ,Reach-1,1
Up Type=0
Dn Type=3
Dn Slope=0.005
Boundary for River Rch & Prof#=Kauffman Branch ,Reach-1,2
Up Type=0
Dn Type=3
Dn Slope=0.005
Boundary for River Rch & Prof#=Kauffman Branch ,Reach-1,3
Up Type=0
Dn Type=3
Dn Slope=0.005
Boundary for River Rch & Prof#=Kauffman Branch ,Reach-1,4
Up Type=0
Dn Type=3
Dn Slope=0.005
Boundary for River Rch & Prof#=Kauffman Branch ,Reach-1,5
Up Type=0
Dn Type=3
Dn Slope=0.005
Boundary for River Rch & Prof#=Kauffman Branch ,Reach-1,6
Up Type=0
Dn Type=3
Dn Slope=0.005
Boundary for River Rch & Prof#=Kauffman Branch ,Reach-1,7
Up Type=0
Dn Type=3
Dn Slope=0.005

--- Kauffman Branch Trib 2.g01 (geometry) ---

Geom Title=Existing Conditions

River Reach=Kauffman Branch ,Reach-1
Reach XY= 30
      2655026.00      6909711.00      2655065.90      6909670.99
      2655065.12      6909650.97      2654985.46      6909571.88
      2654931.62      6909555.38      2654917.72      6909505.21
      2654846.04      6909430.36      2654822.68      6909419.14
      2654772.77      6909452.75      2654724.32      6909415.45
      2654666.00      6909400.38      2654631.75      6909363.54
      2654617.82      6909304.98      2654534.18      6909217.02
      2654522.11      6909162.43      2654499.84      6909133.86
      2654423.84      6909104.89      2654374.23      6909065.20
      2654323.42      6909055.29      2654289.22      6909024.67
      2654276.04      6908992.89      2654270.83      6908816.41
      2654224.21      6908804.73      2654174.30      6908765.18
      2654123.70      6908755.17      2653985.66      6908621.79
      2653912.43      6908597.53      2653879.71      6908559.66
      2653868.05      6908504.89      2653826.00      6908461.00

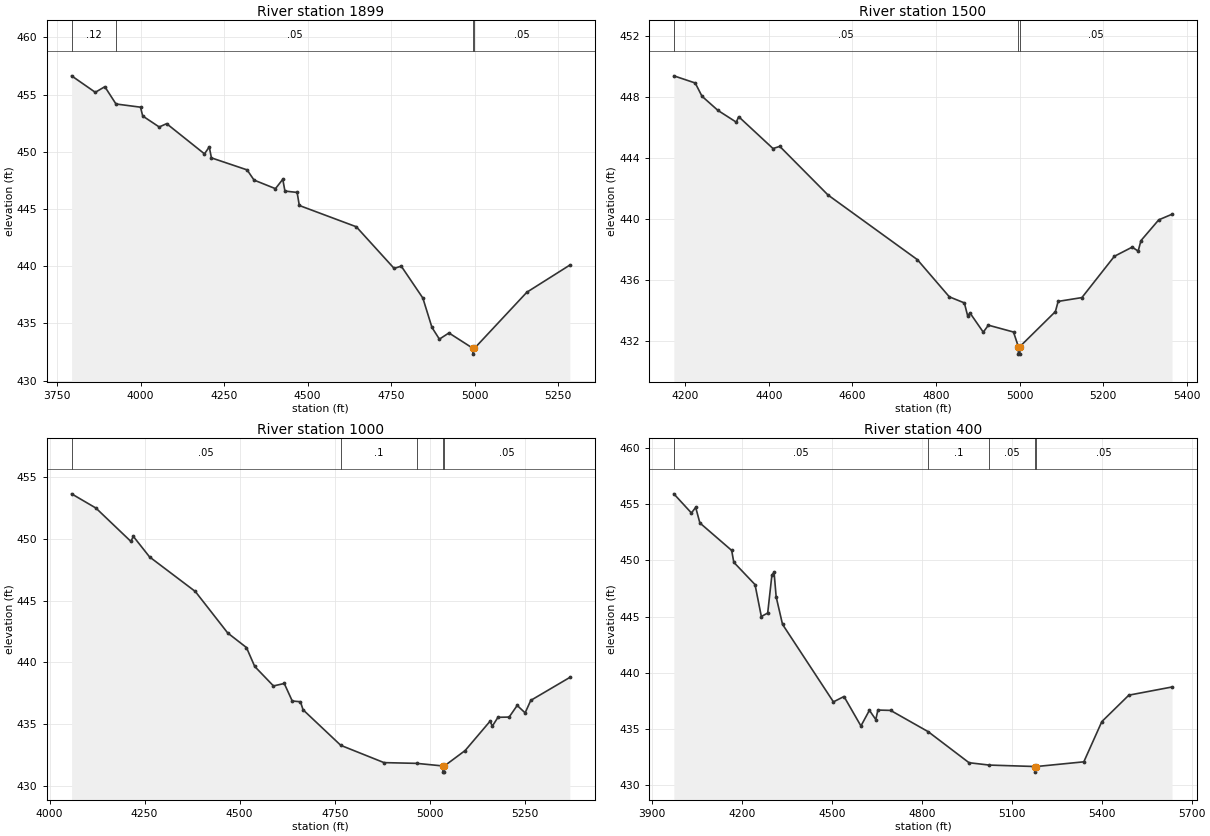
Type RM Length L Ch R = 1,1899,399,399,399
BEGIN DESCRIPTION:
Kauffman Branch Trib 2 4.0
END DESCRIPTION:
XS GIS Cut Line= 3
      2655976.01      6908860.99      2655046.85      6909630.92
      2654825.97      6909811.03
#Sta/Elev= 30
  3793.3  456.64  3864.3  455.20  3892.9  455.69  3926.2  454.18  3999.7  453.90
  4006.2  453.13  4055.7  452.17  4077.9  452.46  4191.2  449.82  4205.5  450.43
  4212.0  449.47  4318.8  448.42  4339.6  447.53  4403.7  446.78  4425.6  447.60
  4432.1  446.57  4468.6  446.45  4475.1  445.31  4645.7  443.45  4759.0  439.81
  4780.3  440.01  4845.0  437.22  4872.3  434.65  4894.5  433.63  4923.1  434.17
  4995.3  432.82  4995.6  432.32  4999.3  432.82  5156.4  437.73  5285.0  440.10
#Mann=4,-1,0
  3793.3    0.12       0  3926.2    0.05       0  4995.3    0.03       0
  4999.3    0.05       0
Bank Sta=4995.3,4999.3
Exp/Cntr=0.3,0.1

Type RM Length L Ch R = 1,1500,500,500,500
BEGIN DESCRIPTION:
Kauffman Branch Trib 2 3.0
END DESCRIPTION:
XS GIS Cut Line= 3
      2655153.00      6908716.99      2654763.64      6909447.61
      2654490.38      6909690.04
#Sta/Elev= 30
  4172.1  449.37  4223.3  448.90  4239.6  448.03  4277.8  447.10  4321.7  446.33
  4327.4  446.69  4409.6  444.60  4425.9  444.74  4541.4  441.55  4755.3  437.31
  4831.9  434.87  4867.9  434.47  4875.8  433.62  4881.4  433.81  4913.2  432.55
  4925.4  433.01  4985.6  432.56  4997.1  431.61  4997.3  431.11  5000.8  431.11
  5001.1  431.61  5085.9  433.90  5092.5  434.57  5149.4  434.82  5227.2  437.53
  5269.8  438.13  5284.1  437.87  5290.9  438.56  5333.4  439.92  5365.3  440.29
#Mann=3,-1,0
  4172.1    0.05       0  4997.1    0.04       0  5001.1    0.05       0
Bank Sta=4997.1,5001.1
Exp/Cntr=0.3,0.1

Type RM Length L Ch R = 1,1000,600,600,600
BEGIN DESCRIPTION:
Kauffman Branch Trib 2 2.0
END DESCRIPTION:
XS GIS Cut Line= 3
      2655075.98      6908411.02      2654444.86      6909110.34
      2654232.88      6909411.40
#Sta/Elev= 30
  4058.0  453.64  4121.9  452.49  4213.8  449.79  4220.5  450.19  4263.1  448.53
  4383.4  445.73  4468.6  442.37  4517.9  441.19  4539.6  439.66  4588.9  438.08
  4617.3  438.28  4638.3  436.86  4659.9  436.80  4666.7  436.15  4765.9  433.27
  4879.6  431.87  4965.4  431.81  5034.4  431.60  5034.7  431.10  5038.2  431.10
  5038.4  431.60  5093.0  432.85  5158.4  435.22  5164.5  434.83  5179.3  435.54
  5208.7  435.56  5229.8  436.50  5250.7  435.90  5265.5  436.91  5368.2  438.77
#Mann=5,-1,0
  4058.0    0.05       0  4765.9     0.1       0  4965.4    0.05       0
  5034.4    0.03       0  5038.4    0.05       0
Bank Sta=5034.4,5038.4
Exp/Cntr=0.3,0.1

Type RM Length L Ch R = 1,400,0,0,0
BEGIN DESCRIPTION:
Kauffman Branch Trib 2 1.0
END DESCRIPTION:
XS GIS Cut Line= 3
      2654816.21      6907998.23      2654024.53      6908800.32
      2654052.31      6909335.01
#Sta/Elev= 30
  3972.2  455.95  4030.9  454.24  4045.1  454.74  4059.2  453.35  4165.2  450.90
  4172.3  449.84  4243.1  447.85  4264.2  445.00  4285.4  445.31  4299.5  448.71
  4306.7  448.94  4313.7  446.75  4334.9  444.30  4504.7  437.38  4540.0  437.86
  4596.5  435.23  4624.8  436.63  4646.1  435.80  4653.1  436.65  4695.5  436.62
  4820.9  434.72  4957.2  431.95  5024.3  431.74  5178.0  431.61  5178.2  431.11
  5182.0  431.61  5340.2  432.03  5400.3  435.62  5490.4  437.98  5634.6  438.71
#Mann=5,-1,0
  3972.2    0.05       0  4820.9     0.1       0  5024.3    0.05       0
  5178.0    0.07       0  5182.0    0.05       0
Bank Sta=5178,5182
Exp/Cntr=0.3,0.1

Chan Stop Cuts=-1