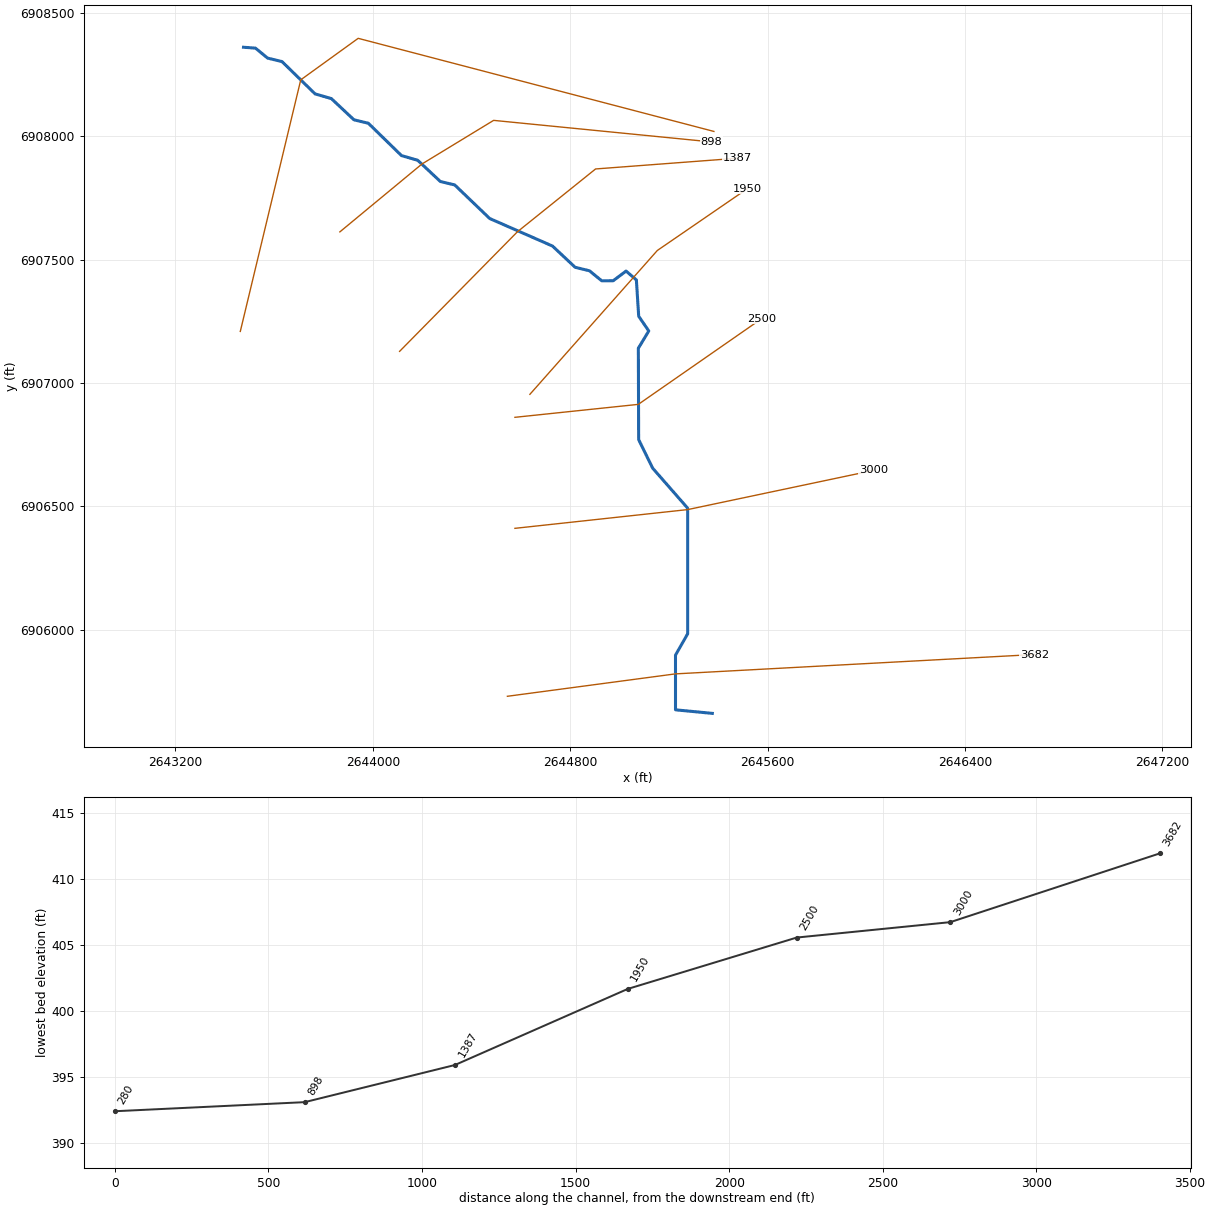
--- Kauffman Branch Trib 3.prj (project) ---

Proj Title=Kauffman Branch Trib 3 Base Level Engineering
Current Plan=p01
Default Exp/Contr=0.3,0.1
English Units
Geom File=g01
Flow File=f01
Plan File=p01
BEGIN DESCRIPTION:
Kauffman Branch Trib 3
END DESCRIPTION:

--- Kauffman Branch Trib 3.p01 (plan) ---

Plan Title=Multiple Run
Short Identifier=Multiple
Geom File=g01
Flow File=f01
Subcritical Flow
K Sum by GR= 0
Std Step Tol= 0.01
Critical Tol= 0.01
Num of Std Step Trials= 20
Max Error Tol= 0.3
Flow Tol Ratio= 0.001
Split Flow NTrial= 30
Split Flow Tol= 0.02
Split Flow Ratio= 0.02
Log Output Level= 0
Friction Slope Method= 1
Unsteady Friction Slope Method= 2
Unsteady Bridges Friction Slope Method= 1
Parabolic Critical Depth
Global Vel Dist=  1 , 1 , 1
Global Log Level= 0
CheckData=True
Encroach Param= -1, 0, 0, 0
BEGIN DESCRIPTION:
Multiple Run
END DESCRIPTION:

--- Kauffman Branch Trib 3.f01 (steady flow) ---

Flow Title=Multiple
Number of Profiles=7
Profile Names=10-year,25-year,50-year,1pct_min,100-year,1pct_plu,500-year
River Rch & RM= Kauffman Branch ,Reach-1,3682
     370     486     577     341     681    1359     946
Boundary for River Rch & Prof#=Kauffman Branch ,Reach-1,1
Up Type=0
Dn Type=3
Dn Slope=0.005
Boundary for River Rch & Prof#=Kauffman Branch ,Reach-1,2
Up Type=0
Dn Type=3
Dn Slope=0.005
Boundary for River Rch & Prof#=Kauffman Branch ,Reach-1,3
Up Type=0
Dn Type=3
Dn Slope=0.005
Boundary for River Rch & Prof#=Kauffman Branch ,Reach-1,4
Up Type=0
Dn Type=3
Dn Slope=0.005
Boundary for River Rch & Prof#=Kauffman Branch ,Reach-1,5
Up Type=0
Dn Type=3
Dn Slope=0.005
Boundary for River Rch & Prof#=Kauffman Branch ,Reach-1,6
Up Type=0
Dn Type=3
Dn Slope=0.005
Boundary for River Rch & Prof#=Kauffman Branch ,Reach-1,7
Up Type=0
Dn Type=3
Dn Slope=0.005

--- Kauffman Branch Trib 3.g01 (geometry) ---

Geom Title=Existing Conditions

River Reach=Kauffman Branch ,Reach-1
Reach XY= 30
      2645376.00      6905661.00      2645226.74      6905675.37
      2645226.68      6905897.08      2645276.09      6905983.69
      2645275.91      6906492.78      2645134.14      6906654.94
      2645077.36      6906770.65      2645076.18      6907141.02
      2645118.44      6907211.00      2645077.56      6907270.60
      2645068.19      6907417.83      2645026.33      6907453.75
      2644974.38      6907414.62      2644927.74      6907414.37
      2644878.19      6907454.82      2644819.95      6907469.15
      2644728.29      6907555.15      2644473.70      6907666.83
      2644332.05      6907802.84      2644273.72      6907816.87
      2644182.04      6907902.82      2644116.32      6907921.78
      2643982.05      6908052.84      2643923.72      6908066.87
      2643832.04      6908152.82      2643766.32      6908171.78
      2643632.06      6908302.87      2643573.76      6908316.97
      2643524.51      6908357.40      2643476.00      6908361.00

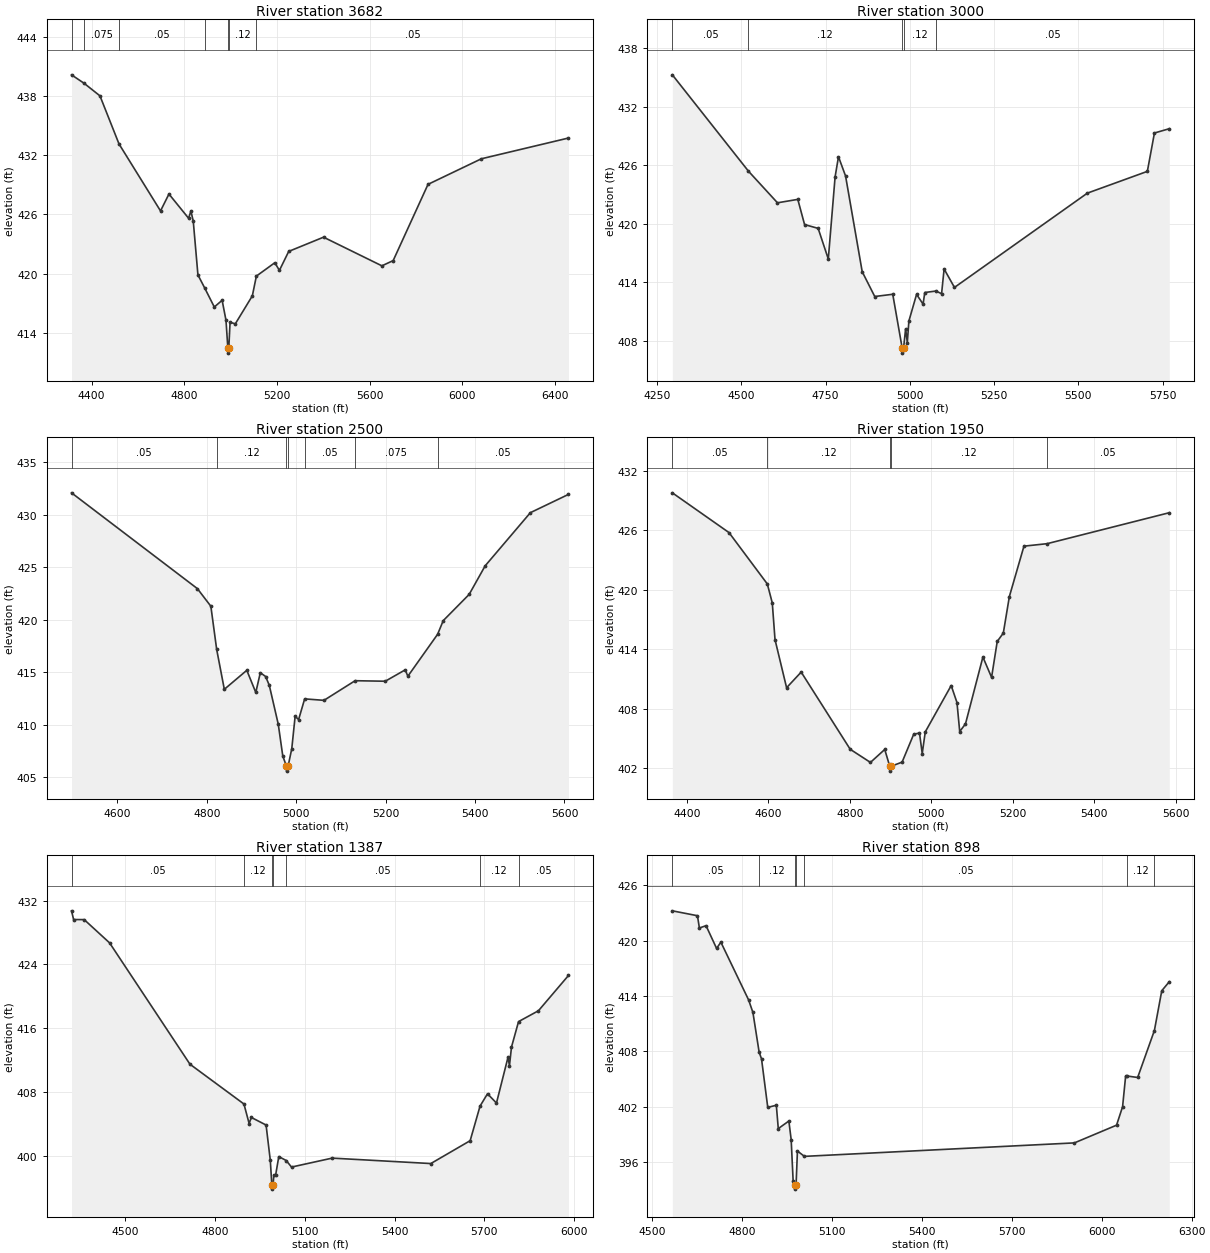
Type RM Length L Ch R = 1,3682,682,682,682
BEGIN DESCRIPTION:
Kauffman Branch Trib 3 7.0
END DESCRIPTION:
XS GIS Cut Line= 3
      2644545.50      6905730.29      2645225.88      6905821.04
      2646680.96      6905899.57
#Sta/Elev= 30
  4313.6  440.14  4368.1  439.28  4436.3  438.01  4518.5  433.14  4697.5  426.36
  4733.9  428.07  4818.5  425.62  4828.6  426.34  4838.7  425.34  4858.9  419.88
  4888.4  418.54  4929.5  416.63  4963.3  417.31  4979.9  415.29  4988.0  412.46
  4988.3  411.96  4992.0  412.46  4997.5  415.08  5020.2  414.93  5093.6  417.76
  5111.0  419.76  5190.4  421.11  5210.4  420.34  5250.5  422.26  5400.7  423.70
  5652.4  420.80  5701.1  421.33  5851.4  429.05  6081.7  431.64  6457.2  433.74
#Mann=7,-1,0
  4313.6    0.05       0  4368.1   0.075       0  4518.5    0.05       0
  4888.4    0.12       0  4988.0    0.07       0  4992.0    0.12       0
  5111.0    0.05       0
Bank Sta=4988,4992
Exp/Cntr=0.3,0.1

Type RM Length L Ch R = 1,3000,500,500,500
BEGIN DESCRIPTION:
Kauffman Branch Trib 3 6.0
END DESCRIPTION:
XS GIS Cut Line= 3
      2644575.96      6906411.00      2645276.25      6906487.01
      2646029.65      6906646.04
#Sta/Elev= 30
  4295.6  435.25  4521.4  425.38  4607.5  422.14  4667.8  422.49  4687.9  419.91
  4728.2  419.52  4758.3  416.38  4778.5  424.80  4788.5  426.86  4809.5  424.89
  4858.9  415.08  4896.1  412.54  4949.5  412.77  4977.6  407.24  4977.9  406.74
  4981.6  407.24  4987.7  409.24  4992.7  407.82  4997.4  410.03  5020.2  412.76
  5039.5  411.76  5044.6  412.95  5077.5  413.10  5094.4  412.83  5101.9  415.36
  5132.6  413.47  5526.9  423.13  5704.9  425.36  5725.9  429.29  5770.0  429.73
#Mann=5,-1,0
  4295.6    0.05       0  4521.4    0.12       0  4977.6    0.07       0
  4981.6    0.12       0  5077.5    0.05       0
Bank Sta=4977.6,4981.6
Exp/Cntr=0.3,0.1

Type RM Length L Ch R = 1,2500,550,550,550
BEGIN DESCRIPTION:
Kauffman Branch Trib 3 5.0
END DESCRIPTION:
XS GIS Cut Line= 3
      2644576.03      6906861.00      2645075.98      6906913.48
      2645575.98      6907260.98
#Sta/Elev= 30
  4497.3  432.07  4778.8  422.95  4809.0  421.27  4822.0  417.16  4839.1  413.36
  4889.4  415.17  4909.5  413.06  4919.6  414.94  4931.5  414.58  4939.7  413.74
  4959.8  410.03  4969.9  407.00  4977.9  406.07  4978.2  405.57  4981.9  406.07
  4990.0  407.71  4997.5  410.79  5005.3  410.48  5018.8  412.45  5062.0  412.31
  5131.7  414.18  5199.1  414.13  5243.6  415.21  5249.7  414.61  5316.2  418.60
  5328.8  419.90  5386.8  422.40  5422.6  425.12  5523.7  430.18  5608.9  431.92
#Mann=7,-1,0
  4497.3    0.05       0  4822.0    0.12       0  4977.9    0.07       0
  4981.9    0.12       0  5018.8    0.05       0  5131.7   0.075       0
  5316.2    0.05       0
Bank Sta=4977.9,4981.9
Exp/Cntr=0.3,0.1

Type RM Length L Ch R = 1,1950,563,563,563
BEGIN DESCRIPTION:
Kauffman Branch Trib 3 4.0
END DESCRIPTION:
XS GIS Cut Line= 3
      2644636.71      6906954.27      2645153.04      6907537.19
      2645516.60      6907786.78
#Sta/Elev= 30
  4364.3  429.80  4503.4  425.78  4597.4  420.59  4609.6  418.67  4616.3  414.96
  4644.7  410.10  4680.5  411.68  4800.8  403.88  4850.5  402.55  4885.6  403.86
  4897.8  402.17  4898.0  401.67  4901.8  402.17  4928.2  402.58  4956.7  405.40
  4970.9  405.52  4977.6  403.45  4985.1  405.64  5048.7  410.32  5062.9  408.60
  5069.6  405.67  5083.8  406.45  5126.5  413.20  5147.8  411.15  5161.7  414.78
  5176.6  415.62  5191.5  419.32  5227.3  424.41  5284.1  424.66  5584.0  427.79
#Mann=5,-1,0
  4364.3    0.05       0  4597.4    0.12       0  4897.8    0.07       0
  4901.8    0.12       0  5284.1    0.05       0
Bank Sta=4897.8,4901.8
Exp/Cntr=0.3,0.1

Type RM Length L Ch R = 1,1387,489,489,489
BEGIN DESCRIPTION:
Kauffman Branch Trib 3 3.0
END DESCRIPTION:
XS GIS Cut Line= 4
      2644108.66      6907128.35      2644585.84      6907612.81
      2644902.85      6907867.66      2645475.97      6907911.00
#Sta/Elev= 30
  4320.0  430.71  4327.0  429.62  4362.4  429.61  4447.3  426.70  4716.0  411.52
  4896.5  406.54  4913.9  404.09  4921.1  404.86  4970.5  403.91  4984.6  399.50
  4989.8  396.39  4990.0  395.89  4993.8  396.39  4996.5  397.66  5002.5  397.66
  5013.0  399.96  5037.8  399.47  5055.5  398.65  5191.4  399.77  5521.3  399.09
  5652.8  401.95  5685.9  406.28  5710.8  407.82  5740.8  406.66  5779.3  412.38
  5784.3  411.35  5791.0  413.66  5814.6  416.85  5881.2  418.21  5981.5  422.62
#Mann=7,-1,0
  4320.0    0.05       0  4896.5    0.12       0  4989.8    0.07       0
  4993.8    0.12       0  5037.8    0.05       0  5685.9    0.12       0
  5814.6    0.05       0
Bank Sta=4989.8,4993.8
Exp/Cntr=0.3,0.1

Type RM Length L Ch R = 1,898,618,618,618
BEGIN DESCRIPTION:
Kauffman Branch Trib 3 2.0
END DESCRIPTION:
XS GIS Cut Line= 4
      2643866.55      6907612.61      2644199.44      6907887.94
      2644489.62      6908064.58      2645371.01      6907977.41
#Sta/Elev= 30
  4568.0  423.23  4651.7  422.70  4658.2  421.37  4680.4  421.62  4715.5  419.16
  4729.9  419.83  4822.4  413.57  4836.7  412.22  4857.5  407.91  4865.4  407.19
  4886.2  401.93  4914.8  402.16  4921.3  399.63  4956.6  400.45  4964.3  398.44
  4970.8  393.99  4976.7  393.57  4976.9  393.07  4980.7  393.57  4985.2  397.20
  5008.4  396.62  5908.9  398.08  6049.5  400.00  6069.6  402.00  6079.7  405.29
  6084.3  405.33  6119.9  405.17  6175.7  410.26  6200.3  414.57  6225.4  415.55
#Mann=7,-1,0
  4568.0    0.05       0  4857.5    0.12       0  4976.7    0.07       0
  4980.7    0.12       0  5008.4    0.05       0  6084.3    0.12       0
  6175.7    0.05       0
Bank Sta=4976.7,4980.7
Exp/Cntr=0.3,0.1

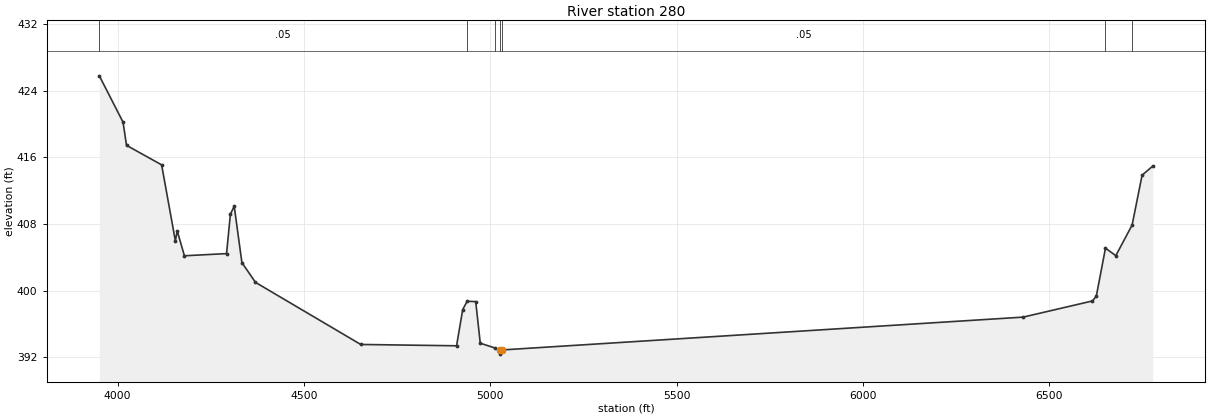
Type RM Length L Ch R = 1,280,0,0,0
BEGIN DESCRIPTION:
Kauffman Branch Trib 3 1.0
END DESCRIPTION:
XS GIS Cut Line= 4
      2643463.03      6907209.11      2643708.03      6908228.89
      2643940.81      6908397.10      2645382.45      6908019.76
#Sta/Elev= 30
  3951.2  425.77  4014.8  420.21  4024.1  417.43  4118.3  415.09  4155.1  405.99
  4160.3  407.15  4179.4  404.18  4292.5  404.44  4302.8  409.17  4313.1  410.12
  4333.7  403.36  4370.1  400.99  4652.5  393.54  4909.6  393.38  4926.1  397.72
  4938.0  398.72  4961.0  398.68  4973.2  393.69  5012.4  393.12  5026.8  392.88
  5027.0  392.38  5030.8  392.88  6429.6  396.82  6615.7  398.76  6626.0  399.34
  6650.6  405.10  6678.3  404.19  6722.1  407.87  6748.8  413.85  6777.4  414.94
#Mann=7,-1,0
  3951.2    0.05       0  4938.0    0.12       0  5012.4    0.05       0
  5026.8    0.07       0  5030.8    0.05       0  6650.6    0.12       0
  6722.1    0.05       0
Bank Sta=5026.8,5030.8
Exp/Cntr=0.3,0.1

Chan Stop Cuts=-1