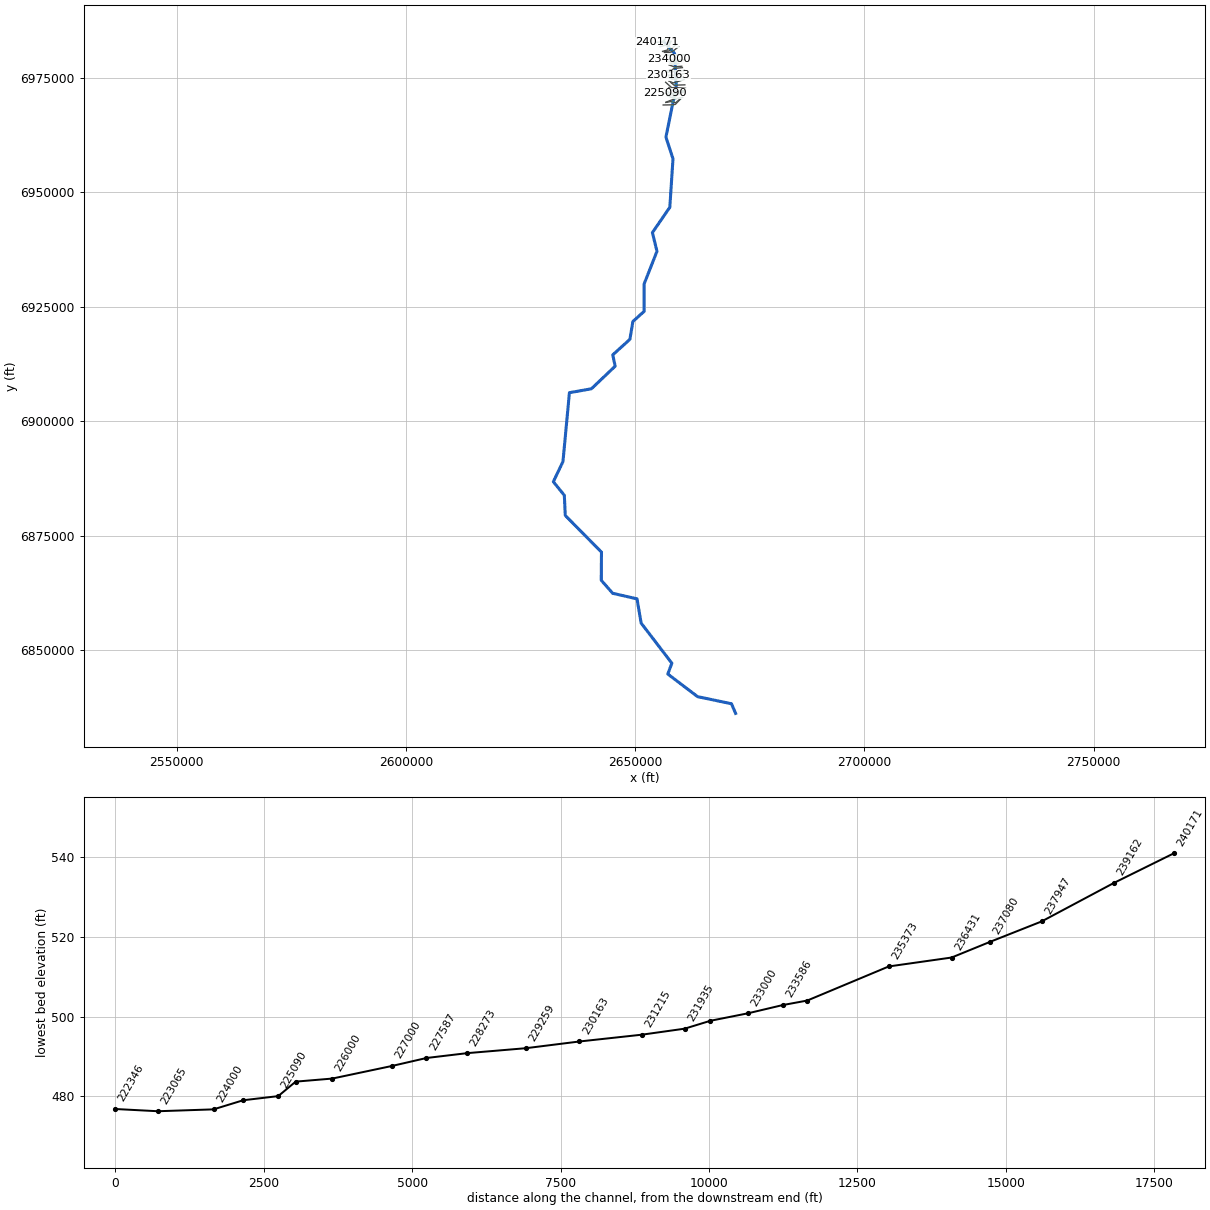
--- Kings Creek.prj (project) ---

Proj Title=Kings Creek Base Level Engineering
Current Plan=p01
Default Exp/Contr=0.3,0.1
English Units
Geom File=g01
Flow File=f01
Plan File=p01
Y Axis Title=Elevation
X Axis Title(PF)=Main Channel Distance
X Axis Title(XS)=Station
BEGIN DESCRIPTION:
Kings Creek
END DESCRIPTION:
DSS File=dss
DSS Export Rating Curves= 0
DSS Export Rating Curve Sorted= 0
DSS Export Volume Flow Curves= 0
DXF OffsetX= 0
DXF OffsetY= 0
DXF ScaleX= 1
DXF ScaleY= 10

--- Kings Creek.p01 (plan) ---

Plan Title=Multiple Run
Program Version=4.10
Short Identifier=Multiple Run
Geom File=g01
Flow File=f01
Subcritical Flow
K Sum by GR= 0
Std Step Tol= 0.01
Critical Tol= 0.01
Num of Std Step Trials= 20
Max Error Tol= 0.3
Flow Tol Ratio= 0.001
Split Flow NTrial= 30
Split Flow Tol= 0.02
Split Flow Ratio= 0.02
Log Output Level= 0
Friction Slope Method= 1
Unsteady Friction Slope Method= 2
Unsteady Bridges Friction Slope Method= 1
Parabolic Critical Depth
Global Vel Dist= 1 , 1 , 1
Global Log Level= 0
CheckData=True
Encroach Param=-1 ,0,0, 0
BEGIN DESCRIPTION:
Multiple Run
END DESCRIPTION:
Computation Interval=1HOUR
Output Interval=1HOUR
Run HTab= 0
Run UNet= 0
Run PostProcess= 0
Run WQNet= 0
UNET Theta= 1
UNET Theta Warmup= 1
UNET ZTol= 0.02
UNET ZSATol= 0.05
UNET MxIter= 20
UNET MaxInSteps= 0
UNET DtIC= 0
UNET DtMin= 0
UNET MaxCRTS= 20
UNET WFStab= 2
UNET SFStab= 1
UNET WFX= 1
UNET SFX= 1
UNET DSS MLevel= 4
UNET DZMax Abort= 100
UNET Convert EG Bridges= 0
UNET Use Existing IB Tables=-1
UNET Froude Reduction=False
UNET Froude Limit= 1
UNET Froude Power= 10
UNET Time Slicing=0,0, 5
UNET Junction Losses=0
Instantaneous Interval=1HOUR
DSS File=dss
Write IC File= 0
Write IC File at Sim End=0
Echo Input=False
Echo Parameters=False
Echo Output=False
Write Detailed= 0
WQ AD Non Conservative
WQ ULTIMATE=-1
WQ Max Comp Step=1HOUR
WQ Output Interval=15MIN
WQ Output Selected Increments= 0
WQ Output face flow=0
WQ Output face velocity=0
WQ Output face area=0
WQ Output face dispersion=0
WQ Output cell volume=0
WQ Output cell surface area=0
WQ Output cell continuity=0
WQ Output cumulative cell continuity=0
WQ Output face conc=0
WQ Output face dconc_dx=0
WQ Output face courant=0
WQ Output face peclet=0
WQ Output face adv mass=0
WQ Output face disp mass=0
WQ Output cell mass=0
WQ Output cell source sink temp=0
WQ Output cell source sink nsm=0
WQ Output MaxMinRange=-1
WQ Daily Max Min Mean=-1
WQ Daily Range=0
WQ Daily Time=0
WQ Create Restart=0
WQ Fixed Restart=0
WQ System Summary=0
WQ Use Fixed Temperature=0
Sorting and Armoring Iterations= 10
XS Update Threshold= 0.02
Hydraulics Update Threshold= 0.02
Energy Slope Method= 1
Volume Change Method= 0
XS Weighting Method= 0
Number of US Weighted Cross Sections= 1
Number of DS Weighted Cross Sections= 1
Upstream XS Weight=0.25
Main XS Weight=0.5
Downstream XS Weight=0.25
Number of DS XS's Weighted with US Boundary= 1
Upstream Boundary Weight= 1
Weight of XSs Associated with US Boundary= 0
Number of US XS's Weighted with DS Boundary= 1
Downstream Boundary Weight= 0.5
Weight of XSs Associated with DS Boundary= 0.5
Sediment Output Level= 4
Mass or Volume Output= 0
Output Increment Type= 1
Profile and TS Output Increment= 10
XS Output Flag= 0
XS Output Increment= 10
Disregard all LS=0
Disregard all Conn=0
Disregard all Breaches=0
Disregard all Pumps=0

--- Kings Creek.f01 (steady flow) ---

Flow Title=Multiple
Program Version=4.10
Number of Profiles= 7
Profile Names=10-year,25-year,50-year,1pct_min,100-year,1pct_plu,500-year
River Rch & RM=Kings Creek,Reach-1         ,240171
     472     622     741     438     874    1744    1216
River Rch & RM=Kings Creek,Reach-1         ,237947
     656     882    1064     637    1270    2535    1811
River Rch & RM=Kings Creek,Reach-1         ,235373
     941    1289    1576     954    1904    3798    2778
River Rch & RM=Kings Creek,Reach-1         ,231935
    1285    1785    2203    1345    2683    5353    3981
River Rch & RM=Kings Creek,Reach-1         ,227000
    1539    2157    2677    1642    3276    6537    4913
River Rch & RM=Kings Creek,Reach-1         ,225090
    1749    2466    3072    1891    3773    7529    5697
River Rch & RM=Kings Creek,Reach-1         ,224000
    1970    2787    3482    2148    4285    8550    6497
River Rch & RM=Kings Creek,Reach-1         ,220000
    1993    2817    3516    2167    4324    8627    6543
River Rch & RM=Kings Creek,Reach-1         ,218512
    2260    3212    4024    2488    4965    9906    7564
River Rch & RM=Kings Creek,Reach-1         ,216180
    2261    3213    4024    2487    4963    9902    7557
River Rch & RM=Kings Creek,Reach-1         ,215500
    2389    3399    4262    2637    5262   10498    8026
River Rch & RM=Kings Creek,Reach-1         ,215000
    2602    3717    4672    2897    5780   11533    8857
River Rch & RM=Kings Creek,Reach-1         ,213547
    3532    5100    6456    4029    8039   16040   12475
River Rch & RM=Kings Creek,Reach-1         ,209456
    3717    5373    6807    4251    8482   16924   13180
River Rch & RM=Kings Creek,Reach-1         ,206500
    3873    5604    7105    4439    8858   17673   13777
River Rch & RM=Kings Creek,Reach-1         ,205000
    5504    8050   10284    6469   12907   25753   20343
River Rch & RM=Kings Creek,Reach-1         ,201202
    5596    8178   10441    6563   13094   26126   20607
River Rch & RM=Kings Creek,Reach-1         ,197660
    6139    8987   11488    7228   14422   28776   22740
River Rch & RM=Kings Creek,Reach-1         ,191416
    6420    9397   12009    7554   15072   30073   23748
River Rch & RM=Kings Creek,Reach-1         ,189000
    6454    9455   12089    7606   15176   30281   23932
River Rch & RM=Kings Creek,Reach-1         ,182658
    6468    9472   12108    7615   15194   30316   23944
River Rch & RM=Kings Creek,Reach-1         ,179500
    6451    9432   12043    7566   15095   30119   23733
River Rch & RM=Kings Creek,Reach-1         ,175500
    6403    9340   11906    7467   14899   29727   23344
River Rch & RM=Kings Creek,Reach-1         ,171000
    7833   11422   14557    9122   18201   36316   28463
River Rch & RM=Kings Creek,Reach-1         ,167078
    7824   11406   14536    9108   18173   36259   28413
River Rch & RM=Kings Creek,Reach-1         ,166221
    8569   12512   15963   10012   19976   39858   31288
River Rch & RM=Kings Creek,Reach-1         ,159597
    8632   12603   16077   10082   20117   40138   31500
River Rch & RM=Kings Creek,Reach-1         ,158139
    8627   12587   16050   10060   20073   40052   31403
River Rch & RM=Kings Creek,Reach-1         ,156281
    8789   12824   16353   10250   20451   40806   31993
River Rch & RM=Kings Creek,Reach-1         ,153662
    9417   13735   17512   10973   21894   43684   34222
River Rch & RM=Kings Creek,Reach-1         ,150563
    9243   13505   17235   10809   21567   43032   33785
River Rch & RM=Kings Creek,Reach-1         ,140060
    9342   13648   17416   10921   21791   43479   34128
River Rch & RM=Kings Creek,Reach-1         ,137835
    9515   13901   17741   11126   22199   44292   34767
River Rch & RM=Kings Creek,Reach-1         ,136092
    9740   14223   18146   11376   22697   45287   35520
River Rch & RM=Kings Creek,Reach-1         ,121999
   11202   16396   20955   13157   26252   52379   41202
River Rch & RM=Kings Creek,Reach-1         ,114500
   17342   25506   32726   20620   41141   82088   64970
River Rch & RM=Kings Creek,Reach-1         ,107888
   17342   25506   32726   20620   41141   82088   64970
River Rch & RM=Kings Creek,Reach-1         ,106918
   17210   25283   32414   20407   40717   81241   64197
River Rch & RM=Kings Creek,Reach-1         ,99277
   17348   25477   32655   20554   41010   81825   64623
River Rch & RM=Kings Creek,Reach-1         ,93812
   17260   25334   32460   20422   40748   81303   64161
River Rch & RM=Kings Creek,Reach-1         ,92479
   17346   25450   32600   20505   40912   81630   64381
River Rch & RM=Kings Creek,Reach-1         ,89912
   17355   25438   32561   20465   40834   81474   64163
River Rch & RM=Kings Creek,Reach-1         ,80101
   17387   25452   32553   20442   40788   81382   63977
River Rch & RM=Kings Creek,Reach-1         ,70068
   17276   25273   32308   20278   40461   80730   63401
River Rch & RM=Kings Creek,Reach-1         ,66913
   18572   27176   34751   21817   43531   86857   68236
River Rch & RM=Kings Creek,Reach-1         ,57399
   18542   27108   34644   21736   43370   86534   67898
River Rch & RM=Kings Creek,Reach-1         ,54000
   18449   26943   34408   21572   43041   85878   67278
River Rch & RM=Kings Creek,Reach-1         ,51000
   18449   26943   34408   21572   43041   85878   67278
River Rch & RM=Kings Creek,Reach-1         ,44000
   18589   27128   34629   21700   43297   86389   67612
River Rch & RM=Kings Creek,Reach-1         ,40868
   18652   27214   34732   21761   43418   86630   67775
River Rch & RM=Kings Creek,Reach-1         ,32332
   18589   27087   34538   21619   43136   86068   67209
River Rch & RM=Kings Creek,Reach-1         ,23802
   20284   29519   37619   23534   46956   93690   73042
River Rch & RM=Kings Creek,Reach-1         ,19500
   20279   29491   37565   23489   46867   93511   72828
River Rch & RM=Kings Creek,Reach-1         ,15125
   20305   29517   37589   23497   46883   93543   72813
River Rch & RM=Kings Creek,Reach-1         ,9978
   20718   30120   38361   23982   47851   95475   74328
River Rch & RM=Kings Creek,Reach-1         ,7720
   20626   29966   38147   23837   47560   94895   73804
River Rch & RM=Kings Creek,Reach-1         ,5110
   20610   29934   38098   23801   47489   94754   73661
Boundary for River Rch & Prof#=Kings Creek,Reach-1         , 1
Up Type= 0
Dn Type= 1
Dn Known WS=322.21
Boundary for River Rch & Prof#=Kings Creek,Reach-1         , 2
Up Type= 0
Dn Type= 1
Dn Known WS=322.85
Boundary for River Rch & Prof#=Kings Creek,Reach-1         , 3
Up Type= 0
Dn Type= 1
Dn Known WS=323.35
Boundary for River Rch & Prof#=Kings Creek,Reach-1         , 4
Up Type= 0
Dn Type= 1
Dn Known WS=322.74
Boundary for River Rch & Prof#=Kings Creek,Reach-1         , 5
Up Type= 0
Dn Type= 1
Dn Known WS=323.87
Boundary for River Rch & Prof#=Kings Creek,Reach-1         , 6
Up Type= 0
Dn Type= 1
Dn Known WS=324.9
Boundary for River Rch & Prof#=Kings Creek,Reach-1         , 7
Up Type= 0
Dn Type= 1
Dn Known WS=325.18
DSS Import GetInterval= 0
DSS Import GetPeak= 0
DSS Import FillOption= 0

--- Kings Creek.g01 (geometry) ---

Geom Title=Existing Conditions
Program Version=4.10

River Reach=Kings Creek     ,Reach-1
Reach XY= 30
        2656226.        6982861.      2658618.12      6980264.22
      2658976.29      6973040.83        2656726.        6962011.
      2658268.44        6957261.      2657576.29      6946681.23
      2653777.96      6941155.36      2654775.51      6937076.22
      2651977.67      6929955.47      2651973.77      6923966.93
      2649531.33      6921763.74      2648868.66      6917854.57
      2645134.41      6914467.76      2645659.76      6911993.77
        2640476.        6907061.       2635681.4      6906213.48
       2634274.9      6891171.55      2632176.07      6886776.39
      2634572.57      6883809.78        2634776.        6879411.
      2642672.88      6871409.37        2642626.        6865261.
      2645123.55      6862416.46      2650420.48      6861213.43
        2651326.        6855911.      2658023.01      6847159.59
      2657136.05      6844801.02      2663627.47      6839864.54
        2671026.        6838311.        2671926.        6836211.

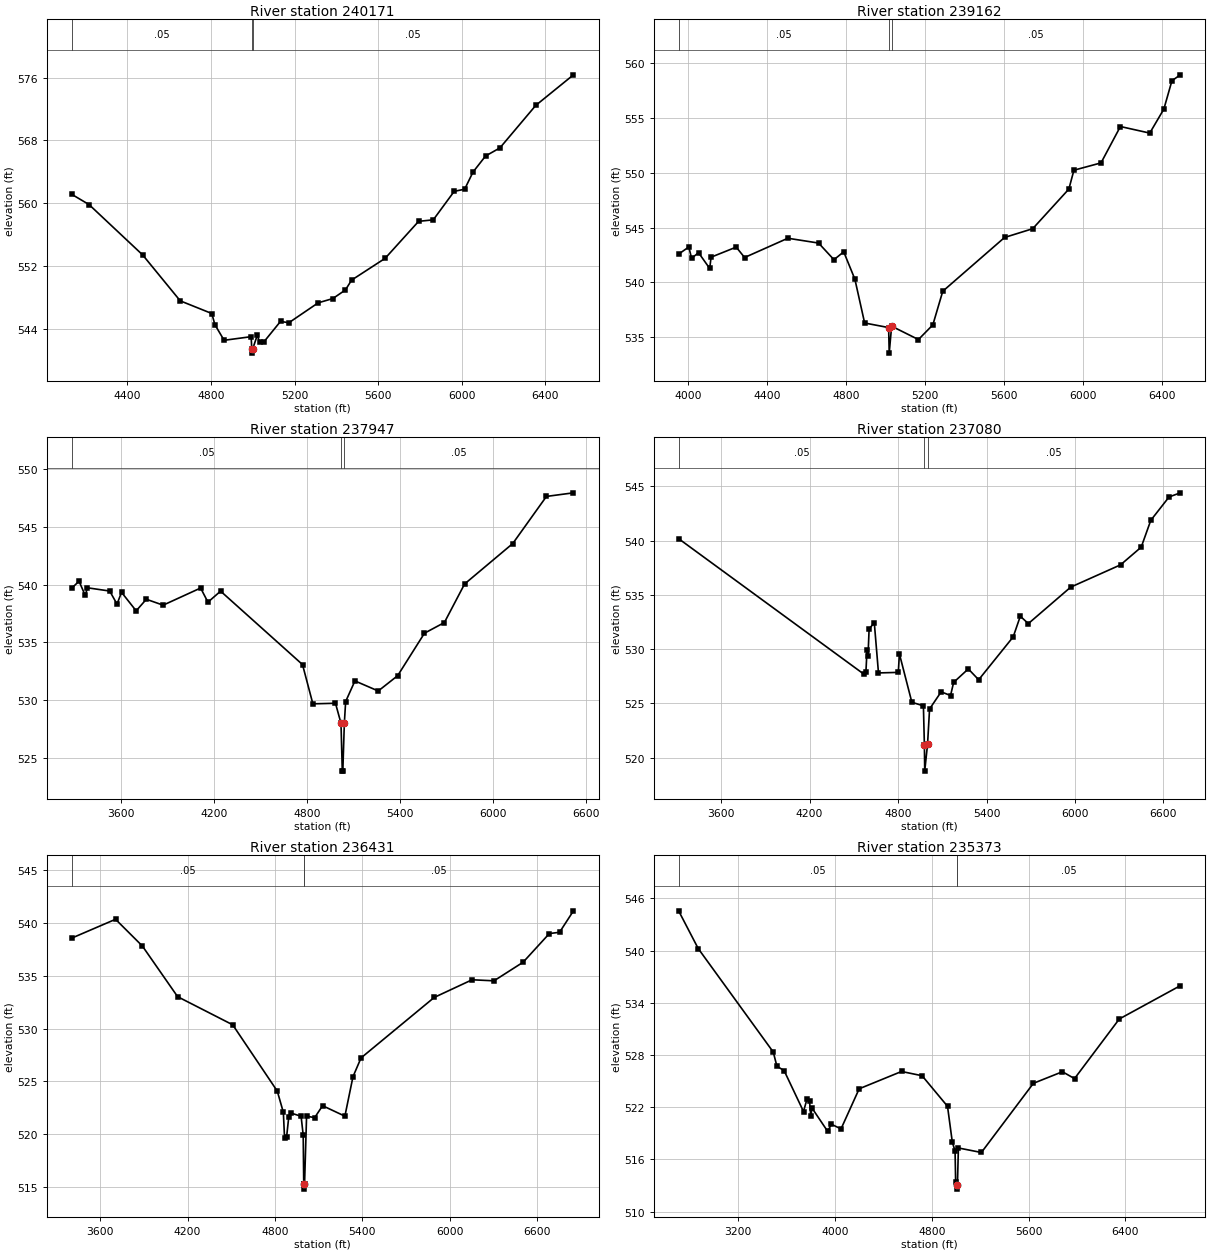
Type RM Length L Ch R = 1 ,240171  ,1009,1009,1009
BEGIN DESCRIPTION:
Kings Creek 475.0
END DESCRIPTION:
XS GIS Cut Line= 3
        2656626.      6983561.01      2656258.86      6982777.13
      2654725.99        6982711.
#Sta/Elev= 30
  4134.4  561.16  4217.1  559.86  4473.7  553.46  4653.4  547.63  4804.4  546.02
    4819  544.61  4863.2  542.62  4992.6  543.08  4995.5  541.49  4995.7  540.99
  4999.5  541.49    5022  543.27  5032.9  542.37  5052.9   542.4    5133  545.02
    5173  544.85  5313.2  547.38  5383.2  547.92  5443.3  549.01  5473.3  550.27
  5633.4  553.03  5793.6  557.73  5863.7  557.92  5963.8  561.54  6013.8  561.81
  6053.8  563.99  6113.9  566.03  6182.6  567.06  6354.1  572.46  6534.3  576.34
#Mann= 3 ,-1 , 0
  4134.4     .05       0  4995.5     .03       0  4999.5     .05       0
Bank Sta=4995.5,4999.5
XS Rating Curve= 0 ,0
Exp/Cntr=0.3,0.1

Type RM Length L Ch R = 1 ,239162  ,1215,1215,1215
BEGIN DESCRIPTION:
Mapping XS bdbb0025
END DESCRIPTION:
XS GIS Cut Line= 3
      2657601.43      6982908.22      2656867.05       6982147.8
      2655445.15      6981720.71
#Sta/Elev= 30
    3953  542.59  4004.5  543.24  4018.7  542.21  4053.9  542.72  4110.5  541.28
  4117.4  542.31  4244.8  543.23  4287.2  542.28  4506.4  544.04    4662   543.6
    4740  542.08  4789.4   542.8    4846   540.3  4895.4   536.3    5017 535.883
  5019.9  533.55  5032.1  536.01  5167.9  534.79    5241  536.13  5291.2   539.2
  5604.3  544.11  5746.9  544.91  5930.1  548.53  5955.6  550.25    6093  550.92
  6191.1  554.24  6339.9  553.64  6411.3  555.83  6452.2  558.42  6494.8  558.96
#Mann= 3 ,-1 , 0
    3953     .05       0    5017     .03       0  5032.1     .05       0
Bank Sta=5017,5032.1
XS Rating Curve= 0 ,0
Exp/Cntr=0.3,0.1

Type RM Length L Ch R = 1 ,237947  ,867,867,867
BEGIN DESCRIPTION:
Mapping XS fa55f600
END DESCRIPTION:
XS GIS Cut Line= 4
       2657835.8      6982934.27      2657169.13      6981366.55
       2657148.3      6981033.22       2655987.7      6980715.74
#Sta/Elev= 30
    3281  539.69    3328  540.29    3368  539.06  3382.4  539.72  3526.2  539.44
  3573.4  538.31  3602.5  539.33  3697.1  537.73  3762.7  538.73  3871.3  538.22
  4113.4   539.7  4160.7  538.48  4242.5  539.43  4771.6  533.09  4838.5   529.7
  4984.6  529.75  5020.2  528.02  5028.5  523.89    5032  523.89 5041.79  528.03
  5050.3   529.9  5110.2  531.68  5260.7  530.81  5386.1  532.13  5559.4   535.8
    5688  536.72  5818.6  540.05  6129.6  543.54  6347.3  547.61  6521.8  547.92
#Mann= 3 ,-1 , 0
    3281     .05       0  5020.2     .03       0 5041.79     .05       0
Bank Sta=5020.2,5041.79
XS Rating Curve= 0 ,0
Exp/Cntr=0.3,0.1

Type RM Length L Ch R = 1 ,237080  ,649,649,649
BEGIN DESCRIPTION:
Mapping XS 8fc1cfa5
END DESCRIPTION:
XS GIS Cut Line= 4
      2659101.42      6982350.92      2657867.05      6981220.72
      2657382.68      6980793.63      2656310.39      6980637.48
#Sta/Elev= 30
  3311.5  540.17  4567.8   527.7    4582  527.94  4589.4   529.9  4596.2  529.39
  4603.6  531.87  4638.8  532.42  4667.1  527.81  4801.6  527.86    4809  529.57
  4893.4  525.11  4971.8  524.78  4978.5  521.17  4980.7  518.77  4999.9  521.24
  5013.6  524.49  5092.3  526.07  5155.9  525.73  5176.8  526.94  5276.4  528.18
  5346.6  527.18  5580.9  531.13  5629.1  533.03  5683.5  532.35  5971.1  535.71
    6309  537.76  6449.2  539.39  6514.2  541.86  6638.1  544.01  6714.5  544.39
#Mann= 3 ,-1 , 0
  3311.5     .05       0  4978.5     .04       0  4999.9     .05       0
Bank Sta=4978.5,4999.9
XS Rating Curve= 0 ,0
Exp/Cntr=0.3,0.1

Type RM Length L Ch R = 1 ,236431  ,1058,1058,1058
BEGIN DESCRIPTION:
Mapping XS c03be980
END DESCRIPTION:
XS GIS Cut Line= 4
      2659492.09      6981736.37      2658242.05      6980741.55
      2657580.59      6980496.76      2656440.47      6980496.76
#Sta/Elev= 30
  3405.3  538.56  3705.8  540.34    3890  537.81  4131.9  533.02  4509.9  530.36
  4815.8  524.09  4857.4  522.08  4865.5   519.7  4879.9  519.78  4894.3  521.62
  4908.4  522.02  4979.2  521.71  4993.6  519.93  4997.3  515.32  4997.6  514.82
  5001.3  515.32  5002.9  515.32  5016.8  521.72  5072.2  521.58  5126.6  522.71
  5279.7  521.72  5335.2  525.45  5390.6  527.23  5892.8  532.95  6152.8  534.62
  6302.8  534.52  6502.8  536.28  6682.8  538.99  6752.8  539.11  6848.3  541.14
#Mann= 3 ,-1 , 0
  3405.3     .05       0  4997.3     .01       0  5001.3     .05       0
Bank Sta=4997.3,5001.3
XS Rating Curve= 0 ,0
Exp/Cntr=0.3,0.1

Type RM Length L Ch R = 1 ,235373  ,1373,1373,1373
BEGIN DESCRIPTION:
Kings Creek 466.0
END DESCRIPTION:
XS GIS Cut Line= 3
      2660768.14       6979960.3      2658476.49      6979905.77
      2656621.47      6979888.22
#Sta/Elev= 30
  2707.7  544.56  2869.9  540.22  3490.1  528.33  3520.1  526.71  3580.1  526.19
  3740.1   521.5  3770.1  522.99  3790.1  522.66  3800.1  520.94  3810.2   521.9
  3940.2  519.21  3970.2  520.04  4050.2   519.5  4200.3  524.11  4550.4   526.1
  4720.4  525.61  4930.5   522.1  4970.5  517.95  4992.9  516.97  4997.7   513.4
  5008.5  513.08  5008.7  512.58  5012.5  513.08  5020.5  517.31  5210.5  516.79
  5640.5  524.74  5880.5  526.07  5980.5  525.28  6350.5  532.13  6855.1  535.96
#Mann= 3 ,-1 , 0
  2707.7     .05       0  5008.5     .04       0  5012.5     .05       0
Bank Sta=5008.5,5012.5
XS Rating Curve= 0 ,0
Exp/Cntr=0.3,0.1

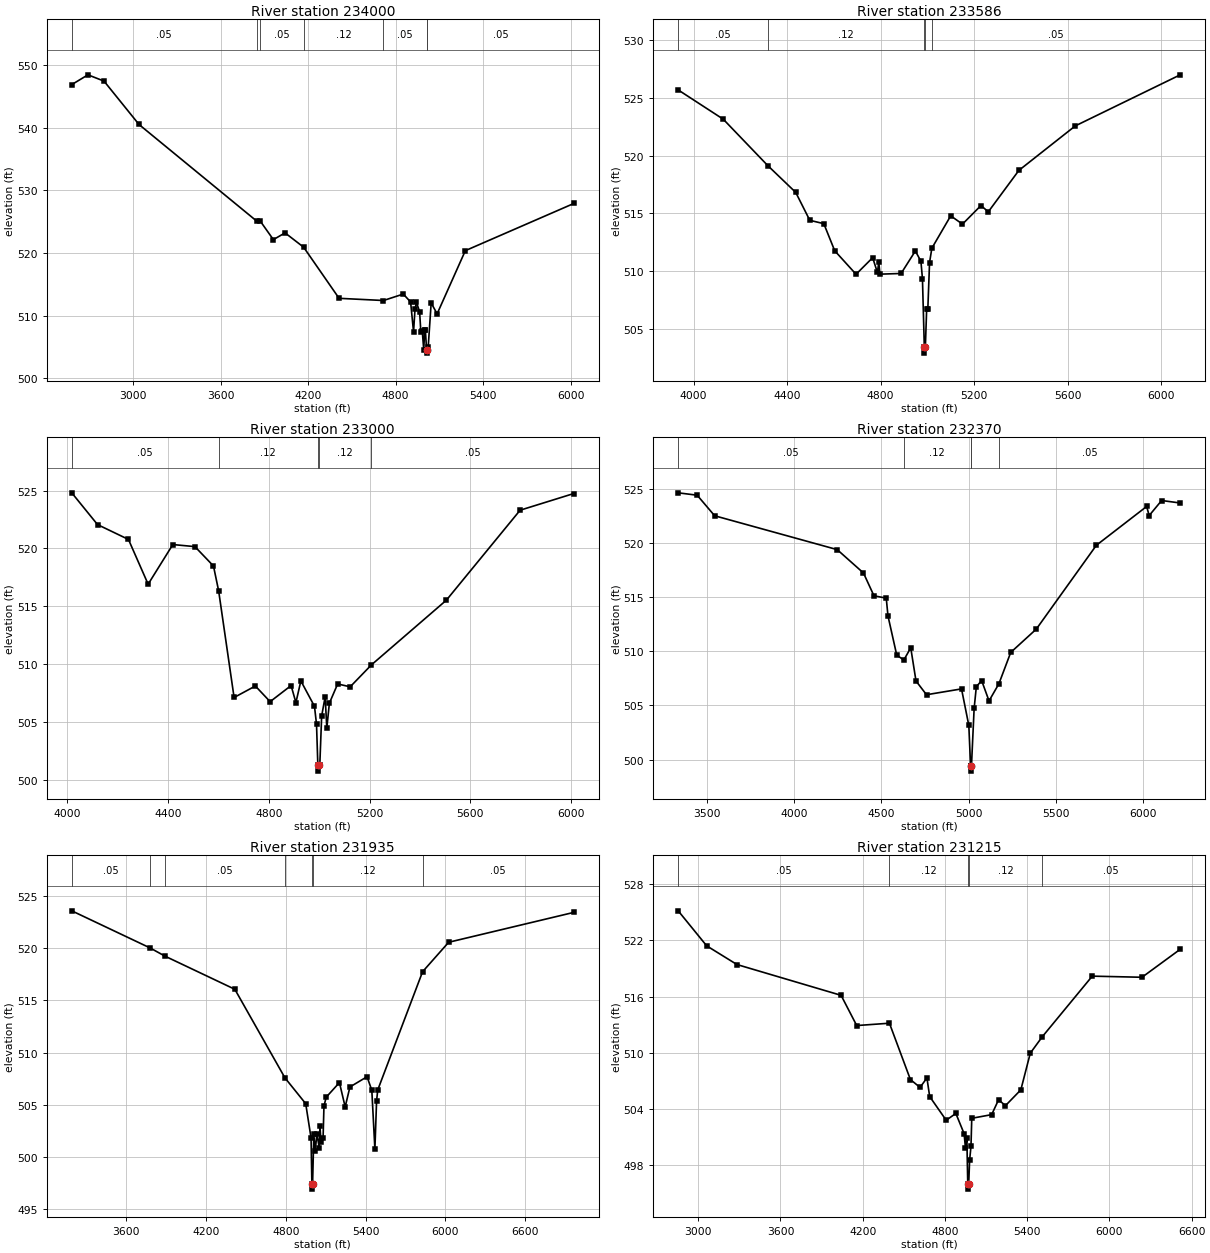
Type RM Length L Ch R = 1 ,234000  ,414,414,414
BEGIN DESCRIPTION:
Kings Creek 463.0
END DESCRIPTION:
XS GIS Cut Line= 3
      2660896.71      6978898.64      2658479.27      6978763.84
      2657475.96      6978961.01
#Sta/Elev= 30
  2578.8  546.88  2689.7  548.44  2799.9  547.44  3040.2  540.51  3847.8  525.08
  3869.6  525.16  3961.7  522.13  4041.8  523.21  4169.3  520.92  4412.4  512.76
  4716.9  512.41    4853  513.44  4903.1  512.17  4923.2   507.4  4933.2  511.02
  4943.2  512.11  4964.7  510.64  4973.2  507.45  4983.2  507.48  4993.3  504.52
  4999.1  507.75  5004.2  507.75  5012.7  504.51  5013.1  504.01  5017.1  504.51
  5023.7  504.97  5044.1  512.02  5084.9  510.28  5278.5  520.37  6022.5   527.9
#Mann= 7 ,-1 , 0
  2578.8     .05       0  3847.8     .12       0  3869.6     .05       0
  4169.3     .12       0  4716.9     .05       0  5012.7     .04       0
  5017.1     .05       0
Bank Sta=5012.7,5017.1
XS Rating Curve= 0 ,0
Exp/Cntr=0.3,0.1

Type RM Length L Ch R = 1 ,233586  ,586,586,586
BEGIN DESCRIPTION:
Kings Creek 462.0
END DESCRIPTION:
XS GIS Cut Line= 3
      2659526.02        6978561.      2658475.61      6978381.13
      2657399.69      6978496.61
#Sta/Elev= 30
  3934.3   525.7  4127.1  523.16  4317.9  519.13  4437.2  516.81  4497.3  514.39
  4557.3   514.1  4603.9  511.75  4695.2  509.71  4766.3  511.15  4786.5  509.87
  4792.5  510.75  4797.6  509.72    4888  509.78  4948.9  511.73  4972.7  510.84
  4979.3  509.33  4987.3  503.37  4987.7  502.87  4991.7  503.37  4997.3  506.69
  5002.3  506.69  5009.7  510.73  5019.5  511.97  5100.2  514.78  5150.5  514.06
  5229.5  515.67  5261.1  515.13  5391.8  518.72  5633.2  522.58  6082.1  527.01
#Mann= 5 ,-1 , 0
  3934.3     .05       0  4317.9     .12       0  4987.3     .07       0
  4991.7     .12       0  5019.5     .05       0
Bank Sta=4987.3,4991.7
XS Rating Curve= 0 ,0
Exp/Cntr=0.3,0.1

Type RM Length L Ch R = 1 ,233000  ,630,630,630
BEGIN DESCRIPTION:
Kings Creek 461.0
END DESCRIPTION:
XS GIS Cut Line= 3
      2659576.02        6978061.      2658615.63       6977851.4
      2657625.98        6978061.
#Sta/Elev= 30
    4017   524.8  4119.4  522.06  4242.2  520.78  4320.4  516.92  4418.5  520.34
  4506.3  520.16    4580  518.49  4600.6  516.34  4661.9  507.15  4746.4  508.14
  4805.1  506.79  4888.4  508.18  4907.5  506.71  4927.2  508.58  4981.3  506.39
  4989.4  504.84  4994.7   501.3  4995.4   500.8  4999.8   501.3  5002.4   501.3
  5009.8  505.55  5023.7  507.21  5030.3  504.51  5040.5  506.66  5073.4  508.32
  5123.1  508.07  5207.4  509.96  5505.2  515.54  5798.2   523.3  6011.6  524.74
#Mann= 5 ,-1 , 0
    4017     .05       0  4600.6     .12       0  4994.7     .07       0
  4999.8     .12       0  5207.4     .05       0
Bank Sta=4994.7,4999.8
XS Rating Curve= 0 ,0
Exp/Cntr=0.3,0.1

Type RM Length L Ch R = 1 ,232370  ,435,435,435
BEGIN DESCRIPTION:
Mapping XS 587c7e8e
END DESCRIPTION:
XS GIS Cut Line= 3
      2660174.32      6977465.51      2658518.09      6977350.93
      2657379.28      6977772.13
#Sta/Elev= 30
  3337.6  524.65  3446.2  524.43  3546.4  522.53  4248.1   519.4  4398.5  517.24
  4458.6  515.13  4528.8  514.92  4538.8  513.27  4588.9  509.65  4629.6   509.2
  4669.1  510.33  4699.2  507.26  4759.3  505.99  4959.8  506.53  5001.6  503.15
  5011.6  499.43  5012.3  498.93  5016.8  499.43    5032  504.72  5044.6  506.73
    5075   507.3  5117.3  505.42    5174  507.01  5241.5   509.9  5388.2  512.06
  5731.7   519.8  6019.8  523.39  6034.2  522.55  6105.7  523.94    6212  523.71
#Mann= 5 ,-1 , 0
  3337.6     .05       0  4629.6     .12       0  5011.6     .07       0
  5016.8     .12       0    5174     .05       0
Bank Sta=5011.6,5016.8
XS Rating Curve= 0 ,0
Exp/Cntr=0.3,0.1

Type RM Length L Ch R = 1 ,231935  ,720,720,720
BEGIN DESCRIPTION:
Mapping XS 36656934
END DESCRIPTION:
XS GIS Cut Line= 5
      2660325.34      6977168.63       2658523.3      6976986.34
      2658330.59      6976903.01      2658146.82       6976635.2
      2656736.85      6976413.43
#Sta/Elev= 30
  3191.5  523.58  3781.3  520.02  3892.4  519.24  4417.1  516.07  4793.8  507.59
  4949.8  505.12    4990  501.84  4996.2  497.44    4997  496.94  5001.5  497.44
  5010.7  502.17  5021.6  500.57  5033.4  502.25  5051.4  500.92  5056.9  502.98
  5065.2  501.42  5080.3  501.82    5087  504.89  5103.8  505.74  5203.3  507.14
  5246.4  504.81  5282.2  506.72  5410.8   507.7  5446.7   506.4  5469.8  500.76
  5482.5  505.39  5491.4  506.44  5828.2  517.75  6024.2  520.57  6964.8  523.43
#Mann= 7 ,-1 , 0
  3191.5     .05       0  3781.3     .12       0  3892.4     .05       0
  4793.8     .12       0  4996.2     .07       0  5001.5     .12       0
  5828.2     .05       0
Bank Sta=4996.2,5001.5
XS Rating Curve= 0 ,0
Exp/Cntr=0.3,0.1

Type RM Length L Ch R = 1 ,231215  ,1052,1052,1052
BEGIN DESCRIPTION:
Mapping XS 20e9b5ba
END DESCRIPTION:
XS GIS Cut Line= 3
      2660762.86      6976538.42      2658622.26       6976335.3
      2657119.04      6976163.65
#Sta/Elev= 30
  2853.6  525.17  3061.4  521.43  3282.4  519.43  4042.2  516.14  4156.3  512.91
    4395  513.16    4548  507.14  4618.3   506.3  4668.6  507.31  4688.7  505.32
  4809.2  502.79  4879.5  503.52  4939.8  501.36  4949.8  499.82  4959.9  500.85
  4966.6  495.93  4967.6  495.43  4973.3  495.93    4980   498.5    4990     500
  4995.7     503    5141  503.39  5191.3  504.98  5241.6  504.35  5353.8  506.04
  5422.8  509.96  5510.6  511.72  5874.9  518.19    6238  518.07  6516.8  521.06
#Mann= 5 ,-1 , 0
  2853.6     .05       0    4395     .12       0  4966.6     .07       0
  4973.3     .12       0  5510.6     .05       0
Bank Sta=4966.6,4973.3
XS Rating Curve= 0 ,0
Exp/Cntr=0.3,0.1

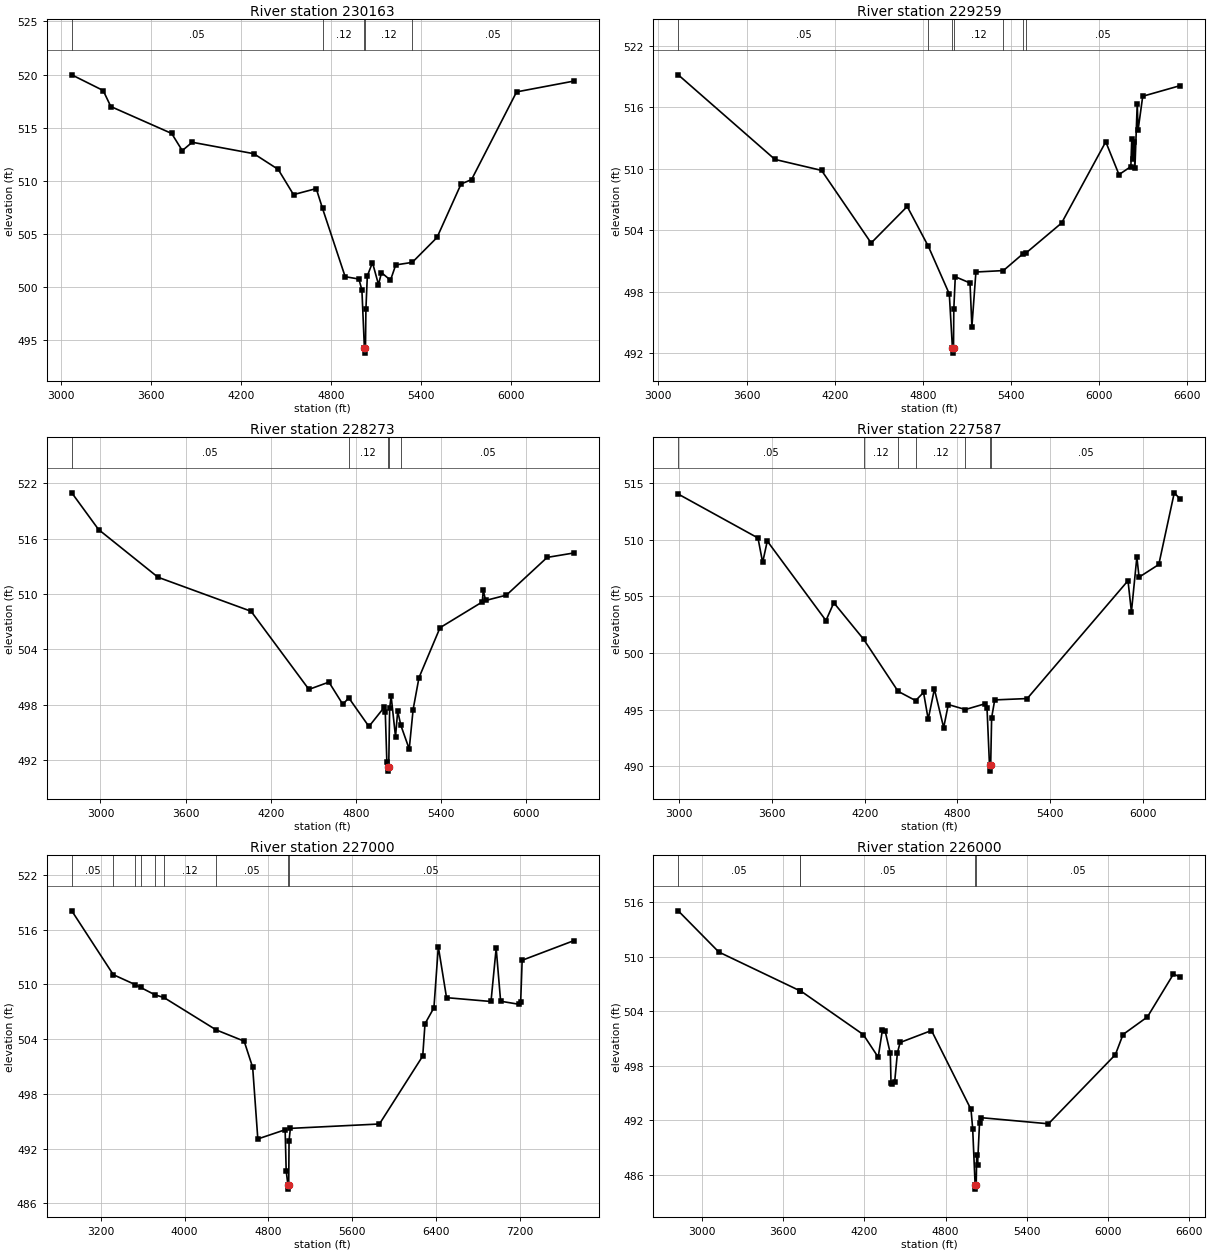
Type RM Length L Ch R = 1 ,230163  ,904,904,904
BEGIN DESCRIPTION:
Mapping XS 10ed9aab
END DESCRIPTION:
XS GIS Cut Line= 3
      2660522.41      6975827.48      2658579.72      6975504.57
       2657204.7      6975514.99
#Sta/Elev= 30
  3072.7  519.97  3281.9  518.49  3332.6  516.98  3738.1  514.44  3808.8  512.82
  3874.8  513.61  4285.5  512.53  4447.7  511.05  4549.8  508.67  4701.1  509.24
    4743  507.37  4893.8  500.93    4985  500.71  5005.3  499.68  5021.9  494.22
  5023.1  493.72  5029.1  494.22    5032  497.85  5041.4     501  5075.8  502.26
  5115.8  500.19  5135.8  501.31  5195.8   500.6  5230.7  502.04  5340.8  502.28
  5505.8  504.63  5665.8  509.67  5735.8  510.09  6035.8  518.36  6417.1  519.38
#Mann= 5 ,-1 , 0
  3072.7     .05       0    4743     .12       0  5021.9     .07       0
  5029.1     .12       0  5340.8     .05       0
Bank Sta=5021.9,5029.1
XS Rating Curve= 0 ,0
Exp/Cntr=0.3,0.1

Type RM Length L Ch R = 1 ,229259  ,986,986,986
BEGIN DESCRIPTION:
Mapping XS 0ee7e6f1
END DESCRIPTION:
XS GIS Cut Line= 4
      2660549.34      6975090.51      2658716.01      6974694.68
      2658064.97       6974647.8      2657294.16       6975090.5
#Sta/Elev= 30
  3134.9  519.17  3793.1  510.92  4110.2  509.85  4447.8  502.77  4693.3  506.33
  4837.6  502.43  4979.8   497.8  5001.1  492.53  5002.3  492.03  5008.4  492.53
  5010.5  496.33  5020.5  499.48  5120.8  498.87  5133.6  494.61  5160.9  499.94
  5347.8  500.08  5481.4  501.72  5499.1  501.76  5744.2  504.72  6044.7  512.64
  6134.8  509.44  6215.5  510.22  6221.6   512.9  6227.3  510.96  6237.4  512.62
  6243.1  510.06  6258.9  516.36  6264.7  513.79  6296.3  517.08  6552.1  518.12
#Mann= 7 ,-1 , 0
  3134.9     .05       0  4837.6     .12       0  5001.1     .07       0
  5008.4     .12       0  5347.8     .05       0  5481.4     .12       0
  5499.1     .05       0
Bank Sta=5001.1,5008.4
XS Rating Curve= 0 ,0
Exp/Cntr=0.3,0.1

Type RM Length L Ch R = 1 ,228273  ,686,686,686
BEGIN DESCRIPTION:
Kings Creek 452.0
END DESCRIPTION:
XS GIS Cut Line= 4
      2660726.39      6974559.25      2658622.05      6973909.37
      2658314.97      6973830.09      2657379.24      6974230.38
#Sta/Elev= 30
  2797.6  520.96  2986.4  516.98    3405  511.81  4060.8  508.12  4468.3  499.65
  4609.3  500.44  4707.2  498.03  4749.3  498.73  4891.2  495.63    5000  497.73
  5006.3  497.21  5017.6  491.74  5023.1  491.29  5024.3  490.79  5030.7  491.29
  5037.2   497.6  5047.6  498.92  5078.5  494.52  5093.8  497.29  5116.2  495.75
  5175.1  493.18  5202.5  497.47  5243.8  500.92  5392.2  506.34  5689.7  509.13
  5696.7   510.4  5713.3  509.29  5859.9  509.87  6146.9  513.96  6334.9  514.44
#Mann= 5 ,-1 , 0
  2797.6     .05       0  4749.3     .12       0  5023.1     .07       0
  5030.7     .12       0  5116.2     .05       0
Bank Sta=5023.1,5030.7
XS Rating Curve= 0 ,0
Exp/Cntr=0.3,0.1

Type RM Length L Ch R = 1 ,227587  ,587,587,587
BEGIN DESCRIPTION:
Kings Creek 450.0
END DESCRIPTION:
XS GIS Cut Line= 3
      2660851.45      6973408.22      2658505.06      6973329.38
      2657816.29      6973907.11
#Sta/Elev= 30
  2994.2  514.04  3509.9  510.16    3540     508    3570  509.89  3949.4  502.87
  4000.2  504.44  4193.3  501.21  4415.7  496.62  4529.2   495.8  4580.5  496.52
  4610.6  494.15  4650.6  496.82  4710.6  493.41  4740.6  495.45    4851  495.01
  4980.8  495.53  4990.8  495.18    5007  490.07  5008.1  489.57  5014.6  490.07
  5020.8  494.29  5040.8  495.86  5250.9  495.98  5902.6  506.39  5924.7  503.63
  5959.9  508.47  5974.2   506.7  6101.7  507.82  6201.8  514.15  6240.9  513.59
#Mann= 7 ,-1 , 0
  2994.2     .05       0  4193.3     .12       0  4415.7     .05       0
  4529.2     .12       0    4851     .05       0    5007     .04       0
  5014.6     .05       0
Bank Sta=5007,5014.6
XS Rating Curve= 0 ,0
Exp/Cntr=0.3,0.1

Type RM Length L Ch R = 1 ,227000  ,1000,1000,1000
BEGIN DESCRIPTION:
Kings Creek 449.0
END DESCRIPTION:
XS GIS Cut Line= 4
      2660997.26      6972658.22      2658926.08      6972812.24
      2657977.07      6972793.37      2656663.96       6973975.9
#Sta/Elev= 30
  2923.1  518.06  3319.5  511.06  3528.6  509.97  3580.5  509.66  3719.2  508.84
  3802.3  508.56  4300.9  505.01  4568.9  503.77  4650.1   500.9  4699.3  493.05
    4960  494.06    4970  489.58  4986.1  488.05  4987.3  487.55  4994.1  488.05
  4997.5  492.86  5010.1  494.21  5860.3  494.69  6273.6  502.14  6295.3  505.68
  6380.5  507.43  6422.4  514.13  6500.9  508.54  6925.4  508.12  6974.7  513.96
  7017.3  508.15  7194.4  507.81  7208.6  508.07  7222.8  512.64  7716.3  514.79
#Mann= 9 ,-1 , 0
  2923.1     .05       0  3319.5     .12       0  3528.6     .05       0
  3580.5     .12       0  3719.2     .05       0  3802.3     .12       0
  4300.9     .05       0  4986.1     .03       0  4994.1     .05       0
Bank Sta=4986.1,4994.1
XS Rating Curve= 0 ,0
Exp/Cntr=0.3,0.1

Type RM Length L Ch R = 1 ,226000  ,616,616,616
BEGIN DESCRIPTION:
Kings Creek 447.0
END DESCRIPTION:
XS GIS Cut Line= 3
      2660783.68      6972163.42      2658623.82      6971917.61
      2657382.35      6972816.96
#Sta/Elev= 30
  2826.2  515.07  3125.8  510.53  3724.5  506.26  3726.5  506.28  4192.6  501.43
  4302.5  498.94  4333.5  501.93  4353.7  501.82    4392  499.35  4397.1  496.14
    4404  495.98  4424.1  496.22  4444.3  499.41  4464.4  500.56  4695.9  501.88
  4987.7  493.18    5000  491.08    5018   484.9  5019.2   484.4  5026.1   484.9
  5029.8  488.16  5035.9  487.06  5050.6  491.69    5059  492.28  5559.5   491.6
  6053.6  499.22    6110  501.44  6290.2  503.38  6482.7  508.11    6533  507.76
#Mann= 5 ,-1 , 0
  2826.2     .05       0  3724.5     .12       0  3726.5     .05       0
    5018     .03       0  5026.1     .05       0
Bank Sta=5018,5026.1
XS Rating Curve= 0 ,0
Exp/Cntr=0.3,0.1

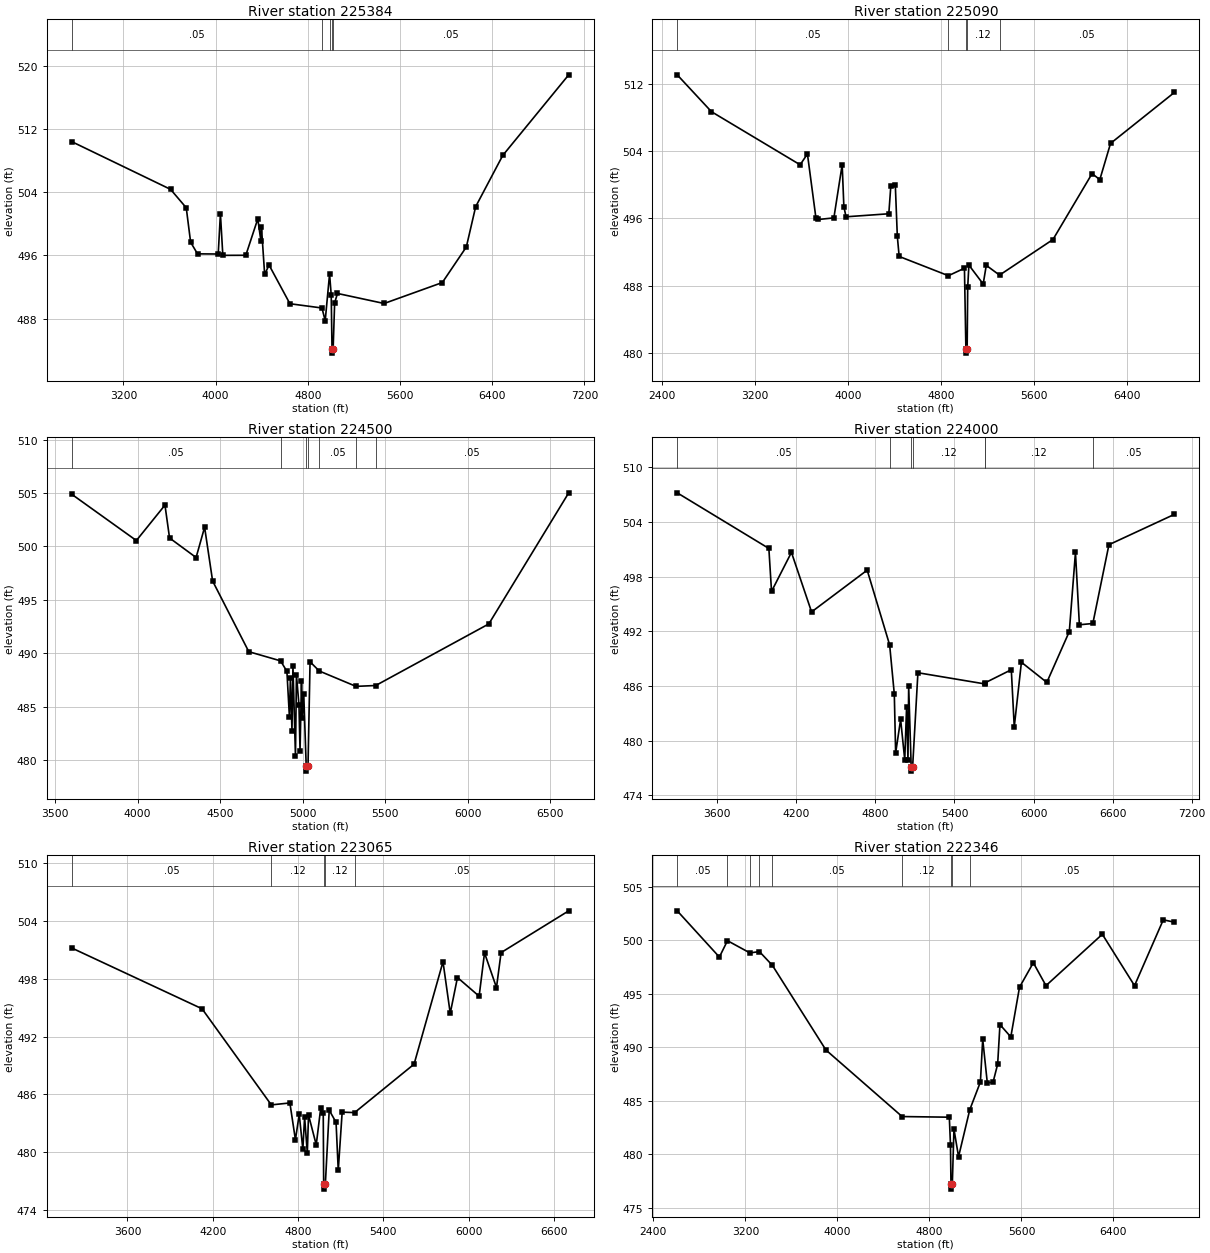
Type RM Length L Ch R = 1 ,225384  ,294,294,294
BEGIN DESCRIPTION:
Kings Creek 446.0
END DESCRIPTION:
XS GIS Cut Line= 5
      2660460.84      6971929.06       2658648.3      6971371.76
      2658299.34      6971434.26       2656960.8      6971923.84
      2656466.16      6972326.71
#Sta/Elev= 30
  2749.5   510.4  3608.9  504.35  3744.9  502.02  3782.9  497.66  3842.6  496.19
  4022.3  496.17  4041.4  501.27  4062.3     496  4261.7  496.01  4365.7  500.62
  4392.5  497.83  4397.7  499.53  4425.2  493.58  4463.2  494.78  4644.4  489.88
  4922.4  489.34  4950.6  487.73  4988.5  493.64  5002.8  490.98  5009.7  484.13
    5011  483.63  5019.3  484.13  5032.5     490  5057.1  491.18  5461.7  489.91
  5966.8  492.56  6175.1  497.06  6256.1  502.16    6491  508.64  7063.5  518.84
#Mann= 5 ,-1 , 0
  2749.5     .05       0  4922.4     .12       0  4988.5     .05       0
  5009.7     .04       0  5019.3     .05       0
Bank Sta=5009.7,5019.3
XS Rating Curve= 0 ,0
Exp/Cntr=0.3,0.1

Type RM Length L Ch R = 1 ,225090  ,590,590,590
BEGIN DESCRIPTION:
Kings Creek 445.0
END DESCRIPTION:
XS GIS Cut Line= 3
      2660637.87      6971892.59        2658276.        6971186.
      2656509.31      6971564.12
#Sta/Elev= 30
  2534.7  513.06  2828.9  508.68  3590.9  502.37  3653.5  503.66  3726.6  496.04
  3748.3  495.87  3880.7  496.06  3952.1  502.39  3966.6   497.4  3985.2  496.19
  4352.8  496.55  4370.2  499.89  4408.6  499.97  4425.9  493.87  4441.7  491.48
  4864.8  489.19  5002.6  490.08  5015.1  480.49  5016.6  479.99  5025.8  480.49
  5030.7  487.83  5040.9  490.45  5163.6   488.2  5190.2  490.42  5304.2  489.26
  5763.2  493.49  6099.2  501.32  6165.8  500.61  6257.9  504.91  6806.7  510.97
#Mann= 5 ,-1 , 0
  2534.7     .05       0  4864.8     .12       0  5015.1     .07       0
  5025.8     .12       0  5304.2     .05       0
Bank Sta=5015.1,5025.8
XS Rating Curve= 0 ,0
Exp/Cntr=0.3,0.1

Type RM Length L Ch R = 1 ,224500  ,500,500,500
BEGIN DESCRIPTION:
Kings Creek 444.0
END DESCRIPTION:
XS GIS Cut Line= 4
      2659799.32      6971517.58      2658612.63      6970773.83
      2657950.38      6970663.43      2657076.01      6971010.99
#Sta/Elev= 30
  3599.5   504.9  3992.4  500.55  4165.7  503.87  4193.5  500.79  4354.3  498.96
  4405.9   501.8  4454.4  496.76  4673.6  490.14  4866.1  489.28  4904.6   488.3
  4919.9  484.01  4925.8  487.65  4935.3  482.75  4941.2   488.8  4956.5  480.35
  4962.4  487.98  4977.7  485.14  4984.2  480.84    4993   487.4    4998  483.88
  5006.7  486.15  5021.5  479.45    5023  478.95  5032.5  479.45  5044.9  489.19
  5100.6  488.33  5323.2  486.89  5442.9  486.97  6128.1  492.74  6612.3  505.02
#Mann= 7 ,-1 , 0
  3599.5     .05       0  4866.1     .12       0  5021.5     .07       0
  5032.5     .12       0  5100.6     .05       0  5323.2     .12       0
  5442.9     .05       0
Bank Sta=5021.5,5032.5
XS Rating Curve= 0 ,0
Exp/Cntr=0.3,0.1

Type RM Length L Ch R = 1 ,224000  ,935,935,935
BEGIN DESCRIPTION:
Kings Creek 443.0
END DESCRIPTION:
XS GIS Cut Line= 3
      2660382.71      6970653.01      2658700.22      6970385.01
      2656773.27      6969632.16
#Sta/Elev= 30
  3296.3  507.18  3991.7  501.08  4011.9  496.37    4163  500.65  4315.7  494.12
  4737.7   498.7  4908.1   490.5  4943.5  485.11  4953.6  478.65  4991.4  482.33
  5022.7   477.9  5036.7   483.7  5047.2  477.84  5052.5  485.99  5071.5  477.16
    5073  476.66  5082.6  477.16  5122.6  487.45  5631.7  486.22  5634.4  486.36
  5831.2  487.78  5853.6  481.51  5907.9   488.6  6100.7  486.39  6271.4  491.97
    6318  500.64  6347.8  492.71  6449.8  492.85    6572  501.49  7068.8  504.82
#Mann= 7 ,-1 , 0
  3296.3     .05       0  4908.1     .12       0  5071.5     .07       0
  5082.6     .12       0  5631.7     .05       0  5634.4     .12       0
  6449.8     .05       0
Bank Sta=5071.5,5082.6
XS Rating Curve= 0 ,0
Exp/Cntr=0.3,0.1

Type RM Length L Ch R = 1 ,223065  ,719,719,719
BEGIN DESCRIPTION:
Kings Creek 442.0
END DESCRIPTION:
XS GIS Cut Line= 5
      2659841.02      6970350.93      2658830.59      6969486.34
      2658399.73      6969618.08      2657768.09      6969762.38
        2656716.      6969569.67
#Sta/Elev= 30
  3206.6  501.19  4124.8  494.88  4612.1  484.92  4742.8  485.12  4781.8   481.3
  4808.4  483.95    4834  480.32  4846.4  483.65  4865.4  479.94    4874  483.87
  4928.2  480.78  4959.5  484.56  4977.5  484.04  4980.5  476.69  4982.1  476.19
  4992.2  476.69  5019.5  484.37  5067.6  483.11  5083.1  478.14  5110.6  484.17
    5198  484.12  5616.5  489.14    5820  499.75  5870.9  494.41  5921.7  498.12
  6074.2  496.18  6112.1  500.67  6196.2  497.08  6228.6   500.7  6704.5  505.03
#Mann= 5 ,-1 , 0
  3206.6     .05       0  4612.1     .12       0  4980.5     .07       0
  4992.2     .12       0    5198     .05       0
Bank Sta=4980.5,4992.2
XS Rating Curve= 0 ,0
Exp/Cntr=0.3,0.1

Type RM Length L Ch R = 1 ,222346  ,810,810,810
BEGIN DESCRIPTION:
Kings Creek 441.0
END DESCRIPTION:
XS GIS Cut Line= 4
      2659934.79      6970340.54      2658780.62      6969139.85
      2658059.16       6969044.4      2656129.23      6969012.41
#Sta/Elev= 30
  2606.8  502.75  2973.4  498.43  3043.9  499.96  3238.7  498.82  3321.8  498.94
  3434.7  497.65  3899.8  489.75  4562.4  483.53  4972.9  483.47  4982.9  480.91
  4987.3  477.25  4988.9  476.75    4999  477.25  5013.2  482.35  5053.2  479.78
  5150.8  484.17  5243.2  486.76  5263.2  490.76  5303.2  486.68  5353.2  486.74
  5393.2  488.42  5413.2  492.12  5507.6  490.97  5583.2  495.61  5703.3   497.9
  5813.3  495.76  6303.3  500.56  6583.4  495.76  6833.4  501.91  6930.2  501.69
#Mann= 9 ,-1 , 0
  2606.8     .05       0  3043.9    .075       0  3238.7     .05       0
  3321.8    .075       0  3434.7     .05       0  4562.4     .12       0
  4987.3     .07       0    4999     .12       0  5150.8     .05       0
Bank Sta=4987.3,4999
XS Rating Curve= 0 ,0
Exp/Cntr=0.3,0.1