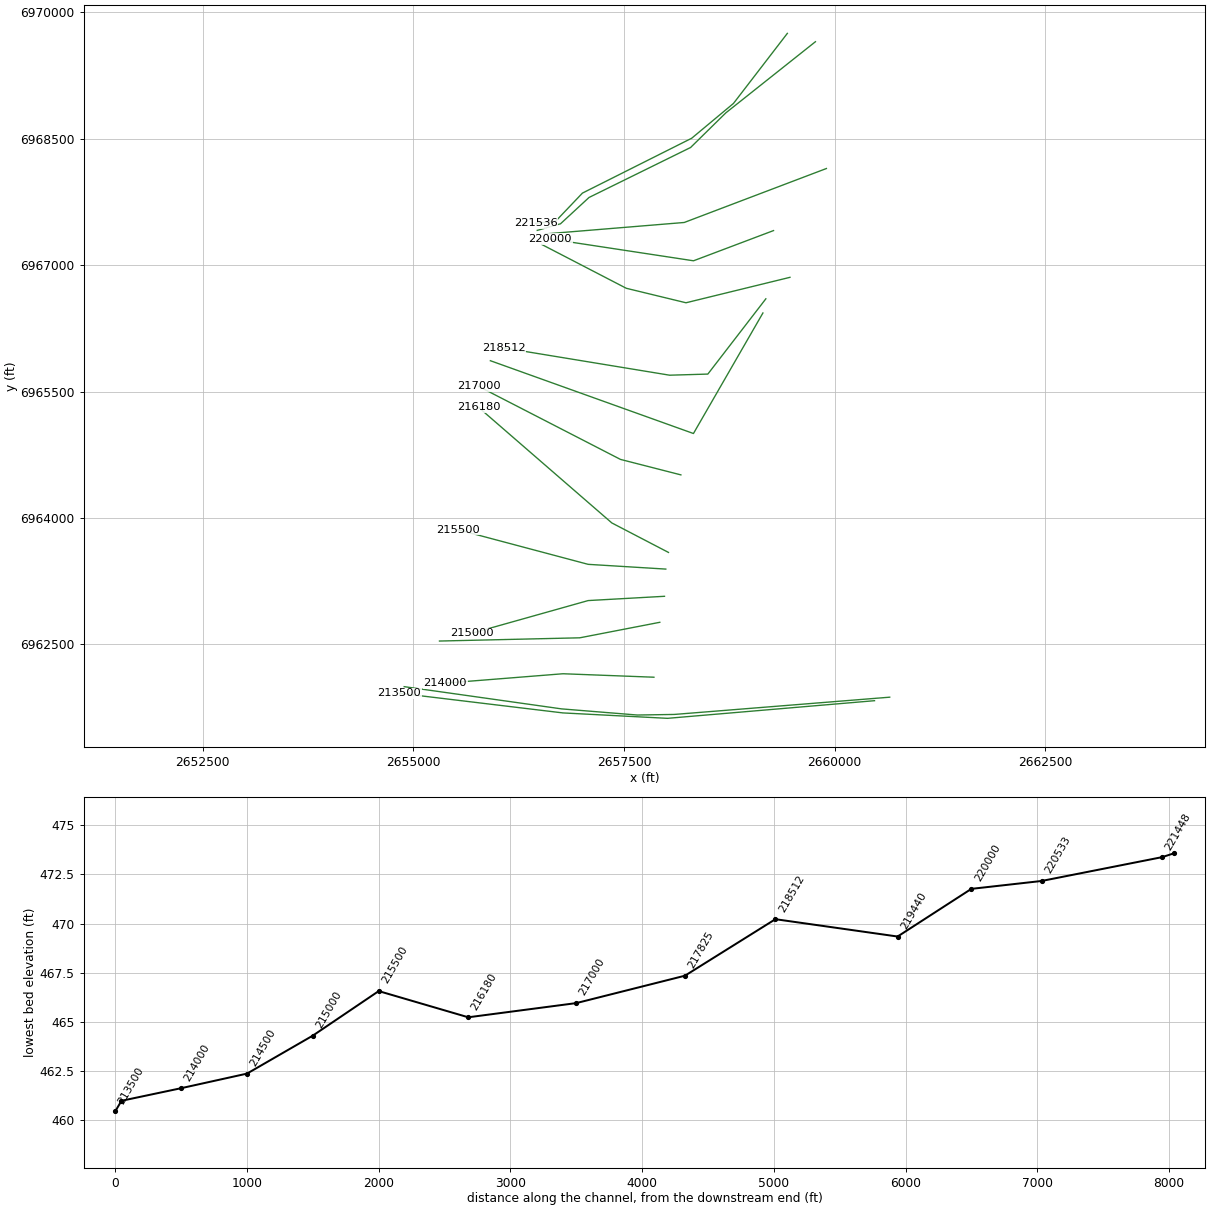
HEC-RAS study Kings Creek.prj: Kings Creek Base Level Engineering

--- Kings Creek.g01 (geometry) --- (continued)

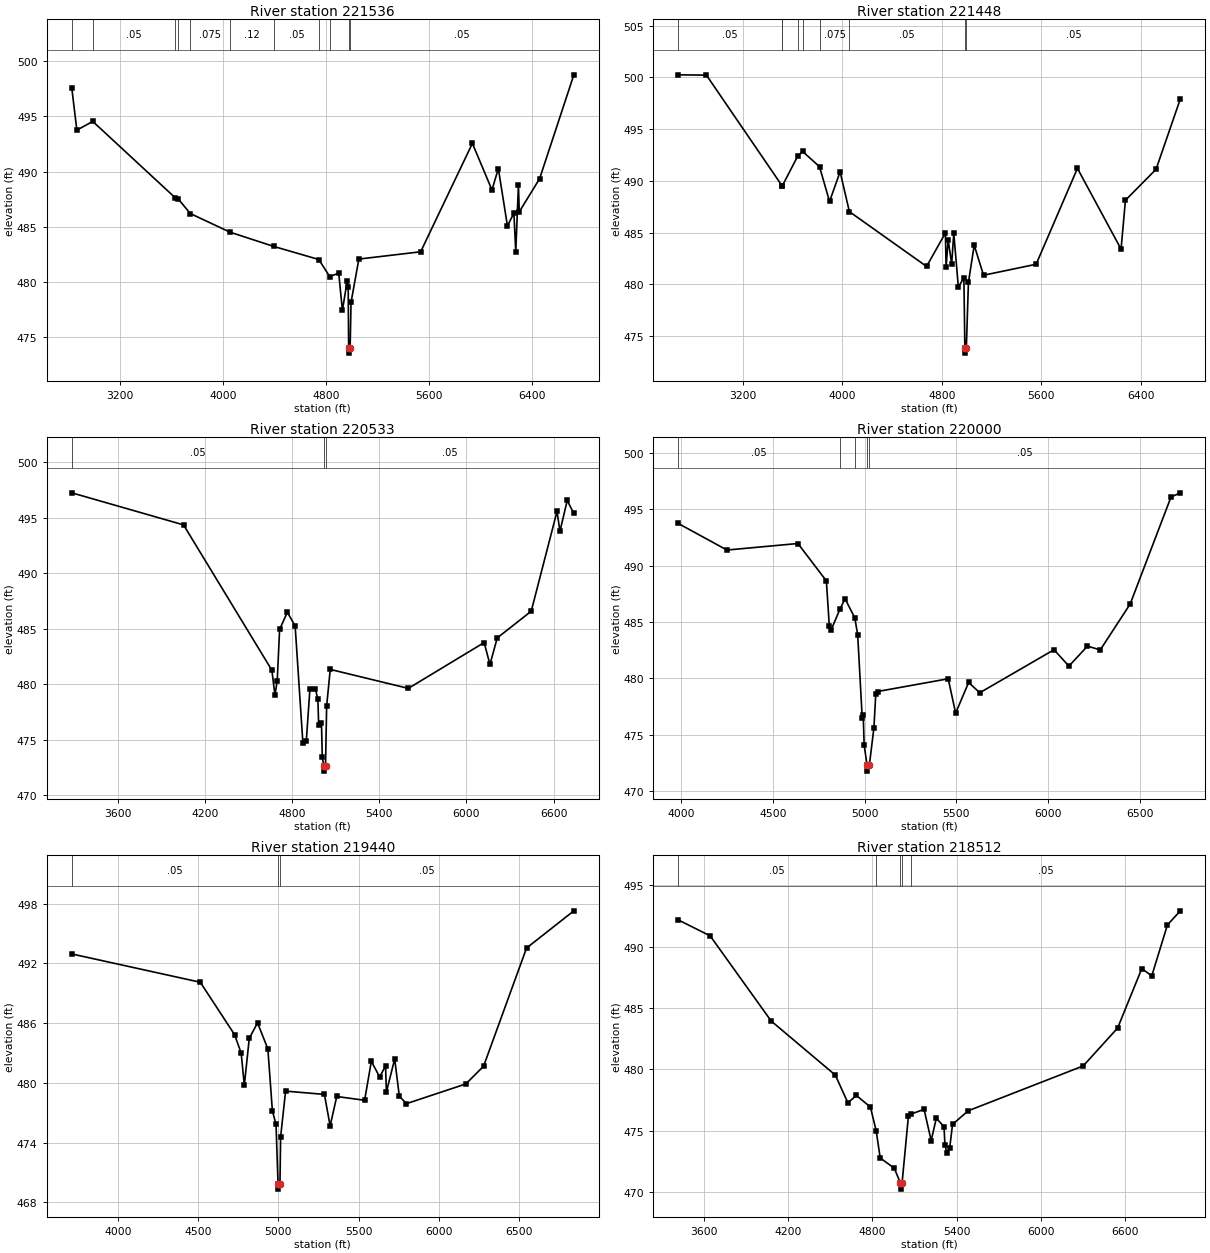
Type RM Length L Ch R = 1 ,221536  ,88,88,88
BEGIN DESCRIPTION:
Mapping XS 1dcc8f9b
END DESCRIPTION:
XS GIS Cut Line= 6
      2659439.98      6969751.98      2658800.58      6968920.52
      2658304.55      6968507.18      2657007.68      6967856.13
      2656689.97       6967522.8      2656450.67      6967496.79
#Sta/Elev= 30
  2824.7  497.58  2864.2  493.76  2987.7  494.55    3628  487.64  3653.2   487.5
  3746.5   486.2  4055.9  484.51  4395.8  483.22  4744.3  482.04  4829.5  480.49
  4898.9  480.81  4927.7  477.43  4965.3  480.13  4972.8  479.56    4976  474.06
  4977.6  473.56  4987.7  474.06  4994.8  478.16  5055.6  482.08  5535.7  482.74
  5937.7  492.56  6089.9  488.34  6139.4  490.28    6210  485.09  6260.4  486.24
  6274.7  482.73  6295.5  488.79    6302  486.36  6460.3  489.37  6726.1  498.77
#Mann= 11 ,-1 , 0
  2824.7    .075       0  2987.7     .05       0    3628    .075       0
  3653.2     .05       0  3746.5    .075       0  4055.9     .12       0
  4395.8     .05       0  4744.3     .12       0  4829.5     .05       0
    4976     .03       0  4987.7     .05       0
Bank Sta=4976,4987.7
XS Rating Curve= 0 ,0
Exp/Cntr=0.3,0.1

Type RM Length L Ch R = 1 ,221448  ,915,915,915
BEGIN DESCRIPTION:
Mapping XS a04edc19
END DESCRIPTION:
XS GIS Cut Line= 6
      2659773.32      6969653.02       2658710.8      6968809.26
      2658291.69      6968397.51       2657085.8      6967804.05
      2656747.26      6967491.55      2656471.24      6967413.43
#Sta/Elev= 30
  2680.6  500.24  2907.2  500.21  3516.3  489.51  3517.9  489.53  3640.4  492.37
  3680.2  492.85  3816.6  491.37  3897.3  488.01  3982.2  490.88  4056.8  487.03
  4677.6  481.74  4828.9  484.97  4834.5   481.7  4851.3   484.3  4879.3  481.98
  4896.2  484.95  4932.8  479.76  4977.5  480.62  4985.5  473.87  4987.1  473.37
  4997.2  473.87  5014.1   480.2  5060.5  483.79  5135.6  480.89  5558.5  481.95
  5890.5  491.21  6241.4  483.41  6276.5  488.13  6522.7  491.12  6717.8  497.91
#Mann= 9 ,-1 , 0
  2680.6     .05       0  3516.3    .075       0  3517.9     .05       0
  3640.4    .075       0  3680.2     .05       0  3816.6    .075       0
  4056.8     .05       0  4985.5     .03       0  4997.2     .05       0
Bank Sta=4985.5,4997.2
XS Rating Curve= 0 ,0
Exp/Cntr=0.3,0.1

Type RM Length L Ch R = 1 ,220533  ,533,533,533
BEGIN DESCRIPTION:
Kings Creek 436.0
END DESCRIPTION:
XS GIS Cut Line= 3
      2659903.51       6968147.8      2658216.01      6967507.18
      2656570.58      6967371.79
#Sta/Elev= 30
  3283.2  497.25  4052.5  494.36  4660.4  481.26  4681.8  479.03  4697.4  480.28
  4713.8  484.93  4767.3  486.49  4820.8  485.24  4874.3  474.66  4897.7  474.91
  4922.4  479.55  4959.9  479.58  4977.4  478.64  4982.7   476.3  5002.1   476.5
  5007.5  473.41  5018.2  472.66  5019.8  472.16  5029.9  472.66  5037.6  478.03
  5062.4  481.33  5599.9  479.62  6121.7  483.75  6161.8  481.78    6212  484.17
  6445.9  486.58  6623.4  495.58  6643.5  493.78  6693.6  496.56  6739.2  495.39
#Mann= 3 ,-1 , 0
  3283.2     .05       0  5018.2     .03       0  5029.9     .05       0
Bank Sta=5018.2,5029.9
XS Rating Curve= 0 ,0
Exp/Cntr=0.3,0.1

Type RM Length L Ch R = 1 ,220000  ,560,560,560
BEGIN DESCRIPTION:
Kings Creek 435.0
END DESCRIPTION:
XS GIS Cut Line= 3
      2659276.01        6967411.      2658326.14      6967052.41
      2656625.99        6967311.
#Sta/Elev= 30
  3984.7  493.75  4250.1  491.39  4636.7  491.97  4791.7  488.65  4807.8  484.61
  4816.5  484.26  4865.8  486.15  4893.3  487.07  4946.4  485.37  4962.1  483.89
    4987  476.47  4992.3  476.78  4997.4  474.07  5013.7  472.26  5015.3  471.76
  5025.6  472.26  5050.7  475.62  5060.8  478.62  5070.9  478.83  5455.3  479.96
  5495.8  476.91  5566.6  479.63  5627.4  478.72  6031.9  482.54  6112.8  481.08
  6213.9  482.86  6283.6  482.52  6446.6   486.6  6669.1   496.1  6719.7  496.47
#Mann= 5 ,-1 , 0
  3984.7     .05       0  4865.8    .075       0  4946.4     .05       0
  5013.7     .05       0  5025.6     .05       0
Bank Sta=5013.7,5025.6
XS Rating Curve= 0 ,0
Exp/Cntr=0.3,0.1

Type RM Length L Ch R = 1 ,219440  ,928,928,928
BEGIN DESCRIPTION:
Mapping XS 995c998c
END DESCRIPTION:
XS GIS Cut Line= 4
      2659471.21      6966856.13      2658236.84      6966554.05
      2657528.51      6966725.93      2656524.02      6967246.39
#Sta/Elev= 30
  3711.4  492.95  4512.9  490.11  4726.2  484.86  4767.8     483  4787.5  479.76
  4818.3  484.48  4869.8  486.03  4934.3  483.42  4962.5  477.18  4985.2  475.85
  4997.7  469.84  4999.3  469.34  5009.6  469.84  5013.9   474.6  5044.8  479.18
    5287  478.85  5322.6  475.68  5363.8  478.64  5537.7  478.26  5579.5  482.17
  5631.5   480.6  5668.2  481.72  5673.3  479.08  5725.2  482.41    5754  478.67
  5798.3  477.92  6168.9   479.9  6279.5  481.68  6547.3  493.54  6842.4  497.28
#Mann= 3 ,-1 , 0
  3711.4     .05       0  4997.7     .05       0  5009.6     .05       0
Bank Sta=4997.7,5009.6
XS Rating Curve= 0 ,0
Exp/Cntr=0.3,0.1

Type RM Length L Ch R = 1 ,218512  ,687,687,687
BEGIN DESCRIPTION:
Kings Creek 433.0
END DESCRIPTION:
XS GIS Cut Line= 4
      2659184.78      6966600.96      2658496.19      6965707.51
      2658042.29      6965694.29      2656075.39      6966017.59
#Sta/Elev= 30
  3417.9  492.18  3645.1  490.88    4080  483.93  4536.6  479.52  4626.1  477.26
  4686.2  477.86  4786.2  476.92  4827.5  474.98  4856.2  472.76  4956.3  471.93
    5000  470.72  5001.6  470.22  5011.9  470.72    5057  476.17  5075.4  476.34
  5168.5  476.73  5219.2  474.18  5255.9  476.01  5310.4  475.31  5317.1  473.85
  5330.7  473.14  5350.9  473.56  5371.2   475.5  5482.7  476.61  6301.9  480.27
  6546.8  483.36  6719.1  488.21    6790  487.61  6901.5  491.77  6993.3  492.92
#Mann= 5 ,-1 , 0
  3417.9     .05       0  4827.5    .075       0    5000     .07       0
  5011.9    .075       0  5075.4     .05       0
Bank Sta=5000,5011.9
XS Rating Curve= 0 ,0
Exp/Cntr=0.3,0.1

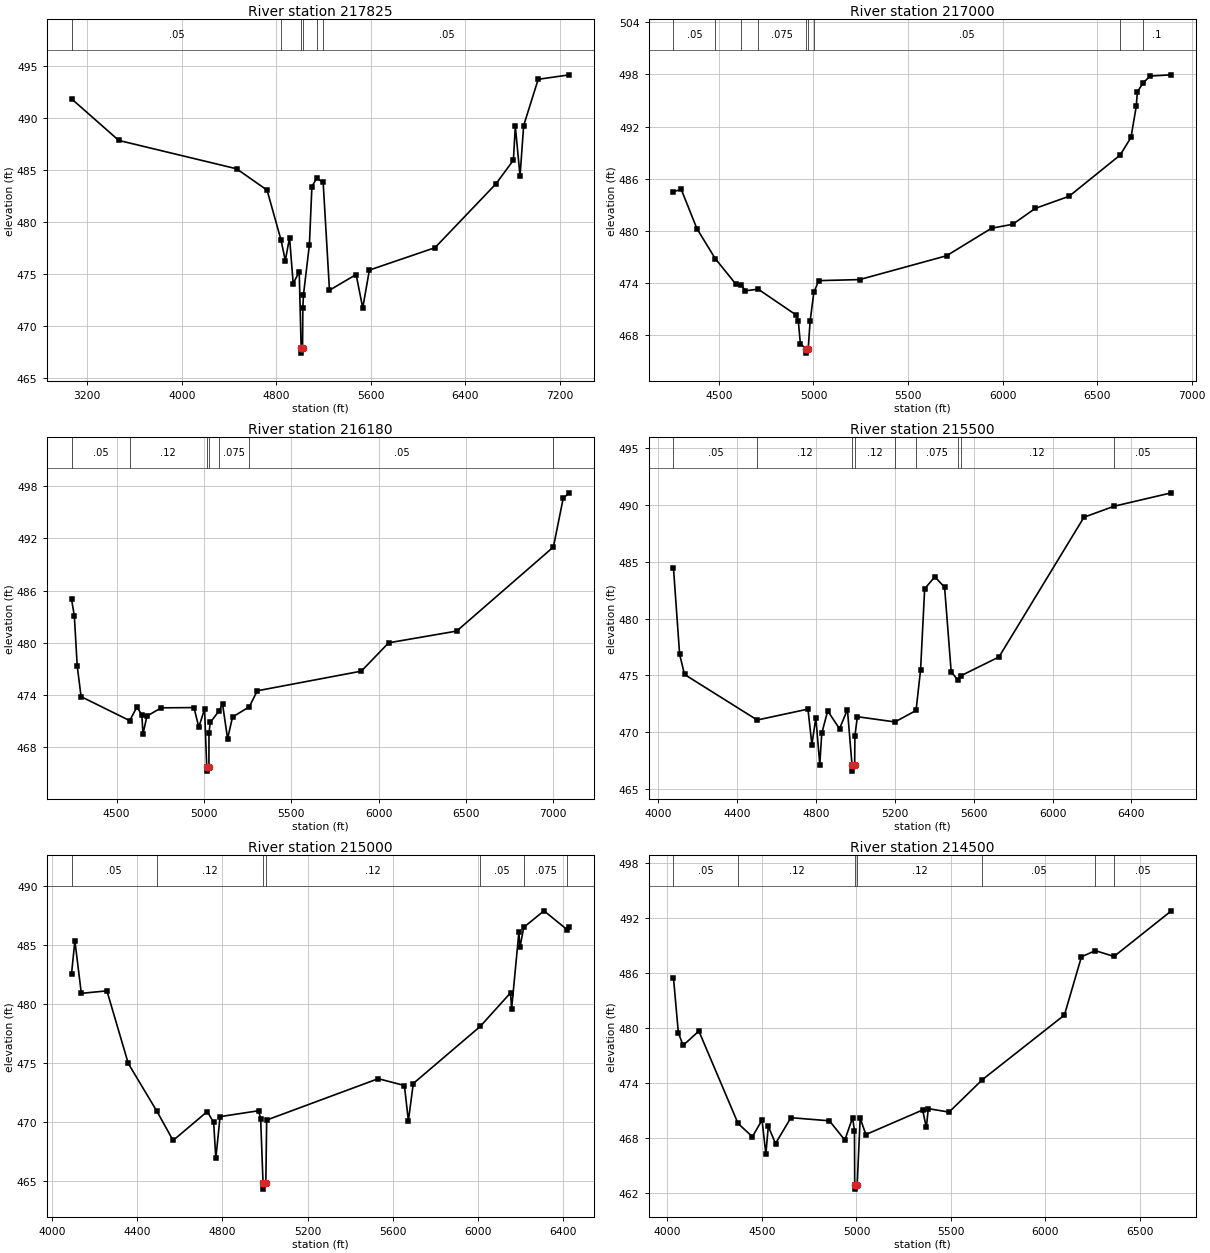
Type RM Length L Ch R = 1 ,217825  ,825,825,825
BEGIN DESCRIPTION:
Kings Creek 432.0
END DESCRIPTION:
XS GIS Cut Line= 3
      2659149.98      6966432.91      2658325.38      6965001.97
      2655914.67      6965866.28
#Sta/Elev= 30
    3068  491.81  3467.5  487.81  4464.5  485.08  4721.9  483.03  4840.5  478.21
  4876.3  476.25  4912.3  478.46  4943.1  474.03    4994   475.2  5010.4  467.85
    5012  467.35  5022.3  467.85  5024.7  471.72    5030  472.96  5080.1  477.77
  5101.3  483.37  5142.1  484.17  5196.6  483.77    5250   473.4  5475.3  474.91
  5531.5   471.7  5587.7  475.34  6142.4  477.49  6657.5  483.62    6806  485.91
  6822.3  489.18  6862.2  484.38  6892.9  489.24  7015.9  493.69  7280.5  494.12
#Mann= 6 ,-1 , 0
    3068     .05       0  4840.5     .12       0  5010.4     .07       0
  5022.3     .12       0  5142.1    .075       0  5196.6     .05       0
Bank Sta=5010.4,5022.3
XS Rating Curve= 0 ,0
Exp/Cntr=0.3,0.1

Type RM Length L Ch R = 1 ,217000  ,820,820,820
BEGIN DESCRIPTION:
Kings Creek 429.0
END DESCRIPTION:
XS GIS Cut Line= 3
      2658175.98        6964511.      2657458.83       6964694.7
      2655776.02      6965560.99
#Sta/Elev= 30
  4259.7  484.52    4301  484.77  4383.6  480.27  4480.4  476.83    4590  473.88
  4617.6  473.81  4639.5  473.12  4707.6  473.31    4910  470.32  4919.9  469.66
  4930.7  467.06  4959.6  466.46  4961.3  465.96  4972.2  466.46  4982.3  469.61
    5002  472.93    5028  474.29  5244.1  474.41  5704.1  477.15  5942.3  480.32
  6053.2  480.76  6172.9  482.59  6352.3  483.99  6621.8  488.72    6679  490.74
  6707.1  494.32  6712.8  495.98  6742.7     497  6780.3   497.8  6892.7  497.94
#Mann= 9 ,-1 , 0
  4259.7     .05       0  4480.4     .12       0  4617.6     .05       0
  4707.6    .075       0  4959.6     .07       0  4972.2    .075       0
    5002     .05       0  6621.8    .075       0  6742.7      .1       0
Bank Sta=4959.6,4972.2
XS Rating Curve= 0 ,0
Exp/Cntr=0.3,0.1

Type RM Length L Ch R = 1 ,216180  ,680,680,680
BEGIN DESCRIPTION:
Kings Creek 427.0
END DESCRIPTION:
XS GIS Cut Line= 3
      2658028.55      6963590.49      2657356.57      6963940.36
        2655776.        6965311.
#Sta/Elev= 30
  4242.4     485  4258.3  483.08  4274.7  477.35  4296.8  473.81  4574.9  471.05
  4617.1  472.63  4644.8  471.67  4651.1   469.5  4673.7  471.57  4755.3  472.52
  4942.9  472.55  4970.7   470.3  5003.7  472.37  5015.9  465.74  5017.7  465.24
  5028.6  465.74  5028.9  469.68  5036.5  470.84  5086.8  472.18  5106.7  472.95
  5135.2  468.97  5163.7  471.46  5259.8  472.64  5305.2  474.48  5900.8  476.74
  6057.4     480  6446.8  481.35  7000.2  491.02  7056.5  496.65  7092.1  497.25
#Mann= 7 ,-1 , 0
  4242.4     .05       0  4574.9     .12       0  5015.9     .07       0
  5028.6     .12       0  5086.8    .075       0  5259.8     .05       0
  7000.2    .075       0
Bank Sta=5015.9,5028.6
XS Rating Curve= 0 ,0
Exp/Cntr=0.3,0.1

Type RM Length L Ch R = 1 ,215500  ,500,500,500
BEGIN DESCRIPTION:
Kings Creek 426.0
END DESCRIPTION:
XS GIS Cut Line= 3
      2657997.24      6963392.59      2657075.27      6963449.01
      2655526.01        6963861.
#Sta/Elev= 30
  4076.3  484.48  4107.6  476.86  4132.4  475.08  4501.3  471.07  4758.8  472.03
  4778.9  468.91  4798.9  471.27  4818.9  467.15  4828.9   469.9    4859  471.87
  4919.1   470.3  4959.2  471.99  4982.7  467.07  4984.5  466.57  4995.8  467.07
  4997.1  469.67  5009.6  471.36  5200.7   470.9  5307.4  471.91  5330.4  475.49
  5351.1  482.62  5402.8  483.68  5452.3  482.75  5485.6  475.33  5518.3   474.6
    5533  474.95  5728.2  476.62  6159.5  488.92  6312.3  489.89  6603.1  491.07
#Mann= 9 ,-1 , 0
  4076.3     .05       0  4501.3     .12       0  4982.7     .07       0
  4995.8     .12       0  5200.7     .05       0  5307.4    .075       0
  5518.3     .05       0    5533     .12       0  6312.3     .05       0
Bank Sta=4982.7,4995.8
XS Rating Curve= 0 ,0
Exp/Cntr=0.3,0.1

Type RM Length L Ch R = 1 ,215000  ,500,500,500
BEGIN DESCRIPTION:
Kings Creek 425.0
END DESCRIPTION:
XS GIS Cut Line= 3
       2657981.6      6963069.67      2657075.52      6963018.89
      2655700.65      6962632.25
#Sta/Elev= 30
  4092.5   482.6  4108.1  485.38  4138.2  480.92  4258.4  481.13  4358.5  474.97
  4492.7  470.92  4568.8  468.44  4729.1  470.89  4759.1  469.97  4769.2  466.91
  4789.2  470.46  4969.5  470.96  4979.5   470.3  4990.7  464.81  4992.6  464.31
  5003.8  464.81  5007.7  470.17  5531.1  473.68  5653.9   473.1  5672.5   470.1
  5695.5  473.27  6009.3  478.11  6151.6  480.96  6156.8  479.61  6190.8  486.09
    6196  484.84  6213.7  486.52  6308.6  487.92    6418  486.31  6428.2  486.56
#Mann= 7 ,-1 , 0
  4092.5     .05       0  4492.7     .12       0  4990.7     .07       0
  5003.8     .12       0  6009.3     .05       0  6213.7    .075       0
    6418     .05       0
Bank Sta=4990.7,5003.8
XS Rating Curve= 0 ,0
Exp/Cntr=0.3,0.1

Type RM Length L Ch R = 1 ,214500  ,500,500,500
BEGIN DESCRIPTION:
Kings Creek 424.0
END DESCRIPTION:
XS GIS Cut Line= 3
      2657925.97        6962761.      2656975.77      6962576.78
      2655310.41      6962538.44
#Sta/Elev= 30
  4032.1  485.48  4057.9  479.47    4083  478.07  4166.5  479.64  4373.8  469.55
  4449.7   468.1  4500.6  469.93    4521  466.21  4533.8  469.24  4571.9  467.36
  4653.4  470.18  4857.2  469.84  4938.6  467.74  4979.4  470.18  4989.6  468.76
  4990.8  462.88  4992.6  462.38  5003.9  462.88  5019.8  470.12  5049.8  468.34
  5349.9  471.02  5369.9  469.11  5379.9  471.17  5489.9  470.79  5666.4  474.34
  6100.1  481.39  6190.1  487.75  6263.6  488.42  6362.6  487.79  6665.8  492.77
#Mann= 7 ,-1 , 0
  4032.1     .05       0  4373.8     .12       0  4990.8     .07       0
  5003.9     .12       0  5666.4     .05       0  6263.6    .075       0
  6362.6     .05       0
Bank Sta=4990.8,5003.9
XS Rating Curve= 0 ,0
Exp/Cntr=0.3,0.1

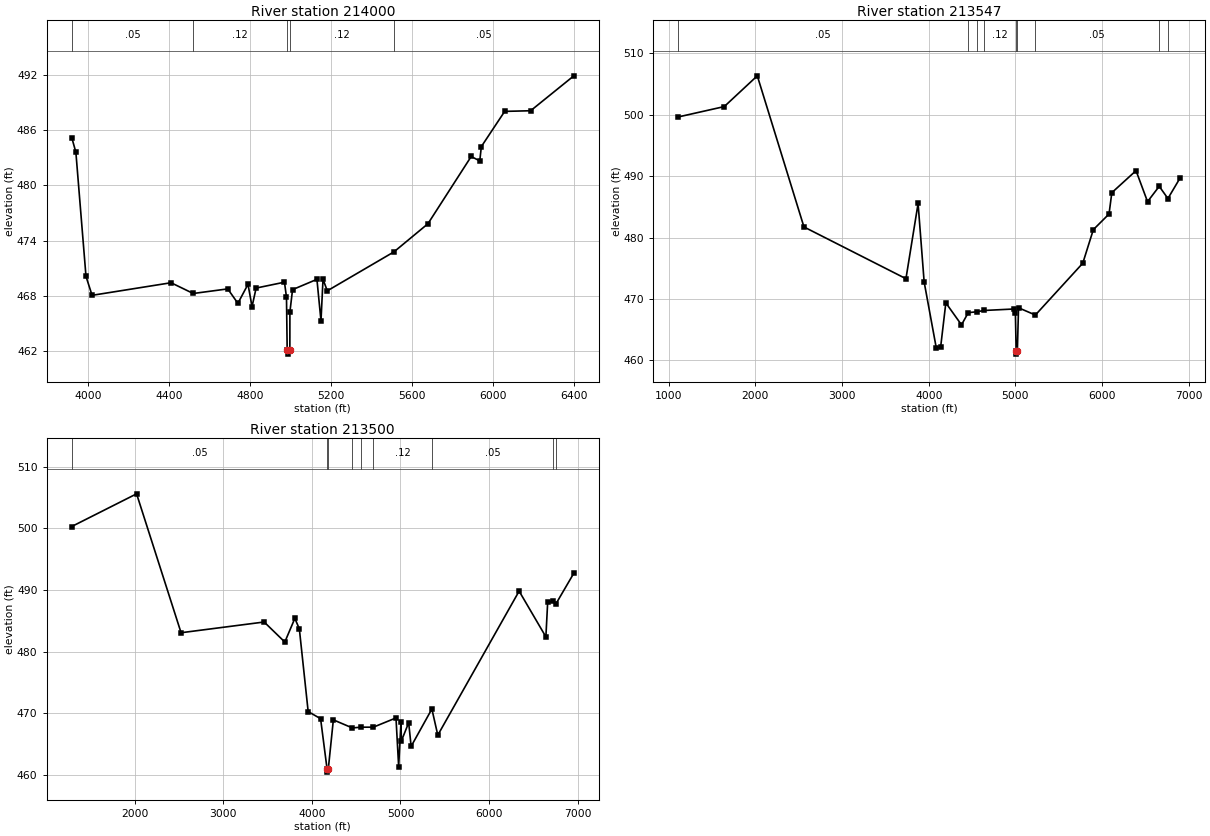
Type RM Length L Ch R = 1 ,214000  ,453,453,453
BEGIN DESCRIPTION:
Kings Creek 423.0
END DESCRIPTION:
XS GIS Cut Line= 3
      2657856.29      6962109.05      2656777.07       6962150.2
      2655380.31      6962038.84
#Sta/Elev= 30
    3920   485.2  3940.3  483.61  3990.3   470.1  4020.4  468.04  4410.6  469.41
  4520.3  468.24  4690.8  468.74  4740.9  467.17  4790.9  469.24  4810.9  466.81
    4831  468.83  4971.1  469.47  4981.1  467.84  4984.5  462.14  4986.4  461.64
  4997.7  462.14    4998  466.23  5011.1  468.66  5131.5  469.78  5151.6  465.26
  5161.6  469.79  5182.7  468.53  5512.2  472.77  5680.1  475.83  5893.9  483.15
  5936.3  482.67  5944.1  484.23  6059.4  488.06  6187.6  488.13  6401.2  491.93
#Mann= 5 ,-1 , 0
    3920     .05       0  4520.3     .12       0  4984.5     .07       0
  4997.7     .12       0  5512.2     .05       0
Bank Sta=4984.5,4997.7
XS Rating Curve= 0 ,0
Exp/Cntr=0.3,0.1

Type RM Length L Ch R = 1 ,213547  ,47,47,47
BEGIN DESCRIPTION:
Mapping XS ba95da48
END DESCRIPTION:
XS GIS Cut Line= 5
      2660655.39        6961872.      2658098.69      6961667.14
      2657657.72       6961660.2      2656759.57      6961733.11
      2654891.54        6961997.
#Sta/Elev= 30
  1109.4  499.64  1640.5  501.33  2021.7  506.34  2560.1  481.72    3737  473.29
    3877  485.54    3947  472.76    4087  462.01  4137.1  462.12  4197.3  469.35
  4377.9  465.77  4456.5  467.76    4556   467.9  4635.7  468.11  4979.9  468.35
  4999.9  467.75  5008.8   461.5  5010.8     461  5022.6   461.5  5036.1  468.55
  5230.6  467.37  5777.5  475.81  5899.3  481.28  6080.5  483.83  6112.6   487.3
  6391.9  490.89  6524.8  485.84  6659.7  488.34    6760  486.35    6903  489.76
#Mann= 9 ,-1 , 0
  1109.4     .05       0  4456.5     .12       0    4556     .05       0
  4635.7     .12       0  5008.8     .07       0  5022.6     .12       0
  5230.6     .05       0  6659.7    .075       0    6760     .05       0
Bank Sta=5008.8,5022.6
XS Rating Curve= 0 ,0
Exp/Cntr=0.3,0.1

Type RM Length L Ch R = 1 ,213500  ,19,19,19
BEGIN DESCRIPTION:
Kings Creek 422.0
END DESCRIPTION:
XS GIS Cut Line= 5
       2660474.9      6961830.34      2658017.54      6961620.94
      2657585.98      6961643.27      2656775.86      6961685.19
      2654832.68      6961918.99
#Sta/Elev= 30
  1290.4  500.31  2021.9  505.61    2524  483.08  3461.8  484.82    3695  481.57
  3808.3  485.41    3859   483.7  3958.5  470.29  4098.7  469.14  4171.9  460.97
  4173.8  460.47  4185.7  460.97  4242.8  468.95  4456.7  467.64    4556  467.76
  4693.9  467.76  4949.8  469.26  4979.8  461.38  5005.9  468.55  5010.9  465.53
    5093  468.49  5120.7  464.65  5354.8  470.71  5421.6  466.47  6339.5  489.83
  6641.6  482.41  6661.8  488.03    6724  488.16  6753.3  487.72  6957.2  492.74
#Mann= 9 ,-1 , 0
  1290.4     .05       0  4171.9     .07       0  4185.7     .05       0
  4456.7     .12       0    4556     .05       0  4693.9     .12       0
  5354.8     .05       0    6724    .075       0  6753.3     .05       0
Bank Sta=4171.9,4185.7
XS Rating Curve= 0 ,0
Exp/Cntr=0.3,0.1