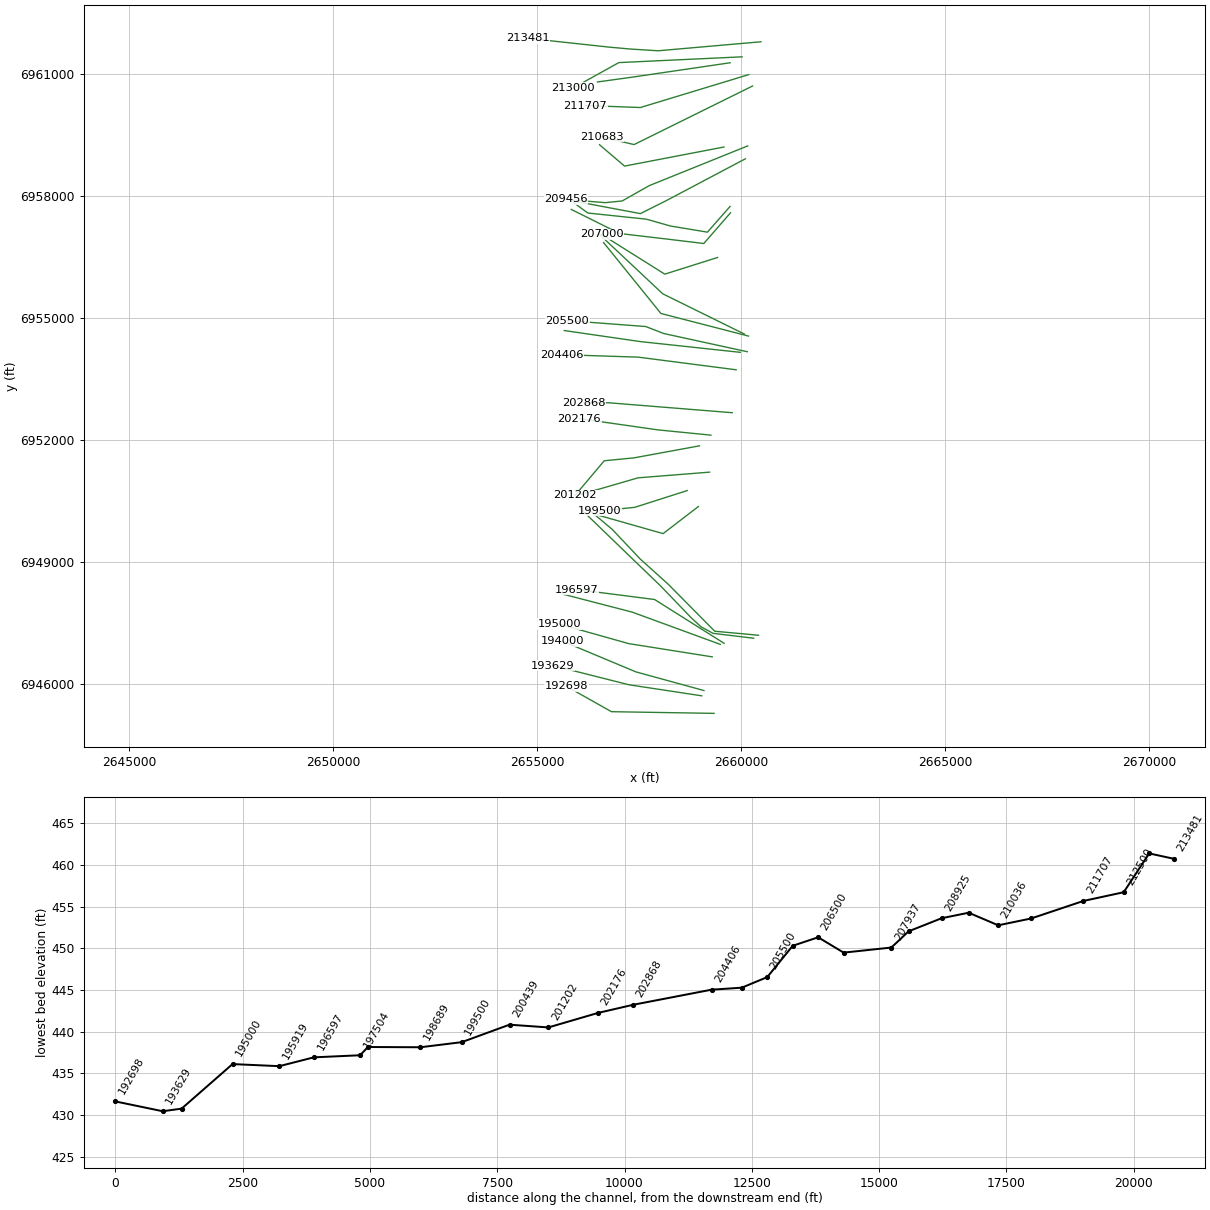
HEC-RAS study Kings Creek.prj: Kings Creek Base Level Engineering

--- Kings Creek.g01 (geometry) --- (continued)

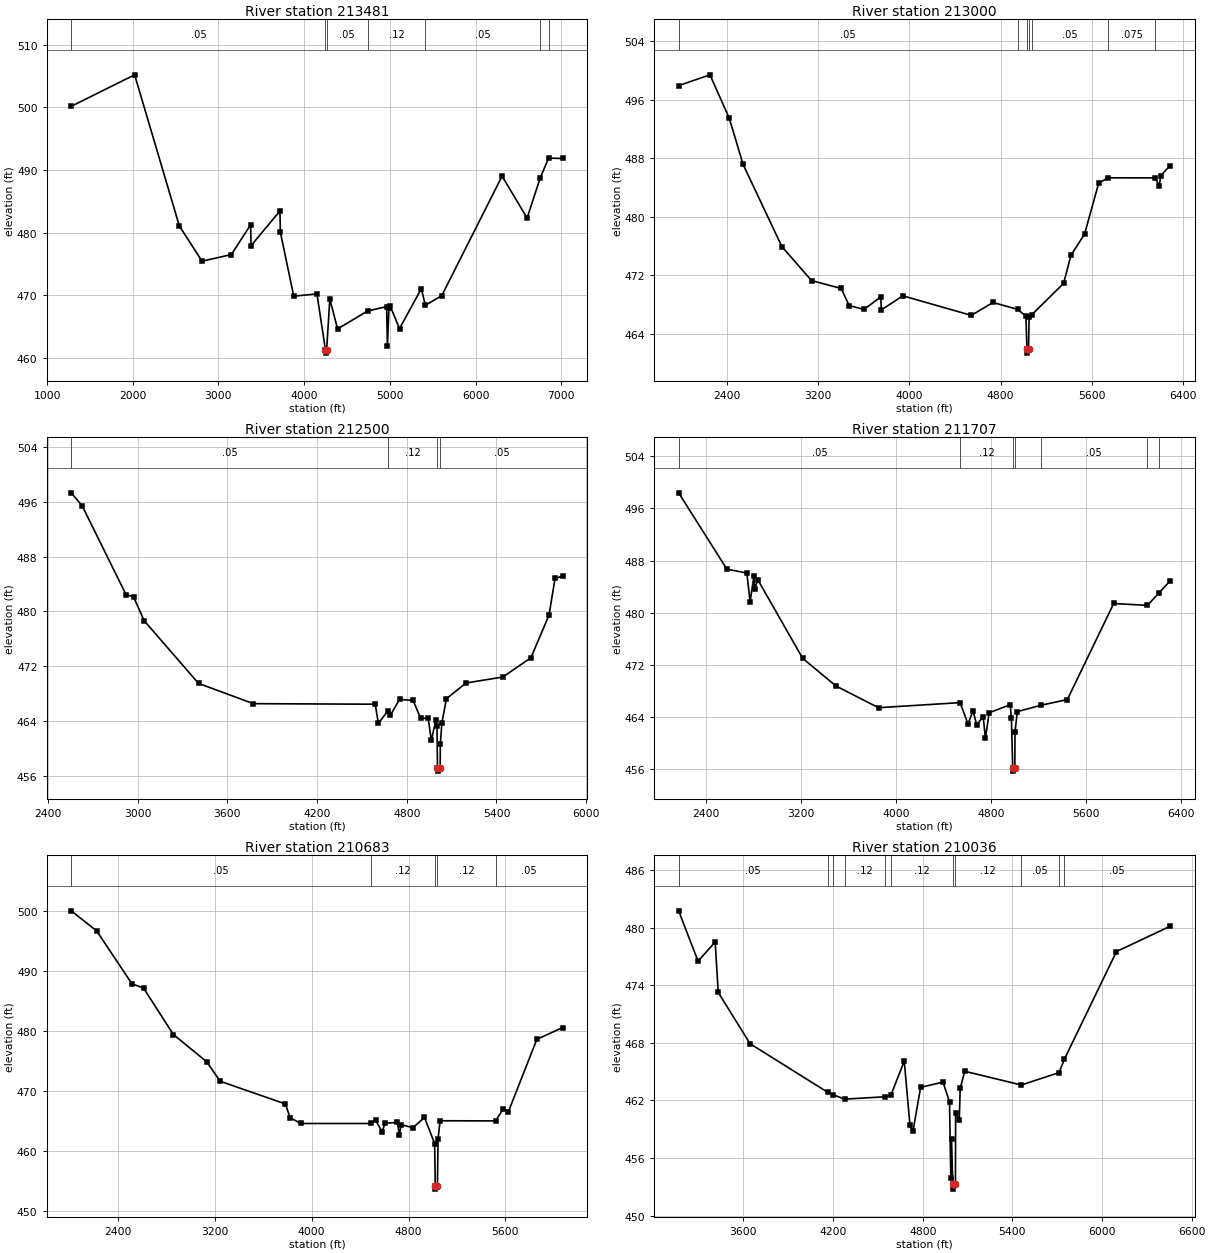
Type RM Length L Ch R = 1 ,213481  ,481,481,481
BEGIN DESCRIPTION:
Mapping XS 099617fd
END DESCRIPTION:
XS GIS Cut Line= 5
      2660482.85      6961799.52      2657963.28      6961578.17
       2657291.4      6961620.27      2656787.93      6961665.41
      2654774.03      6961884.16
#Sta/Elev= 30
  1282.5  500.15  2022.2  505.17  2544.2  481.05  2809.2  475.43  3151.2  476.49
  3375.9  481.25  3380.9  477.91    3718  483.45    3723  480.04  3879.2  469.85
  4149.7  470.21    4249  461.26  4250.9  460.76  4262.8  461.26    4300  469.39
  4390.2  464.62  4741.5  467.49  4962.3  468.18  4972.3  461.85  4988.9   467.9
  5002.5  468.34  5113.1  464.67    5368  471.05  5414.5  468.39    5606  469.93
  6310.1  489.01  6601.8  482.31  6752.7  488.63  6852.5  491.88  7016.2  491.82
#Mann= 7 ,-1 , 0
  1282.5     .05       0    4249     .07       0  4262.8     .05       0
  4741.5     .12       0  5414.5     .05       0  6752.7    .075       0
  6852.5     .05       0
Bank Sta=4249,4262.8
XS Rating Curve= 0 ,0
Exp/Cntr=0.3,0.1

Type RM Length L Ch R = 1 ,213000  ,500,500,500
BEGIN DESCRIPTION:
Kings Creek 421.0
END DESCRIPTION:
XS GIS Cut Line= 3
      2660020.22      6961429.41      2657000.06      6961287.26
      2655876.04      6960661.02
#Sta/Elev= 30
  1976.5   497.9    2251  499.37  2421.2  493.42  2541.3  487.16  2881.7  475.94
    3142   471.3  3402.3  470.22  3472.4  467.89  3602.5  467.36  3749.1  469.07
  3754.1  467.29  3942.9  469.22  4543.6  466.55  4733.8  468.31  4951.8  467.36
  5022.5  466.44  5031.6   461.9  5033.5   461.4  5045.4   461.9  5050.4  466.31
  5074.4  466.64  5352.8  470.91    5418  474.75  5536.9  477.64  5661.5  484.62
  5746.2  485.32  6156.1  485.31  6191.9   484.2  6206.6  485.63  6286.7  486.99
#Mann= 7 ,-1 , 0
  1976.5     .05       0  4951.8     .12       0  5031.6     .07       0
  5045.4     .12       0  5074.4     .05       0  5746.2    .075       0
  6156.1     .05       0
Bank Sta=5031.6,5045.4
XS Rating Curve= 0 ,0
Exp/Cntr=0.3,0.1

Type RM Length L Ch R = 1 ,212500  ,793,793,793
BEGIN DESCRIPTION:
Kings Creek 420.0
END DESCRIPTION:
XS GIS Cut Line= 3
      2659728.49      6961283.57      2657310.39      6960926.61
      2656475.97        6960811.
#Sta/Elev= 30
  2555.7  497.29    2629  495.39  2922.1  482.47  2972.7  482.13  3043.4  478.66
  3407.3  469.52    3774  466.57  4589.1  466.49  4610.2  463.69  4673.8  465.53
  4691.1   464.9  4751.7  467.19  4842.7  467.04  4893.3  464.42  4943.8  464.45
    4964  461.21  4994.3  464.12  5002.2  463.34  5005.5  457.24  5007.5  456.74
  5023.5  457.24  5024.6  460.66  5034.7  463.71    5065  467.29  5196.3  469.58
  5442.6  470.45  5630.4  473.26  5751.5  479.47  5791.9  484.82  5842.4  485.16
#Mann= 4 ,-1 , 0
  2555.7     .05       0  4673.8     .12       0  5005.5     .07       0
  5023.5     .05       0
Bank Sta=5005.5,5023.5
XS Rating Curve= 0 ,0
Exp/Cntr=0.3,0.1

Type RM Length L Ch R = 1 ,211707  ,1024,1024,1024
BEGIN DESCRIPTION:
Kings Creek 418.0
END DESCRIPTION:
XS GIS Cut Line= 3
       2660183.4      6960991.92      2657528.89      6960182.57
      2656172.93      6960231.49
#Sta/Elev= 30
  2171.7  498.39  2576.7  486.69  2744.9  486.08  2772.5  481.69  2805.3  485.66
  2810.6  483.68  2838.1  485.03  3214.4     473  3493.2  468.77  3852.2  465.42
  4538.2   466.2  4604.9  462.93  4646.7  464.95  4678.1  462.79  4732.5  464.06
  4751.2   460.7  4782.6  464.65  4959.8  465.88  4969.8  463.81  4980.8  456.19
  4982.8  455.69  4998.8  456.19  4999.8  461.69  5019.8  464.82  5219.5   465.8
  5440.1  466.67  5830.3  481.41  6113.8  481.12    6213  483.08  6303.7  484.86
#Mann= 7 ,-1 , 0
  2171.7     .05       0  4538.2     .12       0  4980.8     .07       0
  4998.8     .12       0  5219.5     .05       0  6113.8    .075       0
    6213      .1       0
Bank Sta=4980.8,4998.8
XS Rating Curve= 0 ,0
Exp/Cntr=0.3,0.1

Type RM Length L Ch R = 1 ,210683  ,647,647,647
BEGIN DESCRIPTION:
Kings Creek 417.0
END DESCRIPTION:
XS GIS Cut Line= 3
        2660276.        6960711.      2657373.95      6959271.04
      2656579.22      6959460.24
#Sta/Elev= 30
  2015.6  499.98  2225.7  496.63  2517.1  487.81  2612.3  487.11  2858.9  479.36
  3133.4  474.83  3245.5  471.57  3783.4  467.79  3822.6  465.48  3912.2  464.53
    4487  464.53  4528.5  465.03  4583.2  463.15  4605.5  464.58  4707.8   464.7
  4724.7  462.69  4739.5  464.33  4836.7  463.83    4932  465.53    5016  461.18
  5020.7  454.09  5022.7  453.59  5038.7  454.09    5044     462  5060.9  464.99
  5518.5  464.96  5583.1  466.99  5625.2  466.52  5859.6  478.56  6072.2  480.52
#Mann= 5 ,-1 , 0
  2015.6     .05       0    4487     .12       0  5020.7     .07       0
  5038.7     .12       0  5518.5     .05       0
Bank Sta=5020.7,5038.7
XS Rating Curve= 0 ,0
Exp/Cntr=0.3,0.1

Type RM Length L Ch R = 1 ,210036  ,580,580,580
BEGIN DESCRIPTION:
Kings Creek 416.0
END DESCRIPTION:
XS GIS Cut Line= 3
        2659576.        6959211.      2657139.96      6958741.91
      2656526.49        6959267.
#Sta/Elev= 30
  3166.9  481.74  3296.7   476.5  3411.3   478.5  3431.7  473.24  3645.5   467.9
  4165.4  462.84  4200.5   462.6  4276.8  462.14    4547  462.38  4587.3  462.55
  4676.6   466.1  4714.8   459.4  4735.2  458.83  4786.1  463.36  4936.2  463.91
  4979.6  461.83  4988.1  453.92  4993.1  457.95  5001.2  453.27  5003.2  452.77
  5019.2  453.27  5020.3  460.67    5045  460.01  5050.9  463.25  5081.4  465.04
  5459.9  463.61  5712.7   464.9  5748.7  466.31  6096.9   477.5  6455.2  480.13
#Mann= 11 ,-1 , 0
  3166.9     .05       0  4165.4     .12       0  4200.5     .05       0
  4276.8     .12       0    4547     .05       0  4587.3     .12       0
  5001.2     .07       0  5019.2     .12       0  5459.9     .05       0
  5712.7     .12       0  5748.7     .05       0
Bank Sta=5001.2,5019.2
XS Rating Curve= 0 ,0
Exp/Cntr=0.3,0.1

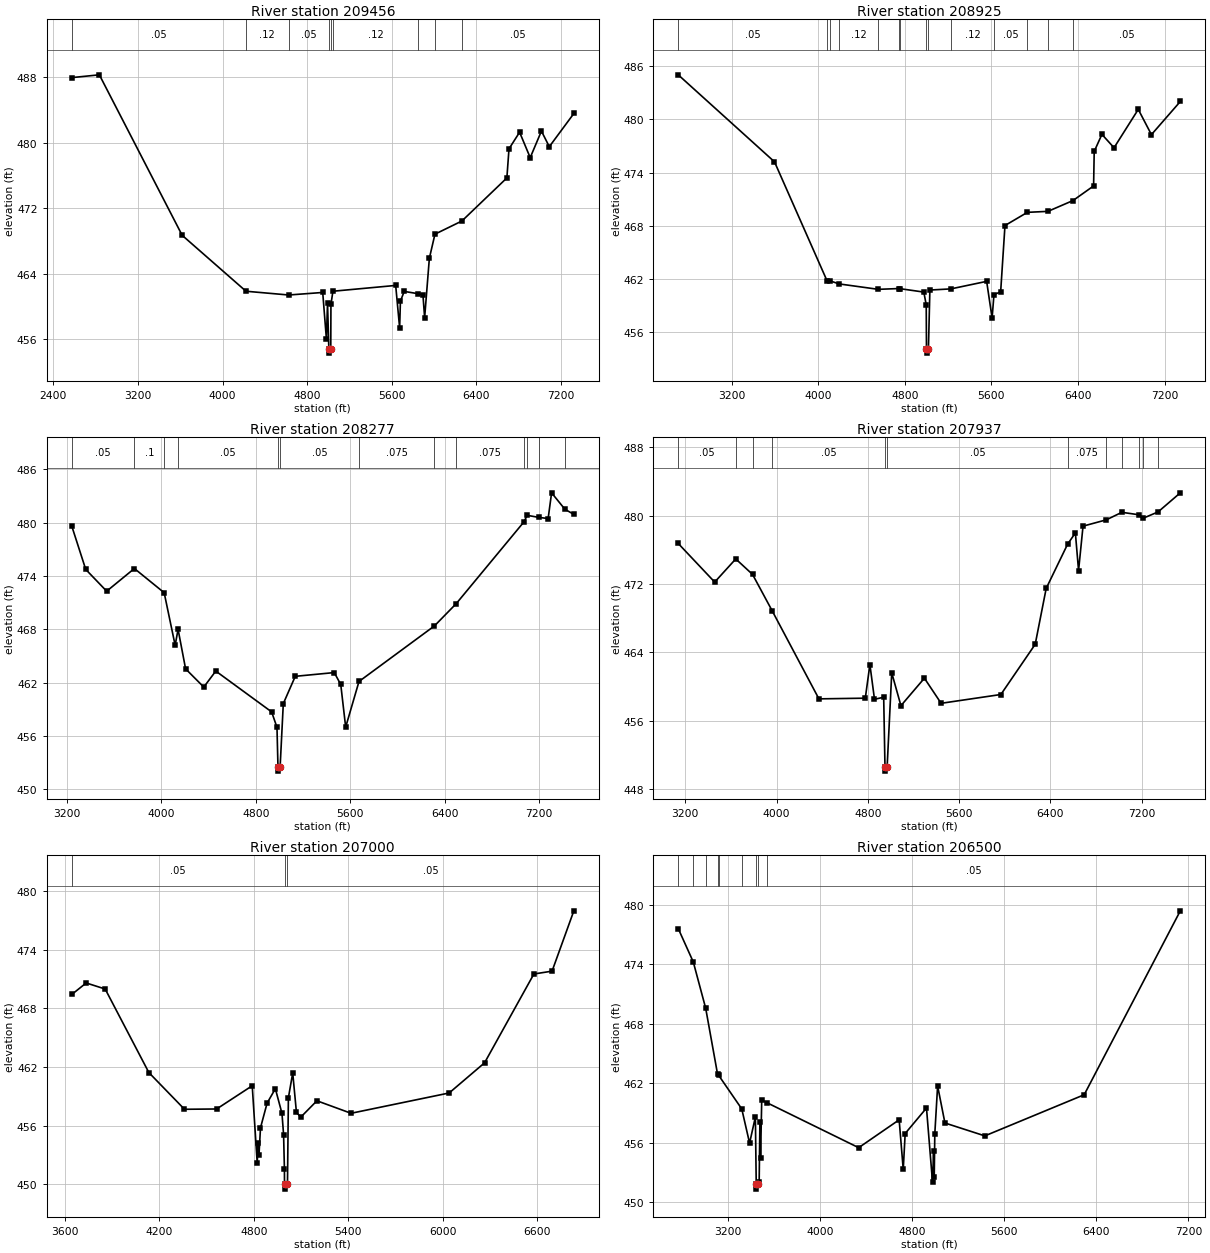
Type RM Length L Ch R = 1 ,209456  ,531,531,531
BEGIN DESCRIPTION:
Kings Creek 415.0
END DESCRIPTION:
XS GIS Cut Line= 5
      2660157.78      6959238.44      2657741.09      6958259.27
       2657082.7      6957884.49      2656668.18       6957842.6
      2655704.68      6957920.72
#Sta/Elev= 30
  2573.7  487.98  2834.6  488.32  3617.8  468.69  4221.5  461.85  4625.5  461.39
  4947.1   461.7    4982  455.99  4992.5  460.41  5005.1  454.78  5007.1  454.28
  5023.1  454.78  5024.8  460.23  5043.5  461.85  5637.1  462.56  5674.5  457.37
  5681.9  460.63  5717.8  461.83  5848.5  461.55    5895  461.41  5910.9  458.61
  5955.6  465.88  6008.5  468.83  6263.3  470.44  6688.7  475.71  6708.8  479.27
  6809.1   481.3  6909.4  478.19  7015.5  481.44    7090  479.53  7322.1  483.59
#Mann= 9 ,-1 , 0
  2573.7     .05       0  4221.5     .12       0  4625.5     .05       0
  5005.1     .03       0  5023.1     .05       0  5043.5     .12       0
  5848.5     .05       0  6008.5      .1       0  6263.3     .05       0
Bank Sta=5005.1,5023.1
XS Rating Curve= 0 ,0
Exp/Cntr=0.3,0.1

Type RM Length L Ch R = 1 ,208925  ,648,648,648
BEGIN DESCRIPTION:
Kings Creek 414.0
END DESCRIPTION:
XS GIS Cut Line= 4
       2660100.5      6958920.74      2658157.76      6957889.48
      2657528.13      6957573.03      2655824.39      6957894.69
#Sta/Elev= 30
  2707.6  485.03  3596.8  475.21  4083.4  461.75  4109.1  461.78  4194.1  461.43
  4555.7  460.82  4749.7  460.91  4758.7  460.89  4976.1  460.51  4998.4  459.08
  5000.8  454.12  5002.8  453.62  5018.8  454.12  5032.2  460.74  5226.3  460.87
  5556.6  461.72  5606.9  457.59  5624.3  460.22    5686  460.54  5725.9  468.02
  5932.9  469.51  6122.7  469.62  6354.3  470.84  6544.6  472.49  6550.2  476.38
  6621.4  478.31  6733.4   476.8  6957.2  481.13  7078.7  478.28  7345.6  482.02
#Mann= 14 ,-1 , 0
  2707.6     .05       0  4083.4     .12       0  4109.1     .05       0
  4194.1     .12       0  4555.7     .05       0  4749.7     .12       0
  4758.7     .05       0  5000.8     .03       0  5018.8     .05       0
  5226.3     .12       0  5624.3     .05       0  5932.9    .075       0
  6122.7      .1       0  6354.3     .05       0
Bank Sta=5000.8,5018.8
XS Rating Curve= 0 ,0
Exp/Cntr=0.3,0.1

Type RM Length L Ch R = 1 ,208277  ,340,340,340
BEGIN DESCRIPTION:
Mapping XS fb12b593
END DESCRIPTION:
XS GIS Cut Line= 6
      2659725.47      6957748.86      2659171.24      6957117.13
      2658266.54       6957267.6      2657676.27      6957436.12
      2656241.09      6957587.39      2655888.12      6957846.93
#Sta/Elev= 30
  3241.8   479.6    3360  474.73  3537.5  472.28  3772.2  474.83  4024.6  472.11
  4117.5   466.2  4142.4  467.99    4206  463.55  4360.2   461.5  4461.8   463.3
  4934.9  458.71  4980.2  456.97  4988.6  452.55  4990.6  452.05  5006.9  452.55
  5033.8  459.64  5135.2  462.71  5465.5  463.13  5520.5  461.79  5562.1     457
    5675  462.13  6314.4  468.38  6499.3  470.89  7073.3  480.09  7099.6  480.81
  7198.4  480.58  7277.3  480.45  7306.6  483.34  7419.5  481.49  7495.1  480.92
#Mann= 13 ,-1 , 0
  3241.8     .05       0  3772.2      .1       0  4024.6    .075       0
  4142.4     .05       0  4988.6     .05       0  5006.9     .05       0
    5675    .075       0  6314.4      .1       0  6499.3    .075       0
  7073.3      .1       0  7099.6     .05       0  7198.4      .1       0
  7419.5     .05       0
Bank Sta=4988.6,5006.9
XS Rating Curve= 0 ,0
Exp/Cntr=0.3,0.1

Type RM Length L Ch R = 1 ,207937  ,937,937,937
BEGIN DESCRIPTION:
Mapping XS 56a10e22
END DESCRIPTION:
XS GIS Cut Line= 5
      2659735.87      6957592.58       2659082.7      6956837.62
       2658207.7      6956943.52      2657016.73      6957084.15
      2655834.84      6957675.94
#Sta/Elev= 30
  3138.1  476.75  3457.7  472.23  3642.2  474.94  3789.4  473.13  3961.4  468.87
  4371.2  458.56  4777.7  458.64    4818  462.58  4858.3  458.51  4938.9  458.75
  4950.2   450.6  4952.2   450.1  4969.1   450.6  5009.4  461.61    5090  457.76
  5295.6  460.98  5442.4  458.04    5966  459.07    6267  464.95  6363.2  471.49
  6550.6  476.66    6619  477.99    6647  473.58  6686.1  478.78  6890.3  479.52
  7026.6   480.4  7176.3  480.11    7208  479.68  7343.5  480.44  7538.8  482.68
#Mann= 12 ,-1 , 0
  3138.1     .05       0  3642.2      .1       0  3789.4    .075       0
  3961.4     .05       0  4950.2     .03       0  4969.1     .05       0
  6550.6    .075       0  6890.3      .1       0  7026.6    .075       0
  7176.3      .1       0    7208    .075       0  7343.5      .1       0
Bank Sta=4950.2,4969.1
XS Rating Curve= 0 ,0
Exp/Cntr=0.3,0.1

Type RM Length L Ch R = 1 ,207000  ,500,500,500
BEGIN DESCRIPTION:
Kings Creek 409.0
END DESCRIPTION:
XS GIS Cut Line= 3
      2659418.21      6956493.65        2658126.       6956084.3
      2656575.97      6957061.02
#Sta/Elev= 30
  3644.5  469.43    3736  470.61  3856.6  469.99    4134  461.43  4360.1  457.67
  4564.3   457.7  4790.2  460.08  4821.7  452.19  4827.9  454.17  4833.1     453
  4842.7  455.77  4884.6   458.3  4937.1  459.78    4979  457.25  4989.3  455.07
  4994.6  451.52  4995.1  449.99  4997.1  449.49    5014  449.99  5019.8  458.85
  5047.3  461.39  5070.9  457.35  5098.7  456.87  5200.9  458.54  5417.7  457.26
  6040.5  459.34  6265.3  462.43  6578.4  471.53  6693.8  471.82  6832.1     478
#Mann= 3 ,-1 , 0
  3644.5     .05       0  4995.1     .04       0    5014     .05       0
Bank Sta=4995.1,5014
XS Rating Curve= 0 ,0
Exp/Cntr=0.3,0.1

Type RM Length L Ch R = 1 ,206500  ,500,500,500
BEGIN DESCRIPTION:
Kings Creek 408.0
END DESCRIPTION:
XS GIS Cut Line= 3
      2660075.98      6954611.01      2658075.93      6955600.44
      2656525.98      6957061.02
#Sta/Elev= 30
  2768.6  477.61  2899.4  474.24  3007.1  469.57  3109.9  462.94  3118.9  462.82
  3320.4  459.42  3388.3  455.97  3438.7  458.61  3446.1  451.83  3448.1  451.33
    3465  451.83  3471.5  452.01    3478  458.07  3483.6  454.44  3493.8   460.3
  3536.6  460.06    4336  455.51  4687.5  458.32    4723  453.31  4739.8  456.94
  4924.9  459.51  4977.6  452.01  4986.6   455.2  4992.2  452.56  4997.2  456.91
  5021.6  461.74  5085.1     458  5431.8   456.7  6294.8  460.85  7129.7   479.4
#Mann= 9 ,-1 , 0
  2768.6     .05       0  2899.4     .12       0  3007.1     .05       0
  3109.9     .12       0  3118.9     .05       0  3320.4     .12       0
  3446.1     .04       0    3465     .12       0  3536.6     .05       0
Bank Sta=3446.1,3465
XS Rating Curve= 0 ,0
Exp/Cntr=0.3,0.1

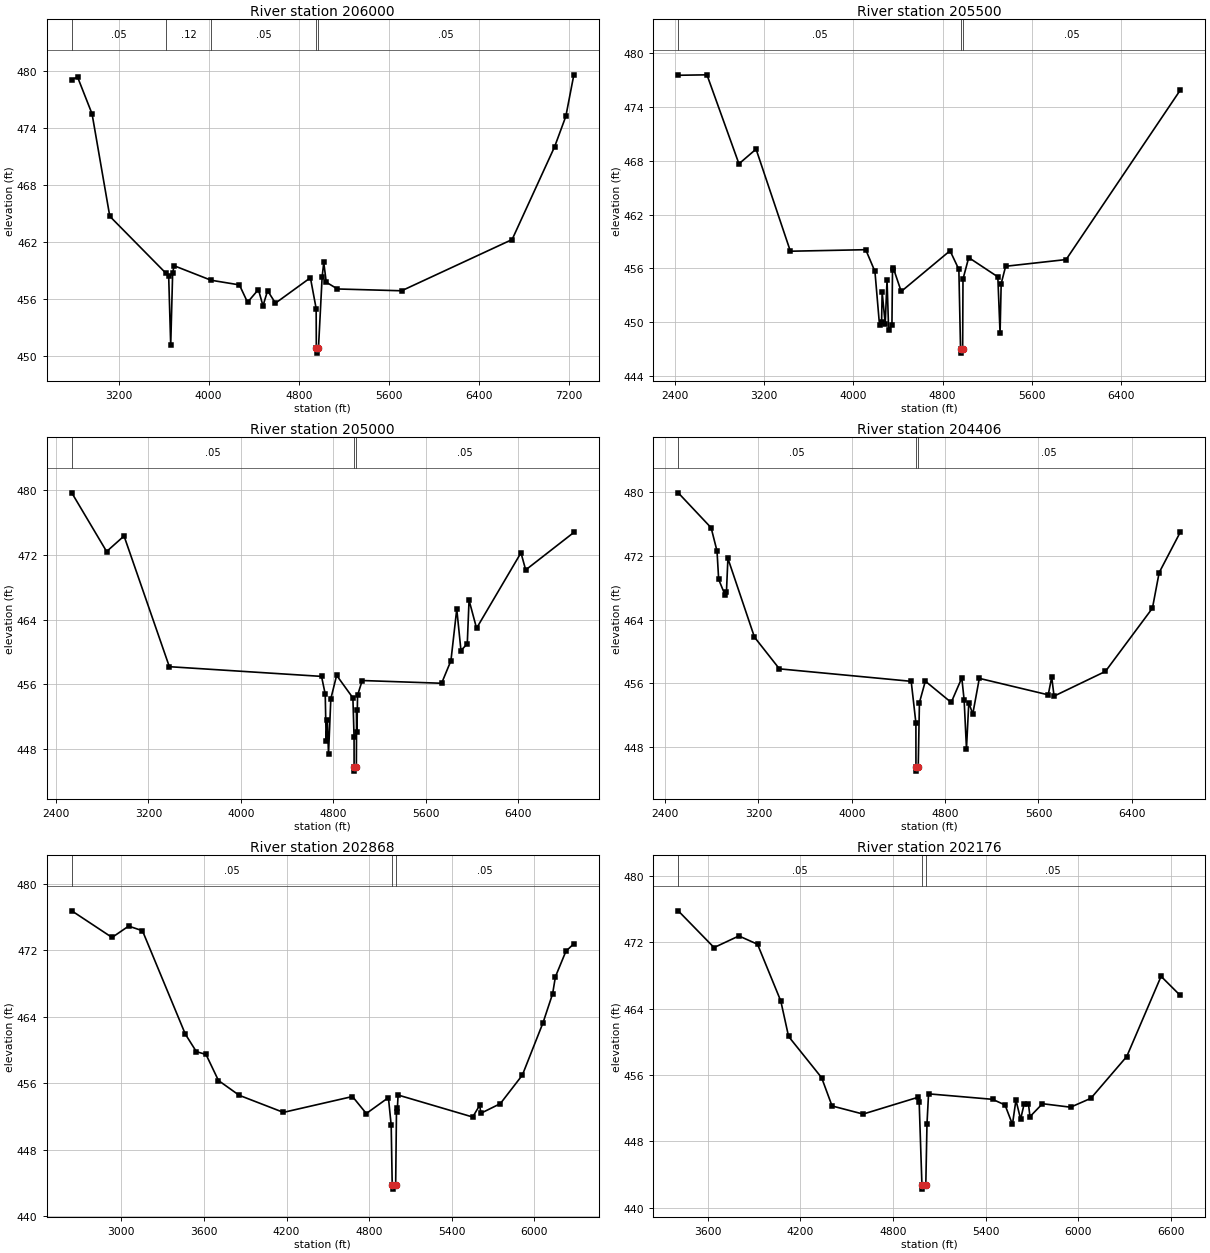
Type RM Length L Ch R = 1 ,206000  ,500,500,500
BEGIN DESCRIPTION:
Kings Creek 407.0
END DESCRIPTION:
XS GIS Cut Line= 3
      2660175.97      6954561.01      2658031.96      6955116.47
      2656625.97      6956861.03
#Sta/Elev= 30
  2785.2  479.09  2836.8  479.35  2965.3  475.48  3122.5  464.71  3622.1   458.7
  3645.1  458.44  3663.2  451.12  3680.5  458.79  3694.2   459.5    4021  457.98
  4272.7  457.49    4345  455.66  4441.5     457  4482.1  455.28  4522.7  456.88
  4592.9  455.57  4902.9  458.24  4953.8     455  4955.4  450.81  4957.4  450.31
  4974.3  450.81  5006.9  458.31  5021.3  459.85  5043.6  457.77  5142.8  457.06
  5712.2  456.87  6692.7  462.26  7070.2  472.03  7169.4  475.22  7240.6  479.59
#Mann= 5 ,-1 , 0
  2785.2     .05       0  3622.1     .12       0    4021     .05       0
  4955.4     .04       0  4974.3     .05       0
Bank Sta=4955.4,4974.3
XS Rating Curve= 0 ,0
Exp/Cntr=0.3,0.1

Type RM Length L Ch R = 1 ,205500  ,500,500,500
BEGIN DESCRIPTION:
Kings Creek 406.0
END DESCRIPTION:
XS GIS Cut Line= 4
      2660147.37      6954175.93      2658100.47      6954623.85
      2657659.96      6954795.48       2655735.9      6954941.56
#Sta/Elev= 30
  2431.9  477.55  2689.2   477.6  2975.8  467.67  3129.1  469.31  3436.5  457.92
  4111.6  458.09    4194  455.66  4234.9  449.69  4253.5     450  4258.6  453.34
  4286.1  449.84  4302.4   454.7  4316.8  449.12  4346.3  449.72  4351.4  455.88
  4357.8  456.07  4429.4  453.43  4866.9  457.97  4945.8  455.89  4960.8  447.05
  4962.8  446.55  4979.7  447.05  4982.8  454.81  5034.1  457.21  5294.8  455.06
  5314.9  448.76  5324.9  454.31    5365  456.24  5906.6  456.99  6929.6   475.9
#Mann= 3 ,-1 , 0
  2431.9     .05       0  4960.8     .04       0  4979.7     .05       0
Bank Sta=4960.8,4979.7
XS Rating Curve= 0 ,0
Exp/Cntr=0.3,0.1

Type RM Length L Ch R = 1 ,205000  ,594,594,594
BEGIN DESCRIPTION:
Kings Creek 405.0
END DESCRIPTION:
XS GIS Cut Line= 3
      2659975.95      6954161.01      2657526.56      6954425.25
      2655662.94      6954696.77
#Sta/Elev= 30
  2536.4  479.71  2838.1  472.45    2989  474.37  3381.2   458.2  4698.8     457
  4730.7  454.81  4739.1  449.03  4749.1  451.59  4759.2   447.4  4779.3  454.24
  4829.6  457.13  4970.4  454.34  4980.5  449.47  4980.8  445.78  4982.8  445.28
  5000.3  445.78  5002.6  452.87  5005.4  450.07  5010.7  454.66  5051.1  456.49
  5738.3  456.15  5819.1  458.94  5869.6  465.33    5906   460.2  5960.6  461.03
    5976  466.43    6041  462.96  6425.5  472.29  6466.4  470.17  6883.3  474.81
#Mann= 3 ,-1 , 0
  2536.4     .05       0  4980.8     .04       0  5000.3     .05       0
Bank Sta=4980.8,5000.3
XS Rating Curve= 0 ,0
Exp/Cntr=0.3,0.1

Type RM Length L Ch R = 1 ,204406  ,1538,1538,1538
BEGIN DESCRIPTION:
Kings Creek 404.0
END DESCRIPTION:
XS GIS Cut Line= 3
       2659875.5      6953731.62      2657474.97       6954042.7
      2655594.76      6954103.84
#Sta/Elev= 30
  2513.3  479.84  2795.1  475.47  2845.6  472.56  2859.7  469.01  2916.1  467.01
  2926.2  467.38  2938.9  471.64  3166.5  461.79    3380  457.83  4509.3  456.27
  4549.7  451.05    4550  445.54    4552  445.04  4569.5  445.54  4579.9  453.61
  4630.4  456.29  4852.2  453.63  4942.9   456.7  4962.9  453.93  4982.9  447.85
  5002.9  453.61  5036.7  452.17    5093  456.64  5683.3  454.58  5713.3  456.79
  5733.3  454.42  6173.5  457.51  6576.3  465.42  6633.8  469.86  6815.1  474.93
#Mann= 3 ,-1 , 0
  2513.3     .05       0    4550     .04       0  4569.5     .05       0
Bank Sta=4550,4569.5
XS Rating Curve= 0 ,0
Exp/Cntr=0.3,0.1

Type RM Length L Ch R = 1 ,202868  ,692,692,692
BEGIN DESCRIPTION:
Kings Creek 401.0
END DESCRIPTION:
XS GIS Cut Line= 3
      2659777.53      6952675.94       2656746.3      6952920.73
      2656142.12      6952915.52
#Sta/Elev= 30
  2640.8  476.77  2933.3  473.56  3053.7  474.93    3154  474.37    3465  461.92
  3545.3   459.8  3615.5  459.46  3705.8  456.32  3856.3  454.54  4177.3  452.48
  4678.9  454.39  4779.3  452.34  4939.8  454.26  4959.9  450.94  4967.4  443.73
  4969.9  443.23  4992.4  443.73  4998.5  452.96  5003.5  452.55    5010  454.57
  5551.8  451.92  5601.9  453.32    5612  452.38  5752.2  453.53  5912.2  456.97
  6062.2  463.28  6132.2  466.79  6152.2  468.82  6228.6   471.9  6286.1   472.8
#Mann= 3 ,-1 , 0
  2640.8     .05       0  4967.4     .03       0  4992.4     .05       0
Bank Sta=4967.4,4992.4
XS Rating Curve= 0 ,0
Exp/Cntr=0.3,0.1

Type RM Length L Ch R = 1 ,202176  ,974,974,974
BEGIN DESCRIPTION:
Kings Creek 399.0
END DESCRIPTION:
XS GIS Cut Line= 3
      2659256.72      6952123.85      2657954.63      6952254.06
      2656032.73       6952530.1
#Sta/Elev= 30
  3409.9  475.81  3641.8  471.38  3802.6  472.78  3923.2  471.78  4073.9  464.93
  4124.2  460.66  4338.1  455.69  4405.6  452.28  4606.6   451.3  4959.6  453.31
  4969.7   452.7  4987.5  442.75    4990  442.25  5012.5  442.75  5020.2  450.13
  5030.3  453.74  5444.5  453.08  5525.3   452.4  5573.5  450.06    5596  452.99
  5626.3  450.68  5649.1  452.53  5676.8  452.56  5686.9  450.99  5767.8  452.55
  5949.6  452.13    6081   453.2  6313.3  458.24  6535.6  467.91  6660.1   465.6
#Mann= 3 ,-1 , 0
  3409.9     .05       0  4987.5     .03       0  5012.5     .05       0
Bank Sta=4987.5,5012.5
XS Rating Curve= 0 ,0
Exp/Cntr=0.3,0.1

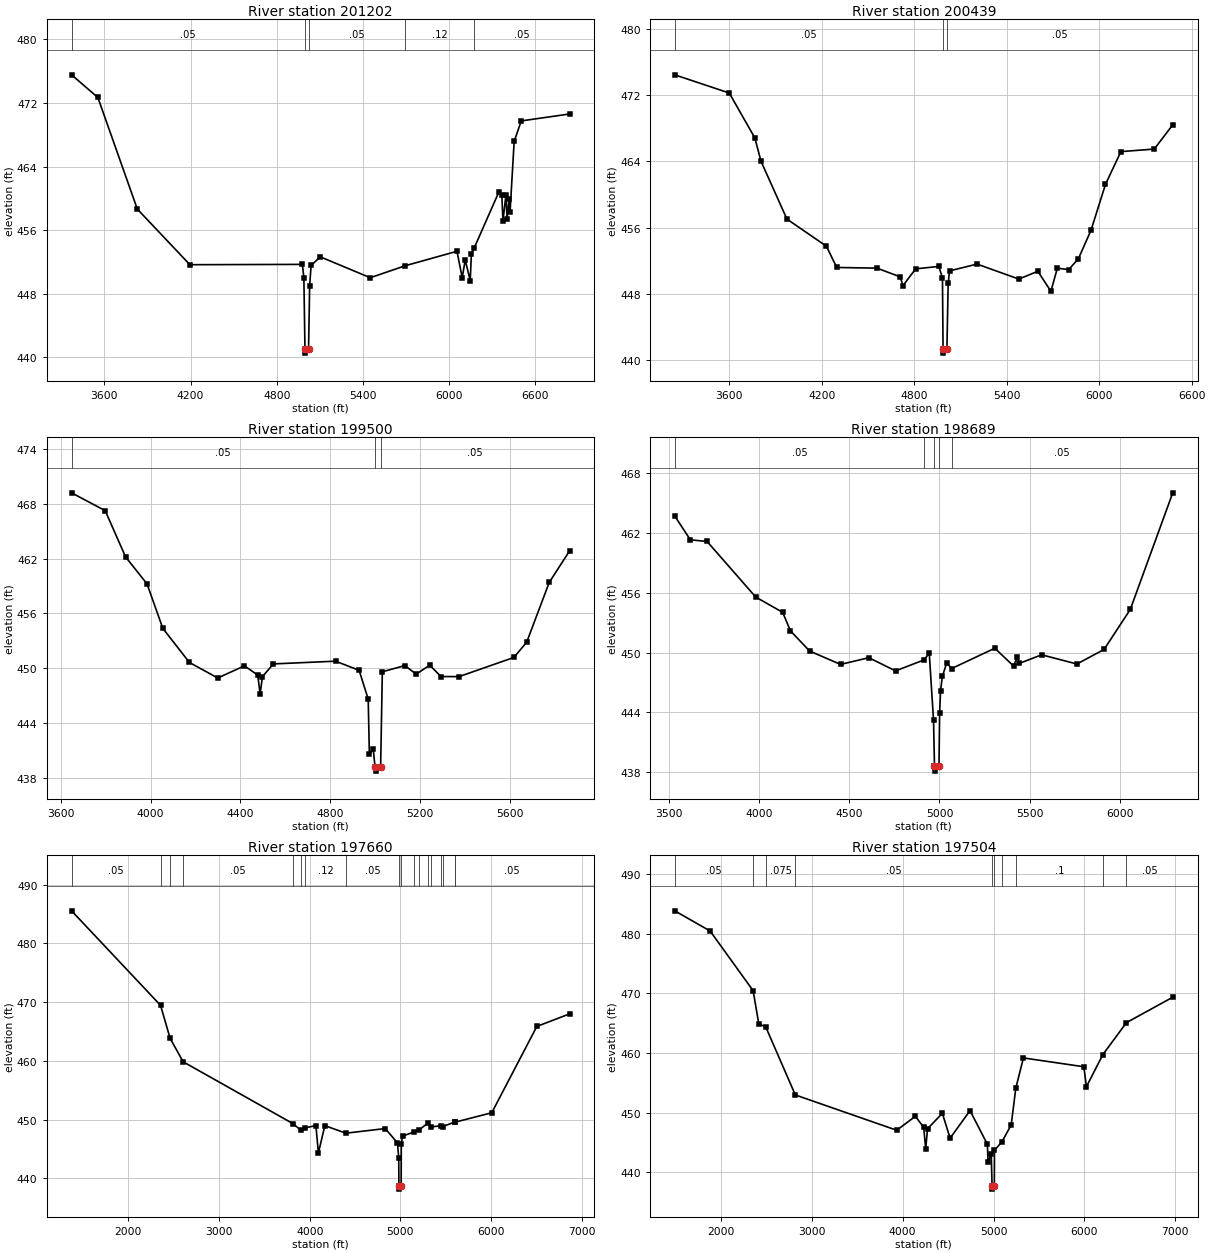
Type RM Length L Ch R = 1 ,201202  ,763,763,763
BEGIN DESCRIPTION:
Kings Creek 397.0
END DESCRIPTION:
XS GIS Cut Line= 4
      2658976.01        6951861.      2657375.16        6951566.
      2656642.13      6951493.64      2655933.83      6950649.93
#Sta/Elev= 30
  3372.2  475.54  3555.2  472.69  3829.8  458.64  4195.8  451.64  4978.8  451.68
    4989     450  4996.7  441.01  4999.2  440.51  5021.7  441.01  5029.3  448.99
  5039.4  451.54  5103.2  452.63  5451.3     450  5694.5  451.51  6054.7  453.33
  6091.1  450.01  6111.9  452.23    6147  449.64  6154.8  452.93  6175.8   453.8
    6346  460.78  6366.9  460.36  6374.7  457.11  6395.5  460.45  6403.3  457.41
  6417.6  459.96  6424.1  458.25  6452.7  467.16  6502.1  469.74  6838.2  470.61
#Mann= 5 ,-1 , 0
  3372.2     .05       0  4996.7     .03       0  5021.7     .05       0
  5694.5     .12       0  6175.8     .05       0
Bank Sta=4996.7,5021.7
XS Rating Curve= 0 ,0
Exp/Cntr=0.3,0.1

Type RM Length L Ch R = 1 ,200439  ,939,939,939
BEGIN DESCRIPTION:
Kings Creek 396.0
END DESCRIPTION:
XS GIS Cut Line= 3
      2659223.76      6951214.13      2657470.99      6951074.19
      2656057.08      6950662.05
#Sta/Elev= 30
  3246.3  474.47    3600  472.27  3765.7  466.85  3805.8  464.03    3974  457.04
  4230.1  453.76  4297.4  451.19  4558.2  451.11  4708.7  450.06  4727.2     449
    4809  451.02  4959.5  451.32  4983.2  449.92  4987.1  441.34  4989.6  440.84
  5012.1  441.34  5020.3  449.33  5029.7  450.78  5207.6   451.6  5478.6  449.79
    5602  450.73  5686.9  448.31  5728.6  451.11  5801.5  450.93    5864   452.2
  5947.3   455.7    6041  461.24  6140.8  465.19  6357.4   465.5  6477.4  468.43
#Mann= 3 ,-1 , 0
  3246.3     .05       0  4987.1     .03       0  5012.1     .05       0
Bank Sta=4987.1,5012.1
XS Rating Curve= 0 ,0
Exp/Cntr=0.3,0.1

Type RM Length L Ch R = 1 ,199500  ,811,811,811
BEGIN DESCRIPTION:
Kings Creek 394.0
END DESCRIPTION:
XS GIS Cut Line= 3
      2658676.01        6950761.      2657388.58      6950347.86
      2656526.04        6950261.
#Sta/Elev= 30
  3647.9  469.19  3797.7  467.24  3888.8  462.17    3984  459.23  4054.6  454.36
    4173  450.63  4299.1  448.93  4418.4  450.26  4477.4  449.25  4488.1  447.22
  4498.6  449.08  4546.9  450.47  4824.2  450.77  4929.2  449.77  4969.7  446.62
  4974.9   440.6  4992.2  441.12  5000.1  439.24  5002.6  438.74  5025.1  439.24
  5032.7  449.61  5133.2  450.29  5183.5  449.35  5243.8  450.33  5294.1  449.09
  5374.5  449.08  5619.1  451.18    5676  452.85  5776.5   459.4  5866.9  462.83
#Mann= 3 ,-1 , 0
  3647.9     .05       0  5000.1     .03       0  5025.1     .05       0
Bank Sta=5000.1,5025.1
XS Rating Curve= 0 ,0
Exp/Cntr=0.3,0.1

Type RM Length L Ch R = 1 ,198689  ,1029,1029,1029
BEGIN DESCRIPTION:
Kings Creek 393.0
END DESCRIPTION:
XS GIS Cut Line= 3
      2658949.41      6950368.63      2658084.84      6949701.98
      2656475.99        6950161.
#Sta/Elev= 30
  3530.3  463.66  3616.6  461.28  3709.9  461.11  3979.8  455.55  4129.3  454.02
  4172.8  452.16  4279.6  450.14  4450.9  448.81    4608  449.48    4756  448.16
  4915.6  449.27  4943.2  449.95    4967   443.2  4972.3  438.63  4974.8  438.13
  4997.3  438.63  5000.8   443.9    5006  446.16    5016  447.61  5039.8  448.94
  5068.2   448.4  5307.2  450.43  5411.2  448.65    5432  449.56  5443.1  448.91
  5567.2  449.77  5763.1  448.85    5914  450.31  6059.6  454.32  6295.1  465.98
#Mann= 5 ,-1 , 0
  3530.3     .05       0  4915.6     .12       0  4972.3     .07       0
  4997.3     .12       0  5068.2     .05       0
Bank Sta=4972.3,4997.3
XS Rating Curve= 0 ,0
Exp/Cntr=0.3,0.1

Type RM Length L Ch R = 1 ,197660  ,156,156,156
BEGIN DESCRIPTION:
Kings Creek 391.0
END DESCRIPTION:
XS GIS Cut Line= 6
      2660423.34      6947201.98      2659350.47      6947300.93
      2658206.12      6948460.93      2657524.99      6949076.42
      2656838.34      6949805.79       2656179.8      6950362.41
#Sta/Elev= 30
  1375.1  485.53  2355.6  469.45  2461.9   463.8  2605.4  459.83    3814  449.32
  3901.8   448.2  3948.3  448.57    4068  448.99  4095.9  444.32  4166.9  448.97
  4397.9  447.68  4832.7  448.47  4967.2  446.03  4981.4  443.48  4983.1  438.66
  4985.6  438.16  5008.1  438.66  5009.5  445.79  5023.7  447.18  5151.9  447.91
  5203.5  448.22  5300.2  449.37  5334.9  448.75  5448.4  448.94  5466.4  448.81
  5596.7  449.57  5597.8  449.54  6006.7  451.16  6503.3  465.85    6864  467.99
#Mann= 18 ,-1 , 0
  1375.1     .05       0  2355.6      .1       0  2461.9    .075       0
  2605.4     .05       0    3814     .12       0  3901.8     .05       0
  3948.3     .12       0  4397.9     .05       0  4983.1     .03       0
  5008.1     .05       0  5151.9    .075       0  5203.5     .05       0
  5300.2    .075       0  5334.9     .05       0  5448.4    .075       0
  5466.4     .05       0  5596.7    .075       0  5597.8     .05       0
Bank Sta=4983.1,5008.1
XS Rating Curve= 0 ,0
Exp/Cntr=0.3,0.1

Type RM Length L Ch R = 1 ,197504  ,907,907,907
BEGIN DESCRIPTION:
Kings Creek 389.0
END DESCRIPTION:
XS GIS Cut Line= 6
      2660303.56      6947129.06       2659308.8      6947248.85
      2659014.99      6947409.96      2658776.28      6947629.14
      2658026.59       6948411.6      2656064.03      6950311.33
#Sta/Elev= 30
  1494.6  483.86  1883.6  480.47    2356  470.47  2418.8  464.88  2494.5  464.41
  2820.3  452.97  3935.1  447.05  4140.4  449.38  4232.3  447.54  4253.7  443.92
  4274.7  447.31  4437.3  449.89  4522.2  445.71  4741.5  450.34  4932.4   444.7
  4939.7  441.65  4974.9  443.07  4983.8  437.67  4986.3  437.17  5008.8  437.67
  5010.4  443.69  5091.2  445.09  5194.3  447.94    5245  454.12  5328.6  459.18
  5993.2   457.7  6021.5  454.35  6202.2  459.74  6461.5   465.1  6970.8  469.37
#Mann= 10 ,-1 , 0
  1494.6     .05       0    2356      .1       0  2494.5    .075       0
  2820.3     .05       0  4983.8     .03       0  5008.8     .05       0
  5091.2    .075       0    5245      .1       0  6202.2    .075       0
  6461.5     .05       0
Bank Sta=4983.8,5008.8
XS Rating Curve= 0 ,0
Exp/Cntr=0.3,0.1

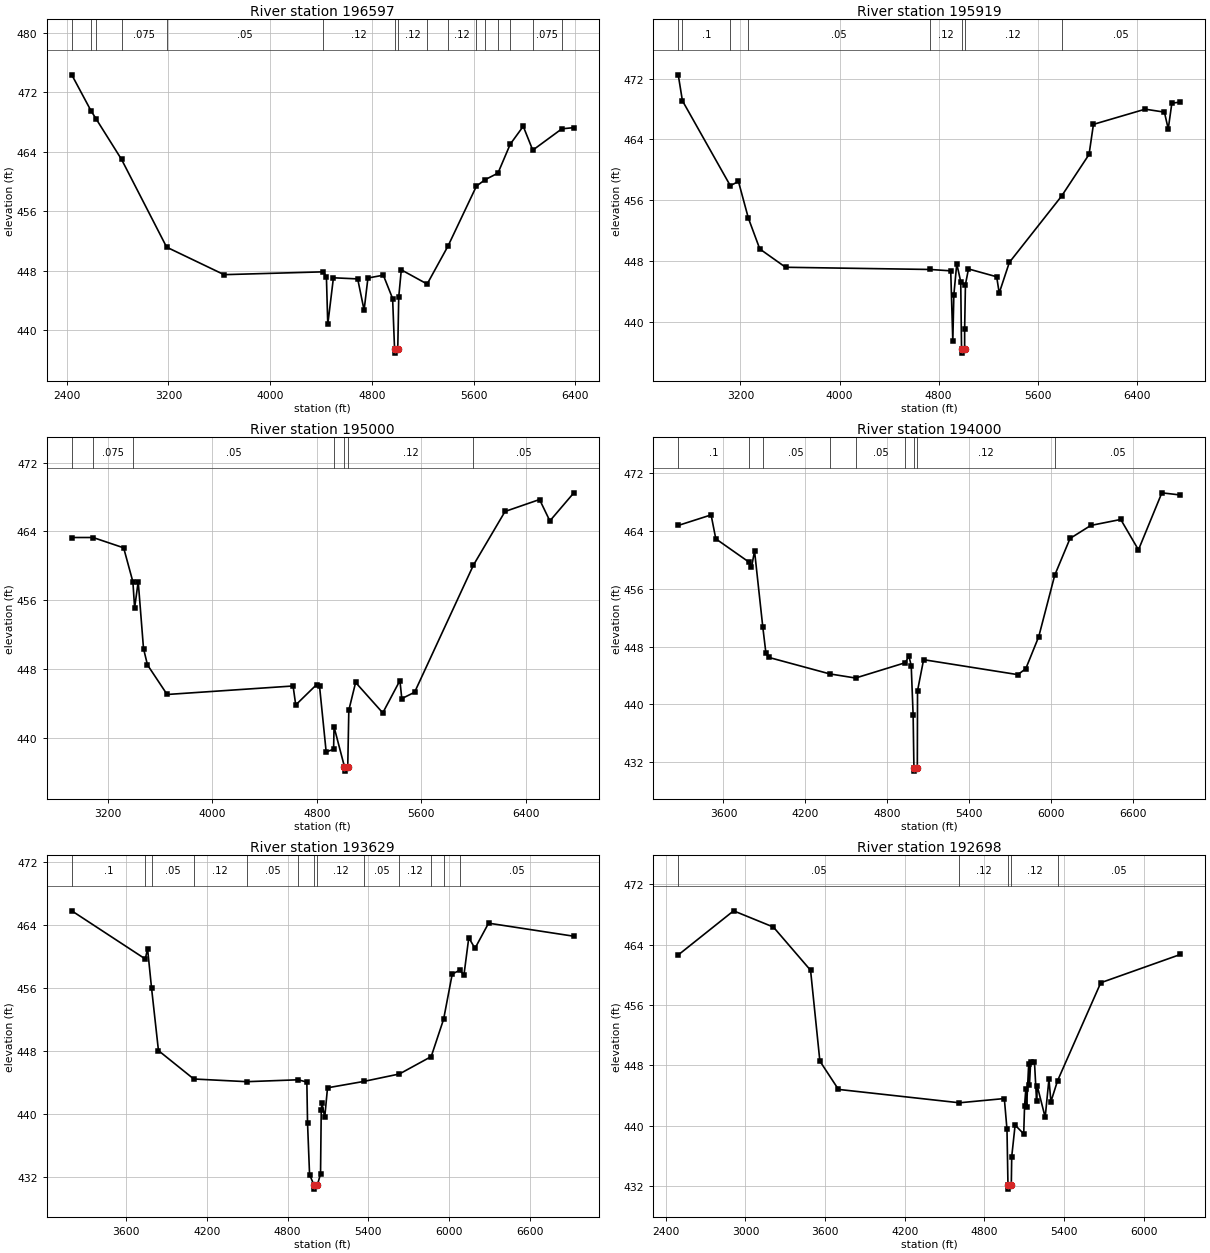
Type RM Length L Ch R = 1 ,196597  ,678,678,678
BEGIN DESCRIPTION:
Kings Creek 388.0
END DESCRIPTION:
XS GIS Cut Line= 4
      2659579.64      6947004.06      2657876.46      6948081.17
      2657336.47      6948151.18      2655960.44       6948326.9
#Sta/Elev= 30
  2440.3  474.34  2591.4  469.51  2632.9  468.38  2831.5  462.97  3186.1  451.17
  3637.5  447.47  4416.9  447.85  4442.1  447.17  4452.8  440.78  4497.2  447.05
  4687.9   446.9  4738.3   442.7  4768.5  447.02  4889.6   447.4  4962.5  444.26
  4977.9  437.42  4980.4  436.92  5002.9  437.42  5010.6  444.45  5030.7  448.12
    5234  446.21  5398.1  451.32  5621.6  459.38  5690.5  460.25  5790.6  461.12
    5887  465.01  5989.4  467.42  6064.2  464.21  6292.9  467.08  6387.2  467.24
#Mann= 16 ,-1 , 0
  2440.3    .075       0  2591.4     .05       0  2632.9      .1       0
  2831.5    .075       0  3186.1     .05       0  4416.9     .12       0
  4977.9     .07       0  5002.9     .12       0    5234     .05       0
  5398.1     .12       0  5621.6     .05       0  5690.5      .1       0
  5790.6    .075       0    5887      .1       0  6064.2    .075       0
  6292.9     .05       0
Bank Sta=4977.9,5002.9
XS Rating Curve= 0 ,0
Exp/Cntr=0.3,0.1

Type RM Length L Ch R = 1 ,195919  ,919,919,919
BEGIN DESCRIPTION:
Kings Creek 387.0
END DESCRIPTION:
XS GIS Cut Line= 3
      2659485.87      6946978.02      2657325.23      6947771.69
      2655631.73      6948212.39
#Sta/Elev= 30
  2698.2  472.49  2731.9  469.08  3118.3   457.9  3184.1  458.45  3264.1  453.63
  3356.3  449.57  3564.4  447.16  4731.7  446.87  4897.2  446.69    4914  437.42
  4922.4  443.54  4945.9  447.62  4977.9  445.26  4984.4  436.36  4986.9  435.86
  5009.4  436.36  5009.5  439.05  5015.9  444.89  5040.5  446.94  5267.9  445.91
  5288.5  443.77  5370.2   447.8  5791.8  456.53  6013.4  462.01  6048.8  465.97
  6466.5  467.97  6621.5  467.58  6652.5  465.36  6681.6  468.76  6749.9   468.9
#Mann= 8 ,-1 , 0
  2698.2    .075       0  2731.9      .1       0  3118.3    .075       0
  3264.1     .05       0  4731.7     .12       0  4984.4     .07       0
  5009.4     .12       0  5791.8     .05       0
Bank Sta=4984.4,5009.4
XS Rating Curve= 0 ,0
Exp/Cntr=0.3,0.1

Type RM Length L Ch R = 1 ,195000  ,1000,1000,1000
BEGIN DESCRIPTION:
Kings Creek 385.0
END DESCRIPTION:
XS GIS Cut Line= 3
        2659288.      6946670.72      2657240.11      6946996.93
      2655539.44       6947477.6
#Sta/Elev= 30
  2926.3   463.3    3089   463.3  3323.2   462.1  3393.9  458.14  3407.1   455.1
  3434.6  458.17  3475.1  450.38  3505.5  448.47  3655.7  445.03  4619.4  446.02
  4639.6  443.81    4800  446.19  4821.9  445.98  4872.5  438.34  4929.4  438.66
  4932.8  441.26  5012.6  436.61  5015.1  436.11  5037.6  436.61  5045.8   443.2
  5097.8  446.43  5305.6  442.89  5436.7  446.65  5451.1  444.55    5549  445.29
  5998.9  460.08  6240.9  466.33    6505  467.72  6583.8  465.23  6767.3   468.5
#Mann= 7 ,-1 , 0
  2926.3      .1       0    3089    .075       0  3393.9     .05       0
  4932.8     .12       0  5012.6     .07       0  5037.6     .12       0
  5998.9     .05       0
Bank Sta=5012.6,5037.6
XS Rating Curve= 0 ,0
Exp/Cntr=0.3,0.1

Type RM Length L Ch R = 1 ,194000  ,371,371,371
BEGIN DESCRIPTION:
Kings Creek 383.0
END DESCRIPTION:
XS GIS Cut Line= 3
      2659084.89      6945842.59        2657416.      6946302.12
      2655621.45      6947056.08
#Sta/Elev= 30
    3269   464.8  3509.7  466.26  3544.1  462.95    3785  459.75  3805.6  458.99
  3827.9  461.26  3888.4  450.72  3910.9  447.16  3931.7  446.52    4379  444.23
  4567.6  443.66  4931.7  445.78  4958.5   446.7  4975.5  445.37  4989.6  438.47
  4995.2  431.26  4997.7  430.76  5020.2  431.26  5021.7  441.89  5066.1   446.2
  5756.3  444.13  5814.6  444.95  5909.7   449.4  6026.7  457.91  6138.9     463
  6290.8   464.8  6510.3  465.63  6639.9  461.42  6811.4  469.32  6946.5  469.02
#Mann= 9 ,-1 , 0
    3269      .1       0    3785    .075       0  3888.4     .05       0
    4379     .12       0  4567.6     .05       0  4931.7     .12       0
  4995.2     .07       0  5020.2     .12       0  6026.7     .05       0
Bank Sta=4995.2,5020.2
XS Rating Curve= 0 ,0
Exp/Cntr=0.3,0.1

Type RM Length L Ch R = 1 ,193629  ,931,931,931
BEGIN DESCRIPTION:
Kings Creek 382.0
END DESCRIPTION:
XS GIS Cut Line= 3
      2659032.77      6945712.39       2657249.9      6945983.72
      2655381.76      6946457.17
#Sta/Elev= 30
  3196.6  465.83  3742.8  459.71  3759.8  461.01  3789.7  455.96  3840.7  448.06
  4103.2  444.45  4497.6  444.11  4878.6  444.35  4943.3  444.06  4948.5  438.83
  4963.5   432.3  4996.7  430.95  4999.2  430.45  5021.7  430.95  5045.1  432.42
  5050.2  440.46  5055.6  441.38  5076.2  439.59  5096.9  443.33    5366  444.14
  5631.1  445.09  5867.3   447.3  5959.5  452.05  6023.5  457.79  6078.6  458.28
  6110.7  457.68  6146.5  462.41  6192.6  461.06  6293.5  464.26  6927.2   462.6
#Mann= 13 ,-1 , 0
  3196.6      .1       0  3742.8    .075       0  3789.7     .05       0
  4103.2     .12       0  4497.6     .05       0  4878.6     .12       0
  4996.7     .07       0  5021.7     .12       0    5366     .05       0
  5631.1     .12       0  5867.3     .05       0  5959.5     .12       0
  6078.6     .05       0
Bank Sta=4996.7,5021.7
XS Rating Curve= 0 ,0
Exp/Cntr=0.3,0.1

Type RM Length L Ch R = 1 ,192698  ,1282,1282,1282
BEGIN DESCRIPTION:
Mapping XS c361902d
END DESCRIPTION:
XS GIS Cut Line= 3
       2659333.1      6945280.62      2656819.71      6945322.16
      2655713.97      6945946.58
#Sta/Elev= 30
  2493.4  462.63  2910.6  468.47  3210.6  466.32  3490.6   460.6  3560.7  448.58
  3700.7  444.83  4612.3  443.06  4950.8  443.62  4970.8  439.55  4978.3  432.13
  4980.8  431.63  5003.3  432.13  5006.5  435.92    5032   440.1  5096.9  438.95
  5103.3  442.67  5112.8  444.89  5118.6  442.48  5134.5  448.24  5140.2  445.41
  5149.2  448.46  5177.8  448.52  5193.7  443.32  5199.4  445.24  5258.7  441.14
    5287  446.18    5302  443.21  5351.7  445.97  5677.5  458.95    6277  462.69
#Mann= 5 ,-1 , 0
  2493.4     .05       0  4612.3     .12       0  4978.3     .07       0
  5003.3     .12       0  5351.7     .05       0
Bank Sta=4978.3,5003.3
XS Rating Curve= 0 ,0
Exp/Cntr=0.3,0.1