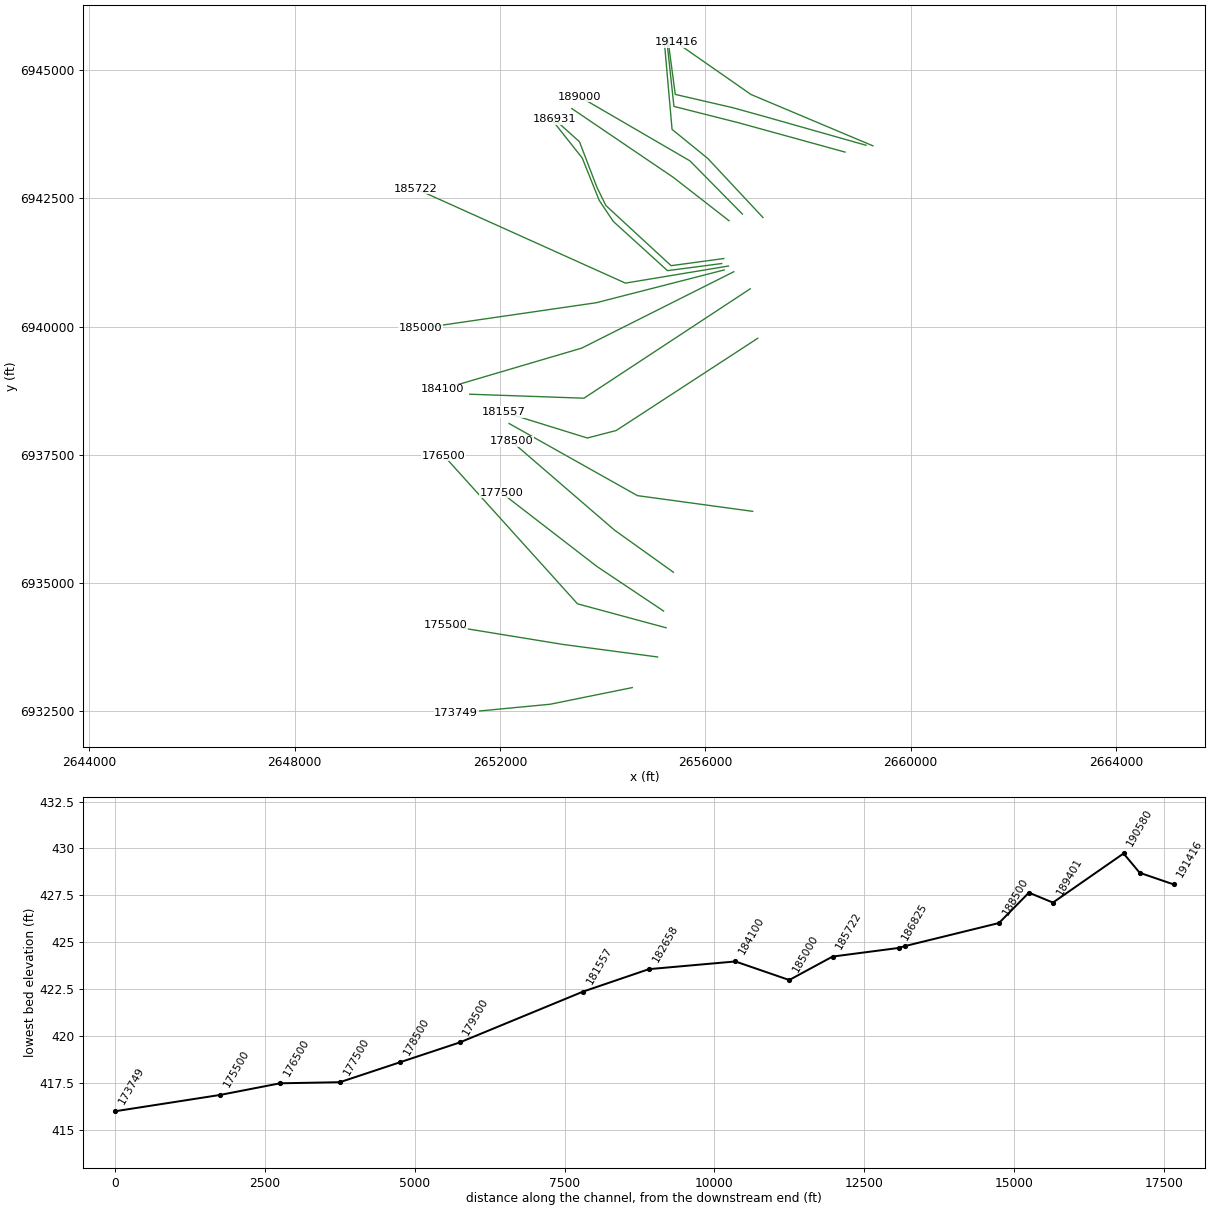
HEC-RAS study Kings Creek.prj: Kings Creek Base Level Engineering

--- Kings Creek.g01 (geometry) --- (continued)

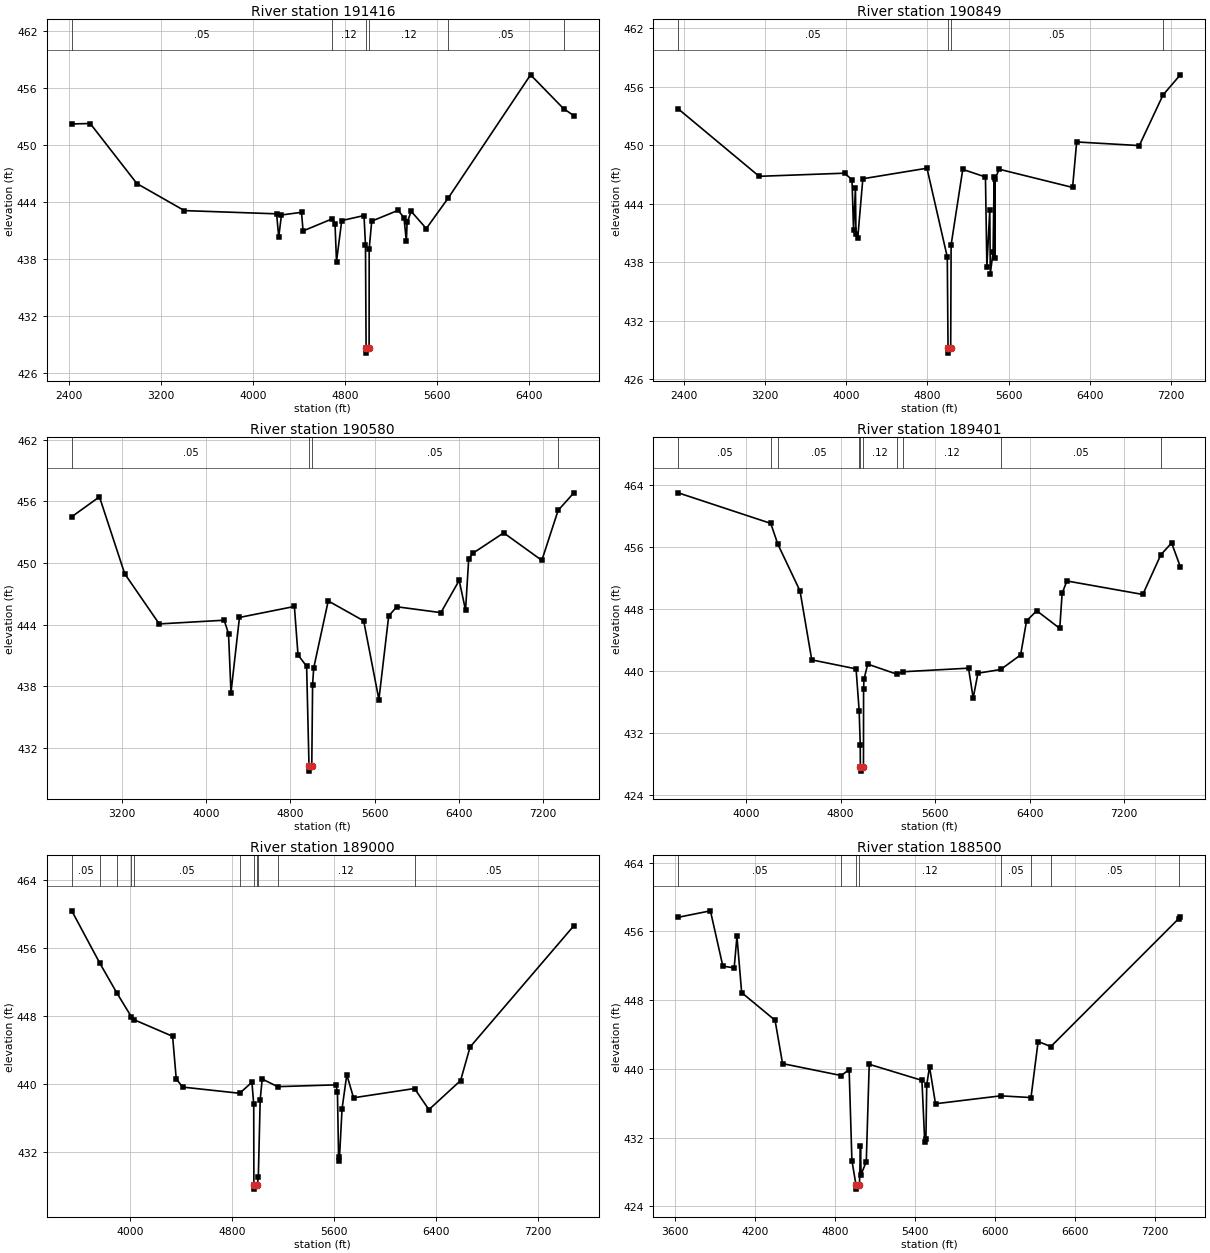
Type RM Length L Ch R = 1 ,191416  ,567,567,567
BEGIN DESCRIPTION:
Mapping XS d7375370
END DESCRIPTION:
XS GIS Cut Line= 3
      2659263.65      6943527.16      2656889.15      6944527.89
      2655427.83      6945546.92
#Sta/Elev= 30
  2426.9  452.22  2587.1  452.26  2992.2  445.94  3404.4  443.09    4205  442.75
  4223.3   440.3  4247.1  442.63  4421.1  442.91  4434.8  440.95  4689.2  442.23
  4712.1  441.67  4724.9  437.73  4770.4  442.04  4963.7  442.57  4976.5  439.47
  4981.8  428.58  4984.4  428.08  5007.8  428.58  5008.6  439.04  5030.6  441.98
    5260  443.12  5310.6  442.34  5331.5  439.85  5337.6  441.84  5373.4  443.01
  5504.3   441.2  5696.3  444.44  6409.5  457.39  6695.7  453.83  6785.2  453.09
#Mann= 6 ,-1 , 0
  2426.9     .05       0  4689.2     .12       0  4981.8     .07       0
  5007.8     .12       0  5696.3     .05       0  6695.7    .075       0
Bank Sta=4981.8,5007.8
XS Rating Curve= 0 ,0
Exp/Cntr=0.3,0.1

Type RM Length L Ch R = 1 ,190849  ,269,269,269
BEGIN DESCRIPTION:
Mapping XS c8b0de82
END DESCRIPTION:
XS GIS Cut Line= 5
      2659128.74      6943538.31      2657206.75      6944083.56
      2656537.97      6944269.68      2655412.97       6944530.1
      2655267.14      6945623.84
#Sta/Elev= 30
  2342.4  453.73  3140.2  446.82  3982.6  447.14  4055.6  446.47  4070.8  441.33
  4089.5  445.62  4094.7  440.91  4112.3  440.49  4162.5  446.57  4794.7  447.65
    4995  438.55  5002.5   429.2  5005.1   428.7  5028.7   429.2  5032.9   439.8
  5147.7  447.53  5371.4  446.75  5385.4  437.57  5414.1  443.35  5419.3  436.82
    5447  439.11  5456.8  446.79    5462  438.47  5467.6   446.5  5504.7  447.55
  6230.4  445.68  6270.8  450.34  6888.1  449.97  7122.5  455.16  7292.6  457.22
#Mann= 4 ,-1 , 0
  2342.4     .05       0  5002.5     .05       0  5028.7     .05       0
  7122.5    .075       0
Bank Sta=5002.5,5028.7
XS Rating Curve= 0 ,0
Exp/Cntr=0.3,0.1

Type RM Length L Ch R = 1 ,190580  ,1179,1179,1179
BEGIN DESCRIPTION:
Mapping XS 52f7c9e5
END DESCRIPTION:
XS GIS Cut Line= 4
      2658720.26       6943405.1      2656642.13      6943978.02
      2655386.93      6944295.73       2655246.3      6945603.04
#Sta/Elev= 30
  2724.6  454.51  2987.3  456.45  3226.9  448.96  3554.7  444.07  4170.9  444.43
  4212.4  443.13  4235.7  437.38  4316.1   444.7  4837.5  445.77  4871.9  441.05
  4953.6  439.94  4976.3  430.23  4978.9  429.73  5002.5  430.23  5010.4  438.14
  5020.7  439.77  5158.6  446.31  5495.2  444.37  5639.6   436.7  5732.7  444.85
  5809.6  445.74    6228  445.17  6401.6  448.31    6462  445.41  6492.1  450.42
  6532.4  450.96    6824  452.94  7186.1  450.26  7340.6  455.13  7489.9  456.84
#Mann= 4 ,-1 , 0
  2724.6     .05       0  4976.3     .03       0  5002.5     .05       0
  7340.6    .075       0
Bank Sta=4976.3,5002.5
XS Rating Curve= 0 ,0
Exp/Cntr=0.3,0.1

Type RM Length L Ch R = 1 ,189401  ,401,401,401
BEGIN DESCRIPTION:
Kings Creek 374.0
END DESCRIPTION:
XS GIS Cut Line= 4
      2657121.27      6942129.09      2656046.66       6943280.4
      2655350.47      6943847.81      2655194.34      6945617.31
#Sta/Elev= 30
  3425.1  462.98  4208.2  459.04  4267.8  456.37  4455.9  450.33  4555.1  441.45
  4930.3  440.29  4956.3  434.91  4965.5  430.51  4966.5  427.61  4969.1  427.11
  4992.8  427.61  4993.8  437.65    4997  438.94  5028.9   440.9    5273  439.62
  5329.7  439.92    5882  440.38  5921.4  436.53  5961.6  439.73  6154.4  440.21
    6323  442.09  6373.2  446.48  6459.7  447.78  6654.2   445.5  6674.3  450.03
  6714.5  451.62    7357  449.88  7509.9     455  7600.8  456.52  7674.5  453.46
#Mann= 10 ,-1 , 0
  3425.1     .05       0  4208.2     .12       0  4267.8     .05       0
  4956.3     .12       0  4966.5     .07       0  4992.8     .12       0
    5273     .05       0  5329.7     .12       0  6154.4     .05       0
  7509.9    .075       0
Bank Sta=4966.5,4992.8
XS Rating Curve= 0 ,0
Exp/Cntr=0.3,0.1

Type RM Length L Ch R = 1 ,189000  ,500,500,500
BEGIN DESCRIPTION:
Kings Creek 373.0
END DESCRIPTION:
XS GIS Cut Line= 3
      2656720.28      6942196.75      2655698.59      6943234.09
       2653553.6      6944483.22
#Sta/Elev= 30
    3544  460.42  3764.8  454.23    3899  450.71  4010.3  447.97  4033.2  447.59
    4335  445.64  4363.3  440.64  4412.7  439.66  4860.9  438.93  4957.2  440.23
  4971.3  437.61  4972.3  428.14  4974.9  427.64  4998.6  428.14  5007.2  429.02
    5022  438.19  5037.7  440.61  5158.7  439.71  5615.2  439.92  5627.9  439.09
  5636.7  431.47  5642.5  430.95    5664  437.09  5701.2  441.12  5754.2   438.4
  6232.5  439.49  6345.4     437  6593.8  440.43  6668.3  444.38  7482.2  458.66
#Mann= 11 ,-1 , 0
    3544     .05       0  3764.8     .12       0    3899     .05       0
  4010.3     .12       0  4033.2     .05       0  4860.9     .12       0
  4972.3     .07       0  4998.6     .12       0  5007.2     .05       0
  5158.7     .12       0  6232.5     .05       0
Bank Sta=4972.3,4998.6
XS Rating Curve= 0 ,0
Exp/Cntr=0.3,0.1

Type RM Length L Ch R = 1 ,188500  ,1569,1569,1569
BEGIN DESCRIPTION:
Kings Creek 372.0
END DESCRIPTION:
XS GIS Cut Line= 3
      2656459.86      6942066.54      2655375.36      6942911.48
      2653397.36      6944254.05
#Sta/Elev= 30
  3625.2  457.64  3866.5  458.39  3959.7  451.96  4044.7  451.75  4065.5  455.42
  4100.8  448.88  4351.4  445.66  4407.5  440.62  4847.9  439.23  4906.9  439.93
  4927.7  429.34    4958  426.52  4960.6  426.02  4984.3  426.52    4992  430.99
  4996.4  427.72  5035.5  429.22  5057.5  440.54  5452.8  438.67  5473.8  431.52
  5482.7  431.88  5488.8  438.13  5509.7  440.26  5554.6  435.95  6043.4  436.87
  6270.7  436.67  6324.2  443.19  6419.6   442.6  7378.4  457.48  7390.6  457.64
#Mann= 8 ,-1 , 0
  3625.2     .05       0  4847.9     .12       0    4958     .07       0
  4984.3     .12       0  6043.4     .05       0  6270.7     .12       0
  6419.6     .05       0  7378.4    .075       0
Bank Sta=4958,4984.3
XS Rating Curve= 0 ,0
Exp/Cntr=0.3,0.1

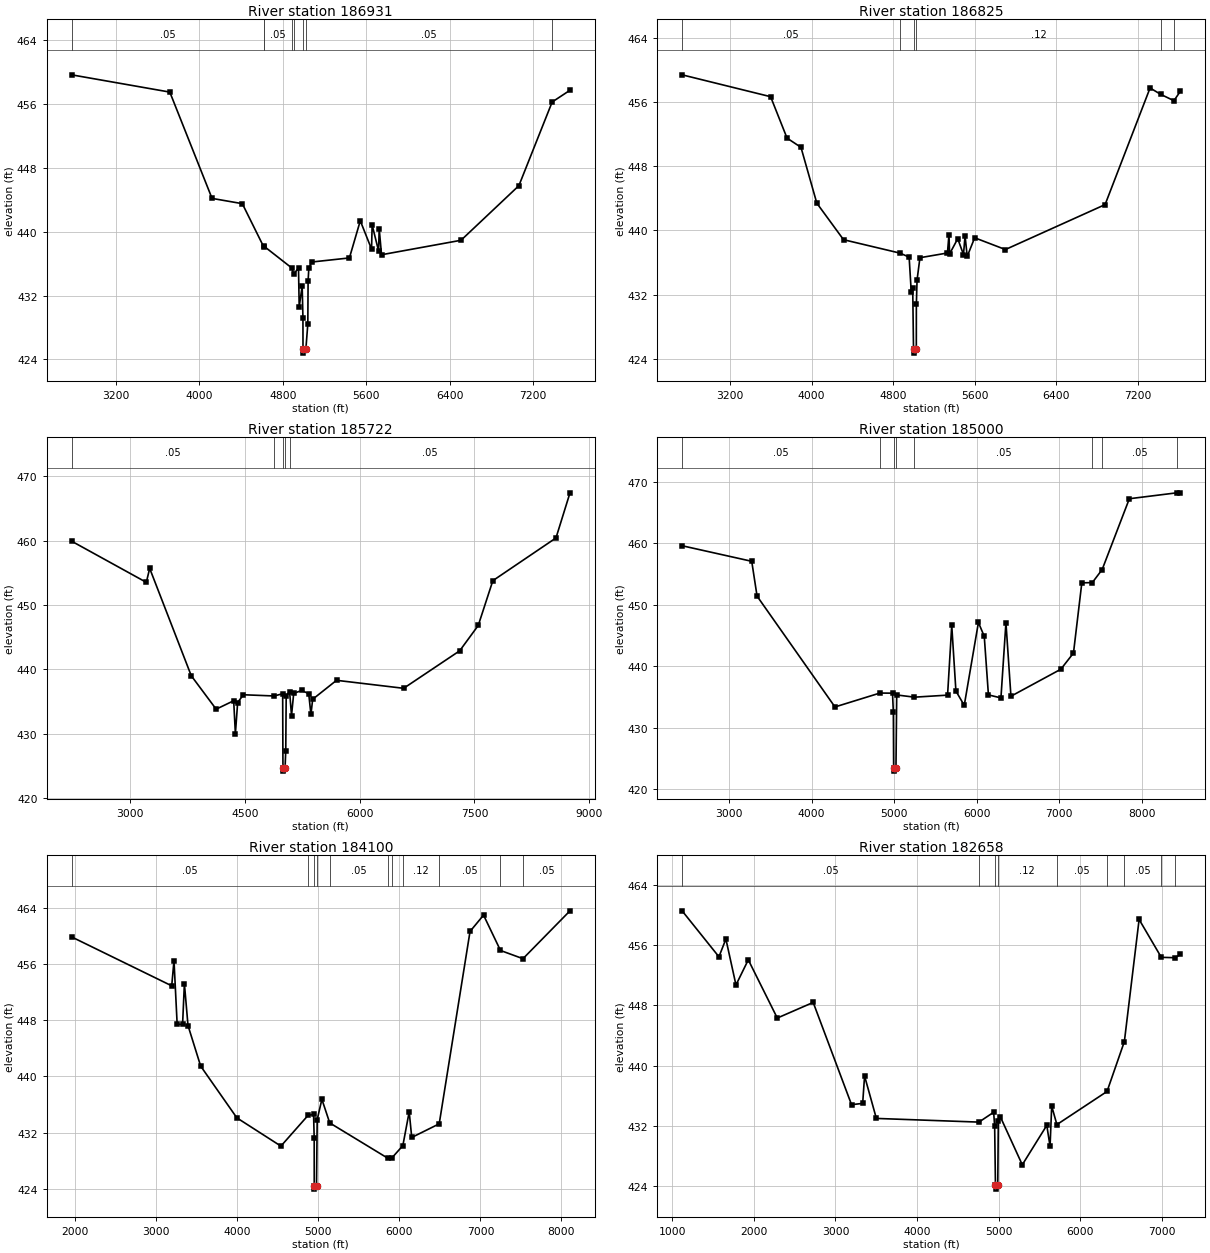
Type RM Length L Ch R = 1 ,186931  ,106,106,106
BEGIN DESCRIPTION:
Mapping XS 589bc8d4
END DESCRIPTION:
XS GIS Cut Line= 6
      2656359.13      6941328.71      2655331.37      6941189.82
      2654060.54      6942363.43      2653886.93       6942717.6
      2653546.65      6943606.49      2653053.63       6944050.9
#Sta/Elev= 30
  2774.8  459.61  3716.4  457.45  4121.2  444.15  4411.4  443.49  4615.4  438.12
  4616.7  438.19  4887.1  435.43  4902.7   434.7  4950.1   435.4  4956.7  430.59
  4985.2  433.17  4992.7  429.19  4993.1  425.29  4995.9  424.79  5020.7  425.29
  5039.4  428.45    5042   433.8    5049  435.41  5077.3  436.19  5438.1   436.7
  5542.3  441.35  5650.4   437.8    5656  440.82  5717.9  437.57  5723.5  440.38
    5746   437.1  6507.9  438.91  7062.7  445.74  7381.7  456.21  7552.6  457.68
#Mann= 8 ,-1 , 0
  2774.8     .05       0  4615.4     .12       0  4616.7     .05       0
  4887.1     .12       0  4902.7     .05       0  4993.1     .05       0
  5020.7     .05       0  7381.7    .075       0
Bank Sta=4993.1,5020.7
XS Rating Curve= 0 ,0
Exp/Cntr=0.3,0.1

Type RM Length L Ch R = 1 ,186825  ,1103,1103,1103
BEGIN DESCRIPTION:
Mapping XS 05b08e9f
END DESCRIPTION:
XS GIS Cut Line= 6
      2656317.47      6941231.49      2655261.93       6941092.6
      2654205.97      6942052.29      2653930.36      6942464.61
      2653600.93      6943288.83      2652970.63      6944085.18
#Sta/Elev= 30
  2728.4  459.43  3597.3   456.7  3758.7  451.53  3895.4  450.38    4051  443.41
  4313.2  438.85  4868.9  437.17  4957.3  436.67  4978.3  432.26  4992.4  432.83
  5000.2  425.19  5002.9  424.69  5027.8  425.19  5028.2  430.77    5035  433.81
  5063.3   436.6  5333.5  437.19  5348.2  439.49  5354.4  437.08  5434.3  438.97
  5490.8     437  5506.2  439.34  5527.4  436.76  5600.6  439.09  5902.3  437.62
    6881  443.23  7322.5  457.79  7428.8  456.98  7556.8   456.2  7621.2   457.4
#Mann= 6 ,-1 , 0
  2728.4     .05       0  4868.9     .12       0  5000.2     .07       0
  5027.8     .12       0  7428.8    .075       0  7556.8      .1       0
Bank Sta=5000.2,5027.8
XS Rating Curve= 0 ,0
Exp/Cntr=0.3,0.1

Type RM Length L Ch R = 1 ,185722  ,722,722,722
BEGIN DESCRIPTION:
Kings Creek 367.0
END DESCRIPTION:
XS GIS Cut Line= 3
      2656449.43      6941182.88      2654442.48      6940849.54
      2650360.06      6942689.41
#Sta/Elev= 30
  2235.4  459.91    3212  453.52  3255.8  455.69  3799.1  439.03  4124.4  433.84
  4353.4  435.15  4375.7  430.02  4405.2  434.87  4480.1  436.08  4882.5  435.89
  4993.4  436.24  4997.2  424.73  4999.9  424.23  5024.8  424.73  5033.8  427.41
  5039.6  435.95  5084.1  436.56  5109.1  432.86  5137.7   436.3  5242.2  436.74
  5333.8  436.25  5362.8  433.02  5385.5  435.38  5697.3  438.32  6574.1  437.08
  7306.6   442.9    7549  446.83  7739.6  453.78  8564.6  460.41  8747.7  467.41
#Mann= 5 ,-1 , 0
  2235.4     .05       0  4882.5     .12       0  4997.2     .07       0
  5024.8     .12       0  5084.1     .05       0
Bank Sta=4997.2,5024.8
XS Rating Curve= 0 ,0
Exp/Cntr=0.3,0.1

Type RM Length L Ch R = 1 ,185000  ,900,900,900
BEGIN DESCRIPTION:
Kings Creek 365.0
END DESCRIPTION:
XS GIS Cut Line= 3
      2656366.07      6941106.48      2653876.38      6940467.42
      2650442.47       6939967.6
#Sta/Elev= 30
  2429.6  459.61  3273.6  457.08  3338.2  451.42  4282.3  433.41  4827.3  435.67
  4979.7  435.65  4990.1  432.59  4993.6  423.48  4996.4  422.98  5021.6  423.48
  5030.7  435.36  5245.9     435  5647.1  435.33  5697.7  446.65  5748.2     436
  5849.2  433.66    6021  447.14  6091.8  444.88  6142.3  435.37  6293.9  434.88
  6354.5  447.12  6415.1  435.15  7019.8  439.54    7173  442.17  7274.1  453.58
  7401.3  453.62  7520.7  455.74  7850.1  467.25  8424.6  468.21  8470.1   468.2
#Mann= 8 ,-1 , 0
  2429.6     .05       0  4827.3     .12       0  4993.6     .07       0
  5021.6     .12       0  5245.9     .05       0  7401.3     .12       0
  7520.7     .05       0  8424.6     .12       0
Bank Sta=4993.6,5021.6
XS Rating Curve= 0 ,0
Exp/Cntr=0.3,0.1

Type RM Length L Ch R = 1 ,184100  ,1442,1442,1442
BEGIN DESCRIPTION:
Kings Creek 363.0
END DESCRIPTION:
XS GIS Cut Line= 3
      2656553.58      6941071.76      2653590.28      6939581.79
      2650873.07      6938780.11
#Sta/Elev= 30
  1955.5  459.85  3191.1  452.89  3219.1  456.48  3258.1  447.43  3325.1   447.4
  3347.4  453.21    3392  447.24  3548.3  441.47  3994.8  434.11  4538.4  430.09
  4874.8  434.48  4941.3  434.59  4949.1  431.25  4949.6  424.47  4952.4  423.97
  4977.7  424.47  4986.1  433.86    5044  436.75  5140.6  433.39  5855.4  428.38
  5905.4  428.38  6042.9  430.16  6121.3  434.97  6152.6  431.32  6491.6  433.26
    6872  460.63  7038.8  462.95  7247.7  457.92  7525.2  456.75  8105.3  463.56
#Mann= 11 ,-1 , 0
  1955.5     .05       0  4874.8     .12       0  4949.6     .07       0
  4977.7     .12       0  5140.6     .05       0  5855.4     .12       0
  5905.4     .05       0  6042.9     .12       0  6491.6     .05       0
  7247.7     .12       0  7525.2     .05       0
Bank Sta=4949.6,4977.7
XS Rating Curve= 0 ,0
Exp/Cntr=0.3,0.1

Type RM Length L Ch R = 1 ,182658  ,1101,1101,1101
BEGIN DESCRIPTION:
Kings Creek 360.0
END DESCRIPTION:
XS GIS Cut Line= 3
        2656873.      6940738.41      2653634.13      6938604.94
       2651409.4      6938682.82
#Sta/Elev= 30
  1121.6   460.6    1573  454.48    1658  456.85  1781.5  450.73  1932.3  454.08
  2287.5  446.33  2727.2  448.41    3197   434.8  3333.3  434.97  3356.6  438.62
  3500.9  432.97  4757.2  432.48  4937.7  433.79  4949.9  431.93  4959.7  424.06
  4962.5  423.56  4987.9  424.06  4994.9  432.63  5018.1  433.22  5288.3   426.8
  5588.5  432.05  5628.5  429.25  5648.5  434.61  5712.2  432.15  6326.3  436.56
  6538.6   443.2  6719.2  459.45    6991  454.41  7158.6  454.36  7226.1  454.79
#Mann= 9 ,-1 , 0
  1121.6     .05       0  4757.2     .12       0  4959.7     .07       0
  4987.9     .12       0  5712.2     .05       0  6326.3     .12       0
  6538.6     .05       0    6991     .12       0  7158.6     .05       0
Bank Sta=4959.7,4987.9
XS Rating Curve= 0 ,0
Exp/Cntr=0.3,0.1

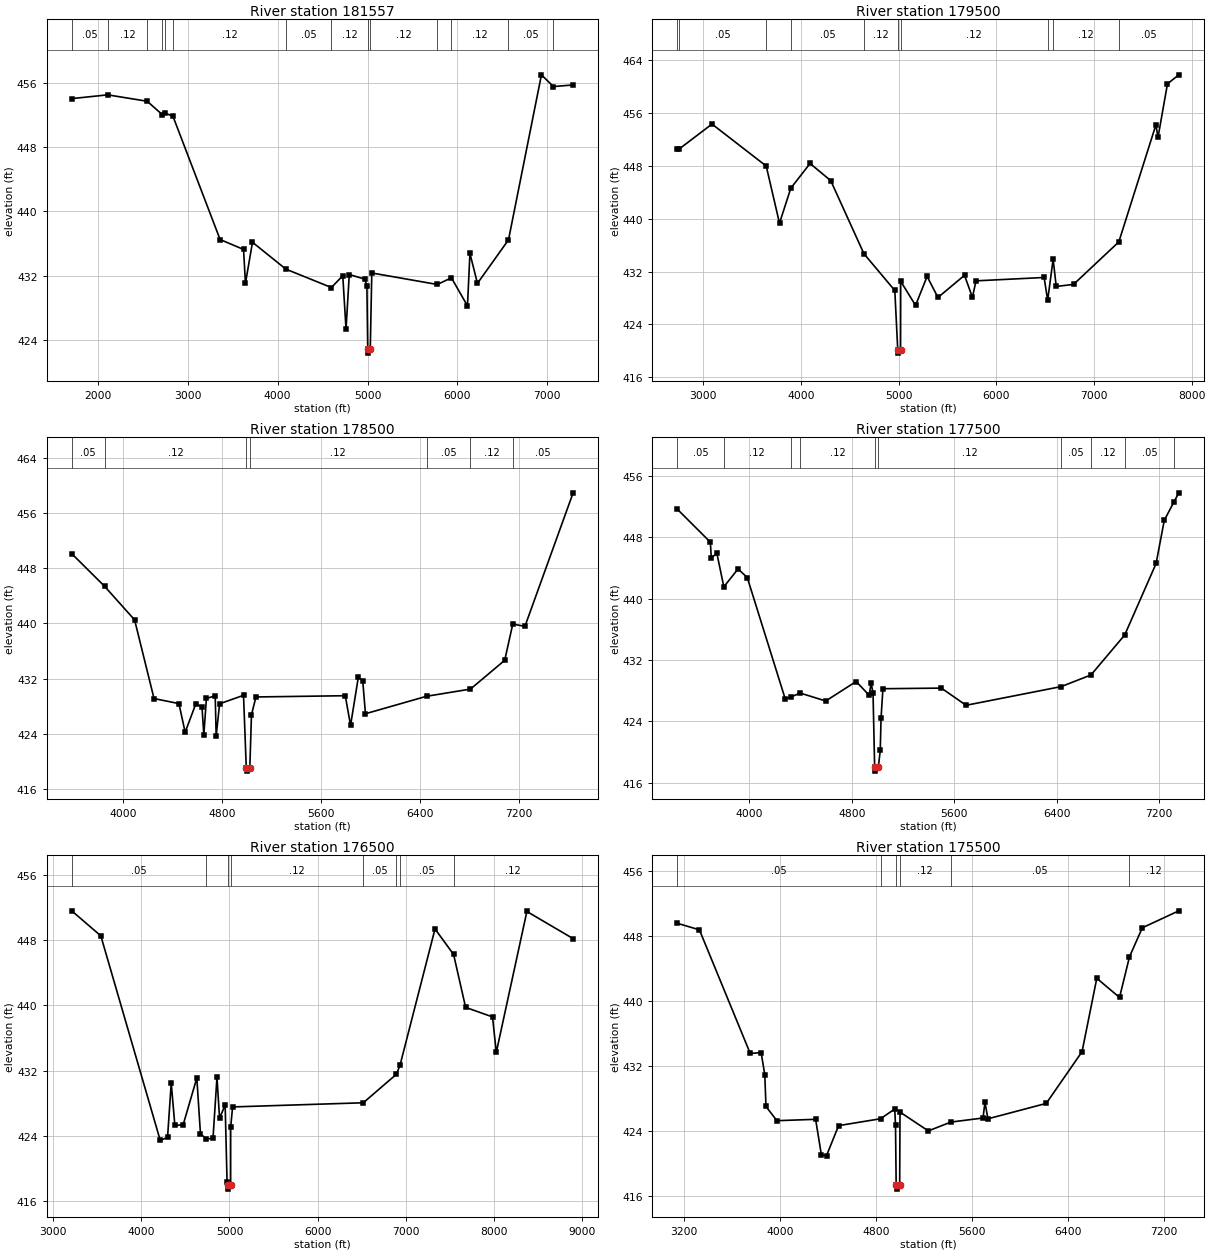
Type RM Length L Ch R = 1 ,181557  ,2057,2057,2057
BEGIN DESCRIPTION:
Kings Creek 359.0
END DESCRIPTION:
XS GIS Cut Line= 4
      2657018.85      6939773.14      2654261.87      6937974.36
      2653699.43      6937828.71      2652069.26       6938335.1
#Sta/Elev= 30
  1708.1  454.02  2108.8  454.49  2548.2  453.69  2714.9  452.04  2749.8   452.2
  2834.1  451.84  3359.3  436.49  3620.2  435.26  3641.3  431.05  3719.7  436.15
  4090.9  432.81  4597.8  430.52  4724.4  431.99  4760.7  425.35  4796.9  432.14
  4971.2  431.56    4993  430.71  5002.2  422.86    5005  422.36  5030.5  422.86
  5047.4  432.33  5776.7   430.9  5933.4  431.73  6112.3  428.24  6139.6  434.77
  6223.3  431.04  6568.8  436.45  6935.4  456.98  7068.6  455.52    7288  455.72
#Mann= 14 ,-1 , 0
  1708.1     .05       0  2108.8     .12       0  2548.2     .05       0
  2714.9     .12       0  2749.8     .05       0  2834.1     .12       0
  4090.9     .05       0  4597.8     .12       0  5002.2     .07       0
  5030.5     .12       0  5776.7     .05       0  5933.4     .12       0
  6568.8     .05       0  7068.6     .12       0
Bank Sta=5002.2,5030.5
XS Rating Curve= 0 ,0
Exp/Cntr=0.3,0.1

Type RM Length L Ch R = 1 ,179500  ,1000,1000,1000
BEGIN DESCRIPTION:
Kings Creek 354.0
END DESCRIPTION:
XS GIS Cut Line= 3
      2656921.63      6936398.16      2654676.64      6936704.51
      2652176.04      6938110.98
#Sta/Elev= 30
  2734.2  450.61  2754.3   450.6  3088.1  454.35  3643.5  447.99  3779.4  439.33
  3894.9  444.63  4092.3  448.38  4304.2  445.78  4643.9  434.71  4960.3  429.14
  4990.4  420.15  4993.2  419.65  5019.2  420.15  5020.7  430.53  5172.8  426.88
    5291  431.27  5402.3  428.08  5674.1  431.44    5755  428.11  5792.4   430.6
  6489.3  431.11  6525.7  427.66  6581.7  433.86  6613.6  429.75  6790.6  430.06
  7254.5   436.5  7634.1  454.23  7655.8  452.34  7752.7  460.45    7869  461.81
#Mann= 10 ,-1 , 0
  2734.2     .12       0  2754.3     .05       0  3643.5     .12       0
  3894.9     .05       0  4643.9     .12       0  4990.4     .07       0
  5019.2     .12       0  6525.7     .05       0  6581.7     .12       0
  7254.5     .05       0
Bank Sta=4990.4,5019.2
XS Rating Curve= 0 ,0
Exp/Cntr=0.3,0.1

Type RM Length L Ch R = 1 ,178500  ,1000,1000,1000
BEGIN DESCRIPTION:
Kings Creek 352.0
END DESCRIPTION:
XS GIS Cut Line= 3
      2655376.01      6935210.99      2654225.87      6936034.73
      2652225.97      6937761.02
#Sta/Elev= 30
  3585.3  450.08  3851.3  445.35  4093.9  440.49  4251.1   429.1  4452.5  428.37
  4502.9  424.22  4588.9  428.32  4639.2  427.88    4654  423.84  4674.9  429.11
  4746.1   429.5  4753.8  423.68  4781.7  428.34  4975.2  429.57  4997.4  419.09
  5000.2  418.59  5026.2  419.09  5039.5  426.73  5075.5  429.33  5798.4  429.51
  5841.2  425.22  5904.8  432.26  5939.9   431.6  5961.8   426.9  6456.3  429.43
  6811.3  430.47  7088.5  434.64  7153.6  439.89  7251.9  439.55  7641.9  458.89
#Mann= 7 ,-1 , 0
  3585.3     .05       0  3851.3     .12       0  4997.4     .07       0
  5026.2     .12       0  6456.3     .05       0  6811.3     .12       0
  7153.6     .05       0
Bank Sta=4997.4,5026.2
XS Rating Curve= 0 ,0
Exp/Cntr=0.3,0.1

Type RM Length L Ch R = 1 ,177500  ,1000,1000,1000
BEGIN DESCRIPTION:
Kings Creek 350.0
END DESCRIPTION:
XS GIS Cut Line= 3
      2655185.54      6934453.71      2653887.84       6935322.2
        2652026.        6936761.
#Sta/Elev= 30
  3438.5  451.65  3695.5  447.37  3702.7  445.33  3746.5   445.9  3800.7  441.55
  3911.7  443.88  3983.7  442.76  4280.2  426.93  4322.6  427.19  4397.7   427.7
  4596.2  426.67  4833.8  429.21  4935.5  427.41  4950.5  428.97  4965.5  427.77
  4978.1  418.03  4980.9  417.53  5006.9  418.03  5021.9  420.23  5028.2  424.47
  5042.7  428.27  5499.2  428.35  5692.1  426.11  6435.4  428.55  6666.8  430.06
  6930.4  435.27  7175.5  444.59  7239.3  450.21  7315.6  452.64    7353   453.8
#Mann= 10 ,-1 , 0
  3438.5     .05       0  3800.7     .12       0  4322.6     .05       0
  4397.7     .12       0  4978.1     .07       0  5006.9     .12       0
  6435.4     .05       0  6666.8     .12       0  6930.4     .05       0
  7315.6     .12       0
Bank Sta=4978.1,5006.9
XS Rating Curve= 0 ,0
Exp/Cntr=0.3,0.1

Type RM Length L Ch R = 1 ,176500  ,1000,1000,1000
BEGIN DESCRIPTION:
Kings Creek 348.0
END DESCRIPTION:
XS GIS Cut Line= 3
      2655234.15      6934127.32      2653508.72       6934594.3
      2650902.02       6937487.1
#Sta/Elev= 30
  3212.5   451.6  3542.1  448.53  4215.5  423.44  4298.4  423.82  4339.8  430.48
  4381.2  425.28  4475.1  425.36  4629.9   431.1  4671.3  424.24  4739.3  423.63
  4813.1  423.69  4858.2  431.17  4887.7  426.17    4951  427.79  4972.6  418.33
  4984.4  417.97  4987.2  417.47  5013.2  417.97  5013.6  425.07  5035.3  427.55
  6516.2  428.06  6891.9  431.56  6933.3   432.7    7329  449.38  7539.5  446.25
  7675.8  439.76  7980.7  438.59  8023.3  434.24  8370.1  451.52    8894  448.19
#Mann= 8 ,-1 , 0
  3212.5     .05       0  4739.3     .12       0  4984.4     .07       0
  5013.2     .12       0  6516.2     .05       0  6891.9     .12       0
  6933.3     .05       0  7539.5     .12       0
Bank Sta=4984.4,5013.2
XS Rating Curve= 0 ,0
Exp/Cntr=0.3,0.1

Type RM Length L Ch R = 1 ,175500  ,1751,1751,1751
BEGIN DESCRIPTION:
Kings Creek 346.0
END DESCRIPTION:
XS GIS Cut Line= 3
      2655067.45      6933557.88       2653226.5      6933802.23
      2650935.58      6934175.93
#Sta/Elev= 30
  3142.9  449.59  3325.9  448.79  3749.6  433.56  3840.4  433.67  3870.7  430.96
  3880.8  427.03  3971.6  425.28  4294.4  425.45  4342.2  421.09  4385.2  420.97
    4486  424.67  4835.3  425.52  4953.9  426.72  4960.1  424.73  4965.7  417.35
  4968.6  416.85  4994.9  417.35  4997.7  426.34  5233.5  424.02  5421.5  425.11
  5689.5  425.61  5705.7  427.56    5730  425.51  6216.4  427.41  6514.7  433.78
  6637.6  442.82    6827  440.46  6910.1  445.47  7016.8  449.04  7321.2  451.13
#Mann= 6 ,-1 , 0
  3142.9     .05       0  4835.3     .12       0  4965.7     .07       0
  4994.9     .12       0  5421.5     .05       0  6910.1     .12       0
Bank Sta=4965.7,4994.9
XS Rating Curve= 0 ,0
Exp/Cntr=0.3,0.1

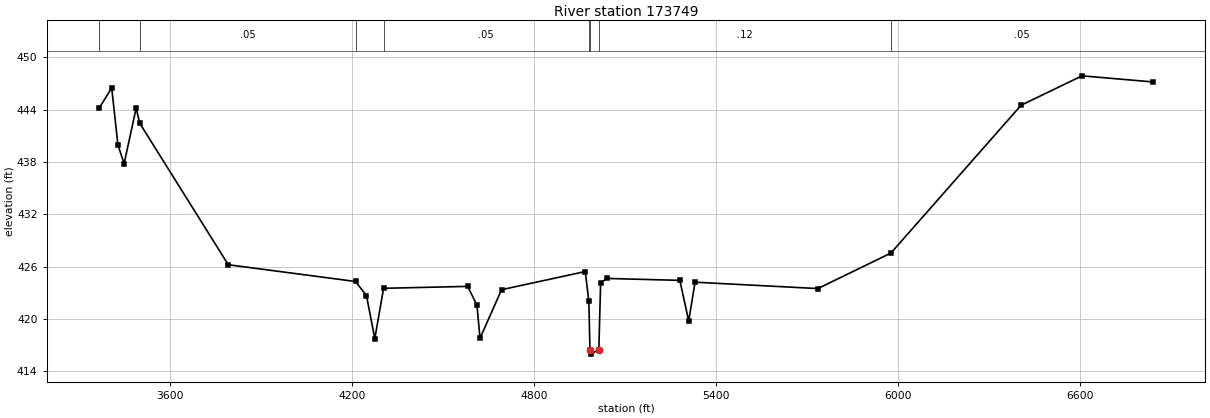
Type RM Length L Ch R = 1 ,173749  ,1749,1749,1749
BEGIN DESCRIPTION:
Kings Creek 343.0
END DESCRIPTION:
XS GIS Cut Line= 3
      2654576.03      6932961.01      2652976.41        6932636.
      2651143.88      6932460.66
#Sta/Elev= 30
  3367.7  444.19  3408.5  446.47    3429  439.94  3449.4   437.8  3489.2  444.18
  3500.5  442.45  3792.9  426.22  4212.3   424.3  4248.5  422.68  4275.9  417.76
  4304.9  423.52    4582  423.74  4612.7  421.59  4622.9   417.8  4693.9  423.36
  4969.8  425.44  4981.6  422.05  4985.3  416.48  4988.2  415.98  5014.6  416.48
  5020.5  424.13  5040.6  424.65  5281.7  424.43  5310.9  419.78  5331.9  424.22
  5736.8  423.49  5977.7  427.56  6406.8  444.49  6607.7  447.86  6840.9  447.16
#Mann= 8 ,-1 , 0
  3367.7     .12       0  3500.5     .05       0  4212.3     .12       0
  4304.9     .05       0  4981.6     .12       0  4985.3     .07       0
  5014.6     .12       0  5977.7     .05       0
Bank Sta=4985.3,5014.6
XS Rating Curve= 0 ,0
Exp/Cntr=0.3,0.1