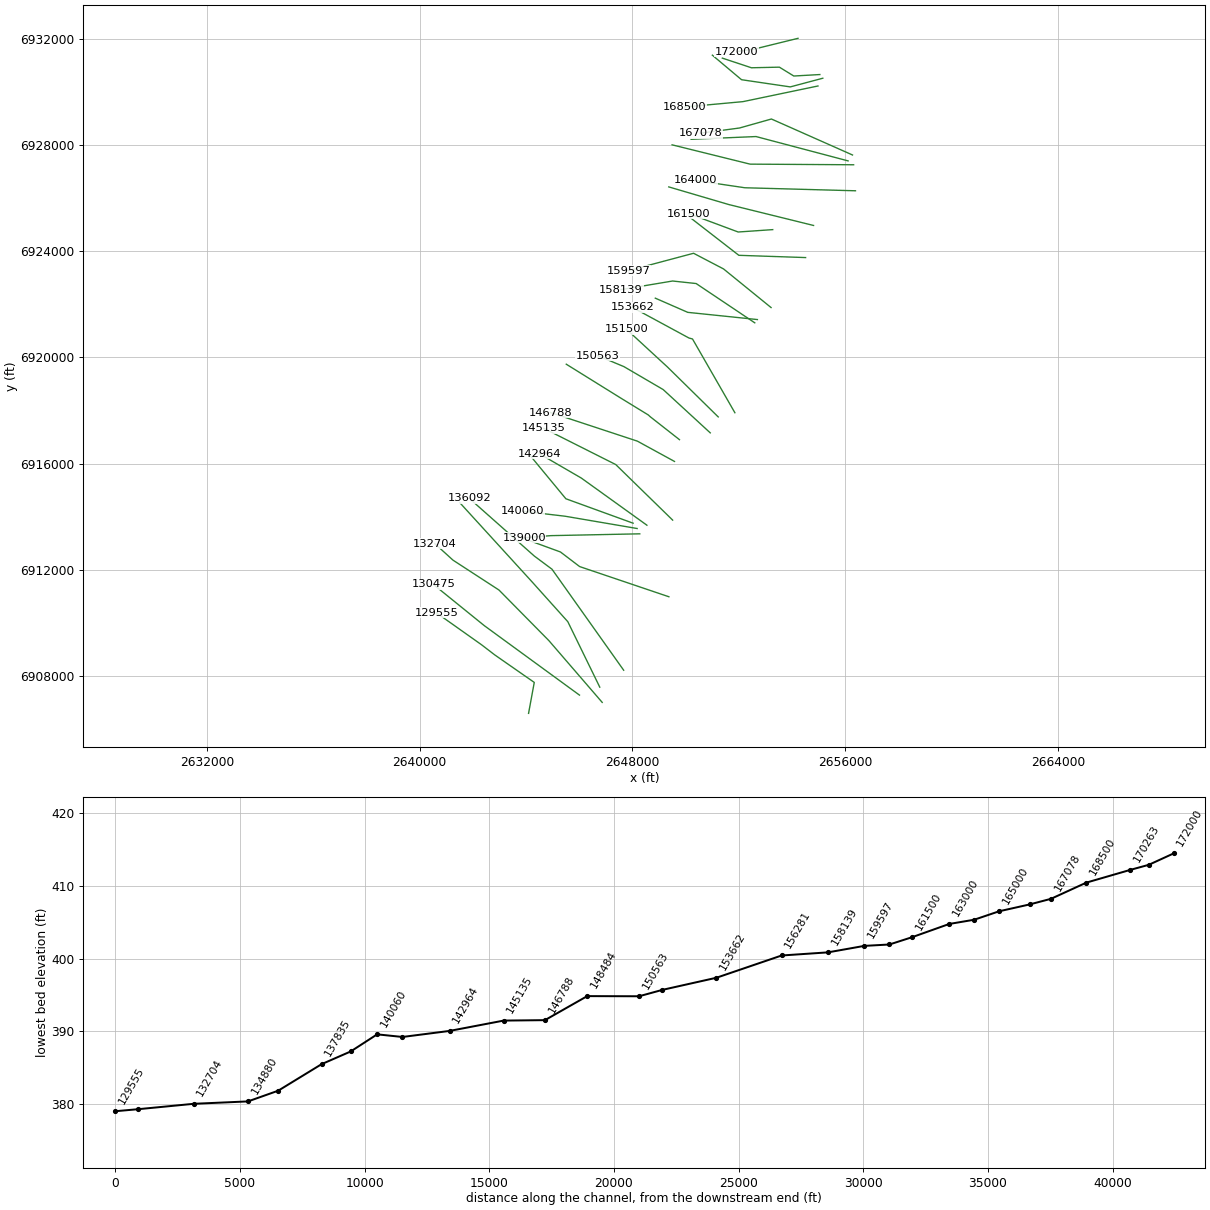
HEC-RAS study Kings Creek.prj: Kings Creek Base Level Engineering

--- Kings Creek.g01 (geometry) --- (continued)

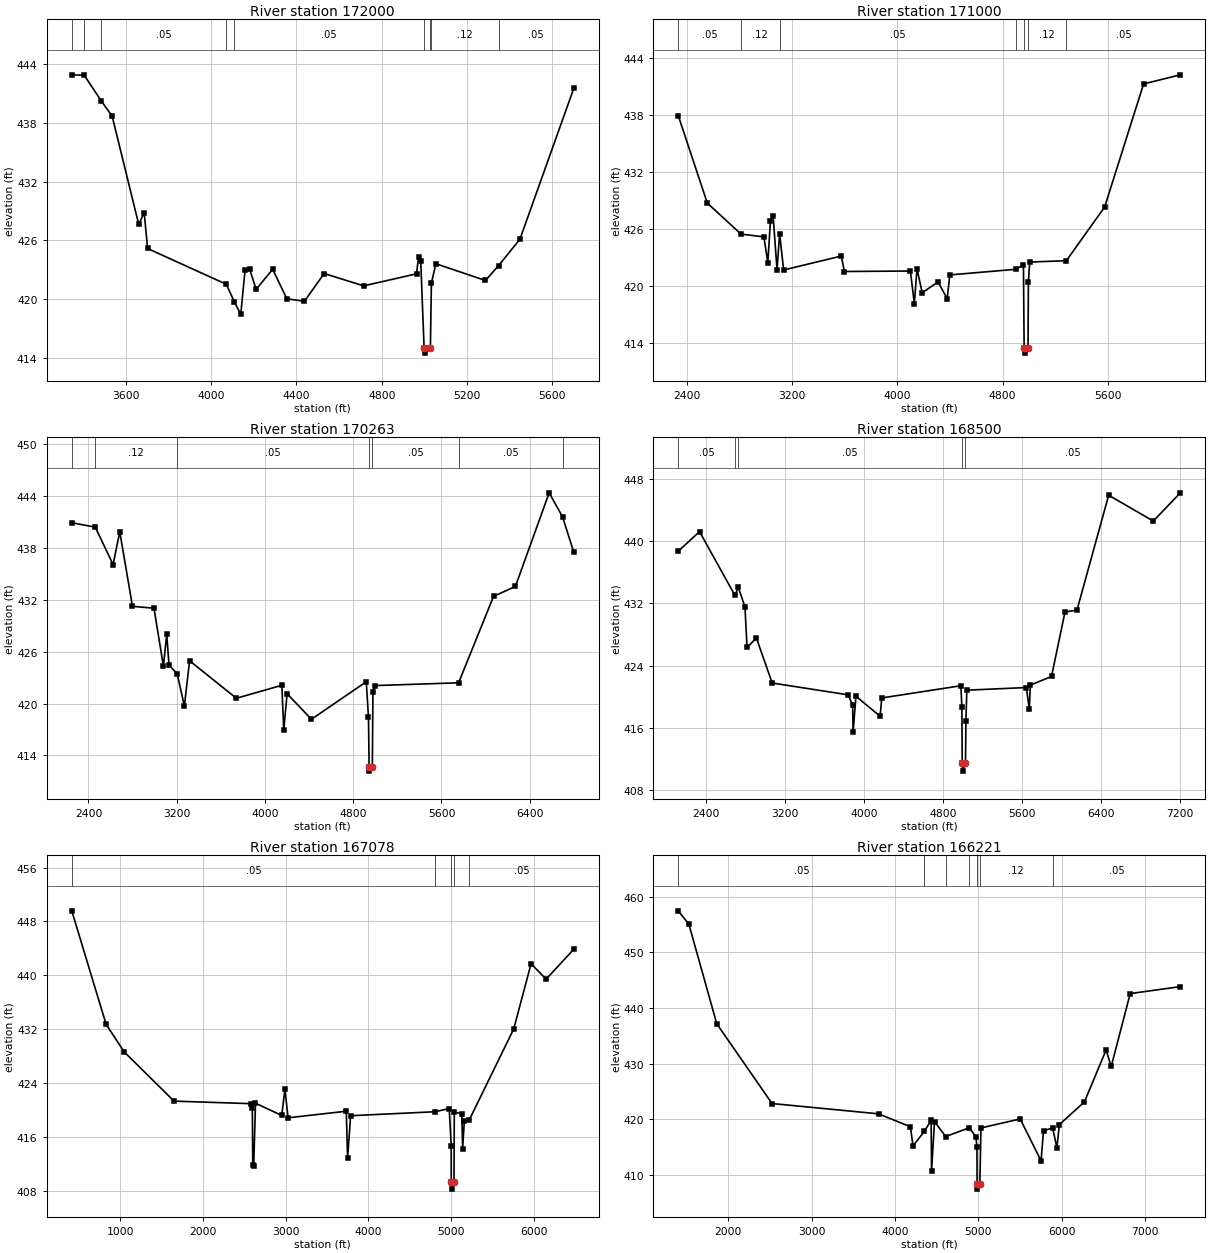
Type RM Length L Ch R = 1 ,172000  ,1000,1000,1000
BEGIN DESCRIPTION:
Kings Creek 339.0
END DESCRIPTION:
XS GIS Cut Line= 3
      2654225.99        6932011.      2652619.38      6931616.22
      2651926.02        6931511.
#Sta/Elev= 30
  3345.6  442.91    3404  442.87  3484.7  440.22  3535.1  438.68  3659.8  427.61
  3685.4  428.83  3701.3  425.15  4070.6  421.49  4108.6  419.69  4138.5  418.42
  4158.4   422.9  4179.7  423.07  4210.6  420.97  4288.2  423.02  4354.7  420.01
  4437.1  419.75  4529.8  422.59  4715.2  421.33  4963.2  422.56  4972.6  424.25
  4982.9  423.88  4998.8  414.95  5001.7  414.45  5028.2  414.95    5033  421.62
    5054  423.59  5286.6  421.88  5348.3   423.4  5448.5  426.11  5701.3  441.55
#Mann= 9 ,-1 , 0
  3345.6     .05       0    3404     .12       0  3484.7     .05       0
  4070.6     .12       0  4108.6     .05       0  4998.8     .03       0
  5028.2     .05       0    5033     .12       0  5348.3     .05       0
Bank Sta=4998.8,5028.2
XS Rating Curve= 0 ,0
Exp/Cntr=0.3,0.1

Type RM Length L Ch R = 1 ,171000  ,737,737,737
BEGIN DESCRIPTION:
Kings Creek 337.0
END DESCRIPTION:
XS GIS Cut Line= 5
       2655046.6      6930648.15      2654067.48       6930592.6
      2653525.82      6930925.93      2652475.27      6930903.22
      2651380.81      6931265.94
#Sta/Elev= 30
  2332.5  437.97  2553.5  428.73    2810  425.45  2984.1  425.16  3014.2  422.45
  3034.2  426.86  3054.3  427.38  3084.3  421.68    3104  425.51  3134.4  421.66
  3573.4  423.13  3596.7   421.5  4099.1  421.55  4129.1   418.1  4149.1  421.79
  4189.1  419.25  4309.1   420.4  4379.1  418.64  4399.1  421.14    4899  421.73
  4959.3  422.18  4964.6  413.38  4967.4  412.88    4994  413.38  4997.1  420.35
  5006.7   422.5  5285.9  422.64  5577.2  428.31  5873.6  441.31    6153  442.27
#Mann= 7 ,-1 , 0
  2332.5     .05       0    2810     .12       0    3104     .05       0
    4899     .12       0  4964.6     .07       0    4994     .12       0
  5285.9     .05       0
Bank Sta=4964.6,4994
XS Rating Curve= 0 ,0
Exp/Cntr=0.3,0.1

Type RM Length L Ch R = 1 ,170263  ,1763,1763,1763
BEGIN DESCRIPTION:
Kings Creek 336.0
END DESCRIPTION:
XS GIS Cut Line= 4
      2655157.77      6930509.27      2653935.54      6930182.88
       2652102.2      6930453.71      2651005.75      6931376.68
#Sta/Elev= 30
  2248.8  440.93  2461.8  440.42  2623.2  436.09    2684  439.88  2799.1  431.26
  2994.3  431.04  3079.6  424.34  3109.4  428.02  3130.4  424.47    3205  423.43
  3269.7  419.71  3316.7  424.96  3740.7  420.62  4153.2  422.12  4170.4  416.94
  4200.8  421.15  4421.4  418.19  4918.5  422.53  4938.7  418.41  4944.2  412.69
  4947.1  412.19  4973.6  412.69  4979.1  421.39  4999.3  422.09  5755.7  422.41
    6072   432.4  6270.9  433.57  6576.5  444.39  6697.7  441.62  6800.3  437.49
#Mann= 7 ,-1 , 0
  2248.8     .05       0  2461.8     .12       0    3205     .05       0
  4944.2     .07       0  4973.6     .05       0  5755.7     .05       0
  6697.7     .12       0
Bank Sta=4944.2,4973.6
XS Rating Curve= 0 ,0
Exp/Cntr=0.3,0.1

Type RM Length L Ch R = 1 ,168500  ,1422,1422,1422
BEGIN DESCRIPTION:
Kings Creek 334.0
END DESCRIPTION:
XS GIS Cut Line= 3
      2654977.18       6930217.6      2652158.35      6929628.63
      2649963.69      6929425.97
#Sta/Elev= 30
  2120.3  438.72    2336  441.24  2694.4  433.04  2728.5  434.07  2795.8  431.57
    2817  426.35  2911.8  427.56  3071.6  421.77  3841.2  420.25    3886  418.92
  3891.1  415.46  3919.5  420.08  4164.7  417.49  4180.8  419.85    4982  421.42
  4992.2   418.7  4995.9  411.44  4999.4  410.44  5028.9  411.44  5033.1  416.94
  5042.5  420.85  5645.1  421.19  5675.2  418.43  5685.7  421.51  5899.9  422.61
  6036.7  430.93  6157.3  431.13  6478.6  445.92  6930.5   442.6    7204  446.23
#Mann= 5 ,-1 , 0
  2120.3     .05       0  2694.4     .12       0  2728.5     .05       0
  4995.9     .03       0  5028.9     .05       0
Bank Sta=4995.9,5028.9
XS Rating Curve= 0 ,0
Exp/Cntr=0.3,0.1

Type RM Length L Ch R = 1 ,167078  ,857,857,857
BEGIN DESCRIPTION:
Kings Creek 331.0
END DESCRIPTION:
XS GIS Cut Line= 4
      2656275.84      6927620.37        2653226.      6928974.55
      2652025.67      6928635.74      2650553.55      6928439.82
#Sta/Elev= 30
   415.8  449.57   831.4  432.68  1050.7  428.59    1652  421.29    2582  420.91
  2598.3  420.34  2603.9  411.83  2614.9  411.58  2636.7  420.98    2954  419.16
  2992.4  423.05  3030.6  418.81    3734  419.79    3750  412.78  3786.7  419.12
  4805.3  419.71  4978.9  420.18  5002.4  414.67  5003.3  409.21  5006.8  408.21
  5036.3  409.21    5040  419.67  5130.8  419.42  5140.9  414.24  5161.1  418.34
  5220.4  418.48  5758.7  432.03  5968.1  441.71  6149.7  439.41  6485.1  443.87
#Mann= 5 ,-1 , 0
   415.8     .05       0  4805.3     .12       0  5003.3     .07       0
  5036.3     .12       0  5220.4     .05       0
Bank Sta=5003.3,5036.3
XS Rating Curve= 0 ,0
Exp/Cntr=0.3,0.1

Type RM Length L Ch R = 1 ,166221  ,1221,1221,1221
BEGIN DESCRIPTION:
Kings Creek 329.0
END DESCRIPTION:
XS GIS Cut Line= 3
      2656109.17      6927398.15      2652647.61      6928314.34
      2650206.37      6928210.66
#Sta/Elev= 30
  1398.1  457.48  1525.5  455.09  1860.2  437.18  2523.4  422.83  3801.3  420.98
    4184  418.65    4215  415.19  4352.5  417.86  4432.3  419.82  4437.8  410.69
  4472.9  419.59  4607.1   416.9  4890.5  418.47  4970.2  416.82  4982.2  414.96
  4983.9  408.44  4987.4  407.44  5017.1  408.44  5030.5  418.44  5500.9  420.06
  5751.2  412.54  5781.2  417.94  5890.4  418.45  5941.3  414.87  5971.4  419.05
  6271.6  423.12  6531.9  432.46  6593.1  429.49  6821.1   442.6  7422.3  443.85
#Mann= 7 ,-1 , 0
  1398.1     .05       0  4352.5     .12       0  4607.1     .05       0
  4890.5     .12       0  4983.9     .07       0  5017.1     .12       0
  5890.4     .05       0
Bank Sta=4983.9,5017.1
XS Rating Curve= 0 ,0
Exp/Cntr=0.3,0.1

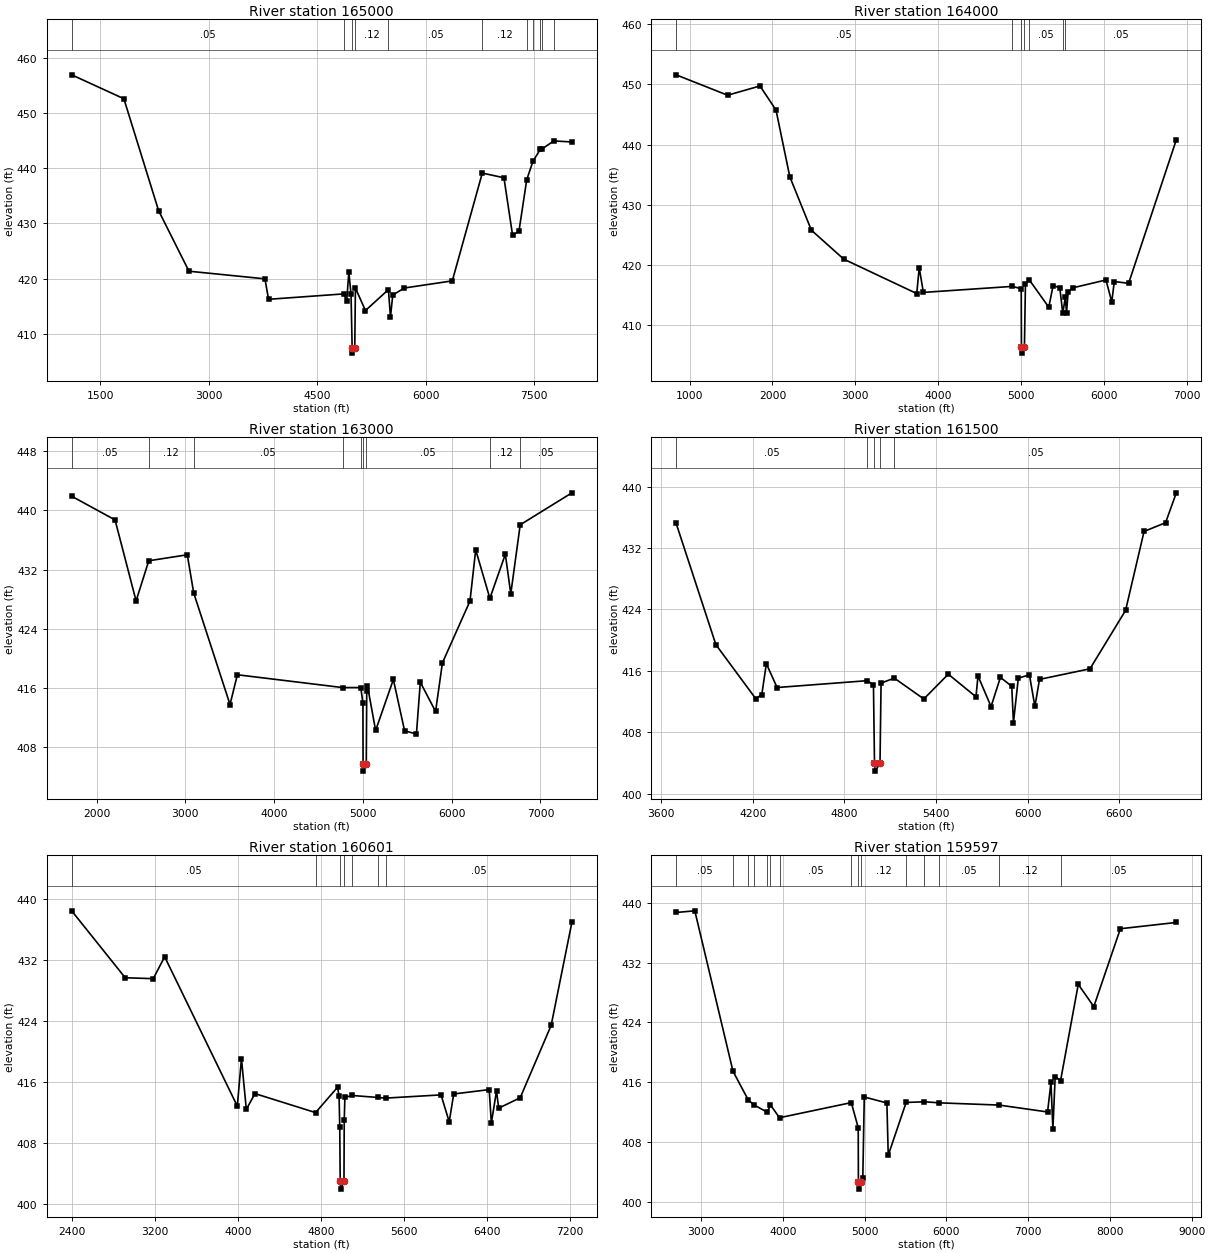
Type RM Length L Ch R = 1 ,165000  ,1000,1000,1000
BEGIN DESCRIPTION:
Kings Creek 327.0
END DESCRIPTION:
XS GIS Cut Line= 3
      2656317.51      6927252.32      2652425.57      6927275.54
      2649491.14      6928002.31
#Sta/Elev= 30
    1108  456.92  1829.5  452.59  2309.5  432.32  2729.5  421.34  3779.6  419.96
  3829.6  416.25  4869.2  417.23  4909.6   415.9  4939.6  421.19  4969.6  417.21
  4985.3   407.5  4989.4   406.5  5021.4   407.5  5030.5   418.3  5168.9  414.21
  5486.9  418.01  5514.7  413.03  5546.7  417.03  5707.2   418.3  6369.6  419.59
  6784.4  439.12  7083.7  438.27  7202.8  427.88  7290.7  428.55  7398.7  437.91
  7485.2  441.27  7587.8  443.45  7614.7  443.54  7773.4  444.94  8023.1  444.76
#Mann= 11 ,-1 , 0
    1108     .05       0  4869.2     .12       0  4985.3     .07       0
  5021.4     .12       0  5486.9     .05       0  6784.4     .12       0
  7398.7     .05       0  7485.2     .12       0  7587.8     .05       0
  7614.7     .12       0  7773.4     .05       0
Bank Sta=4985.3,5021.4
XS Rating Curve= 0 ,0
Exp/Cntr=0.3,0.1

Type RM Length L Ch R = 1 ,164000  ,1000,1000,1000
BEGIN DESCRIPTION:
Kings Creek 325.0
END DESCRIPTION:
XS GIS Cut Line= 3
      2656386.94      6926273.16      2652226.19      6926386.77
        2650376.        6926661.
#Sta/Elev= 30
   837.7  451.59  1458.9   448.2    1849  449.74  2042.5  445.74  2209.1  434.64
  2469.2  425.77  2859.4  420.96  3739.7  415.24  3769.7  419.53  3819.7  415.43
  4891.5  416.43    5000  416.05  5002.4  406.34  5006.5  405.34  5038.5  406.34
  5050.7  416.79  5096.9  417.52  5332.2  412.97  5384.3  416.57  5465.2  416.19
    5501  411.96  5531.3  414.61  5546.1  412.07  5566.3  415.58    5627  416.21
    6022   417.5    6092  413.85  6122.3  417.24  6294.9  416.94  6870.4  440.79
#Mann= 7 ,-1 , 0
   837.7     .05       0  4891.5     .12       0  5002.4     .07       0
  5038.5     .12       0  5096.9     .05       0    5501     .12       0
  5531.3     .05       0
Bank Sta=5002.4,5038.5
XS Rating Curve= 0 ,0
Exp/Cntr=0.3,0.1

Type RM Length L Ch R = 1 ,163000  ,1500,1500,1500
BEGIN DESCRIPTION:
Kings Creek 323.0
END DESCRIPTION:
XS GIS Cut Line= 3
      2654810.56       6924967.6      2651625.03       6925754.6
      2649366.11      6926418.98
#Sta/Elev= 30
  1718.7   441.9  2207.4   438.7  2444.4  427.76  2587.2  433.18  3021.3  433.99
  3093.4  428.84  3502.6  413.76  3585.5  417.78  4770.4  416.05  4975.6  416.05
    5000  413.98  5001.8  405.76  5005.9  404.76  5037.9  405.76  5043.1  415.63
  5051.1  416.32  5143.2  410.25    5343  417.14  5469.5  410.21  5602.9  409.77
  5646.7  416.77  5818.7  412.82  5895.8  419.39  6206.4  427.74  6270.7  434.65
  6430.5  428.11  6604.6  434.06  6666.1  428.72  6772.1  438.04  7354.6  442.36
#Mann= 9 ,-1 , 0
  1718.7     .05       0  2587.2     .12       0  3093.4     .05       0
  4770.4     .12       0  4975.6     .05       0  5001.8     .04       0
  5037.9     .05       0  6430.5     .12       0  6772.1     .05       0
Bank Sta=5001.8,5037.9
XS Rating Curve= 0 ,0
Exp/Cntr=0.3,0.1

Type RM Length L Ch R = 1 ,161500  ,899,899,899
BEGIN DESCRIPTION:
Kings Creek 320.0
END DESCRIPTION:
XS GIS Cut Line= 3
      2653276.03        6924811.      2651976.33      6924721.15
      2650126.04      6925410.98
#Sta/Elev= 30
  3697.2  435.22  3957.9   419.4  4218.5  412.38  4258.6  412.89  4288.6  416.92
  4358.8  413.82  4948.4  414.71  4990.3  414.18  4997.1  403.93  5001.2  402.93
  5033.2  403.93  5040.1   414.4    5127  415.04  5320.5  412.33  5480.6  415.56
    5662  412.61  5675.2  415.33  5760.8  411.34  5822.1  415.14  5896.4  413.98
  5907.5  409.25  5939.5  415.05  6012.3  415.47    6048  411.35  6078.3  414.88
  6409.1  416.26  6642.1  423.86  6763.3  434.15  6904.3  435.29  6974.7  439.18
#Mann= 5 ,-1 , 0
  3697.2     .05       0  4948.4     .12       0  4997.1     .07       0
  5033.2     .12       0    5127     .05       0
Bank Sta=4997.1,5033.2
XS Rating Curve= 0 ,0
Exp/Cntr=0.3,0.1

Type RM Length L Ch R = 1 ,160601  ,1004,1004,1004
BEGIN DESCRIPTION:
Kings Creek 318.0
END DESCRIPTION:
XS GIS Cut Line= 3
      2654511.96      6923759.27      2652001.57       6923843.8
        2650176.        6925261.
#Sta/Elev= 30
  2394.9  438.41  2911.1  429.64  3181.3  429.52  3291.4  432.39  3991.8  412.82
  4031.8  419.02  4078.8  412.39  4161.9  414.46  4746.2  411.97  4958.6  415.29
  4973.1  414.08  4979.5  410.07    4984  402.94  4988.1  401.94  5020.2  402.94
  5022.9  411.02  5029.2  413.98  5101.2  414.21  5348.1  413.95  5424.5  413.87
  5956.1  414.29  6034.8  410.76  6078.3  414.41  6420.3  414.98  6441.2  410.61
    6491  414.79  6511.8  412.55  6719.1  413.91  7017.8   423.4  7217.8  436.91
#Mann= 7 ,-1 , 0
  2394.9     .05       0  4746.2     .12       0    4984     .07       0
  5020.2     .12       0  5101.2     .05       0  5348.1     .12       0
  5424.5     .05       0
Bank Sta=4984,5020.2
XS Rating Curve= 0 ,0
Exp/Cntr=0.3,0.1

Type RM Length L Ch R = 1 ,159597  ,1458,1458,1458
BEGIN DESCRIPTION:
Kings Creek 316.0
END DESCRIPTION:
XS GIS Cut Line= 4
      2653213.33      6921877.31      2651426.41      6923330.94
      2650298.09      6923920.85      2647845.27      6923266.21
#Sta/Elev= 30
  2696.5  438.68  2925.1   438.9  3391.9  417.49  3578.9  413.65  3649.4  412.99
  3810.2  412.02  3849.9  412.98  3960.8  411.28  4838.5   413.3  4922.8  409.95
  4925.3  402.75  4929.5  401.75  4961.8  402.75  4978.8  403.17    4997  414.05
  5273.4  413.25  5289.9  406.27  5508.8  413.32  5732.5  413.41  5910.4  413.27
  6645.5  412.97  7237.9  412.05  7279.3     416  7302.8  409.79  7331.1  416.78
  7396.6  416.22  7613.1  429.08  7803.2  426.12    8128  436.51  8811.9  437.35
#Mann= 15 ,-1 , 0
  2696.5     .05       0  3391.9     .12       0  3578.9     .05       0
  3649.4     .12       0  3810.2     .05       0  3849.9     .12       0
  3960.8     .05       0  4838.5     .12       0  4925.3     .07       0
  4961.8     .12       0  5508.8     .05       0  5732.5     .12       0
  5910.4     .05       0  6645.5     .12       0  7396.6     .05       0
Bank Sta=4925.3,4961.8
XS Rating Curve= 0 ,0
Exp/Cntr=0.3,0.1

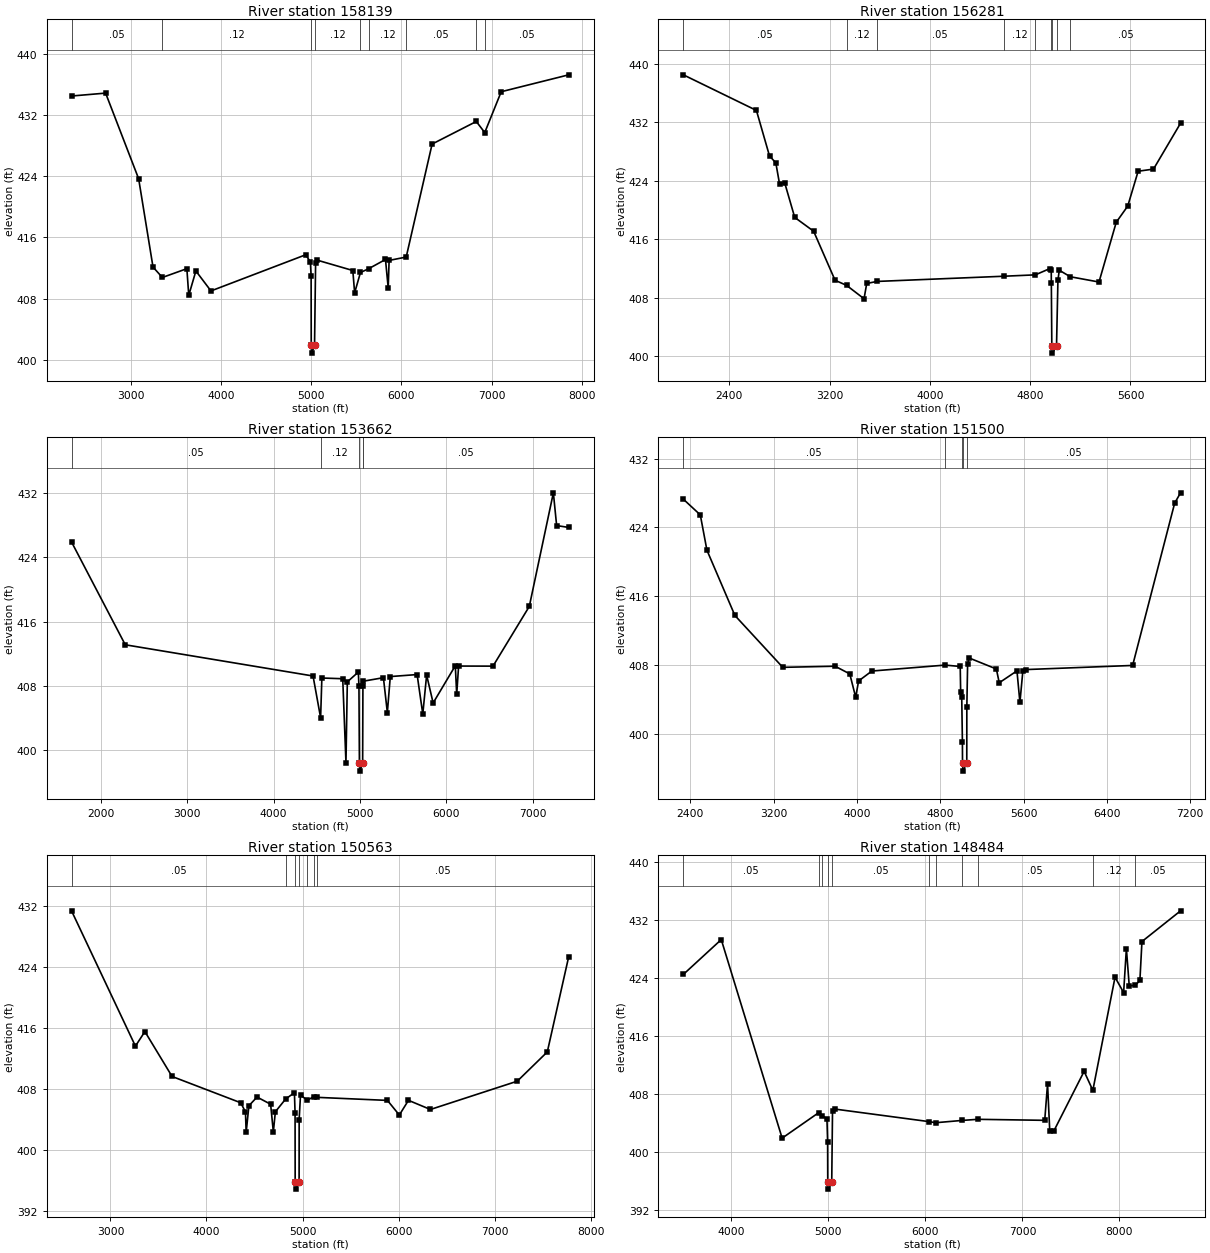
Type RM Length L Ch R = 1 ,158139  ,1858,1858,1858
BEGIN DESCRIPTION:
Kings Creek 314.0
END DESCRIPTION:
XS GIS Cut Line= 4
      2652600.44      6921302.69       2650395.4      6922781.66
      2649510.45      6922876.66      2647572.68      6922552.67
#Sta/Elev= 30
  2344.9  434.47  2722.7  434.85  3088.8  423.65  3247.9  412.11  3351.6  410.75
    3623   411.9    3644  408.41  3722.9   411.6  3890.1  408.99  4940.5  413.72
  4991.6  412.77    5000  410.94  5001.2  401.86  5005.4  400.86  5037.9  401.86
  5049.7  412.62  5059.7  413.04    5462  411.66  5482.2  408.74  5546.7   411.4
  5636.8  411.89  5824.1   413.1  5854.3  409.38  5864.3  412.98  6053.7  413.42
  6340.7  428.19  6830.3  431.14  6924.1  429.69  7106.5  435.03  7854.7  437.24
#Mann= 9 ,-1 , 0
  2344.9     .05       0  3351.6     .12       0  5001.2     .07       0
  5037.9     .12       0  5546.7     .05       0  5636.8     .12       0
  6053.7     .05       0  6830.3     .12       0  6924.1     .05       0
Bank Sta=5001.2,5037.9
XS Rating Curve= 0 ,0
Exp/Cntr=0.3,0.1

Type RM Length L Ch R = 1 ,156281  ,2619,2619,2619
BEGIN DESCRIPTION:
Kings Creek 310.0
END DESCRIPTION:
XS GIS Cut Line= 3
      2652699.38      6921425.94      2650081.37      6921696.77
      2648860.11      6922231.07
#Sta/Elev= 30
  2034.5  438.51  2617.1  433.64  2721.5  427.41  2771.8  426.47    2802  423.54
  2842.2  423.76  2922.6     419  3073.4  417.11  3244.3   410.4  3336.3   409.7
  3475.5  407.87  3496.7  409.96  3578.6  410.24  4587.7  410.95  4841.5  411.14
  4956.1  411.99  4968.2  411.81    4969  410.04  4972.9  401.43  4977.3  400.43
  5010.4  401.43  5021.6  410.41  5032.5  411.77  5120.4  410.88  5349.1  410.16
  5486.7  418.34  5578.3  420.55  5661.3  425.32  5783.7  425.61  5999.5  431.89
#Mann= 9 ,-1 , 0
  2034.5     .05       0  3336.3     .12       0  3578.6     .05       0
  4587.7     .12       0  4841.5     .05       0    4969     .12       0
  4972.9     .07       0  5010.4     .12       0  5120.4     .05       0
Bank Sta=4972.9,5010.4
XS Rating Curve= 0 ,0
Exp/Cntr=0.3,0.1

Type RM Length L Ch R = 1 ,153662  ,2162,2162,2162
BEGIN DESCRIPTION:
Kings Creek 307.0
END DESCRIPTION:
XS GIS Cut Line= 4
      2651852.22      6917918.97      2650259.19      6920694.67
      2650125.19      6920731.41      2647999.51      6921883.47
#Sta/Elev= 30
  1660.7  425.92  2282.9  413.11  4457.3  409.22  4544.9  404.02  4559.4  408.97
    4801  408.88  4838.4  398.43  4854.2  408.49  4981.6  409.71  4988.8  407.99
  4994.1  398.37  4998.6  397.37  5031.6  398.37  5034.8  407.97  5037.3  408.57
  5272.1  409.01  5317.6  404.67  5351.7  409.15  5662.3   409.4    5728  404.48
  5772.5  409.34  5847.8  405.86  6104.5   410.5  6120.7  406.92  6142.6  410.46
    6541  410.45  6961.3  417.89  7239.9  432.04  7277.9  427.96  7417.8  427.73
#Mann= 5 ,-1 , 0
  1660.7     .05       0  4544.9     .12       0  4994.1     .07       0
  5031.6     .12       0  5037.3     .05       0
Bank Sta=4994.1,5031.6
XS Rating Curve= 0 ,0
Exp/Cntr=0.3,0.1

Type RM Length L Ch R = 1 ,151500  ,937,937,937
BEGIN DESCRIPTION:
Kings Creek 301.0
END DESCRIPTION:
XS GIS Cut Line= 3
      2651226.02      6917760.98      2649325.55      6919631.97
        2647776.        6921061.
#Sta/Elev= 30
  2333.1  427.28  2495.8  425.46  2559.4  421.36  2828.1  413.78  3287.7  407.76
  3789.8  407.89  3931.3     407  3987.9  404.29  4016.1  406.18  4143.4  407.33
  4846.9  408.02  4991.9  407.86  4996.2  404.87  5006.4  404.35    5013  399.05
  5013.9  396.71  5018.8  395.71  5054.9  396.71  5055.4   403.1  5062.8  408.09
    5077  408.85  5338.9  407.57  5366.7  405.97  5536.8  407.35  5565.2  403.69
  5593.6  407.35  5621.9   407.5  6647.7  407.98  7051.5  426.83  7107.9  428.02
#Mann= 5 ,-1 , 0
  2333.1     .05       0  4846.9     .12       0  5006.4     .05       0
  5013.9     .07       0  5054.9     .05       0
Bank Sta=5013.9,5054.9
XS Rating Curve= 0 ,0
Exp/Cntr=0.3,0.1

Type RM Length L Ch R = 1 ,150563  ,2079,2079,2079
BEGIN DESCRIPTION:
Kings Creek 298.0
END DESCRIPTION:
XS GIS Cut Line= 4
      2650925.97      6917161.03      2649156.39      6918790.75
      2647678.75      6919654.83      2646700.19       6920064.5
#Sta/Elev= 30
  2594.3  431.34  3259.8  413.59  3358.4   415.5  3641.4  409.61  4356.5  406.16
  4405.8  404.96  4413.2  402.27  4441.6  405.77  4526.1  406.91  4667.9  405.97
  4696.2  402.33  4717.2  404.98  4824.1  406.65  4915.7  407.48  4922.5  404.83
  4923.5  395.83  4928.4  394.83  4964.5  395.83    4965  403.96  4979.2  407.19
  5049.3  406.48  5116.7  406.96  5151.5  406.87  5884.3  406.47  6008.3  404.55
  6103.4  406.48  6332.3  405.28  7236.6  408.99  7549.5  412.83  7772.6  425.34
#Mann= 7 ,-1 , 0
  2594.3     .05       0  4824.1     .12       0  4923.5     .07       0
  4964.5     .12       0  5049.3     .05       0  5116.7     .12       0
  5151.5     .05       0
Bank Sta=4923.5,4964.5
XS Rating Curve= 0 ,0
Exp/Cntr=0.3,0.1

Type RM Length L Ch R = 1 ,148484  ,1696,1696,1696
BEGIN DESCRIPTION:
Mapping XS e9ae88f1
END DESCRIPTION:
XS GIS Cut Line= 5
      2649768.86      6916905.11      2648671.65      6917766.21
      2648595.26      6917835.66      2647588.32      6918453.71
      2645511.89       6919745.4
#Sta/Elev= 30
  3504.9   424.5  3895.7  429.31    4523  401.89    4898  405.39  4939.1  405.01
  4985.1  404.49  4991.8  401.42  4993.2  395.85  4998.1  394.85  5034.3  395.85
  5042.4  405.66  5063.7  405.91  6038.5  404.17  6105.2  404.02  6372.9  404.33
  6539.1  404.49  7229.7  404.35  7258.8  409.38  7281.6  402.88  7324.1  402.89
  7635.7  411.11  7725.7  408.49  7954.5  424.11    8043  421.99  8071.4  428.07
  8100.9  422.92  8164.2     423  8210.7  423.67  8231.9  429.04  8629.8  433.28
#Mann= 11 ,-1 , 0
  3504.9     .05       0    4898     .12       0  4939.1     .05       0
  4993.2     .04       0  5034.3     .05       0  6038.5     .12       0
  6105.2     .05       0  6372.9     .12       0  6539.1     .05       0
  7725.7     .12       0  8164.2     .05       0
Bank Sta=4993.2,5034.3
XS Rating Curve= 0 ,0
Exp/Cntr=0.3,0.1

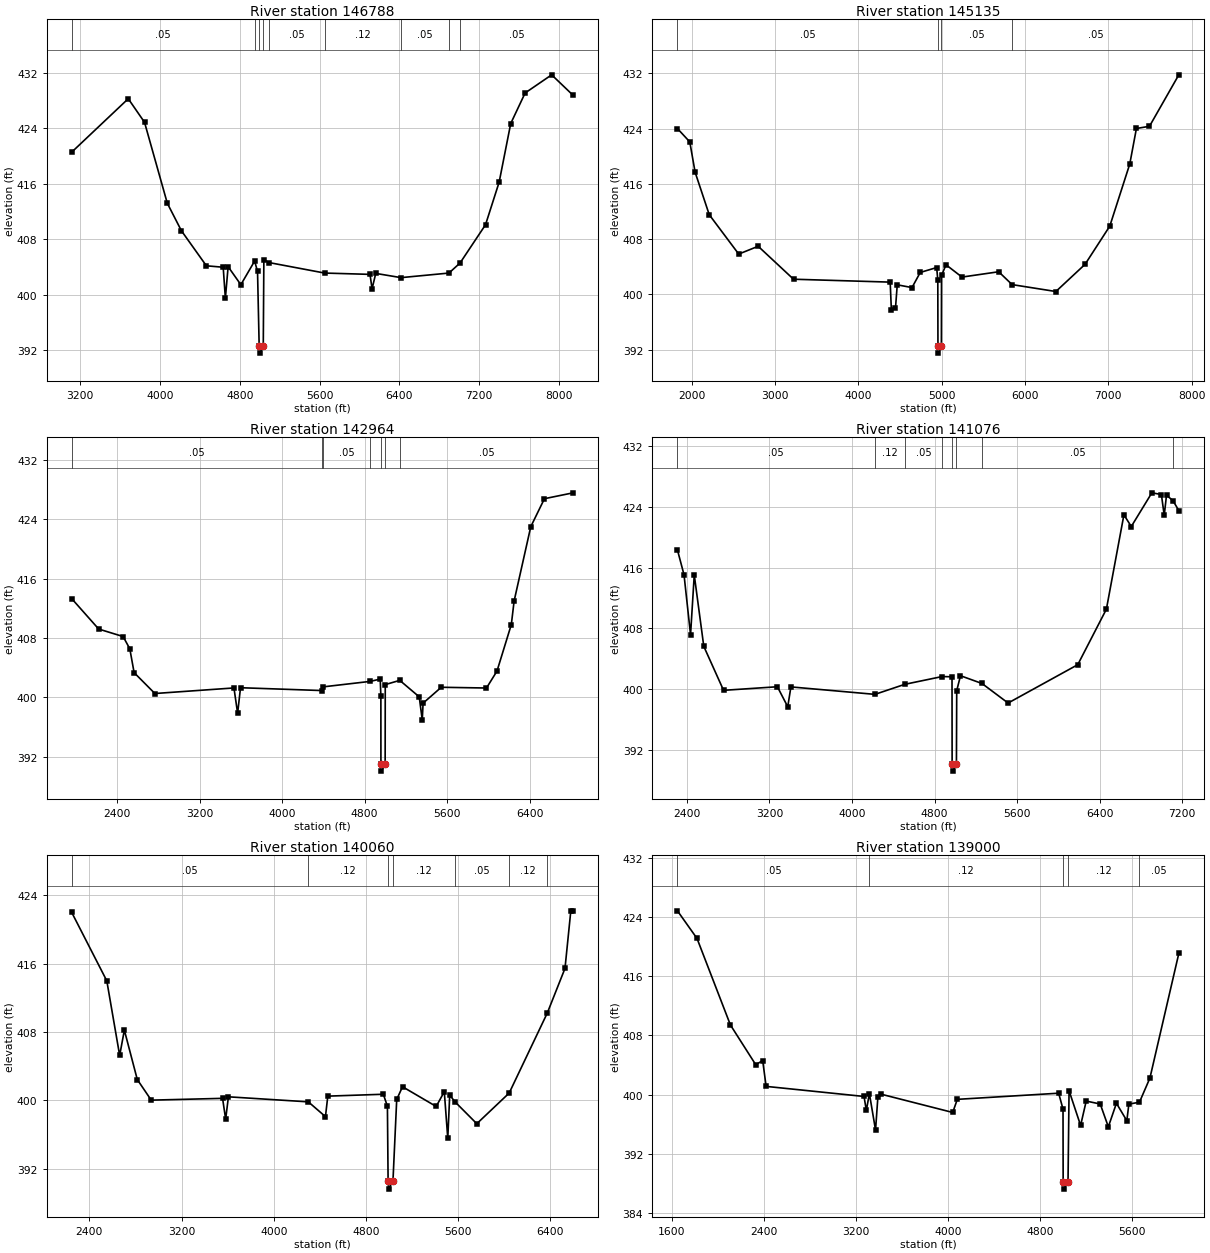
Type RM Length L Ch R = 1 ,146788  ,1653,1653,1653
BEGIN DESCRIPTION:
Kings Creek 292.0
END DESCRIPTION:
XS GIS Cut Line= 3
      2649581.37      6916085.66      2648185.54      6916849.54
      2644921.63      6917925.94
#Sta/Elev= 30
  3115.2  420.57    3682  428.28  3845.1  424.88  4073.6  413.19  4214.9  409.22
  4465.3  404.16  4634.1  403.95  4655.9  399.47  4683.5  404.03  4811.2  401.43
  4949.2  404.84  4978.4  403.34  4994.9  392.55  4999.8  391.55    5036  392.55
  5041.9  405.04  5091.4  404.63  5651.6  403.11  6106.4  402.92    6127  400.84
    6164  403.06  6417.7  402.45    6898  403.11  7009.3  404.56  7264.6  410.08
  7401.5  416.24  7517.3  424.69    7662  429.11    7928  431.73  8143.2  428.77
#Mann= 9 ,-1 , 0
  3115.2     .05       0  4949.2     .12       0  4994.9     .07       0
    5036     .12       0  5091.4     .05       0  5651.6     .12       0
  6417.7     .05       0    6898     .12       0  7009.3     .05       0
Bank Sta=4994.9,5036
XS Rating Curve= 0 ,0
Exp/Cntr=0.3,0.1

Type RM Length L Ch R = 1 ,145135  ,2171,2171,2171
BEGIN DESCRIPTION:
Kings Creek 290.0
END DESCRIPTION:
XS GIS Cut Line= 3
      2649511.94      6913877.31      2647373.04       6915967.6
      2644671.66      6917328.71
#Sta/Elev= 30
  1830.6     424  1978.8  422.07  2042.5  417.69  2212.2  411.53  2565.9  405.83
  2799.2  406.96  3223.4  402.19  4383.2  401.77  4397.4   397.7  4446.8  398.01
  4467.9  401.38  4644.8  400.98  4743.9  403.17  4941.1  403.88  4954.5  402.03
  4956.3  392.49  4961.2  391.49  4997.4  392.49  4999.1  402.73  5053.1  404.28
  5244.5   402.5  5685.1  403.27  5845.9  401.41  6371.1  400.41  6721.6  404.35
  7018.1  409.88  7257.9  418.88  7337.4  424.01  7494.2  424.33  7846.2  431.78
#Mann= 4 ,-1 , 0
  1830.6     .05       0  4956.3     .07       0  4997.4     .05       0
  5845.9     .05       0
Bank Sta=4956.3,4997.4
XS Rating Curve= 0 ,0
Exp/Cntr=0.3,0.1

Type RM Length L Ch R = 1 ,142964  ,1888,1888,1888
BEGIN DESCRIPTION:
Kings Creek 287.0
END DESCRIPTION:
XS GIS Cut Line= 3
      2648544.93       6913684.6      2646076.35      6915460.66
      2644500.63      6916375.82
#Sta/Elev= 30
  1958.9  413.29  2220.3   409.2  2457.2  408.19  2522.2  406.54    2564  403.33
  2765.3  400.52  3532.4  401.27    3568  397.86    3596   401.3    4383  400.92
  4400.5  401.42  4852.8  402.15  4951.2  402.46  4957.5  400.17  4957.9  391.07
  4962.8  390.07    4999  391.07    5000  401.72  5140.8  402.29  5329.6  400.07
  5358.9  396.95  5366.9  399.22  5543.2  401.36  5981.9  401.26  6083.8  403.54
  6222.8  409.81  6250.1  412.99  6411.2  422.97    6544  426.75  6822.2  427.54
#Mann= 7 ,-1 , 0
  1958.9     .05       0    4383     .12       0  4400.5     .05       0
  4852.8     .12       0  4957.9     .07       0    4999     .12       0
  5140.8     .05       0
Bank Sta=4957.9,4999
XS Rating Curve= 0 ,0
Exp/Cntr=0.3,0.1

Type RM Length L Ch R = 1 ,141076  ,1016,1016,1016
BEGIN DESCRIPTION:
Kings Creek 280.0
END DESCRIPTION:
XS GIS Cut Line= 3
      2648025.97      6913761.01      2645496.51       6914680.8
      2644117.85      6916351.26
#Sta/Elev= 30
  2308.5  418.31  2372.3  415.05  2435.5  407.17  2471.4  415.03  2563.8  405.64
  2755.4  399.86  3276.8  400.33  3377.2   397.7  3407.8  400.31  4221.9  399.33
  4511.1  400.65  4872.4  401.67  4968.6  401.64  4969.7  390.24  4974.5  389.24
  5011.4  390.24  5014.2  399.82  5050.7  401.78  5258.9  400.76  5511.9  398.19
  6186.8  403.23  6464.3  410.53    6634  422.93  6705.3  421.39  6904.7  425.82
    6997   425.6  7024.5  422.86  7046.7  425.51  7109.7  424.78  7165.9  423.49
#Mann= 8 ,-1 , 0
  2308.5     .05       0  4221.9     .12       0  4511.1     .05       0
  4872.4     .12       0  4969.7     .07       0  5011.4     .12       0
  5258.9     .05       0  7109.7     .12       0
Bank Sta=4969.7,5011.4
XS Rating Curve= 0 ,0
Exp/Cntr=0.3,0.1

Type RM Length L Ch R = 1 ,140060  ,1060,1060,1060
BEGIN DESCRIPTION:
Kings Creek 278.0
END DESCRIPTION:
XS GIS Cut Line= 3
      2648175.99        6913561.      2645462.64      6914024.21
        2643876.        6914211.
#Sta/Elev= 30
  2247.4     422  2551.7  413.99  2663.3  405.25  2703.9  408.22  2816.2  402.43
  2937.2  400.02  3556.1  400.23  3582.9  397.79  3606.8  400.41  4300.2  399.82
  4448.8  398.09  4469.1  400.49  4951.1  400.71  4986.4   399.3  4992.3   390.6
  4997.1   389.6  5034.7   390.6  5067.1   400.1  5117.4  401.59  5409.5  399.28
  5479.9  401.01  5510.1  395.54  5526.9  400.61  5573.8  399.81  5761.9  397.26
  6042.8  400.85  6373.8  410.23  6527.1  415.45  6577.5  422.17  6597.6  422.19
#Mann= 7 ,-1 , 0
  2247.4     .05       0  4300.2     .12       0  4992.3     .07       0
  5034.7     .12       0  5573.8     .05       0  6042.8     .12       0
  6373.8     .05       0
Bank Sta=4992.3,5034.7
XS Rating Curve= 0 ,0
Exp/Cntr=0.3,0.1

Type RM Length L Ch R = 1 ,139000  ,1165,1165,1165
BEGIN DESCRIPTION:
Kings Creek 276.0
END DESCRIPTION:
XS GIS Cut Line= 3
      2648276.04        6913361.      2644925.54      6913292.42
      2643925.95        6913211.
#Sta/Elev= 30
  1648.8  424.82  1818.9  421.09  2108.9  409.41    2329  404.04    2389  404.61
    2419  401.12  3269.2  399.76  3289.2  397.87  3315.8  400.15  3369.2  395.22
  3389.2  399.62  3419.2  400.06  4039.3   397.6  4079.3  399.37  4959.5   400.2
  4997.3  398.04  4998.4  388.25  5003.2  387.25  5040.8  388.25  5049.7  400.54
    5150  395.85  5198.7  399.14  5320.5  398.74  5390.8  395.66  5461.1  398.84
  5551.4  396.49  5569.1  398.73    5661  398.98    5752  402.25  6002.9  419.07
#Mann= 5 ,-1 , 0
  1648.8     .05       0  3315.8     .12       0  4998.4     .07       0
  5040.8     .12       0    5661     .05       0
Bank Sta=4998.4,5040.8
XS Rating Curve= 0 ,0
Exp/Cntr=0.3,0.1

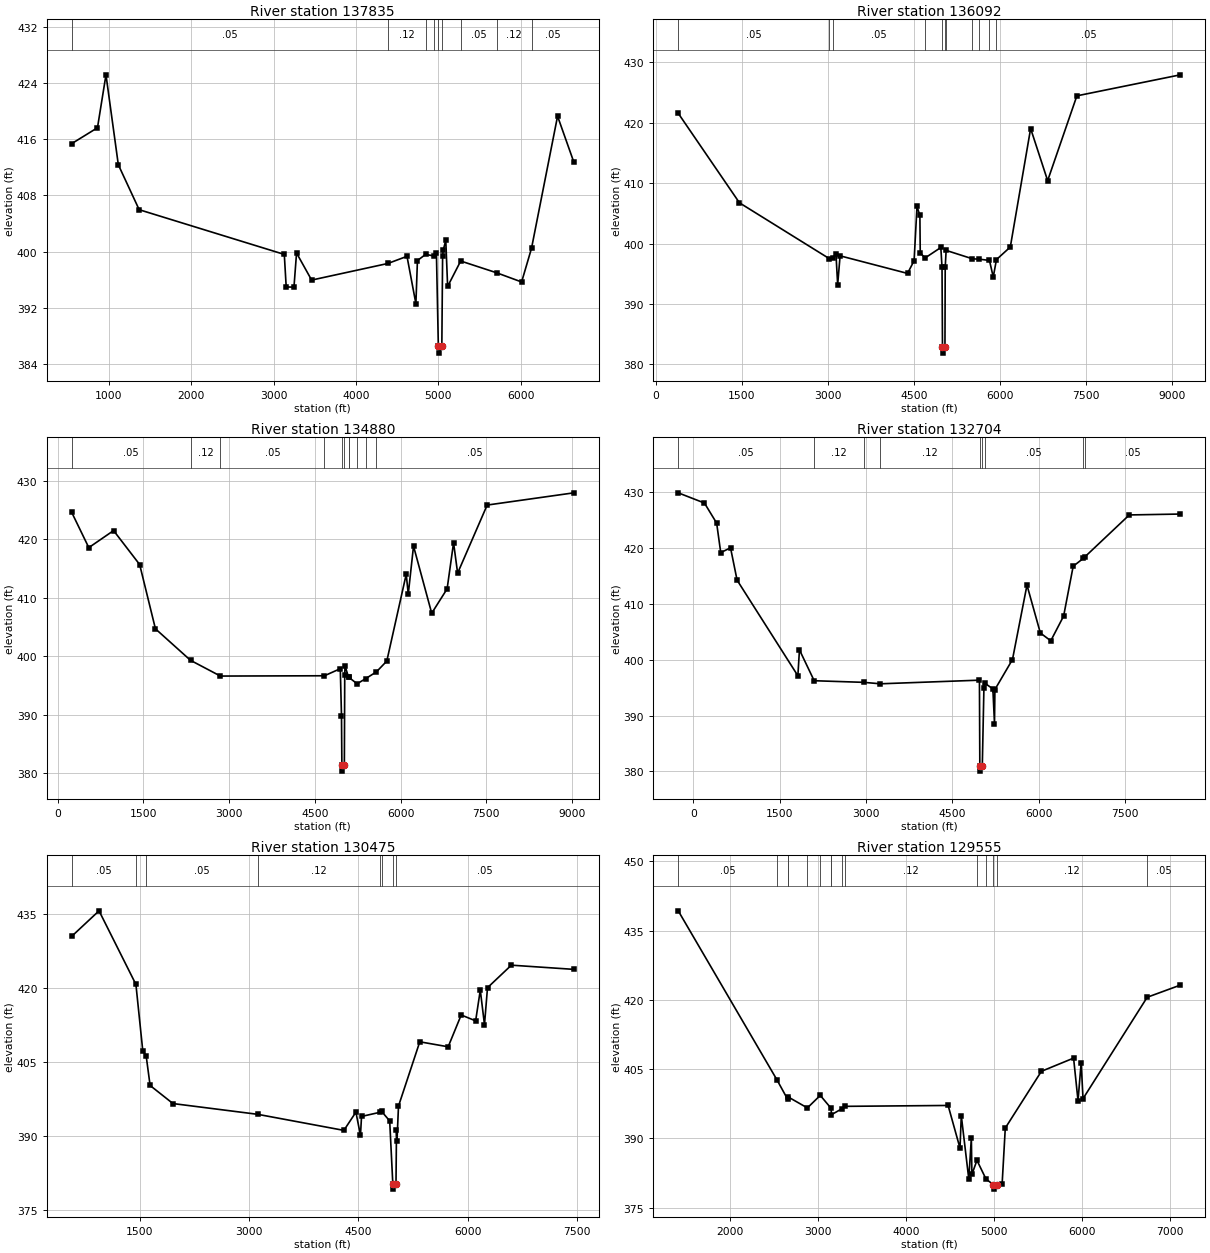
Type RM Length L Ch R = 1 ,137835  ,1743,1743,1743
BEGIN DESCRIPTION:
Kings Creek 273.0
END DESCRIPTION:
XS GIS Cut Line= 5
      2649371.77      6910991.75      2646014.53      6912128.19
      2645493.08      6912525.33      2645292.47      6912678.12
      2643744.54      6913243.65
#Sta/Elev= 30
     548   415.4   860.3  417.66   963.6  425.21  1113.6  412.38  1366.9  405.97
  3130.1  399.59  3153.2  394.95  3247.5  394.92  3278.9  399.79  3462.2  395.93
  4388.9   398.3  4620.8  399.32  4728.9  392.57  4747.8  398.72  4846.8  399.59
  4951.5  399.37  4978.4   399.8  5001.7  386.51  5006.5  385.51  5044.1  386.51
  5053.5  399.31  5060.1  400.17  5092.1  401.59  5114.5  395.02  5273.1  398.65
  5710.4  396.97  6013.4  395.66  6133.8  400.47  6450.2  419.31    6648  412.75
#Mann= 9 ,-1 , 0
     548     .05       0  4388.9     .12       0  4846.8      .1       0
  4951.5     .12       0  5001.7     .07       0  5044.1     .12       0
  5273.1     .05       0  5710.4     .12       0  6133.8     .05       0
Bank Sta=5001.7,5044.1
XS Rating Curve= 0 ,0
Exp/Cntr=0.3,0.1

Type RM Length L Ch R = 1 ,136092  ,1212,1212,1212
BEGIN DESCRIPTION:
Mapping XS 8f3346d7
END DESCRIPTION:
XS GIS Cut Line= 4
      2647670.35      6908227.01      2644975.03      6912029.09
      2644310.97      6912523.88       2641864.4      6914697.16
#Sta/Elev= 30
     388  421.57  1456.1  406.75  3026.5  397.49  3092.1  397.68  3140.5  398.25
    3170  393.19  3212.2  397.97  4388.9  395.06  4503.8  397.16  4554.2  406.14
  4604.7  404.66  4610.8   398.5  4692.6   397.6  4970.1  399.35    4991  396.06
    4999  382.86  5003.7  381.86  5042.1  382.86  5046.6  396.07  5062.8  398.87
  5521.5  397.48  5644.7  397.41  5818.8  397.21  5884.9  394.46    5941  397.35
  6182.6  399.43  6537.2  419.05  6834.1  410.42  7344.2  424.46  9149.1  427.94
#Mann= 11 ,-1 , 0
     388     .05       0  3026.5     .12       0  3092.1     .05       0
  4692.6     .12       0    4999     .07       0  5042.1     .12       0
  5062.8     .05       0  5521.5     .12       0  5644.7     .05       0
  5818.8     .12       0    5941     .05       0
Bank Sta=4999,5042.1
XS Rating Curve= 0 ,0
Exp/Cntr=0.3,0.1

Type RM Length L Ch R = 1 ,134880  ,2176,2176,2176
BEGIN DESCRIPTION:
Mapping XS fd719dfa
END DESCRIPTION:
XS GIS Cut Line= 4
      2646771.93      6907588.95      2645569.45      6910054.46
       2644206.8      6911573.36      2641511.49      6914529.09
#Sta/Elev= 30
   246.9  424.57   544.8  418.57   978.5  421.48  1434.7  415.68  1710.6   404.7
  2324.1  399.32    2847  396.63  4667.7  396.68  4944.7  397.89  4965.7  389.84
  4972.5  381.39  4977.2  380.39  5015.7  381.39  5022.5  396.85  5027.4  398.37
  5088.3  396.46  5088.9  396.45  5239.2  395.31  5390.2   396.2  5575.9  397.34
  5758.3  399.19  6098.1  414.02  6133.9  410.62  6225.8  418.83    6544  407.36
  6813.6  411.53  6926.4   419.4  6997.4  414.21  7514.2  425.84  9030.7  427.93
#Mann= 11 ,-1 , 0
   246.9     .05       0  2324.1     .12       0    2847     .05       0
  4667.7     .12       0  4972.5     .07       0  5015.7     .12       0
  5088.3     .05       0  5088.9     .12       0  5239.2     .05       0
  5390.2     .12       0  5575.9     .05       0
Bank Sta=4972.5,5015.7
XS Rating Curve= 0 ,0
Exp/Cntr=0.3,0.1

Type RM Length L Ch R = 1 ,132704  ,2229,2229,2229
BEGIN DESCRIPTION:
Mapping XS a83db078
END DESCRIPTION:
XS GIS Cut Line= 5
      2646863.07      6907016.05      2644858.89      6909340.51
       2642982.7       6911244.3      2641253.53       6912369.3
      2640571.24       6912989.1
#Sta/Elev= 30
  -263.7   429.9   191.8  428.07   403.8  424.48   475.1  419.19   645.1  420.06
   759.2  414.26  1815.7  397.14  1843.2  401.78  2099.1  396.25    2960  395.96
  3250.8   395.7  4971.6  396.35  4978.3  381.06    4983  380.06  5021.5  381.06
  5049.5  394.95  5067.3  395.79  5205.1  394.79  5233.4  388.58  5240.4  394.67
    5546  400.05  5797.9  413.37  6030.4   404.8  6211.6   403.4  6434.9  407.83
    6601  416.75  6778.3  418.17    6798  418.37  7576.4  425.94  8463.1   426.1
#Mann= 9 ,-1 , 0
  -263.7     .05       0  2099.1     .12       0    2960     .05       0
  3250.8     .12       0  4978.3     .07       0  5021.5     .12       0
  5067.3     .05       0  6778.3    .075       0    6798     .05       0
Bank Sta=4978.3,5021.5
XS Rating Curve= 0 ,0
Exp/Cntr=0.3,0.1

Type RM Length L Ch R = 1 ,130475  ,920,920,920
BEGIN DESCRIPTION:
Mapping XS 35a9e3b0
END DESCRIPTION:
XS GIS Cut Line= 3
      2646008.38      6907290.18      2642431.97      6909903.05
      2640514.13      6911456.41
#Sta/Elev= 30
     563   430.5   937.5  435.65  1444.1  420.76  1538.6   407.3  1584.8  406.32
    1639   400.3    1953  396.64  3117.7  394.46    4301  391.21  4466.3   394.9
    4529   390.2  4543.5  394.03  4796.1  394.87  4819.7  395.04  4930.4  393.13
  4973.5  380.32  4978.1  379.32  5016.9  380.32  5023.9  391.23  5030.4  389.03
  5051.4  396.13  5343.7  409.14  5733.8  408.13  5912.8  414.57    6111  413.38
    6175   419.6  6232.5  412.61  6274.1  420.09  6601.8  424.65  7460.2   423.8
#Mann= 8 ,-1 , 0
     563     .05       0  1444.1     .12       0  1584.8     .05       0
  3117.7     .12       0  4796.1      .1       0  4819.7     .12       0
  4973.5     .07       0  5016.9     .05       0
Bank Sta=4973.5,5016.9
XS Rating Curve= 0 ,0
Exp/Cntr=0.3,0.1

Type RM Length L Ch R = 1 ,129555  ,93,93,93
BEGIN DESCRIPTION:
Mapping XS 34ee2b64
END DESCRIPTION:
XS GIS Cut Line= 5
      2644094.16      6906602.68       2644308.3        6907768.
      2642824.33      6908802.35      2642329.54      6909182.56
      2640631.61      6910385.69
#Sta/Elev= 30
  1417.8  439.28  2537.8  402.71  2660.7  398.45    2662  399.03  2883.6  396.62
  3029.8  399.33  3152.5  396.54  3157.1  395.15  3275.3  396.44  3313.8  396.96
    4481  397.15    4616   387.9  4630.5  394.96  4715.7  381.22  4744.7  390.16
    4751  382.22  4808.1  385.27  4911.5  381.21  4993.1  380.04  4997.7  379.04
  5036.5  380.04  5094.2   380.2  5129.9  392.26  5539.6  404.54  5905.1   407.4
  5955.5  398.18  5991.2  406.44  6012.1  398.62  6740.5  420.57  7116.5   423.2
#Mann= 15 ,-1 , 0
  1417.8     .05       0  2537.8     .12       0  2660.7     .05       0
    2662     .12       0  2883.6     .05       0  3029.8     .12       0
  3152.5     .05       0  3157.1     .12       0  3275.3     .05       0
  3313.8     .12       0  4808.1      .1       0  4911.5     .12       0
  4993.1     .07       0  5036.5     .12       0  6740.5     .05       0
Bank Sta=4993.1,5036.5
XS Rating Curve= 0 ,0
Exp/Cntr=0.3,0.1