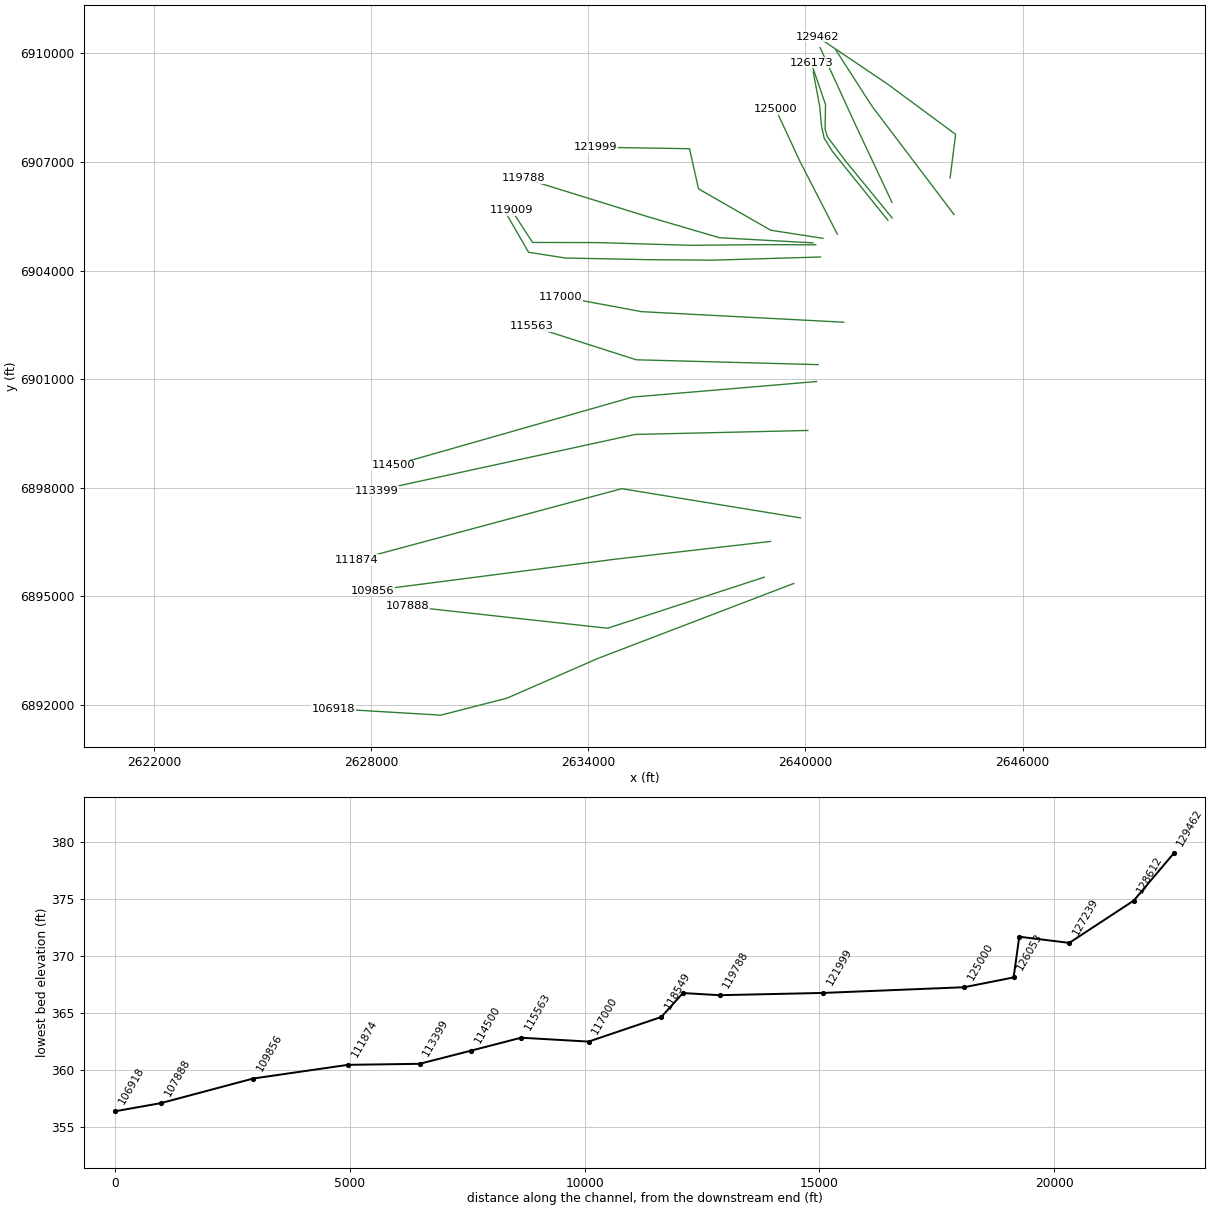
HEC-RAS study Kings Creek.prj: Kings Creek Base Level Engineering

--- Kings Creek.g01 (geometry) --- (continued)

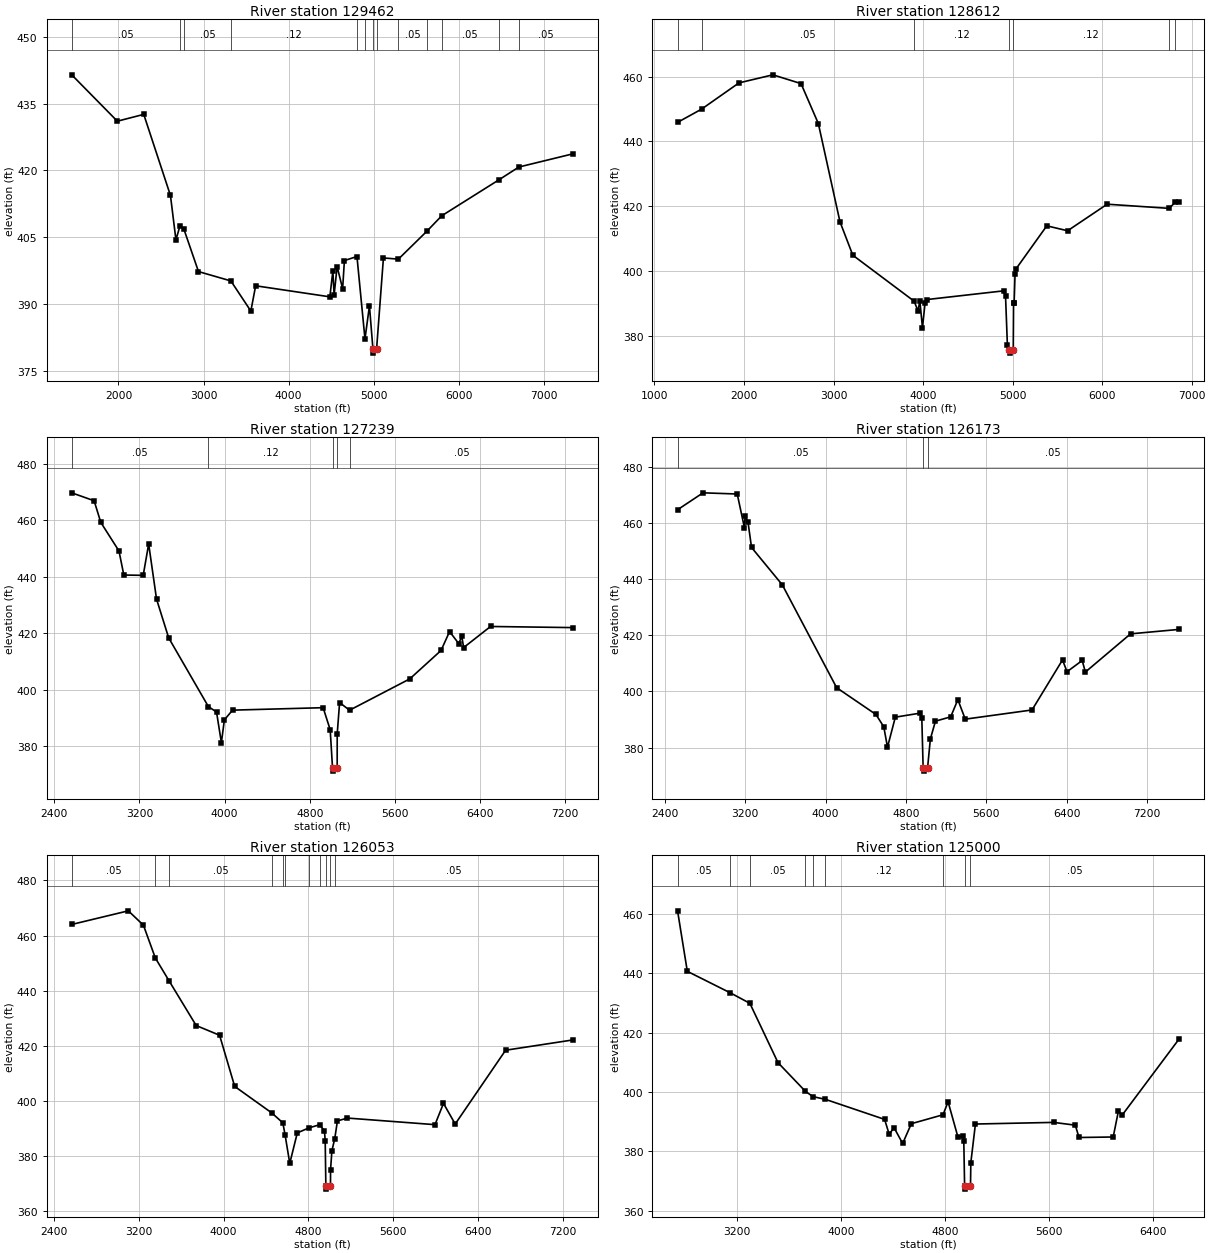
Type RM Length L Ch R = 1 ,129462  ,850,850,850
BEGIN DESCRIPTION:
Mapping XS 7823829e
END DESCRIPTION:
XS GIS Cut Line= 4
      2643994.34      6906559.33      2644146.39      6907761.75
      2642269.97      6909149.36      2640320.05      6910463.19
#Sta/Elev= 30
  1450.5  441.45  1986.6  431.04  2297.3  432.57  2611.3  414.36  2675.6  404.41
  2722.3  407.46  2768.2  406.87  2940.8  397.28  3321.7  395.18  3556.6  388.41
    3613  394.09  4485.6  391.61    4521   397.4  4535.7  392.04  4571.1   398.4
  4635.9  393.42  4656.7  399.75  4804.4  400.66  4898.5  382.16  4951.1  389.58
  4991.9  379.97  4996.5  378.97  5035.4  379.97  5115.6  400.34  5291.4  400.07
    5624  406.29  5801.5  409.81  6471.6  417.85    6708  420.75  7347.5  423.73
#Mann= 13 ,-1 , 0
  1450.5     .05       0  2722.3     .12       0  2768.2     .05       0
  3321.7     .12       0  4804.4      .1       0  4898.5     .12       0
  4991.9     .07       0  5035.4     .12       0  5291.4     .05       0
    5624     .12       0  5801.5     .05       0  6471.6     .12       0
    6708     .05       0
Bank Sta=4991.9,5035.4
XS Rating Curve= 0 ,0
Exp/Cntr=0.3,0.1

Type RM Length L Ch R = 1 ,128612  ,1373,1373,1373
BEGIN DESCRIPTION:
Mapping XS 44f0481d
END DESCRIPTION:
XS GIS Cut Line= 3
      2644103.71      6905546.96      2641835.94      6908541.72
       2640837.7      6910093.33
#Sta/Elev= 30
    1258  445.89  1525.9  449.96  1944.2  458.05  2322.8  460.53    2637  457.83
  2830.4  445.53  3071.8   415.3  3215.4  404.98  3899.7  390.84  3943.6  387.85
  3964.4  390.91  3993.5  382.66  4022.6  390.29  4043.4  391.33  4900.6  394.01
  4921.4  392.35  4942.2  377.24  4964.2  375.83  4968.8  374.83  5007.7  375.83
  5010.9   390.2  5017.1   390.2  5027.6  399.09  5036.8  400.71  5382.3  414.03
  5614.6  412.51  6056.4  420.69  6748.1  419.41  6814.7  421.22  6859.5  421.29
#Mann= 7 ,-1 , 0
    1258    .075       0  1525.9     .05       0  3899.7     .12       0
  4964.2     .07       0  5007.7     .12       0  6748.1     .12       0
  6814.7     .05       0
Bank Sta=4964.2,5007.7
XS Rating Curve= 0 ,0
Exp/Cntr=0.3,0.1

Type RM Length L Ch R = 1 ,127239  ,1066,1066,1066
BEGIN DESCRIPTION:
Mapping XS 02a2d7f6
END DESCRIPTION:
XS GIS Cut Line= 3
      2642389.33      6905883.29      2641358.51      6908075.14
      2640404.22      6910157.22
#Sta/Elev= 30
  2563.7  469.78  2773.9  466.97  2836.8  459.29  3007.5  449.17  3053.1  440.64
  3235.3  440.53  3286.6  451.65  3360.5  432.11  3474.5  418.37  3847.9  393.99
  3924.3  392.08  3969.9  381.22  3998.2  389.32  4075.1  392.74    4926  393.61
  4992.3   385.8  5014.5  372.12  5019.2  371.12    5058  372.12  5058.3  384.34
  5080.8  395.42  5174.3  392.71  5740.3  403.82  6033.9  413.89  6114.3   420.6
  6200.4  416.33  6228.9  418.93  6246.3  414.92  6499.3   422.4  7276.2     422
#Mann= 5 ,-1 , 0
  2563.7     .05       0  3847.9     .12       0  5014.5     .07       0
    5058     .12       0  5174.3     .05       0
Bank Sta=5014.5,5058
XS Rating Curve= 0 ,0
Exp/Cntr=0.3,0.1

Type RM Length L Ch R = 1 ,126173  ,120,120,120
BEGIN DESCRIPTION:
Mapping XS a899679f
END DESCRIPTION:
XS GIS Cut Line= 6
      2642394.03      6905453.34      2641103.42      6907030.07
        2640609.      6907689.35       2640541.3      6907901.59
      2640553.74       6908585.3      2640158.27      6909737.01
#Sta/Elev= 30
  2528.8  464.65    2782  470.67  3122.2  470.25    3194  458.23  3200.4  462.36
  3229.2  460.29  3264.3  451.24  3570.8  437.91  4110.6  401.35  4501.8  391.81
  4579.7  387.41  4616.3  380.17  4694.3  390.86  4943.4   392.3  4957.6  390.62
    4971  372.66  4975.6  371.66  5014.5  372.66  5042.7  383.08  5093.2  389.44
  5244.8  390.97  5316.2  397.08  5389.7  390.15  6053.7  393.42    6357  411.23
  6401.7  407.02  6552.7  411.02    6584   406.9  7033.7   420.5  7515.8  422.08
#Mann= 3 ,-1 , 0
  2528.8     .05       0    4971     .03       0  5014.5     .05       0
Bank Sta=4971,5014.5
XS Rating Curve= 0 ,0
Exp/Cntr=0.3,0.1

Type RM Length L Ch R = 1 ,126053  ,1053,1053,1053
BEGIN DESCRIPTION:
Mapping XS a24e20d4
END DESCRIPTION:
XS GIS Cut Line= 6
      2642275.94      6905390.88      2640749.46      6907284.02
      2640516.12      6907657.67      2640442.62      6908001.97
      2640394.59      6908523.56      2640214.58       6909486.5
#Sta/Elev= 30
  2568.1  464.03  3101.5  468.97  3243.9  463.77  3356.1  451.88  3485.2  443.62
  3741.3  427.39    3962  423.87  4104.4  405.32    4453  395.74  4558.4  392.12
  4579.9  387.64  4623.6  377.43  4694.5  388.47  4805.1  390.31  4905.1  391.42
  4950.5  389.21  4957.6  385.68  4963.9  369.09  4968.6  368.09  5007.4  369.09
  5008.2  375.19  5020.9  382.03  5047.8  386.39  5072.8  392.82  5167.2  393.85
  5992.5  391.46  6072.8  399.16  6183.3  391.69  6658.5  418.44    7296  422.19
#Mann= 11 ,-1 , 0
  2568.1     .05       0  3356.1    .075       0  3485.2     .05       0
    4453     .12       0  4558.4     .05       0  4579.9     .12       0
  4805.1     .05       0  4905.1     .12       0  4963.9     .07       0
  5007.4     .12       0  5047.8     .05       0
Bank Sta=4963.9,5007.4
XS Rating Curve= 0 ,0
Exp/Cntr=0.3,0.1

Type RM Length L Ch R = 1 ,125000  ,3001,3001,3001
BEGIN DESCRIPTION:
Kings Creek 248.0
END DESCRIPTION:
XS GIS Cut Line= 3
      2640881.07      6905004.41      2639848.72      6907011.24
      2639176.01      6908460.97
#Sta/Elev= 30
  2743.2  461.02  2818.1  440.63    3150  433.35    3299  429.85  3515.3  409.85
  3726.2  400.18  3783.8  398.41  3880.1  397.48  4334.9  390.73    4370  385.69
  4407.1  387.96  4473.6  382.61  4540.1  389.28  4783.7  392.29  4822.8  396.65
  4898.5  384.77  4933.7  384.99  4943.5  383.35  4949.7  368.23  4954.2  367.23
    4995  368.23  4997.5  376.14  5032.8  389.17  5634.8  389.72  5800.7  388.78
  5829.1  384.63    6092   384.8  6132.3   393.6  6160.7  392.16  6598.2  417.81
#Mann= 9 ,-1 , 0
  2743.2     .05       0    3150    .075       0    3299     .05       0
  3726.2     .12       0  3783.8     .05       0  3880.1     .12       0
  4783.7     .05       0  4949.7     .04       0    4995     .05       0
Bank Sta=4949.7,4995
XS Rating Curve= 0 ,0
Exp/Cntr=0.3,0.1

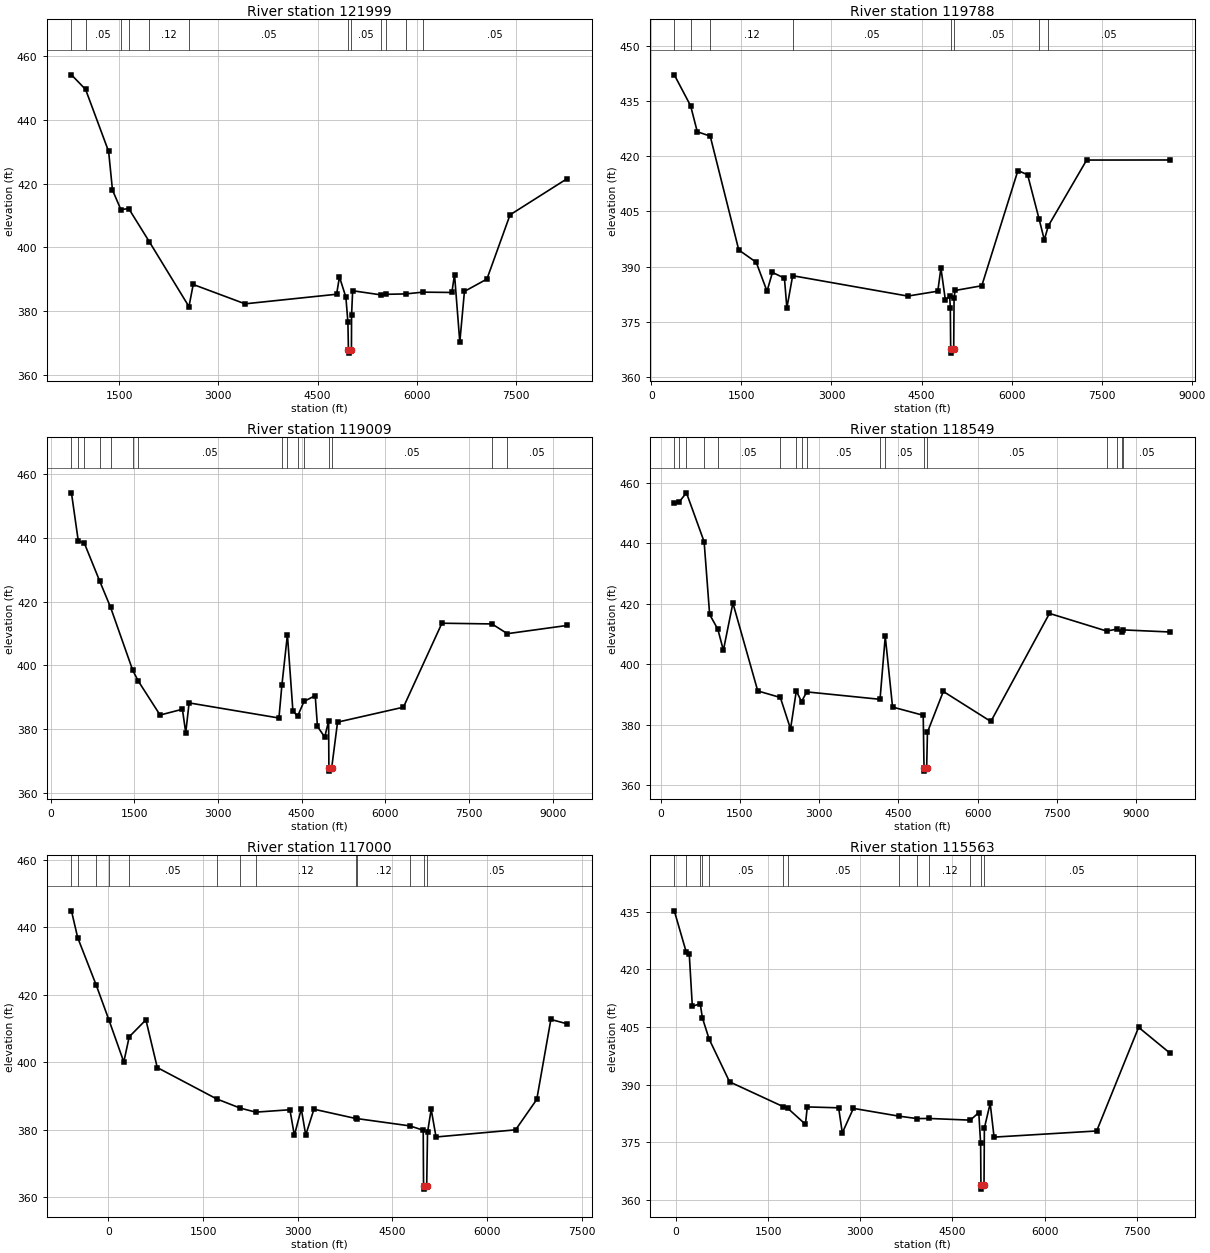
Type RM Length L Ch R = 1 ,121999  ,2211,2211,2211
BEGIN DESCRIPTION:
Kings Creek 245.0
END DESCRIPTION:
XS GIS Cut Line= 5
      2640481.84      6904890.48      2639039.13      6905114.44
      2637046.47      6906256.33      2636796.47      6907365.71
      2634192.34      6907407.37
#Sta/Elev= 30
     777  454.17   991.1  449.57  1339.5  430.08  1397.4  417.98  1524.4  411.83
  1643.1  412.15  1955.7   401.7  2554.5  381.34  2618.7   388.3  3402.8  382.22
  4787.8  385.23    4831  390.68    4928  384.31  4958.7  376.45  4966.8  367.73
  4971.2  366.73  5012.2  367.73  5014.2  378.66  5030.5  386.33  5459.9  385.03
  5534.5  385.21  5831.9  385.33  6091.5  385.89  6531.4  385.79  6571.4  391.43
  6651.4  370.18  6721.4  386.12  7061.5     390  7411.5  410.18  8275.3  421.55
#Mann= 12 ,-1 , 0
     777    .075       0   991.1     .05       0  1524.4     .12       0
  1643.1     .05       0  1955.7     .12       0  2554.5     .05       0
  4966.8     .03       0  5012.2     .05       0  5459.9     .12       0
  5534.5     .05       0  5831.9     .12       0  6091.5     .05       0
Bank Sta=4966.8,5012.2
XS Rating Curve= 0 ,0
Exp/Cntr=0.3,0.1

Type RM Length L Ch R = 1 ,119788  ,779,779,779
BEGIN DESCRIPTION:
Mapping XS 3a199bbd
END DESCRIPTION:
XS GIS Cut Line= 4
      2640208.33      6904765.68      2637625.87      6904906.74
      2635629.34      6905492.67      2632200.87      6906555.93
#Sta/Elev= 30
   381.6  442.09   653.5  433.68   764.5  426.64   979.9  425.45  1455.5  394.54
    1746   391.2  1926.2  383.34  2016.4  388.44  2216.3  386.88  2256.7  378.78
  2353.4  387.55  4270.5  382.02  4770.7  383.35  4822.8  389.67  4895.8  381.03
  4968.8  381.91  4979.2  378.78  4985.4  367.53  4989.4  366.53  5035.4  367.53
  5041.7  381.52  5058.6  383.54  5503.2  384.82  6105.4  416.11  6266.6  414.95
  6459.6  402.83  6544.7  397.28  6611.7  401.08  7249.9  418.95  8638.2  418.97
#Mann= 8 ,-1 , 0
   381.6    .075       0   653.5     .05       0   979.9     .12       0
  2353.4     .05       0  4985.4     .04       0  5035.4     .05       0
  6459.6     .12       0  6611.7     .05       0
Bank Sta=4985.4,5035.4
XS Rating Curve= 0 ,0
Exp/Cntr=0.3,0.1

Type RM Length L Ch R = 1 ,119009  ,460,460,460
BEGIN DESCRIPTION:
Mapping XS 8830f08b
END DESCRIPTION:
XS GIS Cut Line= 6
      2640284.27      6904711.42      2638763.61      6904715.29
      2636815.17      6904697.77      2634244.85      6904773.29
      2632460.94      6904776.53      2631885.94      6905666.14
#Sta/Elev= 30
   374.5  454.17   496.4  439.09   607.8  438.25   878.5  426.53  1076.5  418.15
  1472.5  398.41  1571.6  395.04  1962.8  384.34  2362.8  386.17  2422.8  378.78
  2482.8  388.16  4092.9  383.41  4145.7  393.72  4244.8  409.58    4343  385.67
  4427.2  383.97  4542.1  388.62  4743.1  390.45  4783.2  380.76  4913.2  377.42
  4983.2  382.46  4988.2  367.72  4992.2  366.72  5038.2  367.72  5143.3  382.11
  6323.9  386.81    7014   413.2  7910.6  412.97  8186.3  409.91  9258.3   412.5
#Mann= 15 ,-1 , 0
   374.5     .05       0   496.4    .075       0   607.8     .05       0
   878.5    .075       0  1076.5     .05       0  1472.5    .075       0
  1571.6     .05       0  4145.7    .075       0  4244.8     .05       0
  4427.2    .075       0  4542.1     .05       0  4988.2     .05       0
  5038.2     .05       0  7910.6    .075       0  8186.3     .05       0
Bank Sta=4988.2,5038.2
XS Rating Curve= 0 ,0
Exp/Cntr=0.3,0.1

Type RM Length L Ch R = 1 ,118549  ,1549,1549,1549
BEGIN DESCRIPTION:
Mapping XS 8f32abd5
END DESCRIPTION:
XS GIS Cut Line= 6
      2640414.52      6904375.05      2637445.89      6904287.66
      2635676.45      6904300.81      2633373.33      6904347.08
      2632352.43      6904505.26      2631701.38      6905633.76
#Sta/Elev= 30
   260.6  453.33   345.1  453.48   490.6  456.65     825  440.49   929.4  416.42
  1084.4  411.55  1189.5  404.58  1369.6  420.19  1839.8  391.14  2267.2  388.97
  2460.1  378.57  2569.1  391.14  2668.1   387.6  2767.1  390.82  4153.2  388.37
  4252.2  409.15  4390.4  385.81  4970.5  383.08  4985.5  365.62  4989.5  364.62
  5035.5  365.62  5050.5  377.49  5350.5  390.97  6249.9  381.04  7359.2  416.77
  8441.3  410.94  8642.2   411.6  8734.7  410.53  8758.7  411.32  9639.5  410.63
#Mann= 17 ,-1 , 0
   260.6     .05       0   345.1    .075       0   490.6     .05       0
     825    .075       0  1084.4     .05       0  2267.2    .075       0
  2569.1     .05       0  2668.1    .075       0  2767.1     .05       0
  4153.2    .075       0  4252.2     .05       0  4985.5     .04       0
  5035.5     .05       0  8441.3    .075       0  8642.2     .05       0
  8734.7    .075       0  8758.7     .05       0
Bank Sta=4985.5,5035.5
XS Rating Curve= 0 ,0
Exp/Cntr=0.3,0.1

Type RM Length L Ch R = 1 ,117000  ,1437,1437,1437
BEGIN DESCRIPTION:
Kings Creek 232.0
END DESCRIPTION:
XS GIS Cut Line= 3
      2641054.69      6902573.84      2635476.08      6902864.91
      2633242.16      6903279.14
#Sta/Elev= 30
  -586.2  444.92  -487.8     437  -193.1  422.88    10.4  412.45   243.6  400.14
   329.3  407.59   594.1  412.61   774.3  398.48  1715.7  389.19  2088.2  386.47
  2335.9  385.27  2877.2  385.98  2947.3  378.38  3057.4  386.23  3127.5  378.48
  3257.7  386.14  3917.4   383.4  3937.5  383.37    4781  381.19  4990.1  379.91
  4995.4  363.46  4999.4  362.46  5045.4  363.46  5058.4  379.25  5116.4  386.11
  5193.3  377.91  6454.5  380.03  6790.1  389.03  7013.8  412.74    7272  411.43
#Mann= 13 ,-1 , 0
  -586.2     .05       0  -487.8     .12       0  -193.1     .05       0
    10.4     .12       0   329.3     .05       0  1715.7     .12       0
  2088.2     .05       0  2335.9     .12       0  3917.4     .05       0
  3937.5     .12       0    4781     .05       0  4995.4     .04       0
  5045.4     .05       0
Bank Sta=4995.4,5045.4
XS Rating Curve= 0 ,0
Exp/Cntr=0.3,0.1

Type RM Length L Ch R = 1 ,115563  ,1063,1063,1063
BEGIN DESCRIPTION:
Kings Creek 228.0
END DESCRIPTION:
XS GIS Cut Line= 3
      2640349.41      6901401.96       2635325.8      6901536.08
       2632429.7      6902464.91
#Sta/Elev= 30
   -25.4  435.25   166.9  424.62   218.1  424.02   268.1   410.4   396.3  411.06
   432.3  407.35   541.8  401.86   874.3  390.73  1747.3  384.27  1821.2  383.84
  2108.8  379.68  2138.8   384.2    2649  383.97    2709  377.45    2889  383.82
  3625.5  381.81  3926.6  381.16  4113.9   381.2  4791.6  380.76  4929.8  382.72
  4959.8   374.7  4964.8   363.8  4968.8   362.8  5014.8   363.8  5020.8  378.72
  5115.3  385.13  5178.3  376.34  6848.1  377.94  7530.7  404.92  8041.4   398.2
#Mann= 13 ,-1 , 0
   -25.4     .05       0   166.9    .075       0   396.3     .05       0
   432.3    .075       0   541.8     .05       0  1747.3     .12       0
  1821.2     .05       0  3625.5     .12       0  3926.6     .05       0
  4113.9     .12       0  4791.6     .05       0  4964.8     .03       0
  5014.8     .05       0
Bank Sta=4964.8,5014.8
XS Rating Curve= 0 ,0
Exp/Cntr=0.3,0.1

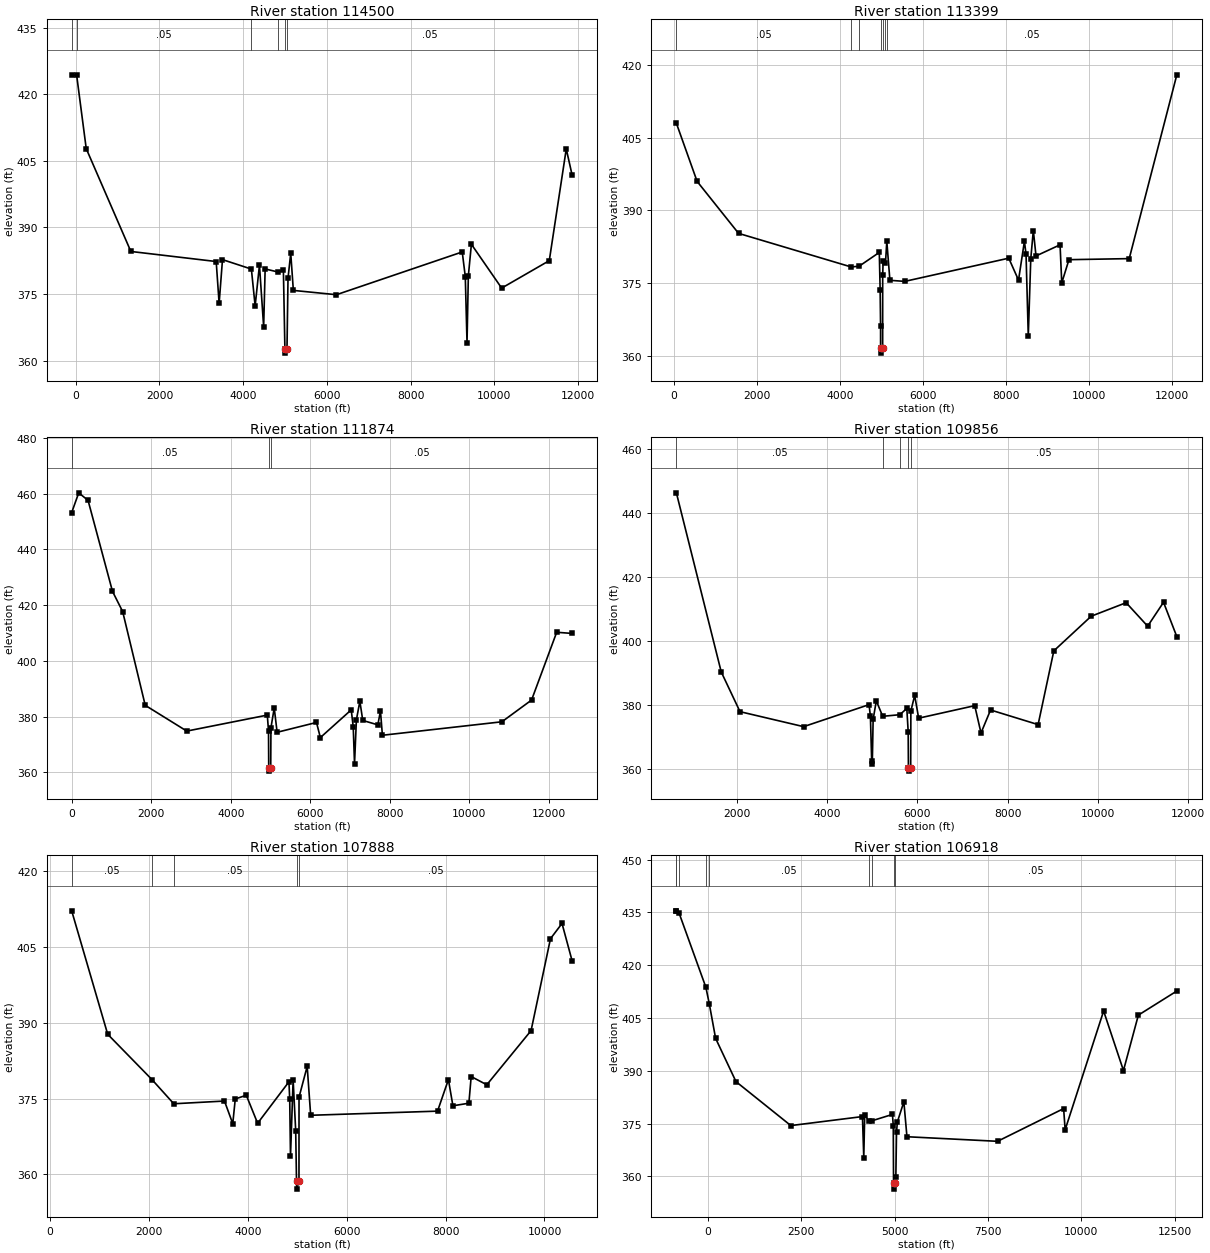
Type RM Length L Ch R = 1 ,114500  ,1101,1101,1101
BEGIN DESCRIPTION:
Kings Creek 227.0
END DESCRIPTION:
XS GIS Cut Line= 3
        2640306.      6900935.38      2635226.42      6900505.97
       2628630.8      6898624.23
#Sta/Elev= 30
   -97.7  424.27    19.7  424.41   249.8  407.77  1315.9  384.59  3354.6  382.32
  3424.8  372.89  3505.1  382.75  4195.2  380.62  4285.1  372.31  4388.2   381.5
  4488.6  367.59  4524.2  380.65  4835.9  379.95  4960.3  380.31  4996.2  362.67
  5000.2  361.67  5046.2  362.67  5070.4  378.54  5135.6   384.2    5198  375.81
  6227.5  374.84    9233  384.48  9305.9  378.93  9347.2  364.03  9378.7  379.06
  9451.6  386.21 10174.8  376.33 11312.6  382.52 11718.2   407.7 11858.8  401.78
#Mann= 6 ,-1 , 0
   -97.7    .075       0    19.7     .05       0  4195.2     .12       0
  4835.9     .05       0  4996.2     .03       0  5046.2     .05       0
Bank Sta=4996.2,5046.2
XS Rating Curve= 0 ,0
Exp/Cntr=0.3,0.1

Type RM Length L Ch R = 1 ,113399  ,1525,1525,1525
BEGIN DESCRIPTION:
Kings Creek 226.0
END DESCRIPTION:
XS GIS Cut Line= 3
      2640065.94      6899583.82      2635294.05      6899473.49
      2628164.08      6897924.76
#Sta/Elev= 30
    55.1  407.97   555.2  395.96  1555.4  385.23  4270.5   378.3  4462.2  378.45
  4949.1   381.3  4969.5  373.44  4979.8  366.14  4980.1  361.51  4984.1  360.51
  5030.1  361.51  5030.9  376.54  5041.2  379.45  5098.6  379.17    5130  383.61
  5204.9  375.54  5563.1  375.32  8071.2  380.11  8306.7  375.58    8449  383.61
  8487.9  380.91  8542.1  364.06  8602.3  380.03  8663.7  385.82  8728.5  380.57
  9308.4  382.87  9349.3     375  9522.9   379.8 10976.4  380.02 12124.5  417.96
#Mann= 7 ,-1 , 0
    55.1     .05       0  4270.5     .12       0  4462.2     .05       0
  4980.1     .03       0  5030.1     .05       0  5098.6     .12       0
    5130     .05       0
Bank Sta=4980.1,5030.1
XS Rating Curve= 0 ,0
Exp/Cntr=0.3,0.1

Type RM Length L Ch R = 1 ,111874  ,2018,2018,2018
BEGIN DESCRIPTION:
Kings Creek 223.0
END DESCRIPTION:
XS GIS Cut Line= 3
       2639861.1      6897170.19      2634925.86      6897976.06
      2627600.38      6896009.31
#Sta/Elev= 30
     -.6  453.23   176.8   460.3   411.3  457.58  1025.6  424.93  1281.4  417.68
  1848.7  384.04  2893.6  374.79  4918.8  380.53  4949.2  374.79  4954.6  361.42
  4958.6  360.42  5004.6  361.42  5010.2  375.99    5093  383.08  5165.5  374.36
  6155.8  377.89  6252.7  372.46  7029.3  382.41  7079.3  376.36  7112.1  363.03
  7159.3  378.83  7246.7  385.51  7319.3  378.61  7698.5  377.03  7764.4  382.02
  7813.3  373.29 10818.7  378.13 11564.4  385.93   12196  410.25 12584.9  409.84
#Mann= 3 ,-1 , 0
     -.6     .05       0  4954.6     .03       0  5004.6     .05       0
Bank Sta=4954.6,5004.6
XS Rating Curve= 0 ,0
Exp/Cntr=0.3,0.1

Type RM Length L Ch R = 1 ,109856  ,1968,1968,1968
BEGIN DESCRIPTION:
Kings Creek 218.0
END DESCRIPTION:
XS GIS Cut Line= 3
      2639036.45      6896519.15      2634725.86      6896026.06
      2628033.81      6895162.81
#Sta/Elev= 30
   661.3  446.33    1655  390.27  2070.9  377.83    3480  373.14  4929.4  380.03
  4959.6  376.47  4989.8  361.36  5002.7  362.48    5020  375.43  5090.6  381.22
  5231.7  376.38  5610.5  376.88  5766.2  378.84  5796.4  371.55  5801.7  360.22
  5805.7  359.22  5851.7  360.22  5856.1  378.04  5940.5  382.93  6028.3  375.79
  7270.4  379.71  7409.7  371.17  7621.4  378.36  8674.6  373.78  9022.9  396.87
  9850.7  407.71 10624.6  411.94 11101.1  404.59 11452.9  412.07 11747.5  401.31
#Mann= 5 ,-1 , 0
   661.3     .05       0  5231.7     .12       0  5610.5     .05       0
  5801.7     .03       0  5851.7     .05       0
Bank Sta=5801.7,5851.7
XS Rating Curve= 0 ,0
Exp/Cntr=0.3,0.1

Type RM Length L Ch R = 1 ,107888  ,970,970,970
BEGIN DESCRIPTION:
Mapping XS 2ce3f325
END DESCRIPTION:
XS GIS Cut Line= 3
      2638862.87      6895531.74      2634533.42      6894121.14
      2629000.33       6894728.7
#Sta/Elev= 30
   439.2  412.16  1167.4  387.72  2063.5  378.74  2503.7  373.96  3528.8   374.5
  3696.3  370.02    3747  374.91  3969.8  375.65  4199.1   370.1  4832.2  378.31
  4847.9  374.88  4863.7  363.53    4917   378.7  4968.9  368.61  4985.2  358.76
  4989.2  357.06  5035.2  358.76  5036.2  375.25  5201.3  381.37  5271.7  371.68
  7837.1   372.5    8057  378.75    8148  373.56  8470.9  374.07  8517.4  379.35
    8833  377.72  9728.4  388.44 10120.7  406.64 10354.1  409.66   10559  402.24
#Mann= 5 ,-1 , 0
   439.2     .05       0  2063.5     .12       0  2503.7     .05       0
  4985.2     .03       0  5035.2     .05       0
Bank Sta=4985.2,5035.2
XS Rating Curve= 0 ,0
Exp/Cntr=0.3,0.1

Type RM Length L Ch R = 1 ,106918  ,1107,1107,1107
BEGIN DESCRIPTION:
Mapping XS 4dc10ec1
END DESCRIPTION:
XS GIS Cut Line= 5
      2639676.64      6895358.12      2634262.16      6893285.64
      2631755.64      6892189.72      2629925.89      6891721.05
       2626960.3      6891896.71
#Sta/Elev= 30
  -839.1  435.44    -836  435.41  -768.7  434.86     -50  413.73    40.7  409.08
   210.9   399.2   756.5   386.9  2223.9  374.41  4140.6  376.97  4176.1  365.33
  4200.8  377.45  4319.7  375.65  4399.6  375.79  4943.6  377.58  4965.2  374.39
  4972.9  358.05  4976.9  356.35  5022.9  358.05  5034.3  359.81  5052.2  372.46
  5074.3  375.43  5248.9  381.17  5331.4  371.24  7755.7  369.94  9524.3  379.24
  9565.1  373.22 10594.6  406.97 11125.5  390.06 11524.1   405.8 12553.7  412.65
#Mann= 9 ,-1 , 0
  -839.1     .05       0    -836    .075       0  -768.7     .05       0
     -50    .075       0    40.7     .05       0  4319.7     .12       0
  4399.6     .05       0  4972.9     .03       0  5022.9     .05       0
Bank Sta=4972.9,5022.9
XS Rating Curve= 0 ,0
Exp/Cntr=0.3,0.1