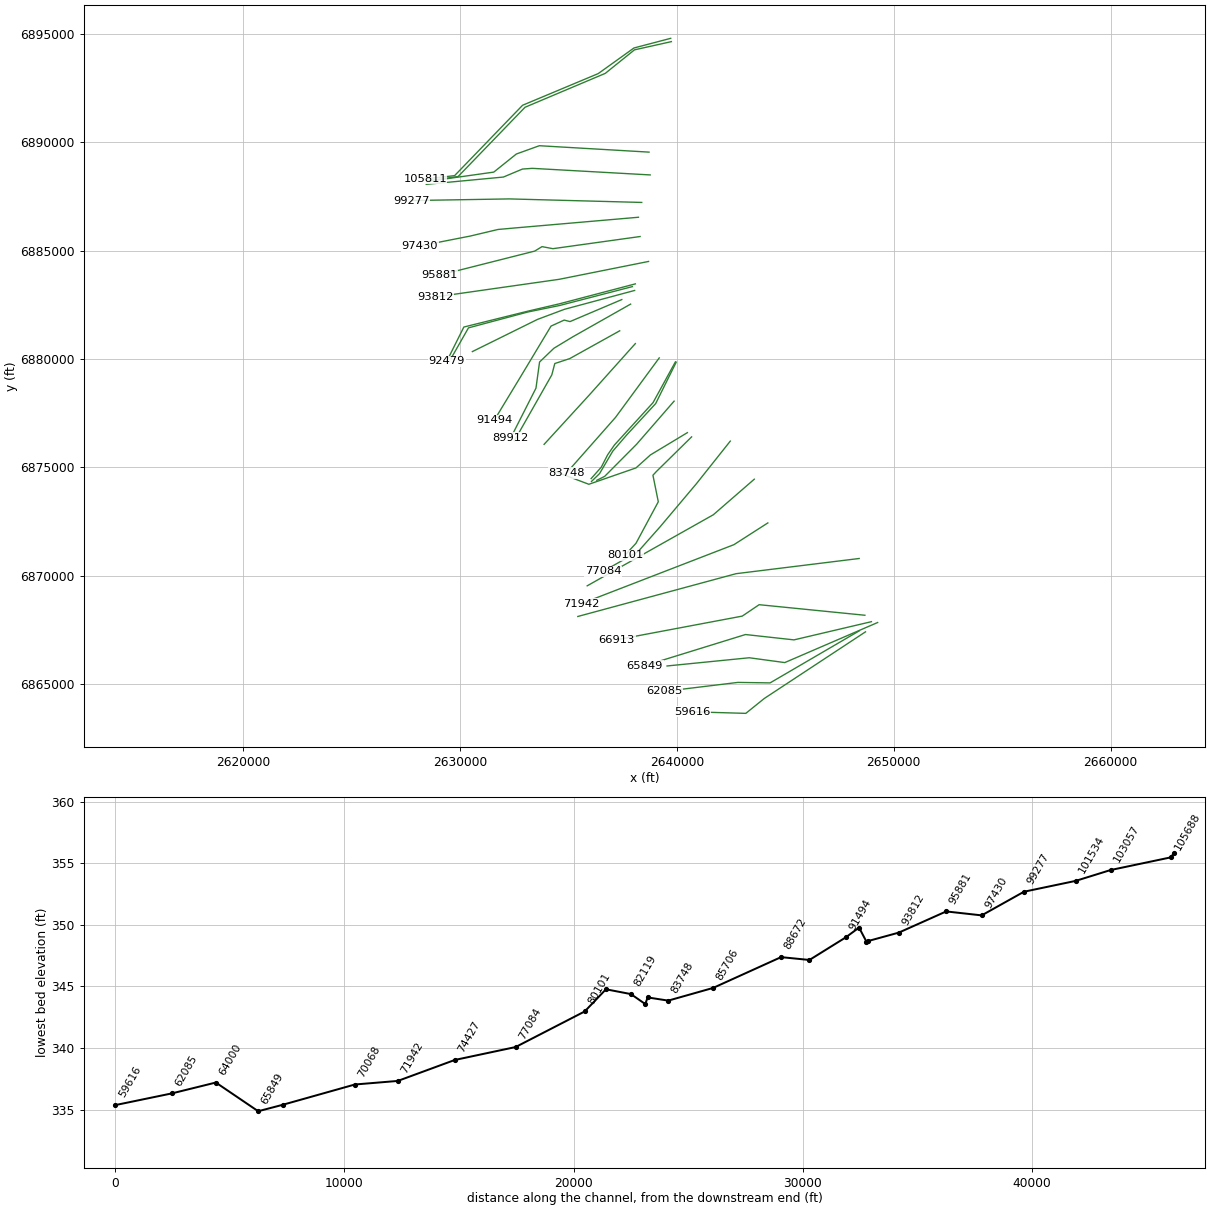
HEC-RAS study Kings Creek.prj: Kings Creek Base Level Engineering

--- Kings Creek.g01 (geometry) --- (continued)

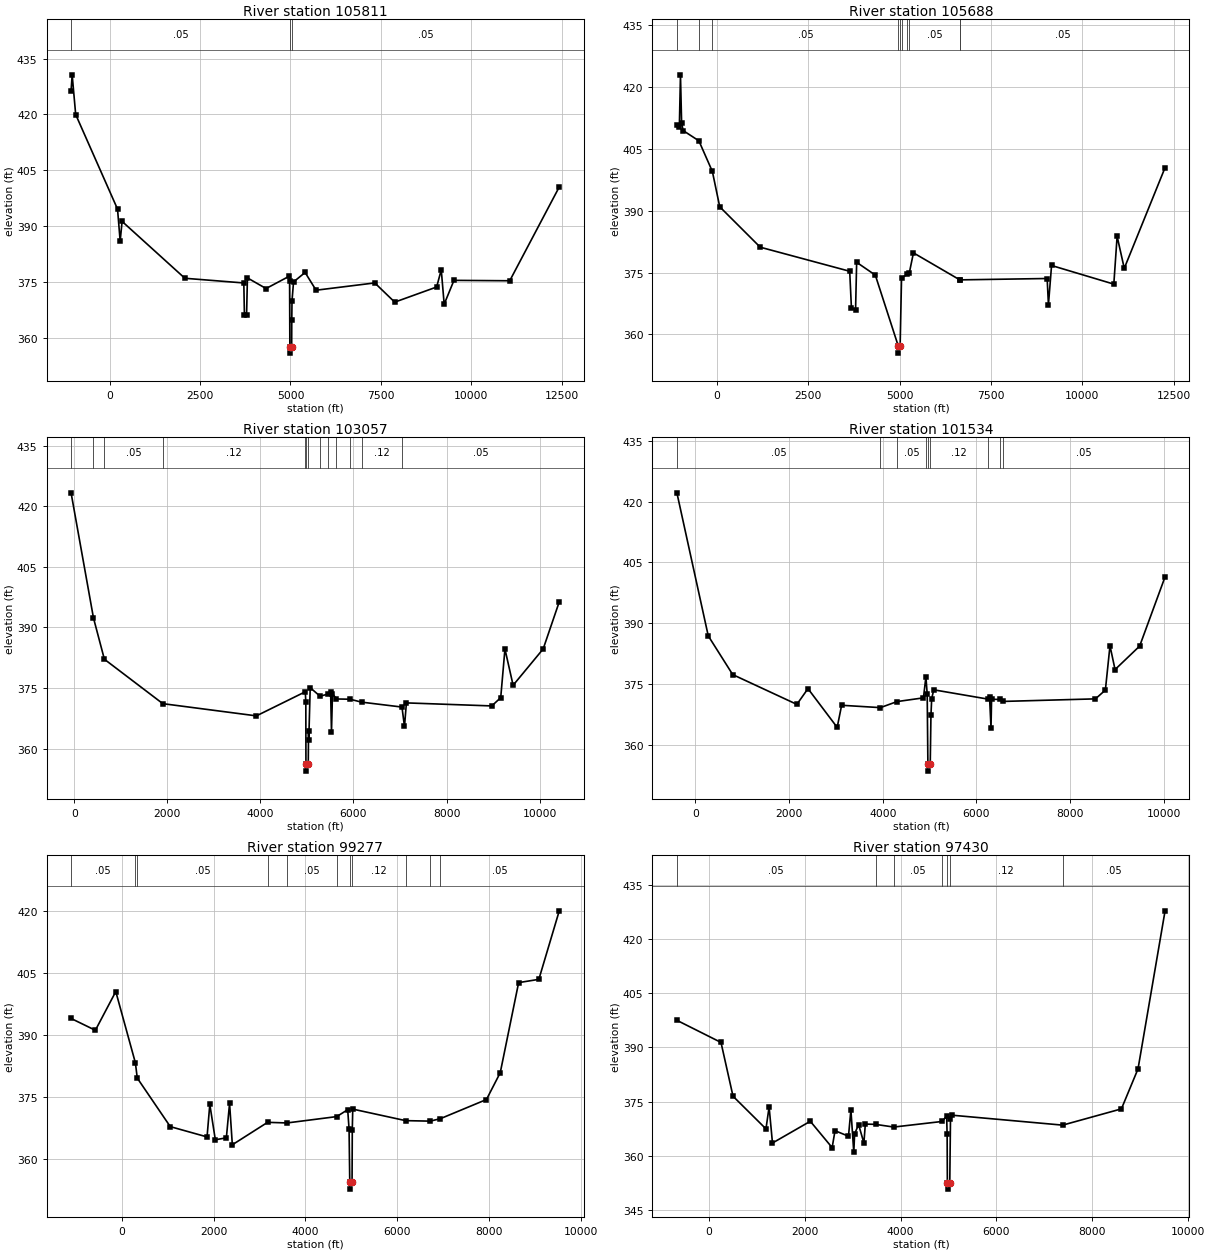
Type RM Length L Ch R = 1 ,105811  ,123,123,123
BEGIN DESCRIPTION:
Mapping XS b83c692d
END DESCRIPTION:
XS GIS Cut Line= 6
      2639709.24       6894793.9       2638016.5      6894349.01
      2636367.19      6893166.28      2632877.87      6891704.69
      2629742.45      6888456.43      2628381.08      6888305.17
#Sta/Elev= 30
 -1068.7  426.31 -1038.6  430.64  -941.3  419.97   216.4  394.53   289.1  385.94
   342.7  391.22  2078.9  375.93  3709.7  374.67  3726.3  366.07    3786  366.05
  3809.6  376.03  4325.2  373.17  4968.6  376.49  4976.2  375.18  4983.2   357.5
  4987.2   355.8  5033.2   357.5  5036.3  364.62  5042.8  369.84  5085.2  374.95
    5405  377.49  5708.4  372.72  7331.9  374.68  7883.8  369.51  9043.3  373.58
  9171.4   378.2    9252  368.95  9522.7  375.37 11065.9  375.26 12435.6  400.49
#Mann= 3 ,-1 , 0
 -1068.7     .05       0  4983.2     .03       0  5033.2     .05       0
Bank Sta=4983.2,5033.2
XS Rating Curve= 0 ,0
Exp/Cntr=0.3,0.1

Type RM Length L Ch R = 1 ,105688  ,2631,2631,2631
BEGIN DESCRIPTION:
Mapping XS 76138505
END DESCRIPTION:
XS GIS Cut Line= 6
      2639741.77      6894641.98       2638038.2       6894262.2
      2636692.71      6893177.13      2632990.72      6891612.68
      2629905.65      6888416.49      2628516.73      6888216.84
#Sta/Elev= 30
 -1100.2  410.67 -1032.8  410.29 -1002.1  422.87  -971.3  411.27    -930  409.38
  -498.1  406.89  -129.1  399.47    72.4  390.92    1181  381.13    3630   375.3
    3677  366.42  3790.5     366  3820.2  377.47  4331.1  374.37  4960.2  357.18
  4964.2  355.48  5010.2  357.18  5048.7  373.73  5207.1  374.52  5258.5  374.78
  5374.7  379.76    6646  373.21  6654.9  373.22  9034.5  373.55  9069.6   367.2
    9155   376.7   10859  372.19 10949.6  383.77 11145.1  376.01 12262.2  400.41
#Mann= 10 ,-1 , 0
 -1100.2     .05       0  -498.1     .12       0  -129.1     .05       0
  4960.2     .07       0  5010.2     .05       0  5048.7     .05       0
  5207.1     .12       0  5258.5     .05       0    6646     .12       0
  6654.9     .05       0
Bank Sta=4960.2,5010.2
XS Rating Curve= 0 ,0
Exp/Cntr=0.3,0.1

Type RM Length L Ch R = 1 ,103057  ,1523,1523,1523
BEGIN DESCRIPTION:
Mapping XS 594cba5c
END DESCRIPTION:
XS GIS Cut Line= 5
      2638710.92      6889542.15      2633652.15      6889837.87
      2632591.15      6889455.35      2631549.48      6888619.84
      2628620.44      6888207.61
#Sta/Elev= 30
   -67.4   423.3   413.7  392.35   648.1  382.13  1903.9  371.14  3914.3  368.12
  4964.2  374.08  4976.1  371.61  4978.4  356.15  4982.4  354.45  5028.4  356.15
  5034.1  364.27  5039.4   362.2  5070.3   375.1  5281.1  372.99  5450.2   373.5
  5509.1  373.99  5527.4  364.08  5548.7  373.62  5635.1   372.3  5926.3  372.24
  6172.3  371.52  7041.6   370.3  7095.6  365.51  7137.2  371.33  8971.4  370.58
  9163.3  372.63  9254.2  384.65  9429.5  375.69 10075.5  384.68 10421.1  396.34
#Mann= 13 ,-1 , 0
   -67.4     .05       0   413.7     .12       0   648.1     .05       0
  1903.9     .12       0  4964.2     .05       0  4978.4     .03       0
  5028.4     .05       0  5281.1     .12       0  5450.2     .05       0
  5635.1     .12       0  5926.3     .05       0  6172.3     .12       0
  7041.6     .05       0
Bank Sta=4978.4,5028.4
XS Rating Curve= 0 ,0
Exp/Cntr=0.3,0.1

Type RM Length L Ch R = 1 ,101534  ,2257,2257,2257
BEGIN DESCRIPTION:
Mapping XS 86c93401
END DESCRIPTION:
XS GIS Cut Line= 5
      2638765.16      6888489.64        2633329.      6888793.45
      2632873.27       6888760.9      2631994.36      6888391.98
      2628435.35      6888055.61
#Sta/Elev= 30
  -397.1  422.16   273.1   386.9   795.6  377.36    2166  370.02  2403.2   373.9
  3027.4  364.35  3122.2   369.8  3950.7  369.22  4305.5  370.71  4870.3  371.63
    4923  376.81  4950.4  372.57  4965.4  355.27  4969.4  353.57  5015.4  355.27
  5030.5  367.29  5046.5  371.46  5090.6  373.61  6243.6  371.33  6282.3  371.86
  6313.7  364.25  6325.7  371.28  6500.2  371.24  6575.2  370.75  8545.4  371.38
  8757.1  373.55  8855.4  384.46  8963.8   378.6  9489.4  384.39 10032.5  401.46
#Mann= 9 ,-1 , 0
  -397.1     .05       0  3950.7     .12       0  4305.5     .05       0
    4923     .12       0  4965.4     .07       0  5015.4     .12       0
  6243.6     .05       0  6500.2     .12       0  6575.2     .05       0
Bank Sta=4965.4,5015.4
XS Rating Curve= 0 ,0
Exp/Cntr=0.3,0.1

Type RM Length L Ch R = 1 ,99277   ,1847,1847,1847
BEGIN DESCRIPTION:
Mapping XS 647e6355
END DESCRIPTION:
XS GIS Cut Line= 3
      2638374.52       6887220.1      2632265.63      6887382.86
      2627751.73      6887306.91
#Sta/Elev= 30
 -1101.1  393.98  -572.4  391.12    -128  400.49   298.5  383.25   339.8  379.55
  1058.2  367.81  1858.5  365.32  1918.5  373.19  2038.5  364.63  2278.6   365.1
  2348.6  373.46  2408.7  363.42  3176.2  368.85  3598.3   368.7  4681.8  370.24
  4919.6  371.91  4949.6   367.2  4964.6  354.39  4968.6  352.69  5014.6  354.39
  5019.6  367.09  5029.6  372.05  6180.8  369.26  6713.6  369.14  6933.7  369.72
    7940  374.37    8240  380.86  8640.1  402.65  9080.2  403.44  9524.5  420.02
#Mann= 11 ,-1 , 0
 -1101.1     .05       0   298.5     .12       0   339.8     .05       0
  3176.2     .12       0  3598.3     .05       0  4681.8     .12       0
  4964.6     .07       0  5014.6     .12       0  6180.8     .05       0
  6713.6     .12       0  6933.7     .05       0
Bank Sta=4964.6,5014.6
XS Rating Curve= 0 ,0
Exp/Cntr=0.3,0.1

Type RM Length L Ch R = 1 ,97430   ,1549,1549,1549
BEGIN DESCRIPTION:
Mapping XS 5cd8c3e2
END DESCRIPTION:
XS GIS Cut Line= 5
      2638222.65      6886536.51      2632591.15      6886048.23
      2631744.79      6885972.27      2630464.41      6885668.45
      2628142.33      6885212.72
#Sta/Elev= 30
  -667.7  397.49   252.4  391.37   503.3  376.48  1190.7  367.44  1256.1  373.52
  1326.4  363.53  2115.5  369.55  2571.1  362.26  2631.3  366.94  2912.3  365.41
  2962.5  372.73  3022.7  360.93  3040.2  366.07  3123.1  368.63  3233.5  363.54
  3263.6  368.78  3476.9  368.69  3856.9  367.95  4861.4  369.49    4960  370.93
    4970  365.95  4975.1  352.47  4979.1  350.77  5025.1  352.47  5040.3  370.22
  5080.5  371.22  7379.5  368.48  8606.3  372.98  8952.8  384.06    9517  427.79
#Mann= 7 ,-1 , 0
  -667.7     .05       0  3476.9     .12       0  3856.9     .05       0
  4861.4     .12       0  4975.1     .07       0  5025.1     .12       0
  7379.5     .05       0
Bank Sta=4975.1,5025.1
XS Rating Curve= 0 ,0
Exp/Cntr=0.3,0.1

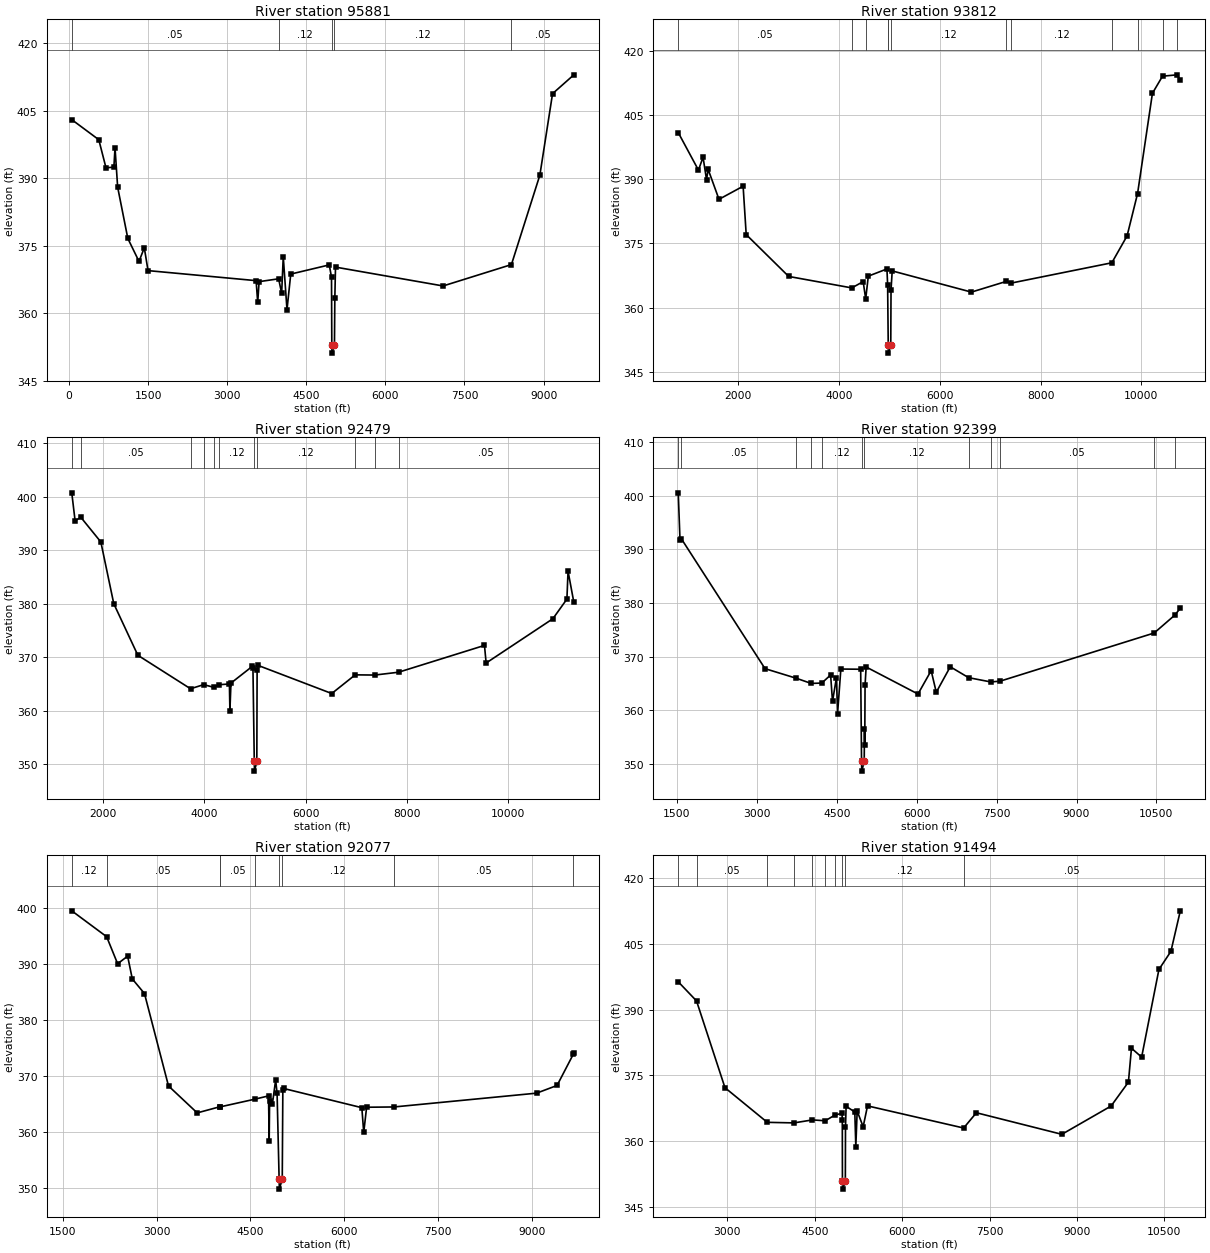
Type RM Length L Ch R = 1 ,95881   ,2069,2069,2069
BEGIN DESCRIPTION:
Mapping XS 5b327704
END DESCRIPTION:
XS GIS Cut Line= 5
      2638298.59      6885646.75      2634276.41        6885086.
      2633773.87      6885180.17       2633437.5      6884974.01
      2629021.31       6883856.4
#Sta/Elev= 30
    51.9  402.99   564.3  398.53   700.7  392.29   850.5  392.42   872.3  396.73
   922.1  387.98  1114.7  376.59  1326.7  371.48  1427.7   374.5  1498.3  369.43
    3548   367.2  3578.3  362.36  3604.8  366.98    3975  367.61  4032.6   364.4
  4062.9  372.53  4133.7  360.74    4205  368.66  4935.5   370.7  4978.1  367.97
  4983.8  352.79  4987.8  351.09  5033.8  352.79    5041  363.28  5053.9  370.21
  7094.2  366.02  8390.4  370.77  8929.8  390.66  9170.2  408.76  9574.2  412.95
#Mann= 5 ,-1 , 0
    51.9     .05       0    3975     .12       0  4983.8     .07       0
  5033.8     .12       0  8390.4     .05       0
Bank Sta=4983.8,5033.8
XS Rating Curve= 0 ,0
Exp/Cntr=0.3,0.1

Type RM Length L Ch R = 1 ,93812   ,1333,1333,1333
BEGIN DESCRIPTION:
Mapping XS 7d99c9d9
END DESCRIPTION:
XS GIS Cut Line= 3
      2638689.27      6884496.58      2634565.97      6883671.93
      2628859.74       6882858.3
#Sta/Elev= 30
   805.6  400.91  1206.7  392.14  1298.4  395.14  1367.1  389.94  1400.4  392.28
  1614.6  385.31  2093.9  388.37  2155.1  377.07  2998.8  367.29  4251.6  364.61
  4477.5  366.08  4527.7  362.03  4579.5  367.36  4949.3  369.04    4963   365.4
  4975.3  351.17  4979.3  349.37  5025.3  351.17  5030.7  364.19  5054.3  368.58
  6626.7  363.63    7322  366.14  7421.6  365.75  9414.8  370.48  9717.7  376.77
  9925.8  386.66 10220.9  410.09 10421.2  414.08 10710.3   414.4 10774.5  413.09
#Mann= 12 ,-1 , 0
   805.6     .05       0  4251.6     .12       0  4527.7     .05       0
    4963     .12       0  4975.3     .07       0  5025.3     .12       0
    7322     .05       0  7421.6     .12       0  9414.8     .05       0
  9925.8     .12       0 10421.2     .05       0 10710.3     .12       0
Bank Sta=4975.3,5025.3
XS Rating Curve= 0 ,0
Exp/Cntr=0.3,0.1

Type RM Length L Ch R = 1 ,92479   ,80,80,80
BEGIN DESCRIPTION:
Mapping XS 1f7aef18
END DESCRIPTION:
XS GIS Cut Line= 5
      2638079.02      6883461.43      2634576.02      6882541.01
      2633134.06      6882204.91      2630168.95      6881469.63
      2629381.71      6879889.62
#Sta/Elev= 30
  1378.1  400.69  1443.6  395.48  1558.1  396.11  1952.7  391.51  2208.4  379.97
    2684  370.34  3725.6  364.08  3984.4  364.85  4181.6  364.36    4290  364.84
  4493.4  364.97  4503.4  359.97  4524.4  365.14  4948.3  368.28  4958.7  367.98
  4985.3  350.49  4989.3  348.69  5035.3  350.49  5041.1  367.58  5061.3  368.44
  6516.2  363.19  6979.7  366.68  7365.7  366.64  7836.3  367.17  9534.5  372.18
  9567.5  368.89 10885.9  377.16 11163.7  380.83 11186.1  386.06 11300.8  380.23
#Mann= 11 ,-1 , 0
  1378.1     .12       0  1558.1     .05       0  3725.6     .12       0
  3984.4     .05       0  4181.6      .1       0    4290     .12       0
  4985.3     .07       0  5035.3     .12       0  6979.7     .05       0
  7365.7     .12       0  7836.3     .05       0
Bank Sta=4985.3,5035.3
XS Rating Curve= 0 ,0
Exp/Cntr=0.3,0.1

Type RM Length L Ch R = 1 ,92399   ,322,322,322
BEGIN DESCRIPTION:
Kings Creek 184.0
END DESCRIPTION:
XS GIS Cut Line= 5
      2637941.02       6883334.7      2634575.63      6882460.82
      2633118.06      6882162.81      2630381.84      6881430.68
      2629576.56      6880015.33
#Sta/Elev= 30
    1523  400.54  1555.8  391.83  1583.5  391.94  3152.3  367.75  3738.9  365.96
  4017.5     365  4217.5  365.06  4383.7  366.57  4419.1  361.64  4493.4  366.09
    4514  359.37    4576  367.68    4948  367.64  4964.3  350.44  4968.3  348.64
  5014.3  350.44  5019.5  356.53  5024.6  353.44  5030.2  364.65  5050.7  368.06
    6024  363.02  6271.2  367.38  6367.1  363.35  6629.9   368.1  6974.4  366.07
  7391.7  365.27  7566.9  365.42 10457.9   374.4 10845.1  377.73 10948.6  379.02
#Mann= 12 ,-1 , 0
    1523     .12       0  1583.5     .05       0  3738.9     .12       0
  4017.5     .05       0  4217.5     .12       0  4964.3     .07       0
  5014.3     .12       0  6974.4     .05       0  7391.7     .12       0
  7566.9     .05       0 10457.9     .12       0 10845.1     .05       0
Bank Sta=4964.3,5014.3
XS Rating Curve= 0 ,0
Exp/Cntr=0.3,0.1

Type RM Length L Ch R = 1 ,92077   ,583,583,583
BEGIN DESCRIPTION:
Mapping XS 94c58a98
END DESCRIPTION:
XS GIS Cut Line= 4
      2638044.74      6883157.61      2634815.54      6882289.55
       2633565.7      6881821.22       2630562.1      6880336.44
#Sta/Elev= 30
  1642.2  399.57    2200  394.94  2375.6   390.1  2535.5  391.46  2610.3  387.38
  2804.9  384.77  3189.1  368.24    3648  363.42  4004.7   364.5  4013.3  364.49
  4568.2  365.87  4788.8  366.46  4799.2  358.46  4805.7  365.58    4851  365.06
  4902.7  369.31  4925.6  366.92  4958.2  351.58  4962.2  349.78  5008.2  351.58
  5017.6  367.53  5029.1  367.79  6280.8  364.35  6311.1  359.92  6357.3  364.43
  6795.1  364.48  9075.7  366.95  9403.1  368.33  9660.6  373.87  9671.3  374.12
#Mann= 9 ,-1 , 0
  1642.2     .12       0    2200     .05       0  4004.7     .12       0
  4013.3     .05       0  4568.2     .12       0  4958.2     .07       0
  5008.2     .12       0  6795.1     .05       0  9660.6     .12       0
Bank Sta=4958.2,5008.2
XS Rating Curve= 0 ,0
Exp/Cntr=0.3,0.1

Type RM Length L Ch R = 1 ,91494   ,1582,1582,1582
BEGIN DESCRIPTION:
Mapping XS dd2b154b
END DESCRIPTION:
XS GIS Cut Line= 6
      2637454.01       6882736.6      2635066.84      6881720.97
      2634797.75      6881790.42      2634190.11      6881512.64
       2632766.5      6879142.85      2631569.28      6877164.84
#Sta/Elev= 30
  2156.9  396.38  2470.9     392  2958.9  372.17  3685.1  364.25  4142.3  364.12
  4459.7   364.8  4680.5  364.61  4842.8  365.89  4967.5  366.32  4972.7   364.8
  4974.9  350.78  4978.9  348.98  5024.9  350.78  5027.4   363.1  5038.1  367.92
  5187.2  366.61  5204.7   358.7  5227.7  366.82  5330.8  363.25  5405.4  368.01
  7055.2  362.95  7274.1  366.44  8740.6  361.51    9586  367.98  9883.1  373.44
  9935.4  381.19   10110  379.16 10406.8   399.2 10612.4  403.33 10773.8   412.6
#Mann= 10 ,-1 , 0
  2156.9     .12       0  2470.9     .05       0  3685.1     .12       0
  4142.3     .05       0  4459.7     .12       0  4680.5     .05       0
  4842.8     .12       0  4974.9     .07       0  5024.9     .12       0
  7055.2     .05       0
Bank Sta=4974.9,5024.9
XS Rating Curve= 0 ,0
Exp/Cntr=0.3,0.1

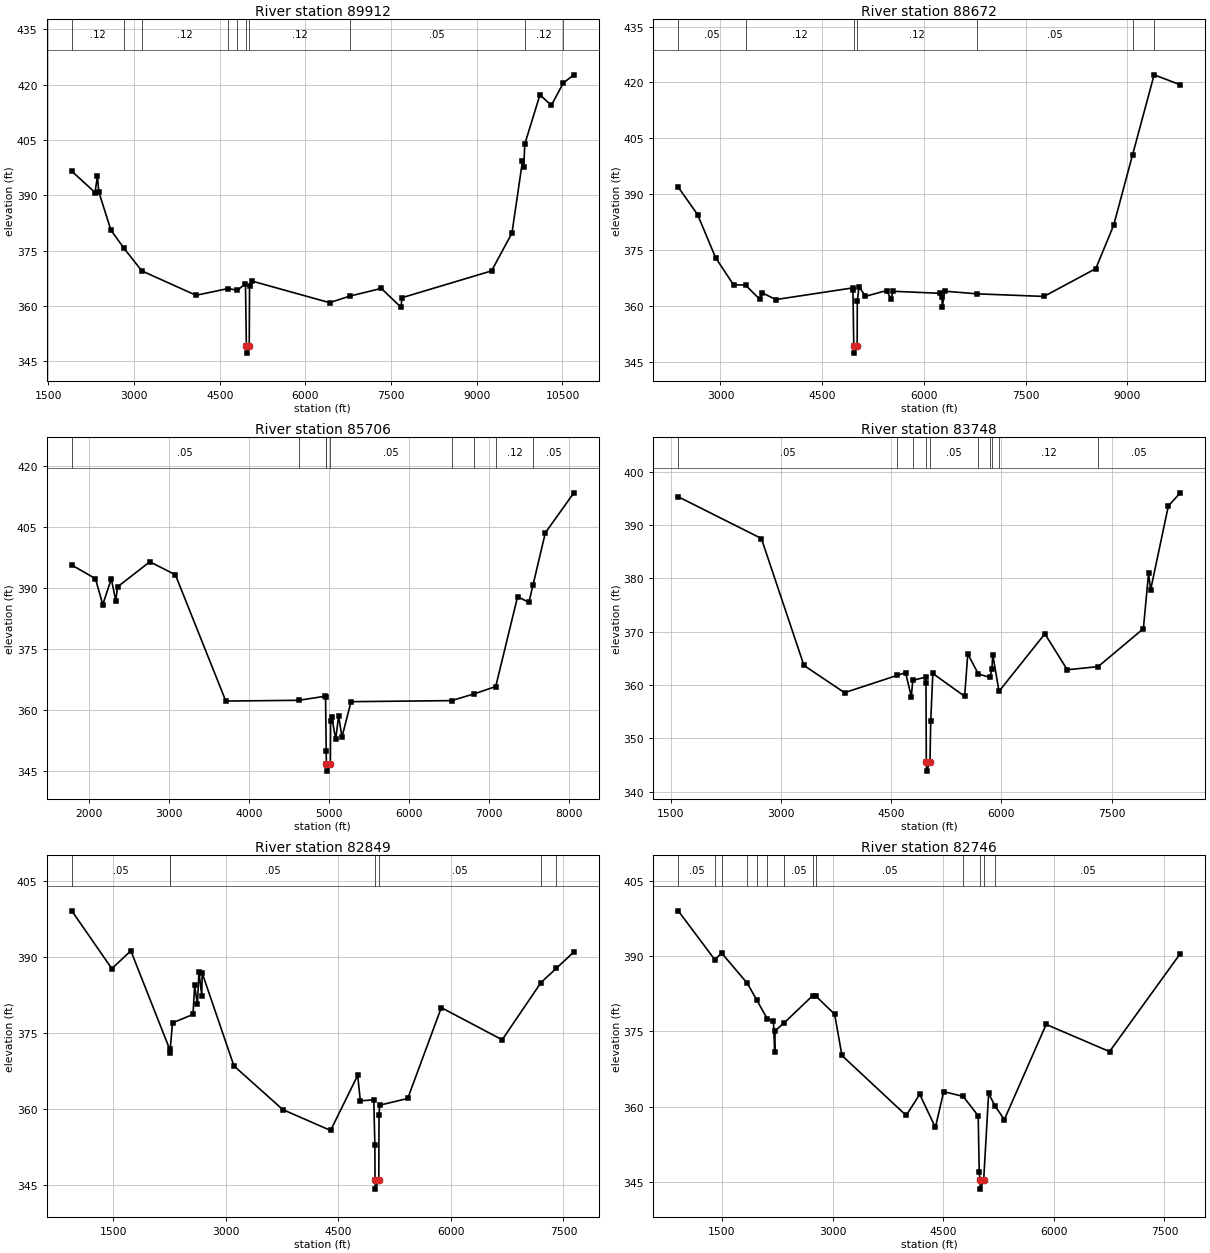
Type RM Length L Ch R = 1 ,89912   ,1240,1240,1240
BEGIN DESCRIPTION:
Mapping XS d0282325
END DESCRIPTION:
XS GIS Cut Line= 6
      2637861.98      6882528.26      2635179.69      6881009.17
      2634320.31      6880488.33      2633661.31      6879853.53
      2633495.66      6878648.05      2632332.45      6876356.36
#Sta/Elev= 30
    1910  396.54  2316.9  390.74  2360.2  395.24  2381.8     391  2594.9  380.54
  2827.3  375.55  3135.8  369.48  4084.5  362.85  4648.2  364.68  4810.1  364.21
  4950.9  366.01  4966.8  348.95  4970.8  347.15  5016.8  348.95  5022.1  365.26
  5058.9  366.73  6422.9  360.85  6774.1  362.61  7328.9  364.72  7672.1  359.61
  7692.3   362.2  9258.6  369.47  9615.9  379.73  9799.6  399.21  9821.9   397.8
  9840.7   403.9 10105.7  417.25   10306  414.42 10515.5  420.49 10699.3  422.69
#Mann= 10 ,-1 , 0
    1910     .12       0  2827.3     .05       0  3135.8     .12       0
  4648.2     .05       0  4810.1     .12       0  4966.8     .07       0
  5016.8     .12       0  6774.1     .05       0  9840.7     .12       0
 10515.5     .05       0
Bank Sta=4966.8,5016.8
XS Rating Curve= 0 ,0
Exp/Cntr=0.3,0.1

Type RM Length L Ch R = 1 ,88672   ,2966,2966,2966
BEGIN DESCRIPTION:
Mapping XS 4266ec4f
END DESCRIPTION:
XS GIS Cut Line= 5
      2637358.47       6881295.6      2635049.48       6880010.9
      2634363.72      6879785.21      2634226.14      6879260.67
      2632497.38      6876217.47
#Sta/Elev= 30
  2376.6   391.9  2661.8  384.56    2927  373.02  3191.9  365.71    3369  365.64
    3581  361.79  3609.7  363.62  3815.6  361.75  4947.6  364.87  4954.2  364.19
  4966.1  349.18  4970.1  347.38  5016.1  349.18  5018.1  361.32  5043.6  365.22
  5138.4  362.62  5449.7  364.17  5513.3  362.03  5550.3  363.97  6231.1  363.44
  6265.6  362.46  6272.5  359.77  6305.8     364  6783.1  363.29  7771.8  362.59
    8536  370.05  8799.9   381.7  9077.8  400.53  9396.7  422.05  9783.1  419.38
#Mann= 7 ,-1 , 0
  2376.6     .05       0    3369     .12       0  4966.1     .07       0
  5016.1     .12       0  6783.1     .05       0  9077.8     .12       0
  9396.7     .05       0
Bank Sta=4966.1,5016.1
XS Rating Curve= 0 ,0
Exp/Cntr=0.3,0.1

Type RM Length L Ch R = 1 ,85706   ,1958,1958,1958
BEGIN DESCRIPTION:
Mapping XS c93c6299
END DESCRIPTION:
XS GIS Cut Line= 3
      2638078.96      6880705.31      2635926.22      6878300.83
      2633869.96       6876053.7
#Sta/Elev= 30
  1781.9  395.58  2077.5  392.24  2169.4  385.86  2275.6  392.18  2332.4  386.78
  2353.3  390.21  2757.1  396.39  3076.2  393.21  3706.6  362.12  4618.5  362.31
  4945.4   363.3  4952.9  363.01    4961  349.91    4963  346.68    4967  344.88
    5013  346.68  5016.4   357.2  5030.6  358.11  5079.9  352.71  5115.7  358.42
  5158.1  353.27  5271.1  361.97  6528.5  362.23  6812.6  363.91  7079.1   365.7
  7352.3  387.81  7493.6   386.4  7545.3  390.71  7698.9  403.52  8055.2  413.36
#Mann= 9 ,-1 , 0
  1781.9     .05       0  4618.5     .12       0    4961     .05       0
    4963     .03       0    5013     .05       0  6528.5      .1       0
  6812.6     .05       0  7079.1     .12       0  7545.3     .05       0
Bank Sta=4963,5013
XS Rating Curve= 0 ,0
Exp/Cntr=0.3,0.1

Type RM Length L Ch R = 1 ,83748   ,899,899,899
BEGIN DESCRIPTION:
Mapping XS c97759c7
END DESCRIPTION:
XS GIS Cut Line= 3
      2639181.43      6880045.63      2637167.54      6877302.57
      2634903.18      6874734.56
#Sta/Elev= 30
  1604.9  395.33  2735.6   387.5  3314.3  363.68  3866.1  358.57  4578.2   361.8
  4695.7  362.33  4774.1  357.81    4794  360.87  4967.3   361.5  4973.5  360.44
  4977.8  345.65  4981.8  343.85  5027.8  345.65  5038.1  353.25  5066.5  362.18
  5499.1  357.88  5541.8  365.84  5685.3  362.07  5844.6  361.45    5870  363.06
  5881.4  365.73  5966.3  358.82    6590  369.62  6894.6  362.87  7314.1  363.46
  7929.5  370.58  7999.7  380.97  8028.2  377.89  8269.1  393.61  8431.6  396.07
#Mann= 10 ,-1 , 0
  1604.9     .05       0  4578.2     .12       0    4794     .05       0
  4977.8     .03       0  5027.8     .05       0  5685.3      .1       0
  5844.6     .12       0    5870     .05       0  5966.3     .12       0
  7314.1     .05       0
Bank Sta=4977.8,5027.8
XS Rating Curve= 0 ,0
Exp/Cntr=0.3,0.1

Type RM Length L Ch R = 1 ,82849   ,103,103,103
BEGIN DESCRIPTION:
Mapping XS f3ac5d96
END DESCRIPTION:
XS GIS Cut Line= 6
      2639927.97      6879863.37      2638894.97      6877979.65
      2637115.45      6876026.53      2636802.95      6875575.14
      2636507.81      6875002.22        2636040.      6874473.76
#Sta/Elev= 30
   946.8  399.05  1481.2  387.63  1734.1  391.16  2249.9   371.8  2254.9  371.01
  2289.6  376.93    2563   378.6  2584.4  384.32  2621.2  380.56  2642.5  387.03
  2679.3  382.21  2685.2  386.76  3108.1  368.44  3759.3  359.81  4396.6  355.69
  4757.6  366.57    4793  361.54    4972  361.73  4986.6  352.83  4988.9  345.91
  4992.9  344.11  5038.9  345.91  5042.3  358.69  5049.7  360.68  5424.5  362.01
  5872.2  379.94  6683.6  373.59  7200.9  384.89  7405.3   387.7  7638.8  390.92
#Mann= 7 ,-1 , 0
   946.8     .05       0  2249.9     .12       0  2254.9     .05       0
  4988.9     .03       0  5038.9     .05       0  7200.9     .12       0
  7405.3     .05       0
Bank Sta=4988.9,5038.9
XS Rating Curve= 0 ,0
Exp/Cntr=0.3,0.1

Type RM Length L Ch R = 1 ,82746   ,627,627,627
BEGIN DESCRIPTION:
Mapping XS 6adfce72
END DESCRIPTION:
XS GIS Cut Line= 6
      2639962.66      6879845.94       2639016.5      6877936.25
       2637686.1      6876494.92      2637037.33      6875740.07
      2636429.69      6874707.08       2636056.4      6874342.48
#Sta/Elev= 30
   907.3  399.01  1402.6  389.29  1496.9  390.58  1844.9  384.56  1971.1  381.26
  2115.7  377.48  2198.4  377.08  2215.2  370.91  2220.8  375.11  2347.4  376.74
  2729.5   382.1  2772.6  382.05    3028   378.4  3127.3  370.19  3998.2  358.25
  4181.9  362.46    4394  355.86  4507.4  362.99  4771.6  362.04  4974.7  358.18
  4988.8     347  4999.1  345.37  5003.1  343.57  5049.1  345.37  5116.2  362.66
  5200.8  360.18  5329.1  357.42  5896.4  376.38  6755.7  370.97  7715.6   390.5
#Mann= 13 ,-1 , 0
   907.3     .05       0  1402.6     .12       0  1496.9     .05       0
  1844.9     .12       0  1971.1     .05       0  2115.7     .12       0
  2347.4     .05       0  2729.5     .12       0  2772.6     .05       0
  4771.6     .12       0  4999.1     .07       0  5049.1     .12       0
  5200.8     .05       0
Bank Sta=4999.1,5049.1
XS Rating Curve= 0 ,0
Exp/Cntr=0.3,0.1

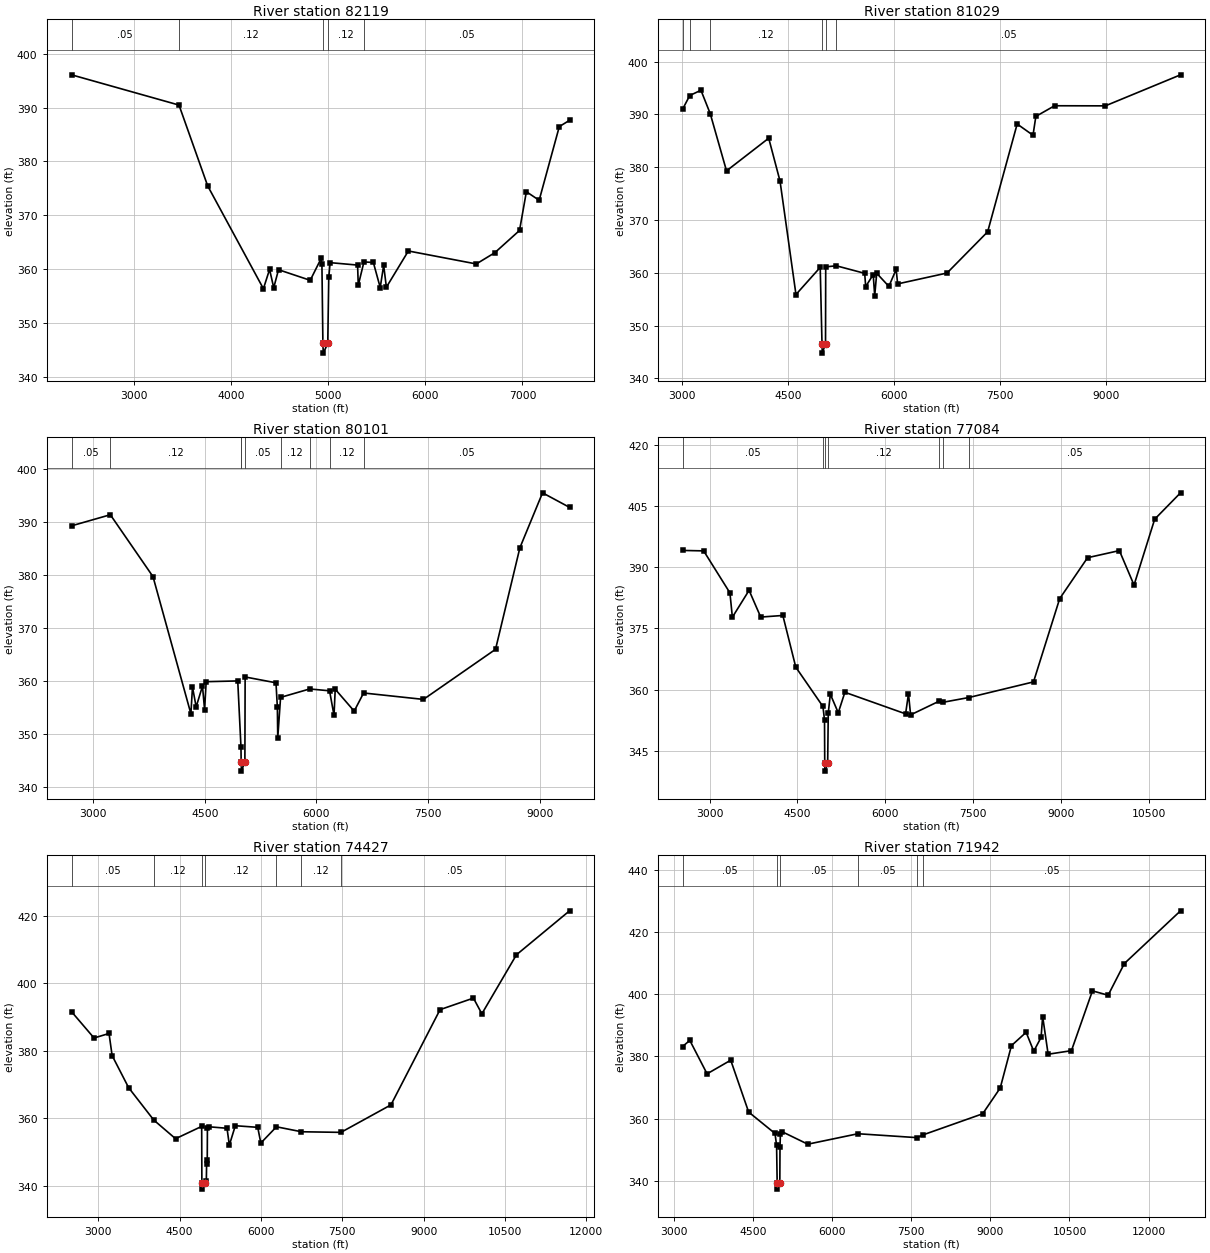
Type RM Length L Ch R = 1 ,82119   ,1090,1090,1090
BEGIN DESCRIPTION:
Mapping XS af0efab0
END DESCRIPTION:
XS GIS Cut Line= 4
      2639867.18      6878049.09      2638131.08      6876052.57
      2636664.06      6874576.87      2636301.64      6874395.66
#Sta/Elev= 30
  2353.4  396.09  3460.6  390.47  3755.9  375.46  4330.4  356.35    4394  359.93
  4436.7  356.53  4486.1  359.88  4812.8  357.91  4925.7  361.98  4933.4  360.88
  4943.5  346.18  4947.5  344.38  4993.5  346.18  5003.9  358.47    5018  361.19
  5300.9  360.74  5307.9  356.99  5366.4  361.33  5463.5  361.22  5534.2  356.57
  5569.6  360.69  5597.8  356.63  5824.1  363.36  6524.2  360.95  6715.1  363.04
  6969.7  367.17  7040.4  374.37  7172.1  372.78  7379.7  386.47  7485.2  387.64
#Mann= 5 ,-1 , 0
  2353.4     .05       0  3460.6     .12       0  4943.5     .07       0
  4993.5     .12       0  5366.4     .05       0
Bank Sta=4943.5,4993.5
XS Rating Curve= 0 ,0
Exp/Cntr=0.3,0.1

Type RM Length L Ch R = 1 ,81029   ,928,928,928
BEGIN DESCRIPTION:
Mapping XS 6f0986e1
END DESCRIPTION:
XS GIS Cut Line= 5
      2640479.14      6876595.08      2638773.44      6875566.46
      2638109.38       6874967.5       2635934.9      6874212.29
      2634186.69      6874873.51
#Sta/Elev= 30
  3004.3  390.98  3106.8  393.59  3264.9  394.59  3397.3  390.13  3627.5  379.31
  4225.4   385.5  4385.9  377.37  4611.7  355.88  4955.3  361.02  4980.6  346.57
  4984.6  344.77  5030.6  346.57  5033.3  361.12  5183.8  361.32  5585.6  359.89
  5599.8  357.38  5706.4  359.65  5727.5  355.63  5755.9   359.9  5928.3  357.42
  6031.6  360.63  6052.8  357.89  6752.6  359.95    7328  367.76  7746.5  388.19
  7970.9  386.06  8011.2  389.63  8276.7  391.65  8996.3  391.63 10061.4  397.51
#Mann= 6 ,-1 , 0
  3004.3     .12       0  3106.8     .05       0  3397.3     .12       0
  4980.6     .07       0  5030.6     .12       0  5183.8     .05       0
Bank Sta=4980.6,5030.6
XS Rating Curve= 0 ,0
Exp/Cntr=0.3,0.1

Type RM Length L Ch R = 1 ,80101   ,3017,3017,3017
BEGIN DESCRIPTION:
Mapping XS a246d1f0
END DESCRIPTION:
XS GIS Cut Line= 6
      2640674.47      6876399.78      2639046.88      6874798.23
      2638890.63      6874628.96      2639138.02        6873405.
      2638108.73      6871488.39      2637598.18        6870936.
#Sta/Elev= 30
  2710.4  389.21  3231.2   391.3  3804.5  379.63  4313.6  353.78  4334.9  358.81
  4384.4  355.08  4469.2     359  4497.5  354.56  4518.7  359.83    4943  359.97
  4986.1  347.59  4988.9  344.77  4992.9  342.97  5038.9  344.77  5042.2  360.72
  5456.8  359.62  5475.3  354.97  5480.4  349.21  5518.5  356.87  5909.3  358.46
  6176.5  358.11  6236.4  353.47  6252.5  358.41  6507.3  354.28  6633.9   357.7
  7437.7  356.49  8406.3  365.93  8733.4  385.07  9037.9  395.43  9400.6  392.69
#Mann= 9 ,-1 , 0
  2710.4     .05       0  3231.2     .12       0  4986.1     .05       0
  4988.9     .03       0  5038.9     .05       0  5518.5     .12       0
  5909.3     .05       0  6176.5     .12       0  6633.9     .05       0
Bank Sta=4988.9,5038.9
XS Rating Curve= 0 ,0
Exp/Cntr=0.3,0.1

Type RM Length L Ch R = 1 ,77084   ,2657,2657,2657
BEGIN DESCRIPTION:
Mapping XS af9b46af
END DESCRIPTION:
XS GIS Cut Line= 5
      2642458.34      6876204.48      2640895.84      6874238.33
      2639229.17      6872259.17      2638213.54      6871113.33
      2636585.97      6870188.87
#Sta/Elev= 30
  2538.9   394.1  2899.5  393.99    3348  383.71  3389.6  377.75  3674.8  384.34
  3873.4  377.79  4251.5  378.18  4472.1  365.53  4935.8   355.9  4962.8   352.6
  4966.6  341.98  4970.6  340.08  5016.6  341.98  5026.8   354.3  5062.1  358.91
  5197.3  354.36  5310.5  359.38    6347   354.1  6396.4  359.04  6432.6  353.85
  6919.4   357.2  6980.7  356.92  7428.1   358.1  8530.9  361.92  8977.5  382.29
  9453.6  392.32  9996.8  394.06 10247.1  385.62 10599.5  401.74 11040.7   408.2
#Mann= 7 ,-1 , 0
  2538.9     .05       0  4935.8     .12       0  4966.6     .07       0
  5016.6     .12       0  6919.4     .05       0  6980.7     .12       0
  7428.1     .05       0
Bank Sta=4966.6,5016.6
XS Rating Curve= 0 ,0
Exp/Cntr=0.3,0.1

Type RM Length L Ch R = 1 ,74427   ,2485,2485,2485
BEGIN DESCRIPTION:
Mapping XS 1e90b2ea
END DESCRIPTION:
XS GIS Cut Line= 3
      2643565.13      6874446.69      2641677.09      6872806.04
      2635857.82      6869525.38
#Sta/Elev= 30
    2509  391.54  2923.4  383.76  3199.7   385.1  3256.7  378.56  3561.5  369.05
  4024.9  359.47  4426.6  353.95    4908   357.6  4911.5  340.93  4915.5  339.03
  4961.5  340.93  4993.5  341.34  5000.1  347.52  5010.3  346.38  5013.8  357.09
  5035.5  357.49    5375  357.04  5418.3  352.07  5528.1   357.8  5941.4  357.32
  5998.8  352.67  6286.6  357.48    6748  356.01  7475.6  355.83    8398  363.97
    9303  392.15  9918.4  395.57 10074.1  390.92 10711.6  408.39 11690.6   421.4
#Mann= 7 ,-1 , 0
    2509     .05       0  4024.9     .12       0  4911.5     .07       0
  4961.5     .12       0  6286.6     .05       0    6748     .12       0
  7475.6     .05       0
Bank Sta=4911.5,4961.5
XS Rating Curve= 0 ,0
Exp/Cntr=0.3,0.1

Type RM Length L Ch R = 1 ,71942   ,1874,1874,1874
BEGIN DESCRIPTION:
Mapping XS 88606d37
END DESCRIPTION:
XS GIS Cut Line= 3
      2644190.14      6872428.45      2642627.61      6871425.83
      2635559.14      6868692.17
#Sta/Elev= 30
  3168.3  383.16  3306.2  385.12  3633.2  374.38  4081.2  378.76  4420.8   362.1
  4919.8  355.22    4950  351.45  4961.3  339.23  4965.3  337.33  5011.3  339.23
  5014.9  350.84  5022.7  355.11  5047.4  355.84  5541.2  351.77  6492.1  355.13
  7615.7  353.87  7720.9  354.74  8854.9  361.54  9187.4  369.83  9400.2  383.45
  9678.2  387.72  9822.6  381.64  9961.6  386.09  9991.5   392.8 10095.2  380.68
 10536.8  381.82 10934.6  401.04 11231.8  399.64 11539.7  409.83 12603.5  426.76
#Mann= 6 ,-1 , 0
  3168.3     .05       0  4961.3     .07       0  5011.3     .05       0
  6492.1     .05       0  7615.7     .12       0  7720.9     .05       0
Bank Sta=4961.3,5011.3
XS Rating Curve= 0 ,0
Exp/Cntr=0.3,0.1

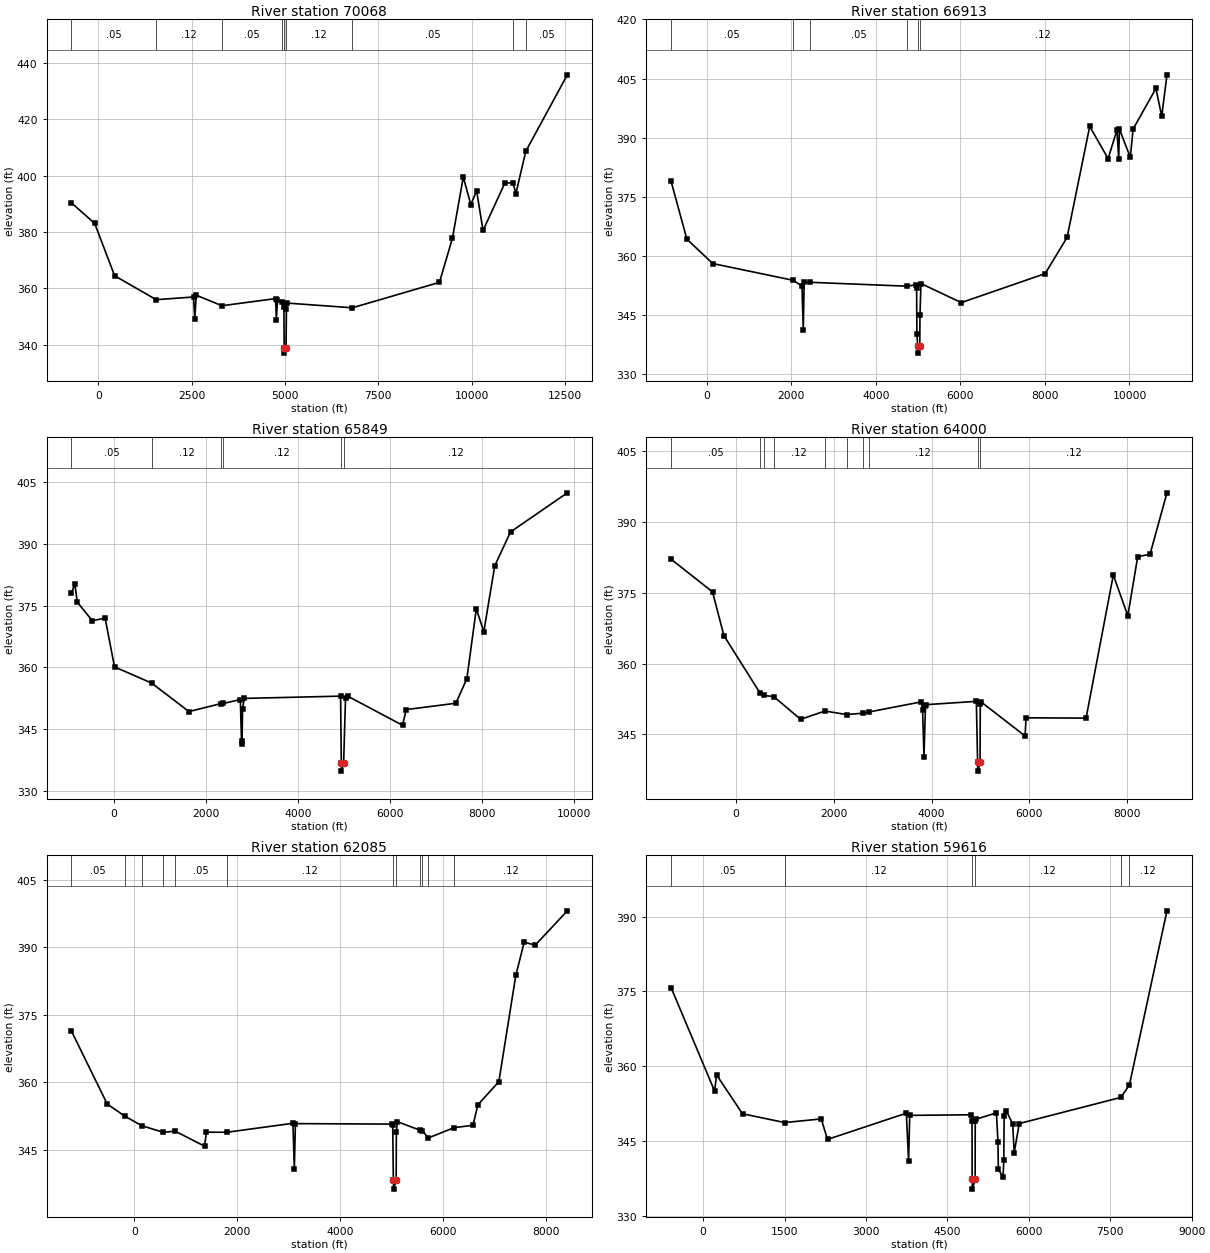
Type RM Length L Ch R = 1 ,70068   ,3155,3155,3155
BEGIN DESCRIPTION:
Kings Creek 139.0
END DESCRIPTION:
XS GIS Cut Line= 3
      2648403.66      6870787.15      2642725.59        6870086.
      2635425.95      6868110.99
#Sta/Elev= 30
  -721.2   390.4   -98.8  383.09   435.4   364.5  1549.2  356.02  2549.1  356.97
  2581.4  349.21  2621.7  357.61  3310.6  353.87  4747.7   356.4  4767.8  348.79
  4798.1  356.05  4907.1  355.16  4969.4  353.54  4977.4  338.94  4981.4  337.04
  5027.4  338.94  5037.1  352.59  5051.4  354.81  6803.6  353.14  9136.7  362.17
  9485.3  377.88  9775.3  399.54  9977.4  389.77 10131.7  394.71 10303.7   380.6
 10892.7  397.52 11106.2  397.43 11184.2  393.69 11449.5  408.72 12562.1  435.85
#Mann= 9 ,-1 , 0
  -721.2     .05       0  1549.2     .12       0  3310.6     .05       0
  4907.1     .12       0  4977.4     .07       0  5027.4     .12       0
  6803.6     .05       0 11106.2     .12       0 11449.5     .05       0
Bank Sta=4977.4,5027.4
XS Rating Curve= 0 ,0
Exp/Cntr=0.3,0.1

Type RM Length L Ch R = 1 ,66913   ,1064,1064,1064
BEGIN DESCRIPTION:
Kings Creek 138.0
END DESCRIPTION:
XS GIS Cut Line= 4
       2648667.5      6868167.36      2643789.63      6868654.57
      2643009.43      6868127.84      2637223.92       6867037.8
#Sta/Elev= 30
  -843.5  378.95  -470.2  364.28   142.9   358.1  2047.6  353.85  2253.3  352.37
  2283.5  341.33  2303.6  353.38  2441.3  353.35    4746  352.36  4955.9  352.75
  4964.7  351.85  4970.8  340.19  4989.4  337.29  4993.4  335.39  5039.4  337.29
  5044.2  344.98  5066.8  353.03  6021.1   348.2  8005.4  355.55    8525  364.74
  9059.7  392.87  9494.5  384.71  9704.3  391.95  9745.5  384.68  9761.8  392.24
 10020.2  385.01 10086.6  392.22 10626.3   402.5 10763.1  395.44 10887.3  405.95
#Mann= 6 ,-1 , 0
  -843.5     .05       0  2047.6     .12       0  2441.3     .05       0
    4746     .12       0  4989.4     .07       0  5039.4     .12       0
Bank Sta=4989.4,5039.4
XS Rating Curve= 0 ,0
Exp/Cntr=0.3,0.1

Type RM Length L Ch R = 1 ,65849   ,1849,1849,1849
BEGIN DESCRIPTION:
Kings Creek 132.0
END DESCRIPTION:
XS GIS Cut Line= 4
      2648968.79      6867871.15      2645396.13      6867030.95
      2643159.12      6867277.58      2638513.07      6865839.91
#Sta/Elev= 30
  -920.7  378.07  -845.9  380.18  -794.6  375.81  -466.2  371.31  -188.5  371.94
    15.5  360.13   823.3   356.2  1635.2   349.3  2336.9  351.25  2378.1  351.26
    2752  352.21  2779.7  341.38  2789.8  342.15  2800.2  350.01  2840.1  352.49
  4932.7  353.04    4948  336.77    4952  334.87    4998  336.77  5039.5  352.63
    5087  353.04  6280.3  345.98  6358.7  349.78    7439  351.32  7677.8  357.24
  7883.9  374.17    8047  368.65  8285.8  384.65  8627.7  392.82  9863.4   402.3
#Mann= 6 ,-1 , 0
  -920.7     .05       0   823.3     .12       0  2336.9     .05       0
  2378.1     .12       0    4948     .07       0    4998     .12       0
Bank Sta=4948,4998
XS Rating Curve= 0 ,0
Exp/Cntr=0.3,0.1

Type RM Length L Ch R = 1 ,64000   ,1915,1915,1915
BEGIN DESCRIPTION:
Kings Creek 126.0
END DESCRIPTION:
XS GIS Cut Line= 4
       2649255.2      6867832.08      2644971.36      6865983.12
      2643332.11      6866205.55      2639541.68      6865826.87
#Sta/Elev= 30
 -1320.1  382.15  -474.4  375.22  -241.1  365.94   499.1  353.72   569.9  353.25
   777.9  353.01  1325.7  348.18  1821.5  349.95  2264.3   349.2  2598.5  349.49
  2724.7  349.75  3785.1  351.88  3816.9  350.21  3845.6   340.3  3875.9  350.94
  3889.4   351.3  4915.3     352  4940.8   339.1  4944.8   337.2  4990.8   339.1
  4995.5  351.38  5006.1  351.93  5910.6  344.65  5930.7  348.51  7156.8  348.44
    7713   378.8  8009.7  370.15  8210.8  382.67  8463.3   383.2  8809.3  396.23
#Mann= 10 ,-1 , 0
 -1320.1     .05       0   499.1     .12       0   569.9     .05       0
   777.9     .12       0  1821.5     .05       0  2264.3     .12       0
  2598.5     .05       0  2724.7     .12       0  4940.8     .07       0
  4990.8     .12       0
Bank Sta=4940.8,4990.8
XS Rating Curve= 0 ,0
Exp/Cntr=0.3,0.1

Type RM Length L Ch R = 1 ,62085   ,2469,2469,2469
BEGIN DESCRIPTION:
Kings Creek 123.0
END DESCRIPTION:
XS GIS Cut Line= 4
      2648395.87      6867441.48      2644294.27      6865045.62
       2642806.1      6865067.86      2639424.53        6864655.
#Sta/Elev= 30
 -1225.2  371.39  -530.5  355.22  -191.9  352.54   147.5  350.38   559.4  348.93
   791.1  349.19    1363  345.85  1400.2  348.95  1797.9  348.94  3082.5  350.93
  3109.8  340.84  3131.3  350.86  5013.2  350.75  5023.4  350.52  5036.2  338.32
  5040.6  336.32  5091.1  338.32  5093.9  349.02  5115.1  351.28  5559.1  349.37
  5598.9  349.29  5715.8  347.67  6212.8  349.95  6584.9  350.49  6679.7  355.04
  7087.5  360.15  7418.8  383.82  7581.9  391.16  7793.8  390.44  8419.9  398.08
#Mann= 12 ,-1 , 0
 -1225.2     .05       0  -191.9     .12       0   147.5     .05       0
   559.4     .12       0   791.1     .05       0  1797.9     .12       0
  5036.2     .07       0  5091.1     .12       0  5559.1      .1       0
  5598.9     .12       0  5715.8     .05       0  6212.8     .12       0
Bank Sta=5036.2,5091.1
XS Rating Curve= 0 ,0
Exp/Cntr=0.3,0.1

Type RM Length L Ch R = 1 ,59616   ,2217,2217,2217
BEGIN DESCRIPTION:
Kings Creek 117.0
END DESCRIPTION:
XS GIS Cut Line= 4
       2648695.3      6867402.39      2644026.53      6864326.19
      2643174.48      6863639.37      2640726.02        6863711.
#Sta/Elev= 30
  -591.1  375.75   210.4  355.02   246.4  358.26   724.3  350.47  1501.6  348.71
  2174.4  349.44  2290.2  345.33  3741.7  350.59  3783.9   341.1  3804.9  350.15
  4940.3  350.27  4952.7  349.05    4955  337.37  4959.4  335.37  5009.9  337.37
  5011.7  348.95  5018.1  349.35    5402  350.65  5430.7  344.89  5437.4  339.36
  5523.5  337.78  5537.9  341.15  5544.3  350.09  5587.5     351  5701.1  348.44
  5729.8  342.69  5822.6  348.51  7690.9  353.74  7850.8  356.19  8543.9  391.14
#Mann= 6 ,-1 , 0
  -591.1     .05       0  1501.6     .12       0    4955     .07       0
  5009.9     .12       0  7690.9     .05       0  7850.8     .12       0
Bank Sta=4955,5009.9
XS Rating Curve= 0 ,0
Exp/Cntr=0.3,0.1