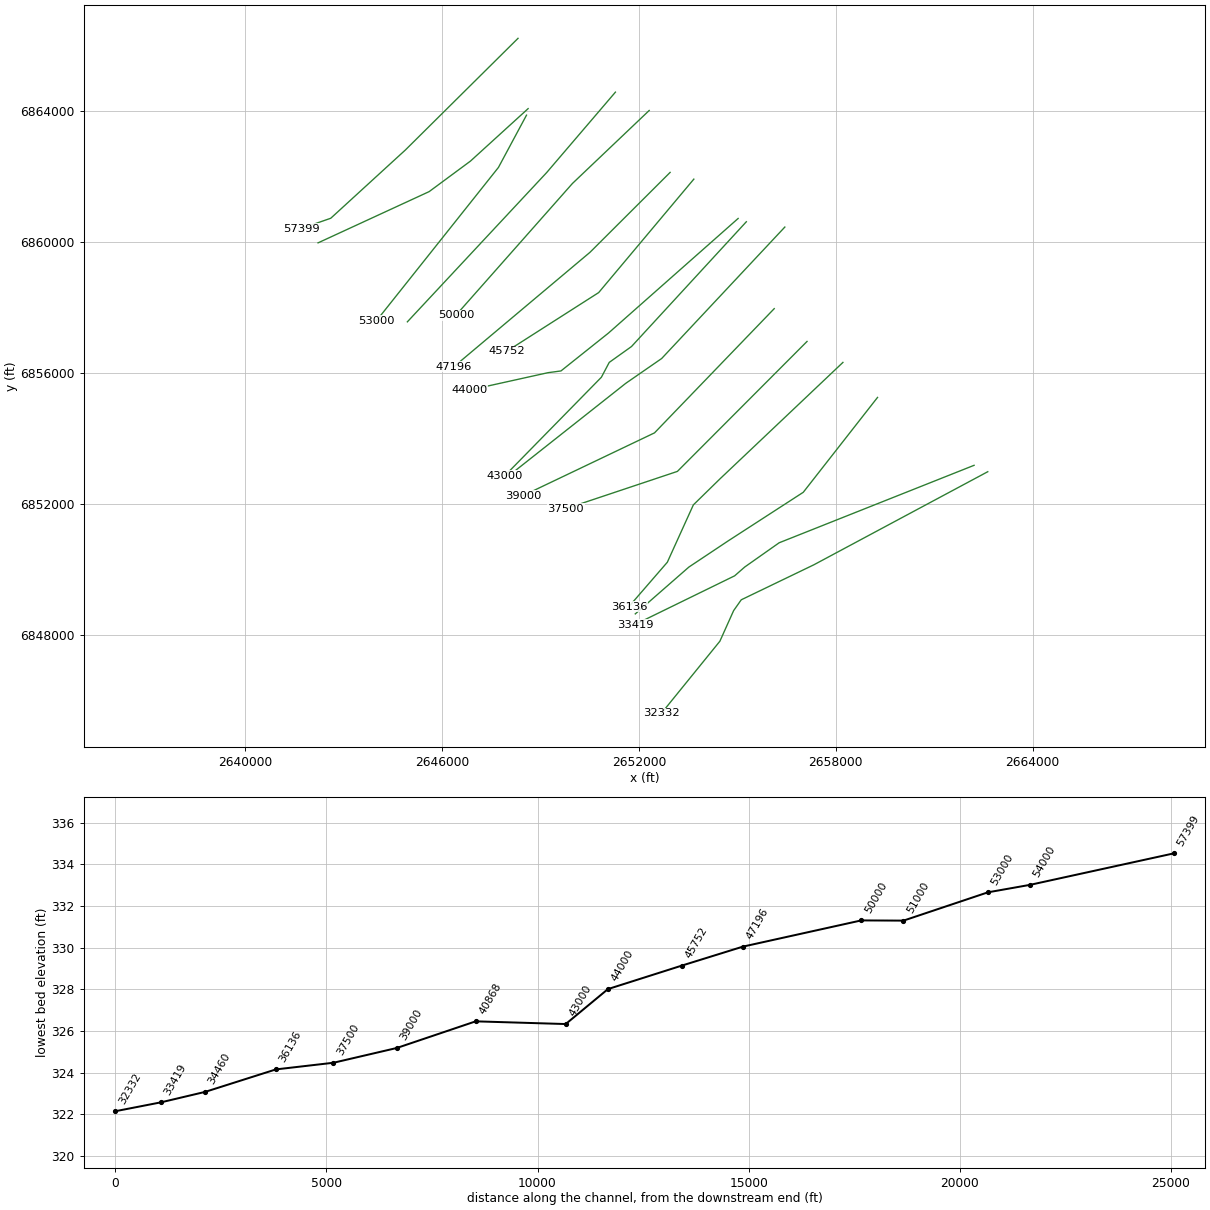
HEC-RAS study Kings Creek.prj: Kings Creek Base Level Engineering

--- Kings Creek.g01 (geometry) --- (continued)

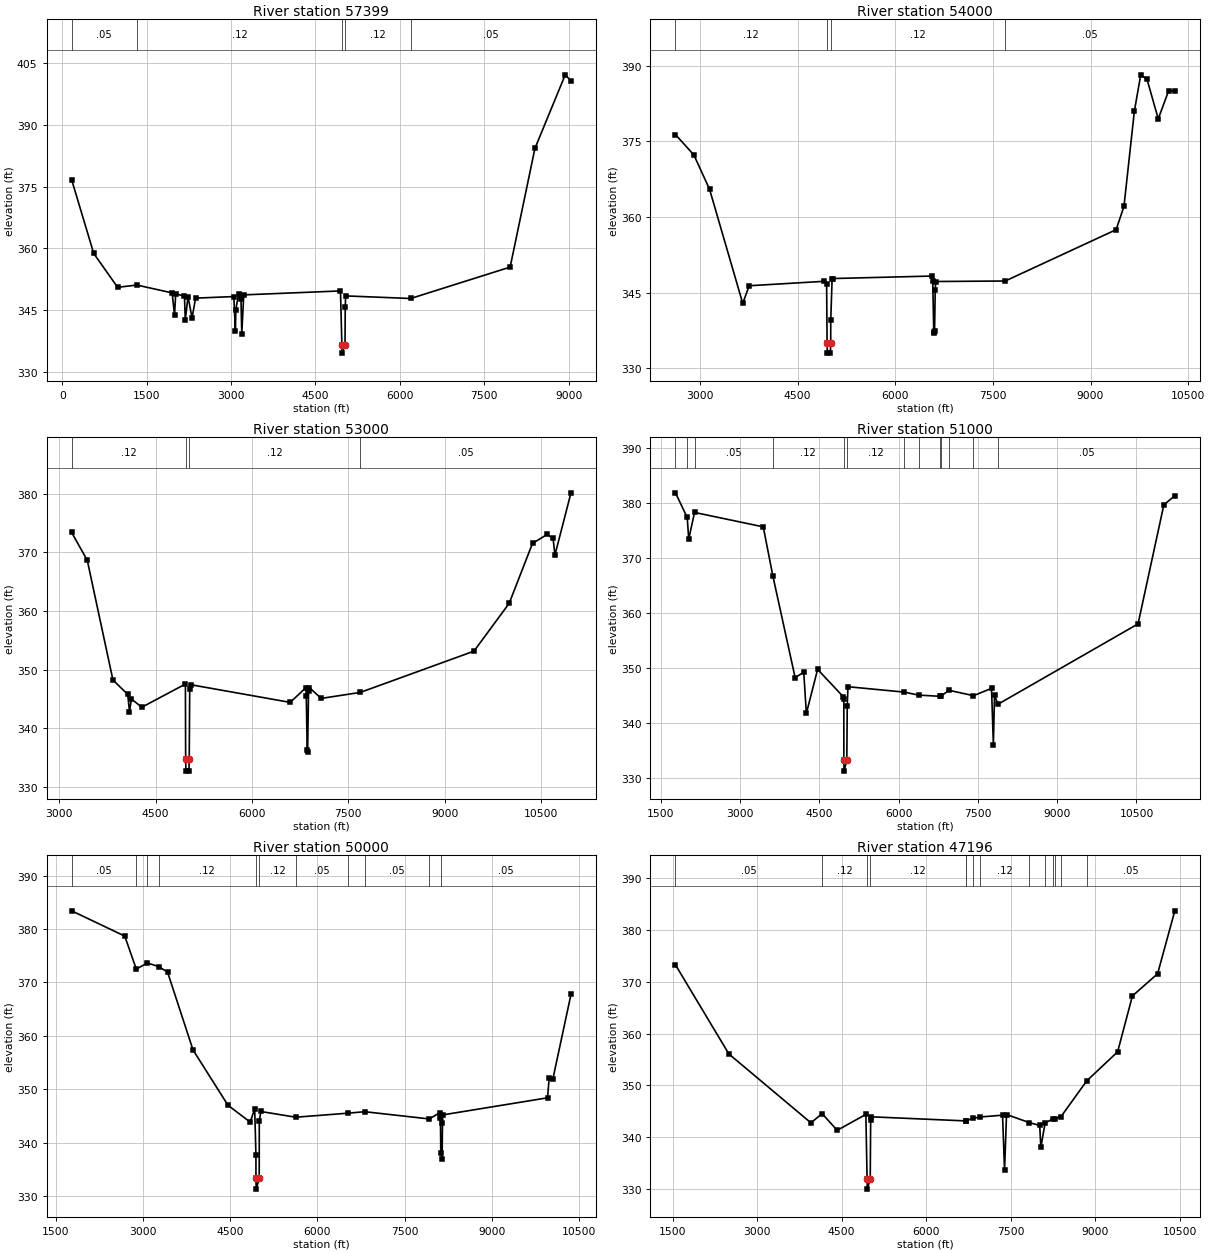
Type RM Length L Ch R = 1 ,57399   ,3399,3399,3399
BEGIN DESCRIPTION:
Kings Creek 115.0
END DESCRIPTION:
XS GIS Cut Line= 4
      2648317.71      6866204.48      2644886.85      6862801.35
      2642611.13       6860717.9      2641709.71      6860404.04
#Sta/Elev= 30
   167.6  376.73   560.2  358.78   984.5  350.54  1327.4  351.09  1953.2  349.18
  1995.6  343.78  2016.8  348.97  2172.4  348.38  2186.5  342.63  2236.1  348.26
  2306.8  343.09  2370.4  347.91  3049.2  348.29  3077.5  339.81  3084.6  345.14
  3134.1  348.91  3176.5  347.68  3190.6  339.27    3226   348.7  4944.3  349.66
  4969.3  336.53  4973.7  334.53  5024.9  336.53  5028.9  345.68  5036.3  348.45
  6191.8  347.82  7959.2  355.46  8399.2  384.33  8937.7  402.23  9039.9  400.78
#Mann= 5 ,-1 , 0
   167.6     .05       0  1327.4     .12       0  4969.3     .07       0
  5024.9     .12       0  6191.8     .05       0
Bank Sta=4969.3,5024.9
XS Rating Curve= 0 ,0
Exp/Cntr=0.3,0.1

Type RM Length L Ch R = 1 ,54000   ,1000,1000,1000
BEGIN DESCRIPTION:
Kings Creek 108.0
END DESCRIPTION:
XS GIS Cut Line= 4
      2648626.02      6864061.02      2646868.89      6862461.09
      2645609.38        6861530.      2642223.96       6859967.5
#Sta/Elev= 30
  2623.6  376.33  2907.1  372.27  3147.6  365.48  3657.1  342.88  3756.4  346.37
  4909.8  347.25  4945.6  346.75  4952.9  335.02  4957.4  333.02  5004.1  333.02
  5008.6  335.02  5009.2  339.56    5030  347.69  5044.7   347.8  6560.2  348.29
  6575.7  347.33    6592  337.19  6598.6  337.02  6604.1  337.46  6614.1  345.44
  6621.6  347.21  7689.9  347.31  9393.4  357.48  9513.6  362.08  9674.2  381.02
  9771.5  388.16  9868.8  387.25 10040.4  379.43   10201  385.03 10294.9  384.98
#Mann= 4 ,-1 , 0
  2623.6     .12       0  4952.9     .07       0  5008.6     .12       0
  7689.9     .05       0
Bank Sta=4952.9,5008.6
XS Rating Curve= 0 ,0
Exp/Cntr=0.3,0.1

Type RM Length L Ch R = 1 ,53000   ,2000,2000,2000
BEGIN DESCRIPTION:
Kings Creek 106.0
END DESCRIPTION:
XS GIS Cut Line= 3
        2648576.        6863861.      2647721.63      6862268.05
      2644007.79      6857597.67
#Sta/Elev= 30
  3192.4  373.42    3436  368.67  3835.6  348.22  4065.5  345.77  4093.1  342.83
  4122.9  344.99  4284.7  343.57  4963.7  347.53  4967.6  334.66  4972.1  332.66
  5018.8  332.66  5023.3  334.66  5030.7  346.67  5051.5  347.41  6595.6   344.4
  6837.5  346.89  6845.6   345.5    6860   336.2  6866.4  335.93  6880.8  346.36
  6895.2   346.9  7079.4  345.08  7685.9   346.1  9456.5  353.15 10004.5  361.31
   10368  371.56 10595.5  373.08 10688.4   372.4 10717.2  369.57   10967  380.19
#Mann= 4 ,-1 , 0
  3192.4     .12       0  4967.6     .07       0  5023.3     .12       0
  7685.9     .05       0
Bank Sta=4967.6,5023.3
XS Rating Curve= 0 ,0
Exp/Cntr=0.3,0.1

Type RM Length L Ch R = 1 ,51000   ,1000,1000,1000
BEGIN DESCRIPTION:
Kings Creek 102.0
END DESCRIPTION:
XS GIS Cut Line= 3
      2651286.45      6864563.84      2649191.26      6862111.35
      2644945.29      6857558.62
#Sta/Elev= 30
  1774.4  381.84  1997.1  377.36  2025.3  373.42  2135.2  378.28    3436  375.66
  3618.4  366.71  4039.8  348.27  4202.3  349.27  4251.7  341.79  4464.7  349.78
  4954.3  344.77    4961  344.42  4961.4   333.3  4965.9   331.3  5017.5   333.3
  5025.4  343.04  5039.5  346.63  6103.9  345.65  6375.2  345.11  6788.7  344.88
  6792.7  344.88    6952  345.98  7414.8     345  7756.3  346.33  7791.5   336.1
    7813  345.05  7879.1  343.45 10529.8  358.04 11017.8  379.66 11225.4  381.31
#Mann= 13 ,-1 , 0
  1774.4     .05       0  1997.1     .12       0  2135.2     .05       0
  3618.4     .12       0  4961.4     .07       0  5017.5     .12       0
  6103.9     .05       0  6375.2     .12       0  6788.7     .05       0
  6792.7     .12       0    6952     .05       0  7414.8     .12       0
  7879.1     .05       0
Bank Sta=4961.4,5017.5
XS Rating Curve= 0 ,0
Exp/Cntr=0.3,0.1

Type RM Length L Ch R = 1 ,50000   ,2804,2804,2804
BEGIN DESCRIPTION:
Kings Creek 100.0
END DESCRIPTION:
XS GIS Cut Line= 3
      2652315.08      6864003.94      2649976.47      6861778.59
      2646426.01      6857761.01
#Sta/Elev= 30
  1771.8   383.4  2685.6  378.67  2883.8  372.49  3074.8  373.64  3266.2  372.97
  3421.3  371.95  3859.8  357.36  4461.2  347.01    4843  343.86  4920.7   346.3
  4942.1   337.7  4942.4  333.31  4946.9  331.31  4998.5  333.31    5000  344.05
  5026.8  345.84  5626.3  344.77  6531.1  345.53  6813.6   345.8  7922.6  344.45
  8101.8  345.59    8116  344.55  8122.1  338.15  8144.5  336.95  8151.1  343.74
  8158.7  345.21    9958   348.4  9986.5   352.1   10050  351.93 10361.6  367.76
#Mann= 11 ,-1 , 0
  1771.8     .05       0  2883.8     .12       0  3074.8     .05       0
  3266.2     .12       0  4942.4     .07       0  4998.5     .12       0
  5626.3     .05       0  6531.1     .12       0  6813.6     .05       0
  7922.6     .12       0  8122.1     .05       0
Bank Sta=4942.4,4998.5
XS Rating Curve= 0 ,0
Exp/Cntr=0.3,0.1

Type RM Length L Ch R = 1 ,47196   ,1444,1444,1444
BEGIN DESCRIPTION:
Kings Creek 95.0
END DESCRIPTION:
XS GIS Cut Line= 3
      2652953.16      6862115.97      2650509.61      6859677.79
      2646364.55      6856191.43
#Sta/Elev= 30
  1548.1  373.21  2497.1  356.06  3953.8  342.81  4152.9  344.58  4420.5  341.37
  4929.6  344.43    4951  332.05  4955.5  330.05  5007.2  332.05  5014.8  343.44
  5021.3  343.97  6700.2  343.18  6703.7  343.17  6825.1  343.66  6954.2  343.93
  7356.8  344.28  7392.3  333.64  7427.5  344.41  7827.9  342.87  8016.7   342.3
  8037.5   338.1    8113   342.8  8250.9  343.54  8281.3  343.64  8395.3  344.01
  8853.5   350.9  9400.5  356.47  9663.3  367.23 10110.7   371.5 10416.3  383.61
#Mann= 14 ,-1 , 0
  1548.1     .05       0  4152.9     .12       0    4951     .07       0
  5007.2     .12       0  6700.2     .05       0  6703.7      .1       0
  6825.1     .05       0  6954.2     .12       0  7827.9     .05       0
    8113      .1       0  8250.9     .05       0  8281.3      .1       0
  8395.3     .12       0  8853.5     .05       0
Bank Sta=4951,5007.2
XS Rating Curve= 0 ,0
Exp/Cntr=0.3,0.1

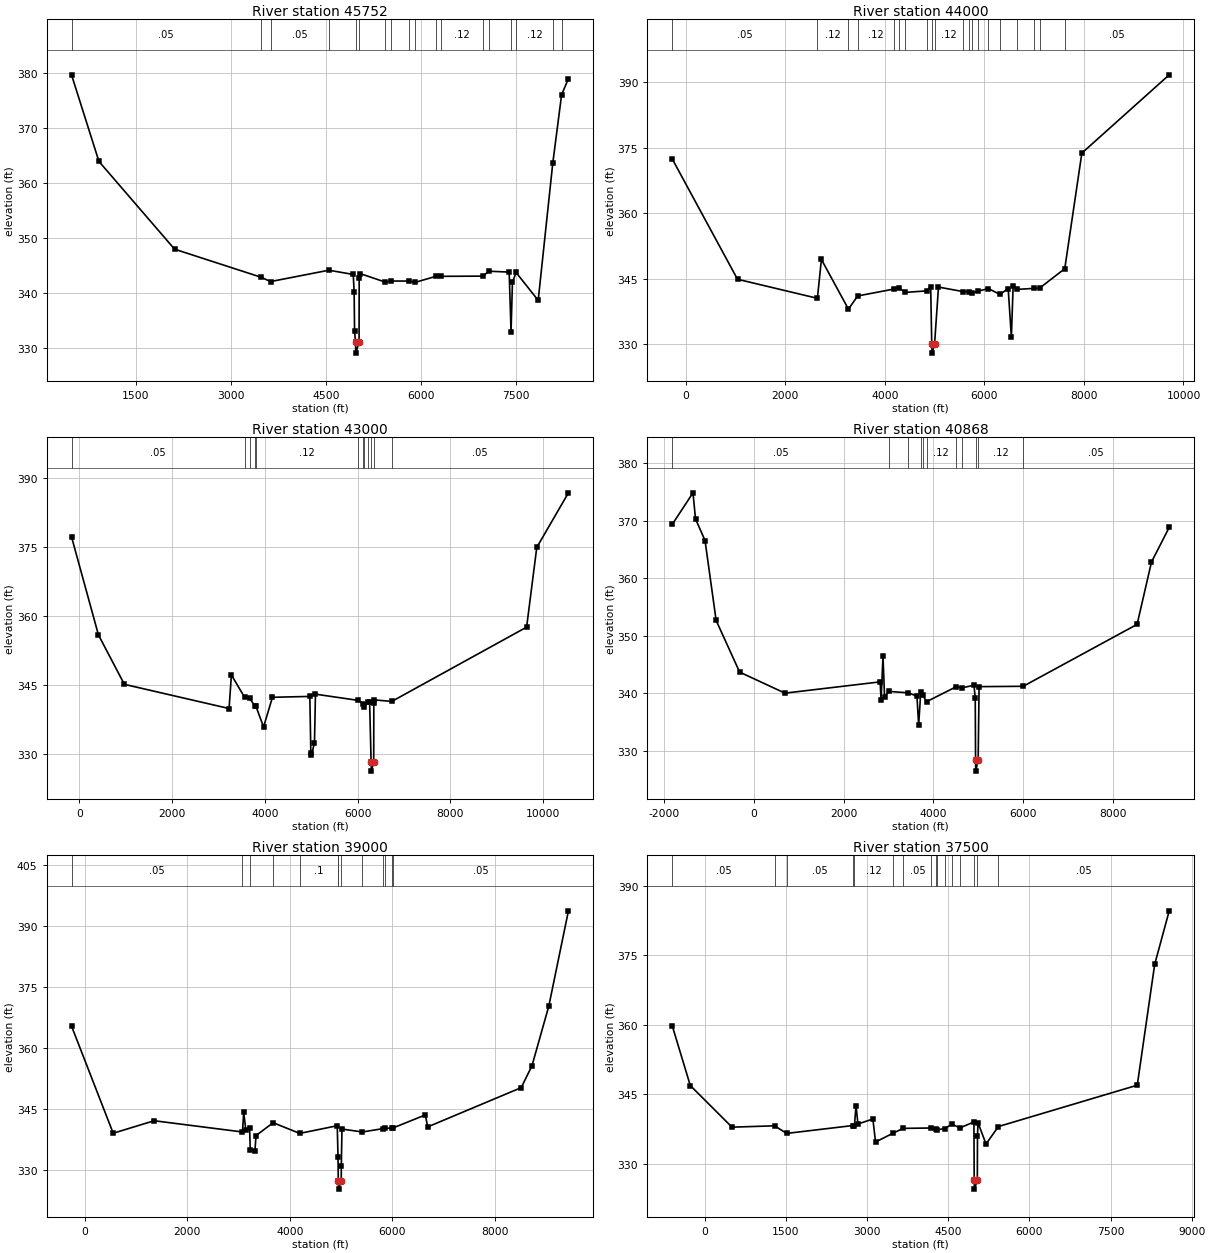
Type RM Length L Ch R = 1 ,45752   ,1752,1752,1752
BEGIN DESCRIPTION:
Kings Creek 91.0
END DESCRIPTION:
XS GIS Cut Line= 3
      2653675.99      6861910.99      2650775.89      6858450.95
      2647976.04      6856661.02
#Sta/Elev= 30
   485.3  379.66   917.9  363.94  2110.9  348.01  3471.5  342.93  3625.2  342.13
  4543.7  344.19    4929  343.42  4943.3  340.16  4949.8  333.19  4964.6  331.14
  4969.1  329.14  5020.8  331.14  5022.7  342.75  5035.5  343.59  5432.3  342.04
  5516.7  342.23  5809.2  342.22    5901  341.97  6230.1  343.07  6308.2  343.08
  6970.1  343.12    7072  344.01  7388.5  343.85    7418  333.04  7440.1     342
  7497.5  343.78  7846.1  338.72  8075.8  363.58  8215.1  376.02  8323.1  378.98
#Mann= 18 ,-1 , 0
   485.3     .05       0  3471.5     .12       0  3625.2     .05       0
  4543.7     .12       0  4964.6     .07       0  5020.8     .12       0
  5432.3      .1       0  5516.7     .12       0  5809.2      .1       0
    5901     .12       0  6230.1      .1       0  6308.2     .12       0
  6970.1      .1       0    7072     .12       0    7418      .1       0
  7497.5     .12       0  8075.8     .05       0  8215.1     .12       0
Bank Sta=4964.6,5020.8
XS Rating Curve= 0 ,0
Exp/Cntr=0.3,0.1

Type RM Length L Ch R = 1 ,44000   ,1000,1000,1000
BEGIN DESCRIPTION:
Kings Creek 88.0
END DESCRIPTION:
XS GIS Cut Line= 5
      2655026.02      6860711.02      2651075.52      6857217.39
       2649626.3      6856061.25      2649232.34      6856008.34
      2646828.34      6855475.65
#Sta/Elev= 30
  -273.7  372.41  1036.7  344.91  2642.5  340.55    2723  349.44  3266.4  338.07
  3451.9  341.09  4181.3  342.67  4290.1  342.84    4413  341.91  4838.4  342.25
  4919.3  343.25  4940.8  330.01  4945.3  328.01    4997  330.01  5076.1  343.12
  5571.1  342.09    5685  342.08  5746.5  341.72  5861.4  342.17    6081  342.77
  6310.6  341.45  6477.2  342.76  6541.2  331.68  6576.5  343.34    6664   342.6
  6996.3  342.82  7111.9  342.91  7614.3  347.33  7957.5  373.77  9713.7  391.68
#Mann= 20 ,-1 , 0
  -273.7     .05       0  2642.5     .12       0  3266.4      .1       0
  3451.9     .12       0  4181.3     .12       0  4290.1      .1       0
    4413     .12       0  4838.4      .1       0  4940.8     .07       0
    4997     .12       0  5571.1      .1       0    5685     .12       0
  5746.5      .1       0  5861.4      .1       0    6081     .12       0
  6310.6      .1       0    6664     .12       0  6996.3     .05       0
  7111.9     .12       0  7614.3     .05       0
Bank Sta=4940.8,4997
XS Rating Curve= 0 ,0
Exp/Cntr=0.3,0.1

Type RM Length L Ch R = 1 ,43000   ,2132,2132,2132
BEGIN DESCRIPTION:
Kings Creek 86.0
END DESCRIPTION:
XS GIS Cut Line= 5
      2655276.02      6860611.03      2651776.84      6856806.24
      2651097.66      6856321.67      2650859.25      6855869.89
      2647920.75      6852871.33
#Sta/Elev= 30
  -169.2  377.21   411.3   355.9   970.5  345.17  3227.6  339.92  3277.6  347.21
  3561.5  342.38  3672.4  342.11  3788.5   340.4  3808.4  340.37  3971.2  335.92
  4162.3  342.36  4968.7  342.55  4990.3  330.19  5003.8  329.75  5068.9  332.54
  5089.8  343.04    6010  341.69  6109.9     341  6142.3  340.32    6214  341.29
  6257.4  341.31  6289.7  328.33  6294.2  326.33  6345.9  328.33  6347.9   341.1
  6353.8   341.8  6734.9  341.46    9642  357.59  9861.1   374.9 10543.5  386.75
#Mann= 12 ,-1 , 0
  -169.2     .05       0  3561.5      .1       0  3672.4     .12       0
  3788.5      .1       0  3808.4     .12       0    6010      .1       0
  6109.9     .12       0  6142.3      .1       0    6214     .12       0
  6289.7     .07       0  6345.9     .12       0  6734.9     .05       0
Bank Sta=6289.7,6345.9
XS Rating Curve= 0 ,0
Exp/Cntr=0.3,0.1

Type RM Length L Ch R = 1 ,40868   ,1868,1868,1868
BEGIN DESCRIPTION:
Kings Creek 82.0
END DESCRIPTION:
XS GIS Cut Line= 4
      2656449.25       6860449.3      2652695.84      6856440.62
      2651602.18      6855684.13      2648260.04      6853041.15
#Sta/Elev= 30
 -1821.4  369.38 -1360.3  374.85 -1303.6  370.31 -1091.6  366.56    -844  352.67
  -320.3  343.68   691.3  340.02  2813.8  341.98  2834.8  338.81  2877.3  346.45
  2912.9  339.29  3002.2  340.33  3446.2  340.07  3634.4  339.49  3673.1  334.46
    3720  340.26  3759.6  339.69  3850.5  338.54  4507.2  341.12  4634.2  340.93
  4906.5   341.4  4934.6  339.18  4942.1  328.46  4946.8  326.46  4999.9  328.46
  5020.6  341.15  6004.5  341.21  8544.7  351.98  8865.3  362.82  9260.9  368.84
#Mann= 11 ,-1 , 0
 -1821.4     .05       0  3002.2     .12       0  3446.2      .1       0
    3720     .12       0  3759.6      .1       0  3850.5     .12       0
  4507.2      .1       0  4634.2     .12       0  4942.1     .07       0
  4999.9     .12       0  6004.5     .05       0
Bank Sta=4942.1,4999.9
XS Rating Curve= 0 ,0
Exp/Cntr=0.3,0.1

Type RM Length L Ch R = 1 ,39000   ,1500,1500,1500
BEGIN DESCRIPTION:
Kings Creek 78.0
END DESCRIPTION:
XS GIS Cut Line= 3
        2656126.        6857961.      2652477.04      6854172.37
      2648476.04      6852261.02
#Sta/Elev= 30
  -260.1  365.33   553.2  338.94  1352.3  342.02  3074.9  339.25  3099.4  344.07
  3141.6  339.62    3214  340.32  3226.5  334.92  3318.6  334.66  3339.6  338.37
    3674  341.53  4192.8   338.9  4923.9  340.79    4939  333.18  4944.6  327.18
  4949.3  325.18  5002.4  327.18  5003.3  330.83  5016.3  339.97  5414.1  339.25
  5818.2  340.08  5851.4  340.11  5999.3  340.26  6019.1  340.28  6642.8  343.45
  6688.2   340.5  8513.3  350.17    8723  355.56  9051.6  370.26  9434.1   393.7
#Mann= 13 ,-1 , 0
  -260.1     .05       0  3074.9      .1       0    3214     .12       0
    3674     .05       0  4192.8      .1       0    4939     .12       0
  4944.6     .07       0  5002.4     .12       0  5414.1     .05       0
  5818.2     .12       0  5851.4     .05       0  5999.3     .12       0
  6019.1     .05       0
Bank Sta=4944.6,5002.4
XS Rating Curve= 0 ,0
Exp/Cntr=0.3,0.1

Type RM Length L Ch R = 1 ,37500   ,1364,1364,1364
BEGIN DESCRIPTION:
Kings Creek 75.0
END DESCRIPTION:
XS GIS Cut Line= 3
      2657125.97      6856960.97      2653175.17      6852997.84
      2649776.04      6851861.01
#Sta/Elev= 30
    -596   359.7  -263.7  346.84     507  337.85  1294.2  338.14  1516.5   336.5
  2733.5  338.19  2768.1  338.12  2798.1  342.52  2833.4  338.53  3109.2  339.61
  3158.7  334.64  3482.5  336.55  3669.8  337.59    4192  337.67  4273.9  337.43
  4291.5  337.25  4433.2  337.55  4574.8  338.48  4716.5  337.69    4976  338.97
  4981.4  326.47  4986.1  324.47  5039.3  326.47  5041.9  335.96  5051.9  338.78
  5199.9  334.21  5428.2  337.98  7993.8  346.91  8315.8     373  8584.2  384.56
#Mann= 16 ,-1 , 0
    -596     .05       0  1294.2     .12       0  1516.5     .05       0
  2733.5      .1       0  2768.1     .12       0  3482.5      .1       0
  3669.8     .05       0    4192      .1       0  4273.9     .12       0
  4291.5      .1       0  4433.2     .12       0  4574.8     .05       0
  4716.5     .12       0  4981.4     .07       0  5039.3     .12       0
  5428.2     .05       0
Bank Sta=4981.4,5039.3
XS Rating Curve= 0 ,0
Exp/Cntr=0.3,0.1

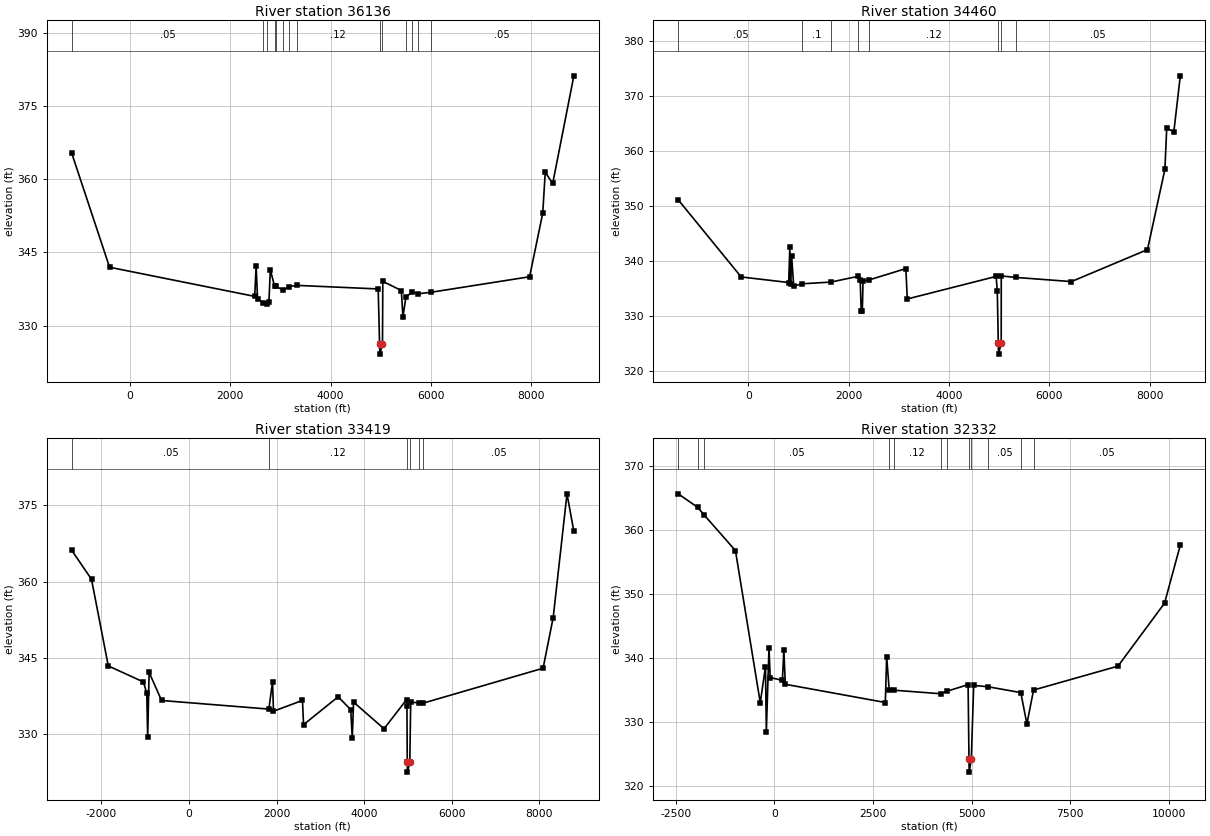
Type RM Length L Ch R = 1 ,36136   ,1676,1676,1676
BEGIN DESCRIPTION:
Mapping XS 8c1aa43f
END DESCRIPTION:
XS GIS Cut Line= 5
      2658220.06      6856321.67      2654483.08        6852780.
      2653661.18      6851976.11      2652868.49      6850227.92
      2651697.56      6848874.84
#Sta/Elev= 30
 -1157.2  365.34  -404.1  341.97    2489  335.99  2517.3  342.26  2545.6  335.48
  2662.1   334.7  2726.2  334.51  2772.1  334.74  2800.4  341.45  2885.5  338.06
  2905.6  338.08  3053.6  337.31  3181.2  338.02  3327.3  338.25  4950.4  337.52
  4978.1  326.15  4982.7  324.15    5036  326.15  5042.3  339.07  5411.8   337.2
  5443.2  331.79  5502.6  335.83    5624  336.91  5751.6  336.54  5992.9  336.82
  7968.1  340.02  8230.2  353.07  8279.6  361.45  8428.7  359.16    8850  381.23
#Mann= 14 ,-1 , 0
 -1157.2     .05       0  2662.1     .12       0  2726.2     .05       0
  2885.5      .1       0  2905.6     .12       0  3053.6      .1       0
  3181.2     .05       0  3327.3     .12       0  4978.1     .07       0
    5036     .12       0  5502.6      .1       0    5624     .05       0
  5751.6     .12       0  5992.9     .05       0
Bank Sta=4978.1,5036
XS Rating Curve= 0 ,0
Exp/Cntr=0.3,0.1

Type RM Length L Ch R = 1 ,34460   ,1041,1041,1041
BEGIN DESCRIPTION:
Mapping XS 1003874e
END DESCRIPTION:
XS GIS Cut Line= 5
      2659274.74      6855253.95       2657010.8      6852360.25
      2654726.32      6850881.13      2653526.13      6850081.06
       2651891.9      6848652.37
#Sta/Elev= 30
 -1395.6   351.1  -140.6  337.09   806.2  336.08   828.8  342.46   842.8  335.81
     864  340.98   906.3  335.44  1080.5  335.85  1648.4  336.16  2187.5   337.2
  2231.3  336.52  2252.1   330.9  2274.7  330.97  2288.2  336.41  2405.5  336.54
  3141.9  338.61  3170.6  333.09  4941.3  337.19  4964.6  334.55  4984.8  325.07
  4989.5  323.07  5042.8  325.07  5043.9  337.28  5338.3     337  6442.4  336.25
  7958.9  342.06  8306.3  356.67    8342  364.12  8483.8  363.46  8613.1  373.63
#Mann= 8 ,-1 , 0
 -1395.6     .05       0  1080.5      .1       0  1648.4     .12       0
  2187.5      .1       0  2405.5     .12       0  4984.8     .07       0
  5042.8     .12       0  5338.3     .05       0
Bank Sta=4984.8,5042.8
XS Rating Curve= 0 ,0
Exp/Cntr=0.3,0.1

Type RM Length L Ch R = 1 ,33419   ,1087,1087,1087
BEGIN DESCRIPTION:
Mapping XS f58342d9
END DESCRIPTION:
XS GIS Cut Line= 5
      2662217.41      6853183.63      2656276.05      6850820.98
      2655226.24      6850081.15      2654919.86      6849813.17
      2651879.97      6848327.39
#Sta/Elev= 30
 -2678.2  366.13 -2227.3  360.44 -1844.2  343.43 -1040.9  340.28  -965.6  338.06
  -944.1  329.46  -911.8  342.17  -627.2  336.64    1824  334.95  1907.8  340.35
  1929.3  334.53  2591.8  336.66  2616.1  331.89  3406.7  337.37  3694.2  334.84
  3729.2  329.19  3758.8  336.32  4454.7  331.09    4972  336.83  4978.1  335.62
    4985  324.57  4989.7  322.57    5043  324.57  5064.3  336.33  5247.9  336.18
  5341.7   336.1    8088  342.98  8318.8  352.93    8634  377.23  8790.6  369.85
#Mann= 6 ,-1 , 0
 -2678.2     .05       0    1824     .12       0    4985     .07       0
    5043     .12       0  5247.9      .1       0  5341.7     .05       0
Bank Sta=4985,5043
XS Rating Curve= 0 ,0
Exp/Cntr=0.3,0.1

Type RM Length L Ch R = 1 ,32332   ,3065,3065,3065
BEGIN DESCRIPTION:
Mapping XS e846302a
END DESCRIPTION:
XS GIS Cut Line= 6
       2662634.1      6852988.32      2657334.64      6850149.79
       2655121.1      6849082.08       2654888.6      6848751.37
      2654470.05      6847819.06      2652686.17      6845618.51
#Sta/Elev= 30
 -2439.2  365.67 -1949.7  363.57 -1791.5  362.43  -988.9  356.79  -359.2  332.99
  -227.6  338.65  -205.7  328.46  -138.5  341.59  -107.4  336.93   201.8   336.5
   237.9  341.22   276.1  335.88    2811  333.03    2845  340.21    2910  334.94
  3020.8  334.96  4215.3   334.4  4377.1   334.8  4909.4  335.82  4931.8  324.14
  4936.6  322.14  4990.5  324.14  5050.8  335.71  5416.5  335.49  6245.3  334.58
  6400.2  329.68  6569.3  334.98  8709.5  338.72  9889.2  348.56 10289.5  357.66
#Mann= 12 ,-1 , 0
 -2439.2     .05       0 -1949.7      .1       0 -1791.5     .05       0
    2910      .1       0  3020.8     .12       0  4215.3      .1       0
  4377.1     .12       0  4931.8     .07       0  4990.5     .12       0
  5416.5     .05       0  6245.3     .12       0  6569.3     .05       0
Bank Sta=4931.8,4990.5
XS Rating Curve= 0 ,0
Exp/Cntr=0.3,0.1