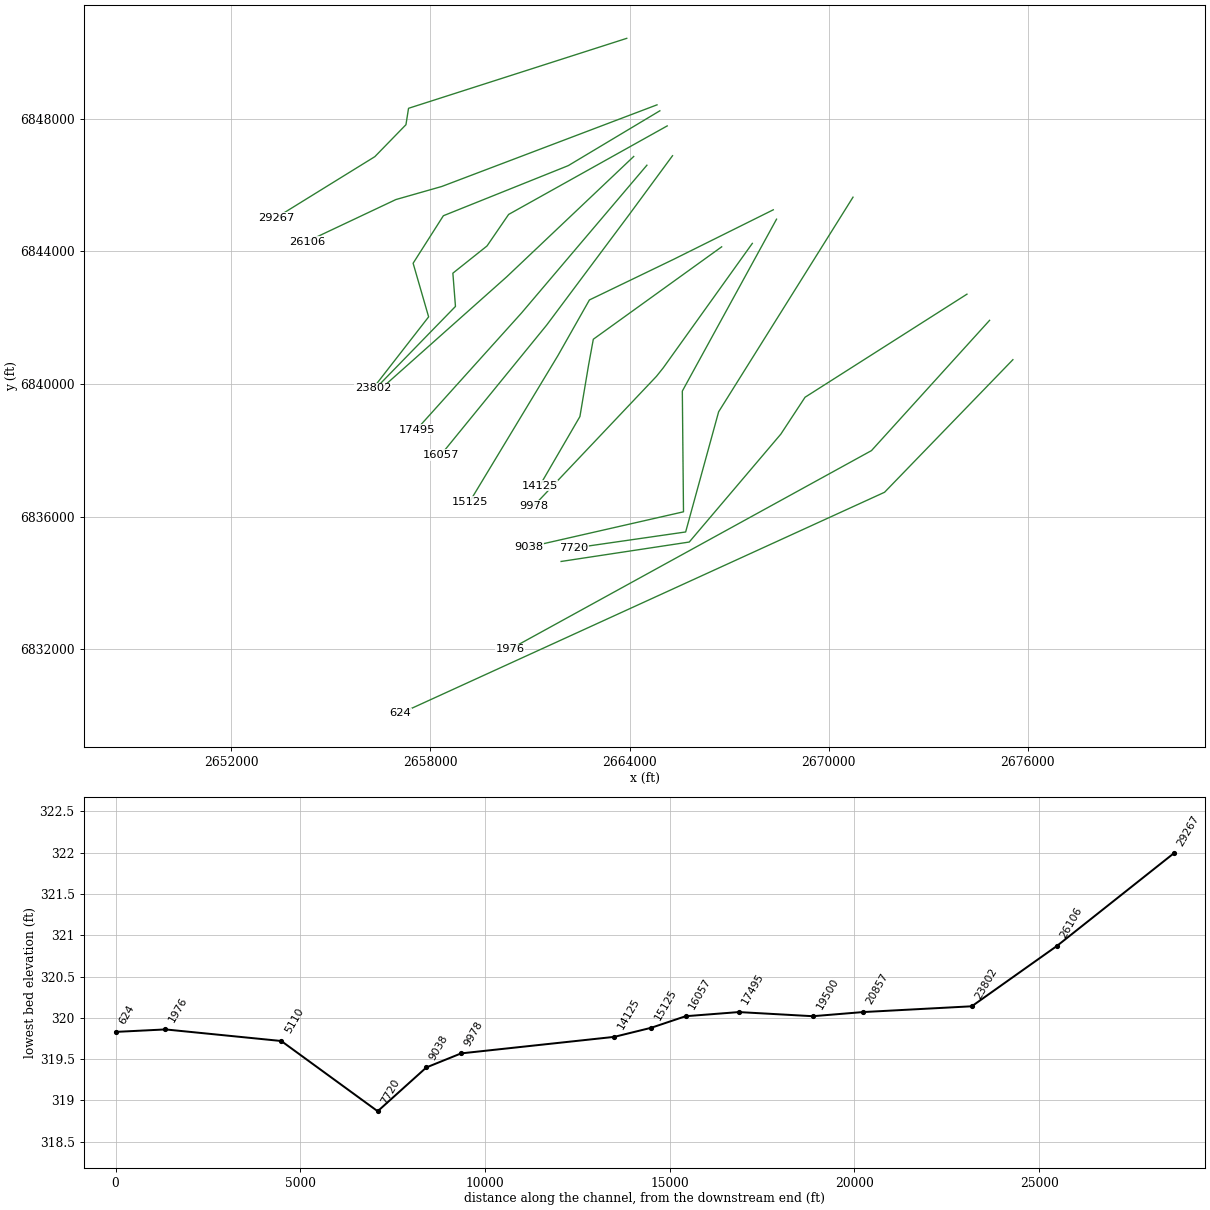
HEC-RAS study Kings Creek.prj: Kings Creek Base Level Engineering

--- Kings Creek.g01 (geometry) --- (continued)

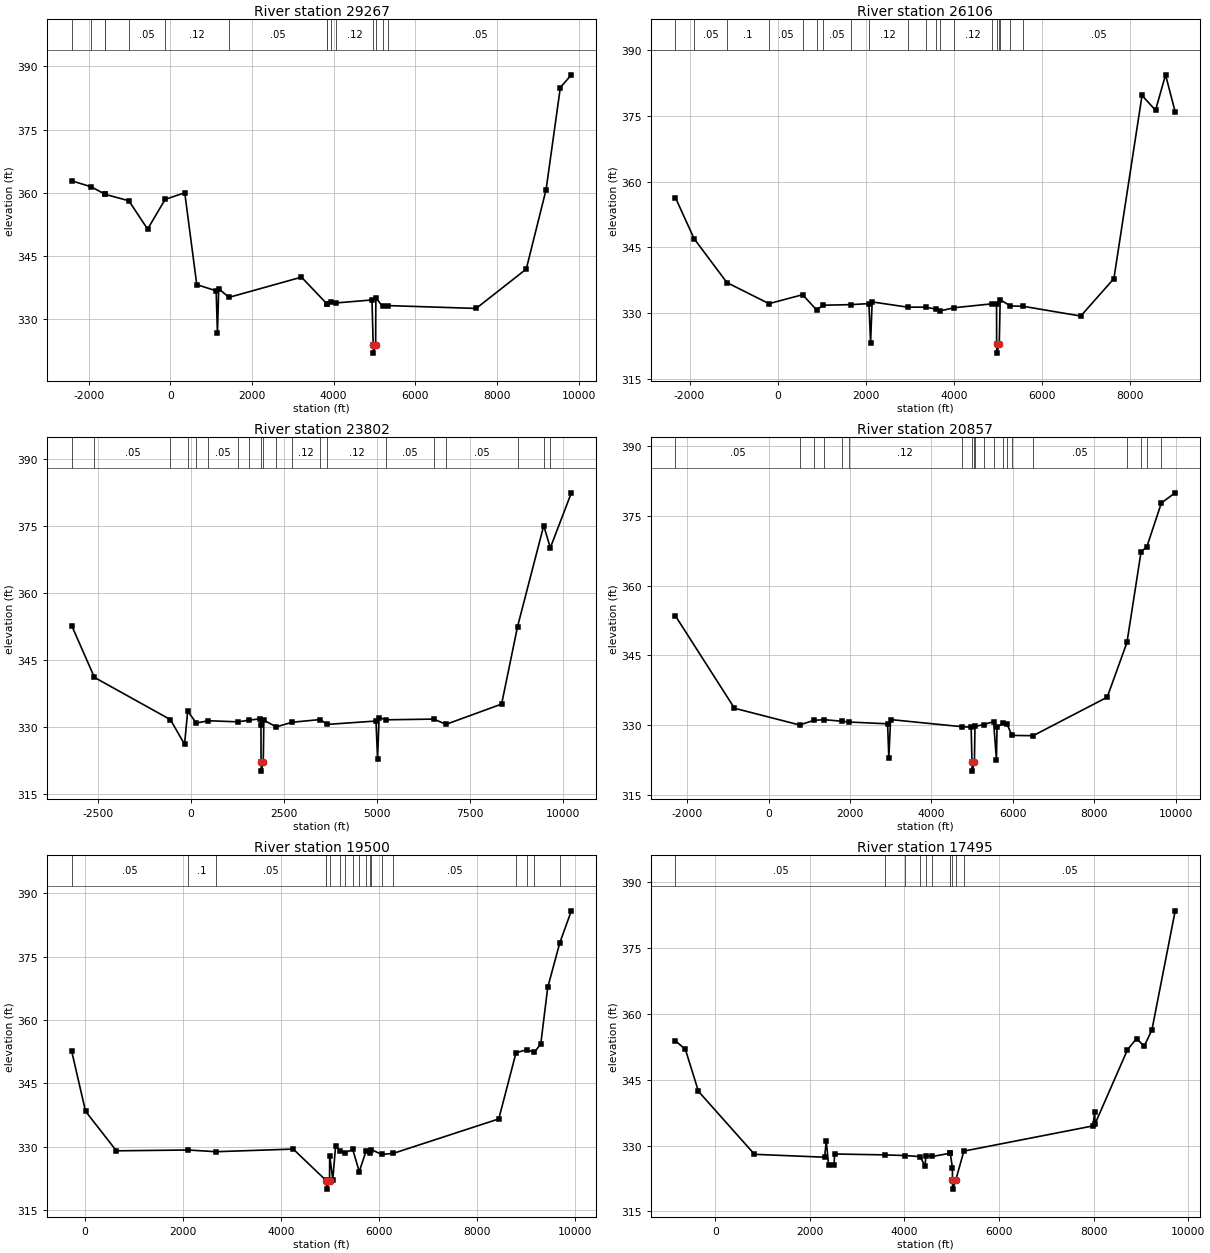
Type RM Length L Ch R = 1 ,29267   ,3161,3161,3161
BEGIN DESCRIPTION:
Mapping XS cc0e8c66
END DESCRIPTION:
XS GIS Cut Line= 5
      2663916.63      6850423.21      2657341.15      6848313.85
      2657263.02      6847819.06      2656325.52      6846855.52
      2653356.77      6845019.58
#Sta/Elev= 30
 -2418.7  362.86   -1937  361.42 -1611.5  359.73 -1605.7  359.67 -1017.4  358.12
  -557.9   351.4  -127.8  358.46     352  360.02   646.4  338.24  1121.1  336.77
  1152.6  326.82  1184.1  337.24  1437.3  335.22    3211  340.01  3831.4  333.71
  3840.7   333.7  3940.9  334.18  4068.2   333.9  4938.4   334.6  4968.8  323.99
  4973.6  321.99  5028.3  323.99  5033.8  335.11  5196.4   333.1  5338.2  333.26
  7490.3  332.59  8718.4  341.93  9204.2  360.78  9553.2  384.98  9822.7  387.99
#Mann= 15 ,-1 , 0
 -2418.7     .05       0   -1937     .12       0 -1611.5     .05       0
 -1605.7     .12       0 -1017.4     .05       0  -127.8     .12       0
  1437.3     .05       0  3831.4      .1       0  3840.7     .12       0
  3940.9      .1       0  4068.2     .12       0  4968.8     .07       0
  5028.3     .12       0  5196.4      .1       0  5338.2     .05       0
Bank Sta=4968.8,5028.3
XS Rating Curve= 0 ,0
Exp/Cntr=0.3,0.1

Type RM Length L Ch R = 1 ,26106   ,2304,2304,2304
BEGIN DESCRIPTION:
Mapping XS c7aebdfc
END DESCRIPTION:
XS GIS Cut Line= 4
       2664828.1      6848418.01      2658343.75      6845957.08
       2656959.2      6845562.12      2654278.21      6844295.37
#Sta/Elev= 30
 -2318.5  356.32 -1897.3  347.01 -1152.8  336.98  -196.7  332.16   565.4   334.2
   886.2  330.71  1028.5   331.8  1663.6  331.94  2071.2  332.17  2109.2  323.29
  2144.7  332.56  2949.5  331.36  3358.1  331.36  3588.6  330.91  3679.9  330.49
  4008.3  331.23    4871  332.13  4968.4  332.17  4969.8  322.87  4974.6  320.87
  5029.4  322.87  5050.3  333.06  5281.5  331.64  5575.6  331.55  6878.9  329.33
    7631  337.88  8269.3  379.67  8576.2   376.3  8803.3  384.38  9022.1   375.9
#Mann= 20 ,-1 , 0
 -2318.5     .05       0 -1897.3     .05       0 -1152.8      .1       0
  -196.7     .05       0   565.4      .1       0   886.2     .12       0
  1028.5     .05       0  1663.6     .12       0  2071.2     .12       0
  2949.5     .12       0  3358.1     .12       0  3588.6      .1       0
  3679.9     .12       0  4008.3     .12       0    4871      .1       0
  4969.8     .07       0  5029.4      .1       0  5050.3     .12       0
  5281.5      .1       0  5575.6     .05       0
Bank Sta=4969.8,5029.4
XS Rating Curve= 0 ,0
Exp/Cntr=0.3,0.1

Type RM Length L Ch R = 1 ,23802   ,2945,2945,2945
BEGIN DESCRIPTION:
Mapping XS 8d0a8a35
END DESCRIPTION:
XS GIS Cut Line= 6
      2664914.07       6848238.6      2662153.65      6846584.95
      2658390.63      6845074.53      2657479.17      6843642.24
      2657946.56      6842025.47      2656268.25      6839866.22
#Sta/Elev= 30
   -3209  352.69 -2596.1  341.09  -551.3  331.65  -171.5  326.13   -87.2  333.54
   145.6  330.89   468.9   331.4  1267.4  331.16    1568  331.53  1865.3  331.84
  1884.5   330.5    1887  322.14  1891.9  320.14  1946.8  322.14  1961.6  331.55
  2292.8  330.02  2722.1  331.07    3484  331.67  3661.9  330.58  4978.5  331.34
  5021.1  322.92  5063.6  332.11  5242.4  331.61  6531.9  331.77    6865   330.6
  8358.5  335.13    8787  352.43  9491.9  375.02  9669.3  370.05 10234.8  382.35
#Mann= 20 ,-1 , 0
   -3209     .05       0 -2596.1     .05       0  -551.3      .1       0
   -87.2     .05       0   145.6      .1       0   468.9     .05       0
  1267.4      .1       0    1568      .1       0    1887     .07       0
  1946.8     .12       0  2292.8     .12       0  2722.1     .12       0
    3484      .1       0  3661.9     .12       0  5242.4     .05       0
  6531.9      .1       0    6865     .05       0    8787     .12       0
  9491.9     .12       0  9669.3     .05       0
Bank Sta=1887,1946.8
XS Rating Curve= 0 ,0
Exp/Cntr=0.3,0.1

Type RM Length L Ch R = 1 ,20857   ,1357,1357,1357
BEGIN DESCRIPTION:
Mapping XS 304f51ac
END DESCRIPTION:
XS GIS Cut Line= 6
      2665135.44      6847782.88      2660356.77      6845113.59
      2659705.73      6844163.07      2658677.09      6843342.76
      2658755.21      6842340.16      2656437.49      6839957.33
#Sta/Elev= 30
 -2286.2  353.48  -837.3  333.61   762.9  330.01  1110.8     331    1359  331.15
  1812.8  330.81  1966.8  330.65  2924.9  330.26  2955.2  322.93  2998.6  331.17
  4754.7  329.63  4977.3  329.53  4998.5  322.07  5003.3  320.07  5058.3  322.07
  5071.6  329.69  5295.6  330.11  5528.6  330.73  5598.8  322.56    5614  329.49
  5748.4  330.33    5861  330.16  5980.3  327.76  6500.5   327.7  8320.7  335.99
  8806.2  347.78  9153.5  367.35  9293.3  368.35  9652.3  377.83  9991.2     380
#Mann= 20 ,-1 , 0
 -2286.2     .05       0   762.9      .1       0  1110.8      .1       0
    1359     .12       0  1812.8      .1       0  1966.8     .12       0
  4754.7     .12       0  4998.5     .07       0  5058.3      .1       0
  5071.6     .12       0  5295.6      .1       0  5528.6      .1       0
  5748.4     .12       0    5861      .1       0  5980.3      .1       0
  6500.5     .05       0  8806.2     .12       0  9153.5     .05       0
  9293.3     .12       0  9652.3     .05       0
Bank Sta=4998.5,5058.3
XS Rating Curve= 0 ,0
Exp/Cntr=0.3,0.1

Type RM Length L Ch R = 1 ,19500   ,2005,2005,2005
BEGIN DESCRIPTION:
Kings Creek 39.0
END DESCRIPTION:
XS GIS Cut Line= 3
      2664125.99      6846860.99      2660301.84      6843235.15
      2656625.99      6839960.99
#Sta/Elev= 30
  -269.8  352.68    13.1  338.44   642.6  329.08  2108.3  329.27  2671.8  328.87
  4250.1  329.49  4918.9  322.08    4924  322.02  4929.4  320.02    4991  322.02
  4993.1  327.96  5056.8  322.28  5113.6  330.16  5212.2  328.97  5309.6  328.64
    5464   329.4  5596.2  324.16  5738.4  329.12  5819.7  328.59  5837.9  329.39
  6055.8  328.21  6291.8  328.48  8442.2  336.62  8794.5  352.28  9015.1  352.99
  9166.3  352.33  9299.3  354.37  9440.6  367.71  9687.4  378.27  9922.6  385.83
#Mann= 19 ,-1 , 0
  -269.8     .05       0  2108.3      .1       0  2671.8     .05       0
  4918.9      .1       0    4924     .07       0    4991      .1       0
  5212.2     .12       0  5309.6      .1       0    5464     .12       0
  5596.2      .1       0  5738.4     .12       0  5819.7      .1       0
  5837.9     .12       0  6055.8      .1       0  6291.8     .05       0
  8794.5     .12       0  9015.1     .05       0  9166.3     .12       0
  9687.4     .05       0
Bank Sta=4924,4991
XS Rating Curve= 0 ,0
Exp/Cntr=0.3,0.1

Type RM Length L Ch R = 1 ,17495   ,1438,1438,1438
BEGIN DESCRIPTION:
Mapping XS b444091a
END DESCRIPTION:
XS GIS Cut Line= 3
      2664523.43      6846597.96       2660747.4      6842144.84
      2657583.37      6838629.25
#Sta/Elev= 30
  -842.6  353.83    -634  351.91  -357.2  342.34   828.1     328    2311  327.34
  2346.2  331.11  2395.6  325.46  2509.9  325.47    2523  328.07  3592.9  327.87
  4005.1  327.72    4334  327.48  4432.2  325.31  4456.6   327.7  4592.5  327.51
  4967.7  328.25  4969.5  328.25  5014.2  324.91  5015.3  322.07  5020.9  320.07
  5083.2  322.07  5256.4  328.73  7987.8  334.47  8023.3  337.65    8030  334.91
  8716.9  351.82  8908.2  354.37  9071.2  352.61  9234.1  356.38  9725.7  383.46
#Mann= 11 ,-1 , 0
  -842.6     .05       0  3592.9      .1       0  4005.1     .12       0
    4334      .1       0  4456.6     .12       0  4592.5      .1       0
  4967.7     .12       0  4969.5      .1       0  5015.3     .07       0
  5083.2      .1       0  5256.4     .05       0
Bank Sta=5015.3,5083.2
XS Rating Curve= 0 ,0
Exp/Cntr=0.3,0.1

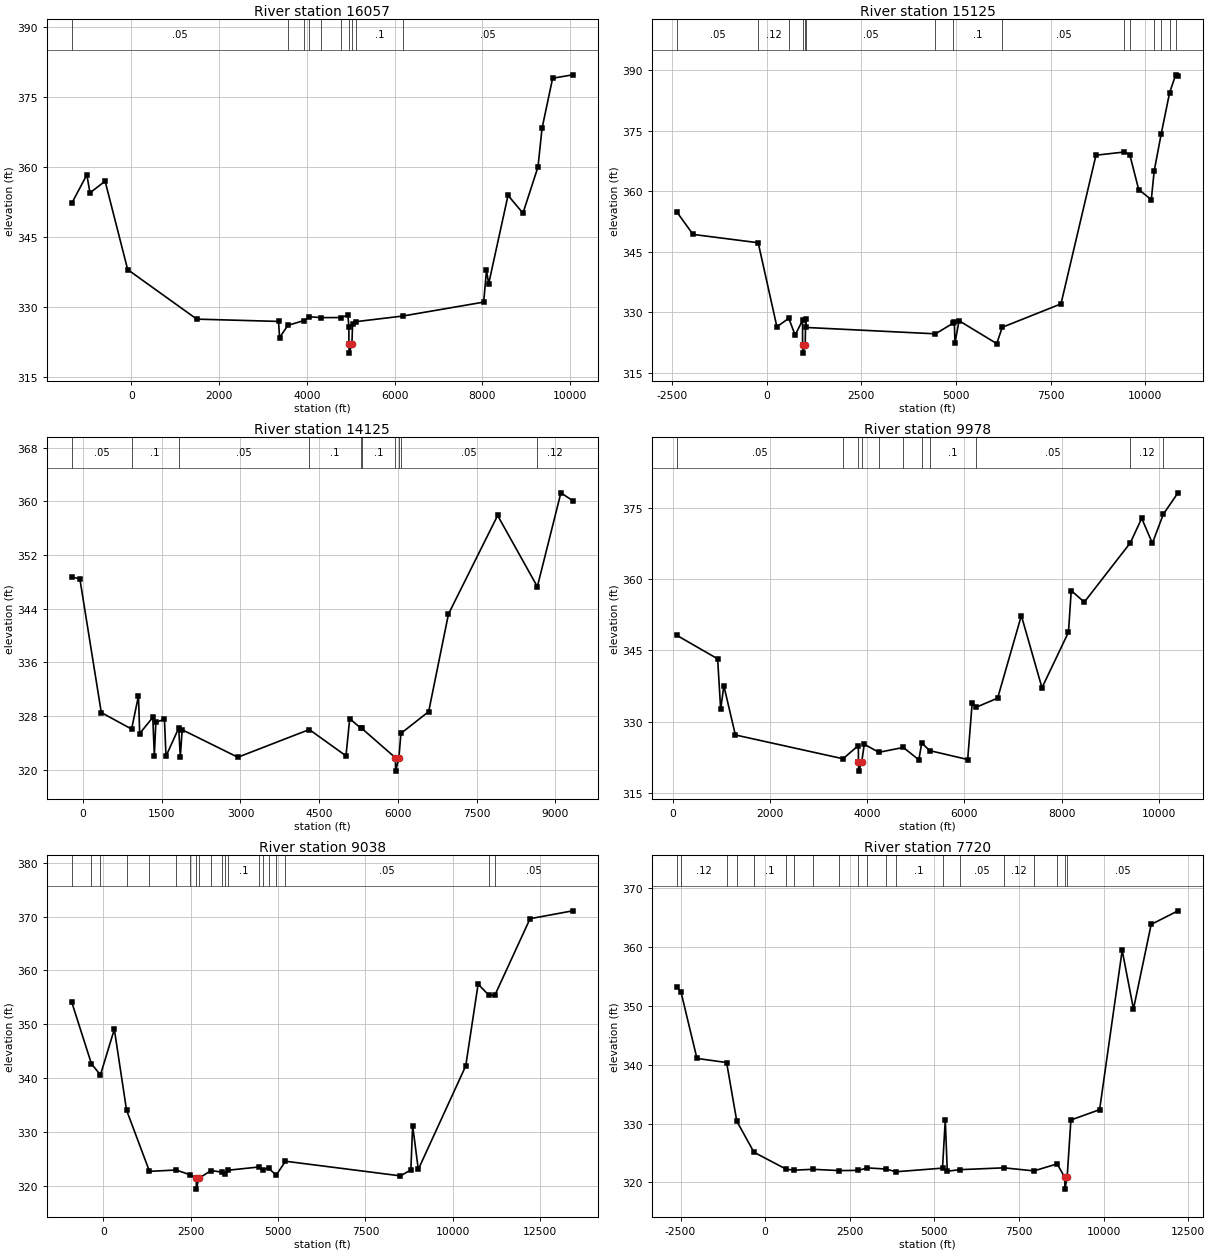
Type RM Length L Ch R = 1 ,16057   ,932,932,932
BEGIN DESCRIPTION:
Kings Creek 33.0
END DESCRIPTION:
XS GIS Cut Line= 4
      2665295.21      6846883.76      2663990.86      6845109.41
      2661505.72      6841780.89      2658312.51        6837861.
#Sta/Elev= 30
 -1356.1  352.14 -1011.3  358.26  -940.3  354.39  -595.6   356.9   -81.6  337.94
  1492.3  327.31  3355.9  326.82  3377.5  323.35  3568.8  325.98    3934     327
  4055.6  327.82  4322.6  327.63  4774.8  327.65  4936.1  328.16    4957  325.55
  4958.4  322.02    4964  320.02  5026.3  322.02  5042.1  326.35  5128.2  326.78
  6181.2  327.97    8028  330.96    8092  337.78  8141.5  334.88  8582.4  353.85
  8922.8  350.04  9264.6  359.94  9357.3  368.22  9598.6  378.97 10055.9   379.7
#Mann= 10 ,-1 , 0
 -1356.1     .05       0  3568.8      .1       0    3934     .12       0
  4055.6      .1       0  4322.6     .12       0  4774.8      .1       0
  4958.4     .07       0  5026.3      .1       0  5128.2      .1       0
  6181.2     .05       0
Bank Sta=4958.4,5026.3
XS Rating Curve= 0 ,0
Exp/Cntr=0.3,0.1

Type RM Length L Ch R = 1 ,15125   ,1000,1000,1000
BEGIN DESCRIPTION:
Mapping XS 8166babe
END DESCRIPTION:
XS GIS Cut Line= 5
      2668331.63      6845253.54      2665326.45      6843759.15
      2662791.67      6842535.47      2661841.15      6840855.78
      2659185.27      6836455.36
#Sta/Elev= 30
 -2373.9   354.8 -1950.8  349.29    -228  347.23   266.6   326.4   580.7  328.51
   748.3  324.34   944.1     328   945.8  321.88   951.4  319.88  1013.7  321.88
  1027.2  328.22  1042.4  326.24  4456.4  324.66  4912.6  327.23  4956.3  327.63
  4972.2  322.39  5080.4  327.91  6076.4  322.24  6222.7  326.28  7774.7  332.08
  8699.4  368.92  9452.2  369.71  9593.6  369.01  9828.3   360.4 10162.1  357.91
 10236.7  364.95 10422.9  374.17 10645.4   384.4 10806.4  388.83 10866.8   388.6
#Mann= 15 ,-1 , 0
 -2373.9     .05       0    -228     .12       0   580.7      .1       0
   945.8     .07       0  1013.7      .1       0  1042.4     .05       0
  4456.4     .12       0  4912.6      .1       0  6222.7     .05       0
  9452.2     .12       0  9593.6     .05       0 10236.7     .12       0
 10422.9     .05       0 10645.4     .12       0 10806.4     .05       0
Bank Sta=945.8,1013.7
XS Rating Curve= 0 ,0
Exp/Cntr=0.3,0.1

Type RM Length L Ch R = 1 ,14125   ,4147,4147,4147
BEGIN DESCRIPTION:
Mapping XS ac855a8f
END DESCRIPTION:
XS GIS Cut Line= 5
      2666776.02      6844137.02      2662908.86      6841350.57
      2662765.63      6840569.32      2662505.21      6839019.84
      2661294.25      6836936.47
#Sta/Elev= 30
  -213.9   348.7     -59  348.45   349.6   328.5   926.9  326.04  1057.7     331
  1080.3  325.37  1330.2  327.78  1359.6  322.04  1388.4  327.07  1552.3  327.48
  1581.7  321.99  1824.4   326.2  1854.2  321.86  1889.7  325.94    2950  321.84
  4310.8  325.97  5009.6  322.05  5080.8  327.59    5297  326.14  5312.6  326.13
    5950  321.77  5955.6  319.77  6017.9  321.77  6055.4  325.39  6584.4  328.64
  6961.7  343.19  7897.8  357.88  8654.3  347.27  9102.8  361.26  9327.8  360.09
#Mann= 10 ,-1 , 0
  -213.9     .05       0   926.9      .1       0  1824.4     .05       0
  4310.8      .1       0    5297     .12       0  5312.6      .1       0
    5950     .07       0  6017.9      .1       0  6055.4     .05       0
  8654.3     .12       0
Bank Sta=5950,6017.9
XS Rating Curve= 0 ,0
Exp/Cntr=0.3,0.1

Type RM Length L Ch R = 1 ,9978    ,940,940,940
BEGIN DESCRIPTION:
Mapping XS 84f4af31
END DESCRIPTION:
XS GIS Cut Line= 4
      2667700.53      6844241.21      2665018.23       6840491.2
       2664809.9      6840230.78      2661125.02      6836337.57
#Sta/Elev= 30
    88.8  348.12   924.6   343.2   987.3  332.55  1052.4  337.54  1289.5  327.18
  3504.4  322.17  3819.2  324.96  3820.6  321.57  3826.2  319.57  3889.2  321.57
  3940.9  325.22  4241.3  323.53    4745  324.55  5063.7  321.94    5122  325.51
  5286.1  323.89  6068.1  322.01  6160.3  333.94  6239.7     333  6683.8  334.93
  7171.7   352.3    7596  337.11  8140.9   348.8  8197.6  357.56  8466.2  355.13
  9412.7   367.6  9647.4  372.77  9866.7  367.52 10091.5  373.63 10393.4  378.13
#Mann= 11 ,-1 , 0
    88.8     .05       0  3504.4      .1       0  3820.6     .07       0
  3889.2      .1       0  4241.3     .05       0    4745      .1       0
    5122     .12       0  5286.1      .1       0  6239.7     .05       0
  9412.7     .12       0 10091.5     .05       0
Bank Sta=3820.6,3889.2
XS Rating Curve= 0 ,0
Exp/Cntr=0.3,0.1

Type RM Length L Ch R = 1 ,9038    ,1318,1318,1318
BEGIN DESCRIPTION:
Mapping XS 7616cca5
END DESCRIPTION:
XS GIS Cut Line= 4
      2668429.71       6844970.4      2665591.15      6839788.07
       2665626.3      6836148.21      2660960.77       6835084.9
#Sta/Elev= 30
    -903  354.14  -339.1  342.68   -80.9  340.61   316.3  349.09   665.5  334.07
  1321.8   322.7  2084.9  322.95  2480.3  322.07  2658.9   321.4  2664.7   319.4
  2730.3   321.4  3086.6  322.85  3398.6  322.54  3491.6  322.24    3570  322.91
  4450.6  323.51  4560.4  323.01  4729.9  323.29  4947.9     322  5212.9  324.58
    8503  321.86    8800  322.97  8851.3  331.19    9013  323.06 10370.1  342.27
 10724.5  357.47 11036.3  355.38 11208.7  355.48 12210.6  369.62   13431  371.08
#Mann= 20 ,-1 , 0
    -903     .05       0  -339.1     .05       0   -80.9     .05       0
   665.5      .1       0  1321.8     .05       0  2084.9     .12       0
  2480.3      .1       0  2658.9     .07       0  2730.3      .1       0
  3086.6     .12       0  3398.6      .1       0  3491.6     .12       0
    3570      .1       0  4450.6     .12       0  4560.4      .1       0
  4729.9     .05       0  4947.9    .075       0  5212.9     .05       0
 11036.3     .12       0 11208.7     .05       0
Bank Sta=2658.9,2730.3
XS Rating Curve= 0 ,0
Exp/Cntr=0.3,0.1

Type RM Length L Ch R = 1 ,7720    ,2610,2610,2610
BEGIN DESCRIPTION:
Mapping XS fc5ebb6f
END DESCRIPTION:
XS GIS Cut Line= 4
      2670734.39      6845634.45       2666684.9      6839163.07
       2665691.4      6835540.57       2662314.2      6835053.17
#Sta/Elev= 30
 -2605.6  353.25 -2485.2  352.32 -2016.2  341.09 -1139.2  340.39  -839.9  330.44
    -332  325.14   617.3  322.27   847.4  322.09  1400.8  322.24  2194.8  322.02
  2754.4  322.06    3018  322.48  3577.6  322.28    3861  321.82  5239.7  322.44
  5320.8  330.67  5380.6  321.91  5755.1  322.18  7059.8  322.49  7940.3  321.97
  8626.7  323.16  8850.6  320.87  8856.4  318.87    8922  320.87  9032.5  330.62
  9881.3  332.38 10548.1  359.46 10881.5  349.49 11404.4  363.87 12196.8  366.18
#Mann= 20 ,-1 , 0
 -2605.6     .05       0 -2485.2     .12       0 -1139.2     .05       0
  -839.9     .05       0    -332      .1       0   617.3     .05       0
   847.4     .12       0  1400.8     .05       0  2194.8      .1       0
  2754.4      .1       0    3018     .12       0  3577.6     .12       0
    3861      .1       0  5239.7     .12       0  5755.1     .05       0
  7059.8     .12       0  7940.3     .12       0  8626.7     .05       0
  8850.6     .07       0    8922     .05       0
Bank Sta=8850.6,8922
XS Rating Curve= 0 ,0
Exp/Cntr=0.3,0.1

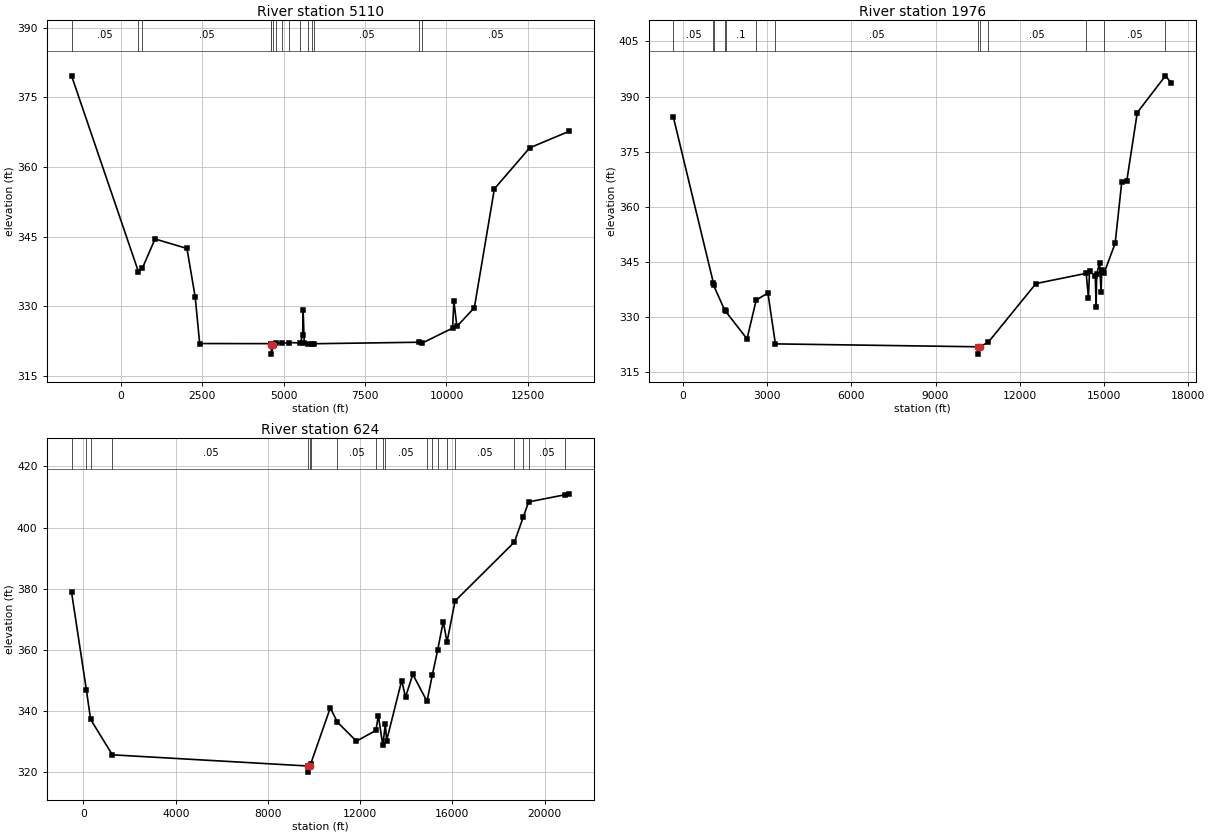
Type RM Length L Ch R = 1 ,5110    ,3134,3134,3134
BEGIN DESCRIPTION:
Mapping XS 13416504
END DESCRIPTION:
XS GIS Cut Line= 5
      2674167.54      6842709.66      2669289.06      6839602.02
       2668559.9      6838490.91      2665799.91      6835236.75
      2661939.04      6834651.12
#Sta/Elev= 30
 -1509.4  379.66   543.3  337.47   664.2  338.23  1053.4  344.52  2032.7  342.48
  2286.5     332  2423.8     322  4607.5  321.98  4617.6  321.72  4623.4  319.72
  4689.3  321.72  4777.9  322.11  4941.5  322.01  5174.1  322.22  5511.8  322.12
  5584.7  323.78  5599.7  329.25  5634.7  322.03  5742.6  321.94  5873.7  321.95
  5941.8  321.96  9150.2  322.28  9263.1  322.13 10188.3  325.32 10228.7  331.18
 10319.8  325.68 10855.8  329.71 11471.9  355.32   12555  364.15 13775.8  367.74
#Mann= 15 ,-1 , 0
 -1509.4     .05       0   543.3     .12       0   664.2     .05       0
  4607.5     .12       0  4617.6     .07       0  4689.3     .12       0
  4777.9      .1       0  4941.5     .12       0  5174.1      .1       0
  5511.8     .12       0  5742.6     .05       0  5873.7      .1       0
  5941.8     .05       0  9150.2     .12       0  9263.1     .05       0
Bank Sta=4617.6,4689.3
XS Rating Curve= 0 ,0
Exp/Cntr=0.3,0.1

Type RM Length L Ch R = 1 ,1976    ,1352,1352,1352
BEGIN DESCRIPTION:
Mapping XS e13bf26a
END DESCRIPTION:
XS GIS Cut Line= 3
      2674849.39      6841920.78      2671290.36      6837992.83
      2660396.25      6832003.24
#Sta/Elev= 30
  -334.8  384.33  1089.7  339.22  1096.4  338.58  1494.9  331.77  1527.2  331.48
  2286.8  324.01  2613.3  334.59  3030.2   336.5    3297  322.65 10502.2  321.86
 10508.1  319.86 10574.2  321.86 10880.4  323.11 12576.6  339.07 14367.2  341.86
 14446.4  335.08 14484.3  342.36 14690.8  341.09 14718.3  332.81 14740.1  341.59
 14843.3  344.73 14897.3  336.72 14919.1  342.69 15011.1  342.08 15397.4  350.03
 15631.4  366.62 15810.4  366.93 16185.5  385.63   17189  395.64 17397.8   393.7
#Mann= 13 ,-1 , 0
  -334.8     .05       0  1089.7     .12       0  1096.4      .1       0
  1494.9     .12       0  1527.2      .1       0  2613.3     .12       0
    3297     .05       0 10502.2     .05       0 10574.2     .05       0
 10880.4     .05       0 14367.2     .12       0 15011.1     .05       0
   17189     .12       0
Bank Sta=10502.2,10574.2
XS Rating Curve= 0 ,0
Exp/Cntr=0.3,0.1

Type RM Length L Ch R = 1 ,624     ,0,0,0
BEGIN DESCRIPTION:
Mapping XS 37a54073
END DESCRIPTION:
XS GIS Cut Line= 3
       2675552.1      6840734.84       2671684.9      6836737.44
      2657101.54      6830070.76
#Sta/Elev= 30
  -517.5  378.76   126.4  346.73   308.5  337.12  1252.8   325.5  9750.9  321.83
  9756.8  319.83  9822.9  321.83  9860.3  322.62 10705.8   340.9   11015   336.2
 11838.3  329.98 12682.4  333.49   12791  338.33   12982  328.63 13095.3  335.64
 13146.7  330.11 13801.9  349.83 13968.6  344.42 14284.3  351.89 14899.9  343.03
   15135  351.79 15358.7   359.7 15605.5  369.19 15768.3  362.48 16118.5  375.92
 18693.7  395.25   19079  403.48 19308.9  408.39 20890.6  410.74 21079.3  411.04
#Mann= 20 ,-1 , 0
  -517.5     .05       0   126.4     .12       0   308.5      .1       0
  1252.8     .05       0  9750.9     .03       0  9822.9     .12       0
  9860.3     .05       0   11015     .05       0 12682.4     .12       0
   12982     .05       0 13095.3     .05       0 14899.9     .12       0
   15135     .05       0 15358.7     .05       0 15768.3     .12       0
 16118.5     .05       0 18693.7     .12       0   19079     .12       0
 19308.9     .05       0 20890.6     .12       0
Bank Sta=9750.9,9822.9
XS Rating Curve= 0 ,0
Exp/Cntr=0.3,0.1

Chan Stop Cuts=-1
Use User Specified Reach Order=0
Composite Channel Slope=5