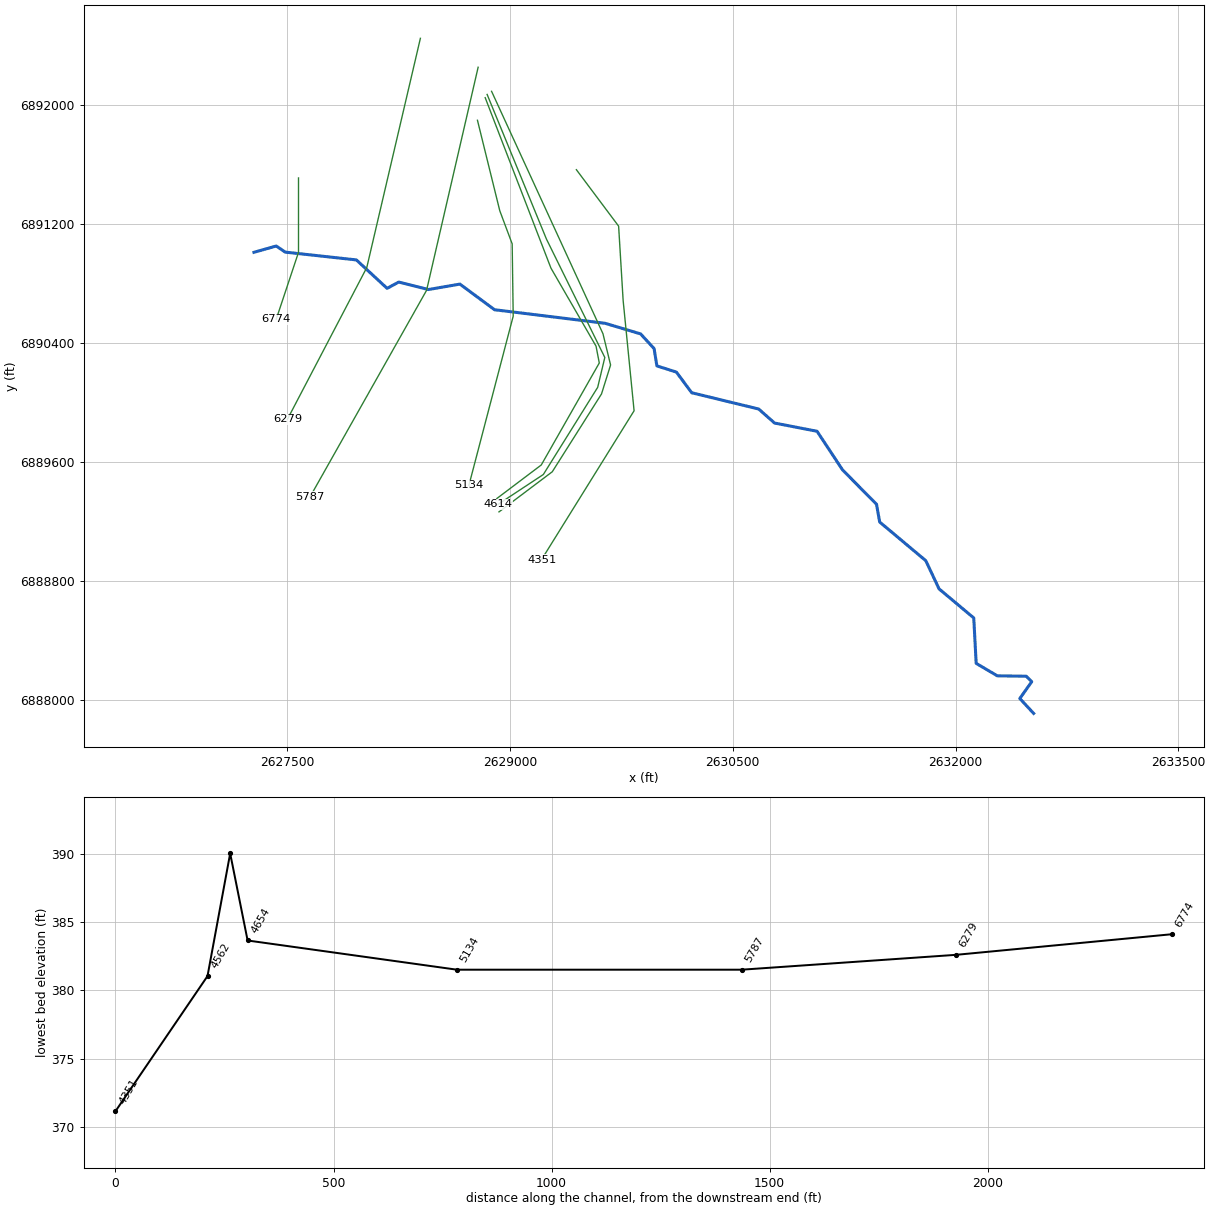
--- Kings Creek 18.prj (project) ---

Proj Title=Kings Creek 18 Base Level Engineering
Current Plan=p01
Default Exp/Contr=0.3,0.1
English Units
Geom File=g01
Flow File=f01
Plan File=p01
BEGIN DESCRIPTION:
Kings Creek 18
END DESCRIPTION:

--- Kings Creek 18.p01 (plan) ---

Plan Title=Multiple Run
Short Identifier=Multiple
Geom File=g01
Flow File=f01
Subcritical Flow
K Sum by GR= 0
Std Step Tol= 0.01
Critical Tol= 0.01
Num of Std Step Trials= 20
Max Error Tol= 0.3
Flow Tol Ratio= 0.001
Split Flow NTrial= 30
Split Flow Tol= 0.02
Split Flow Ratio= 0.02
Log Output Level= 0
Friction Slope Method= 1
Unsteady Friction Slope Method= 2
Unsteady Bridges Friction Slope Method= 1
Parabolic Critical Depth
Global Vel Dist=  1 , 1 , 1
Global Log Level= 0
CheckData=True
Encroach Param= -1, 0, 0, 0
BEGIN DESCRIPTION:
Multiple Run
END DESCRIPTION:

--- Kings Creek 18.f01 (steady flow) ---

Flow Title=Multiple
Number of Profiles=7
Profile Names=10-year,25-year,50-year,1pct_min,100-year,1pct_plu,500-year
River Rch & RM= Kings Creek 18,Reach-1,6774
     587     789     952     570    1138    2270    1624
River Rch & RM= Kings Creek 18,Reach-1,5134
     686     929    1126     677    1351    2695    1944
River Rch & RM= Kings Creek 18,Reach-1,4614
    1034    1429    1756    1068    2131    4251    3140
Boundary for River Rch & Prof#=Kings Creek 18,Reach-1,1
Up Type=0
Dn Type=3
Dn Slope=0.005
Boundary for River Rch & Prof#=Kings Creek 18,Reach-1,2
Up Type=0
Dn Type=3
Dn Slope=0.005
Boundary for River Rch & Prof#=Kings Creek 18,Reach-1,3
Up Type=0
Dn Type=3
Dn Slope=0.005
Boundary for River Rch & Prof#=Kings Creek 18,Reach-1,4
Up Type=0
Dn Type=3
Dn Slope=0.005
Boundary for River Rch & Prof#=Kings Creek 18,Reach-1,5
Up Type=0
Dn Type=3
Dn Slope=0.005
Boundary for River Rch & Prof#=Kings Creek 18,Reach-1,6
Up Type=0
Dn Type=3
Dn Slope=0.005
Boundary for River Rch & Prof#=Kings Creek 18,Reach-1,7
Up Type=0
Dn Type=3
Dn Slope=0.005

--- Kings Creek 18.g01 (geometry) ---

Geom Title=Existing Conditions

River Reach=Kings Creek 18,Reach-1
Reach XY= 30
      2627276.00      6891011.00      2627425.99      6891053.49
      2627486.44      6891012.38      2627965.57      6890959.95
      2628172.58      6890768.79      2628250.89      6890811.13
      2628450.92      6890760.80      2628662.79      6890797.36
      2628896.05      6890625.02      2629640.40      6890533.87
      2629879.62      6890462.50      2629970.46      6890363.42
      2629989.24      6890247.28      2630120.52      6890205.74
      2630223.69      6890066.83      2630674.53      6889957.44
      2630781.86      6889863.08      2631067.65      6889807.81
      2631239.62      6889547.79      2631468.14      6889317.17
      2631489.39      6889197.67      2631799.71      6888937.82
      2631889.62      6888747.79      2632122.93      6888552.70
      2632139.22      6888247.33      2632281.92      6888163.23
      2632476.00      6888161.00      2632513.48      6888124.33
      2632432.98      6888011.00      2632526.00      6887911.00

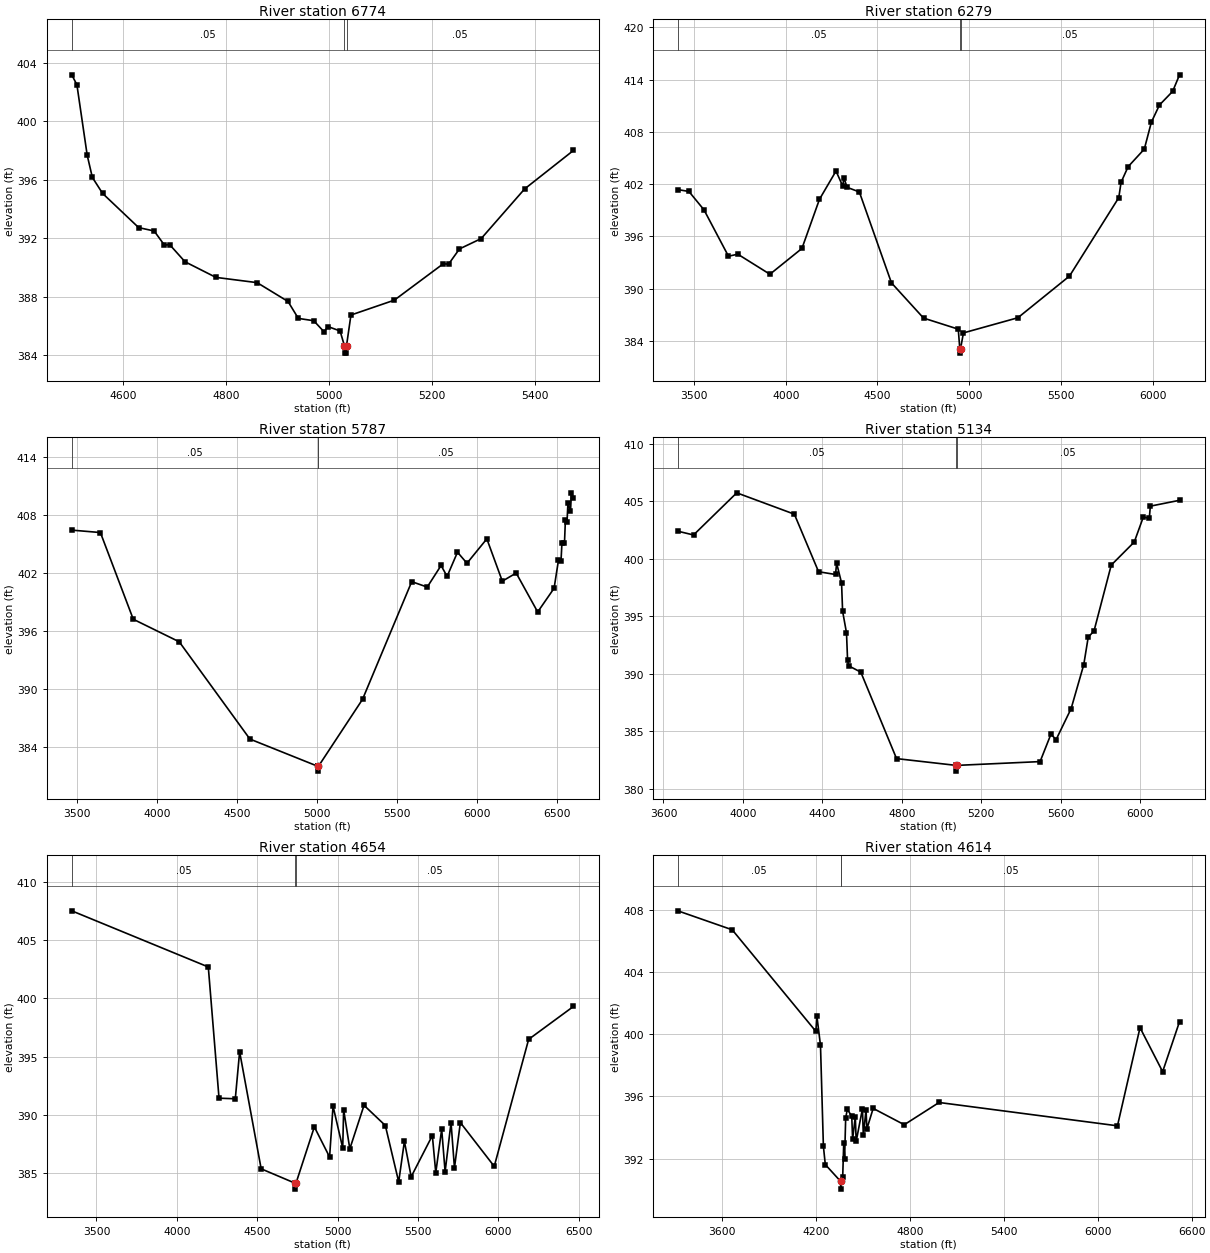
Type RM Length L Ch R = 1,6774,495,495,495
BEGIN DESCRIPTION:
Kings Creek 18 13.0
END DESCRIPTION:
XS GIS Cut Line= 3
      2627576.00      6891511.02      2627576.00      6891011.00
      2627425.99      6890560.96
#Sta/Elev= 30
  4499.9  403.19  4509.9  402.51  4529.9  397.68  4539.9  396.16  4559.9  395.06
  4629.9  392.72  4659.9  392.49  4679.9  391.52  4689.9  391.56  4719.9  390.38
  4779.9  389.31  4859.9  388.95  4919.9  387.66  4939.9  386.50  4969.9  386.34
  4989.9  385.58  4997.4  385.94  5021.0  385.64  5029.5  384.62  5029.8  384.12
  5033.3  384.12  5033.5  384.62  5042.1  386.73  5126.4  387.75  5221.3  390.24
  5231.8  390.22  5252.9  391.26  5295.1  391.97  5379.4  395.37  5474.3  398.01
#Mann=3,-1,0
  4499.9    0.05       0  5029.5    0.04       0  5033.5    0.05       0
Bank Sta=5029.5,5033.5
Exp/Cntr=0.3,0.1

Type RM Length L Ch R = 1,6279,492,492,492
BEGIN DESCRIPTION:
Mapping XS 21327c14
END DESCRIPTION:
XS GIS Cut Line= 3
      2628396.71      6892449.84      2628035.60      6890908.21
      2627500.96      6889887.52
#Sta/Elev= 30
  3411.8  401.37  3472.2  401.16  3554.4  399.05  3687.9  393.73  3738.9  393.96
  3913.9  391.66  4088.5  394.62  4184.1  400.26  4274.2  403.50  4311.5  401.75
  4316.7  402.75  4335.0  401.63  4401.6  401.10  4576.6  390.67  4751.6  386.63
  4940.9  385.36  4949.2  383.11  4949.5  382.61  4953.2  383.11  4969.1  384.93
  5266.1  386.67  5547.3  391.45  5816.1  400.45  5828.5  402.21  5867.0  404.00
  5955.3  406.02  5993.8  409.11  6037.9  411.08  6109.7  412.64  6147.4  414.54
#Mann=3,-1,0
  3411.8    0.05       0  4949.2    0.04       0  4953.2    0.05       0
Bank Sta=4949.2,4953.2
Exp/Cntr=0.3,0.1

Type RM Length L Ch R = 1,5787,653,653,653
BEGIN DESCRIPTION:
Mapping XS 3fccae90
END DESCRIPTION:
XS GIS Cut Line= 3
      2628785.60      6892255.43      2628438.38      6890755.44
      2627653.66      6889366.55
#Sta/Elev= 30
  3466.8  406.40  3645.8  406.15  3851.1  397.20  4138.5  394.87  4579.9  384.83
  5004.2  382.02  5004.4  381.52  5008.2  382.02  5283.6  388.93  5591.1  401.08
  5687.9  400.52  5774.5  402.75  5812.0  401.62  5877.0  404.12  5936.2  402.98
  6060.4  405.50  6157.1  401.13  6243.7  401.97  6378.1  397.95  6480.6  400.40
  6508.0  403.30  6523.9  403.26  6529.6  405.02  6545.5  405.06  6551.3  407.47
  6561.4  407.26  6567.2  409.22  6583.1  408.33  6588.8  410.25  6601.7  409.72
#Mann=3,-1,0
  3466.8    0.05       0  5004.2    0.03       0  5008.2    0.05       0
Bank Sta=5004.2,5008.2
Exp/Cntr=0.3,0.1

Type RM Length L Ch R = 1,5134,480,480,480
BEGIN DESCRIPTION:
Mapping XS 3eba5e59
END DESCRIPTION:
XS GIS Cut Line= 5
      2628781.04      6891898.85      2628931.44      6891290.16
      2629014.77      6891067.94      2629021.72      6890581.82
      2628723.50      6889444.46
#Sta/Elev= 30
  3672.3  402.41  3751.4  402.08  3969.0  405.75  4259.1  403.89  4381.0  398.88
  4466.4  398.64  4471.8  399.63  4496.7  397.91  4502.0  395.44  4521.6  393.56
  4527.0  391.20  4532.3  390.69  4593.6  390.14  4773.6  382.61  5073.3  382.02
  5073.6  381.52  5077.3  382.02  5496.4  382.35  5550.9  384.73  5577.2  384.27
  5652.8  386.97  5716.3  390.79  5738.7  393.18  5768.0  393.73  5854.7  399.46
  5970.7  401.47  6016.3  403.65  6046.3  403.52  6051.5  404.59  6198.6  405.10
#Mann=3,-1,0
  3672.3    0.05       0  5073.3    0.03       0  5077.3    0.05       0
Bank Sta=5073.3,5077.3
Exp/Cntr=0.3,0.1

Type RM Length L Ch R = 1,4654,40,40,40
BEGIN DESCRIPTION:
Mapping XS dfdc6572
END DESCRIPTION:
XS GIS Cut Line= 6
      2628833.12      6892050.79      2629275.82      6890904.97
      2629579.64      6890379.79      2629601.34      6890266.95
      2629210.72      6889581.18      2628911.57      6889355.74
#Sta/Elev= 30
  3346.5  407.50  4195.6  402.69  4262.3  391.45  4363.5  391.40  4390.4  395.43
  4524.3  385.40  4736.7  384.16  4736.9  383.66  4740.7  384.16  4855.0  388.99
  4949.9  386.41  4971.2  390.77  5031.5  387.19  5037.2  390.47  5075.6  387.11
  5163.9  390.84  5296.4  389.11  5379.6  384.28  5415.0  387.75  5457.2  384.72
  5588.8  388.25  5610.1  385.07  5646.9  388.79  5668.2  385.15  5705.0  389.36
  5726.3  385.48  5763.0  389.36  5973.7  385.61  6187.6  396.49  6466.4  399.31
#Mann=3,-1,0
  3346.5    0.05       0  4736.7    0.04       0  4740.7    0.05       0
Bank Sta=4736.7,4740.7
Exp/Cntr=0.3,0.1

Type RM Length L Ch R = 1,4614,52,52,52
BEGIN DESCRIPTION:
Mapping XS 2c73b10b
END DESCRIPTION:
XS GIS Cut Line= 6
      2628846.12      6892072.54      2629245.44      6891100.28
      2629638.59      6890304.00      2629590.67      6890103.30
      2629224.70      6889517.19      2628920.45      6889316.78
#Sta/Elev= 30
  3317.3  407.93  3664.9  406.71  4199.4  400.18  4205.4  401.19  4228.8  399.28
  4247.3  392.80  4259.5  391.62  4357.4  390.54  4357.7  390.04  4361.4  390.54
  4370.7  390.84  4377.3  393.02  4382.8  391.99  4389.7  394.62  4400.1  395.16
  4428.4  394.74  4434.0  393.25  4451.2  394.70  4456.8  393.11  4496.9  395.21
  4502.4  393.49  4519.7  395.14  4525.2  393.91  4565.3  395.23  4764.0  394.18
  4986.4  395.61  6126.1  394.11  6270.2  400.42  6414.8  397.59  6522.8  400.81
#Mann=3,-1,0
  3317.3    0.05       0  4357.4    0.04       0  4361.4    0.05       0
Bank Sta=4357.4,4361.4
Exp/Cntr=0.3,0.1

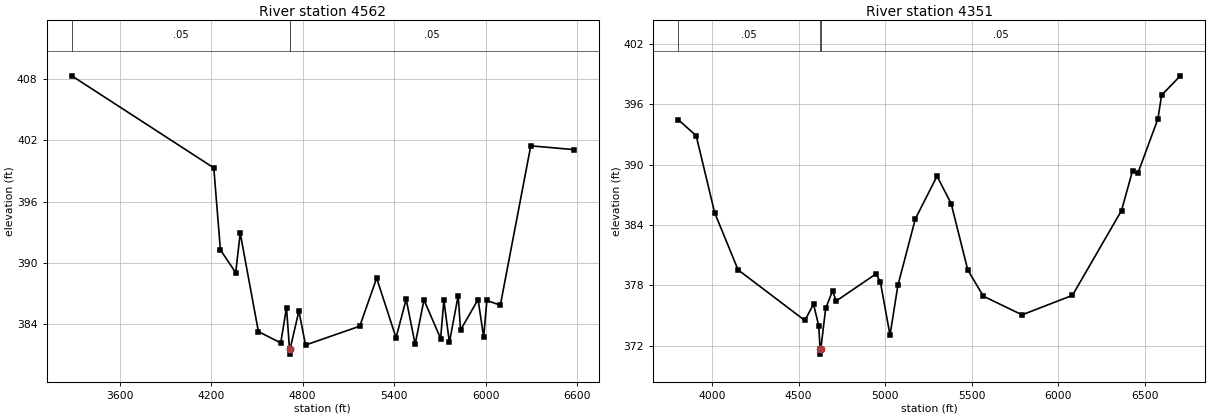
Type RM Length L Ch R = 1,4562,211,211,211
BEGIN DESCRIPTION:
Mapping XS d8419fe0
END DESCRIPTION:
XS GIS Cut Line= 6
      2628876.09      6892093.60      2629626.09      6890463.72
      2629677.43      6890253.58      2629616.36      6890058.86
      2629284.94      6889535.75      2628925.90      6889265.65
#Sta/Elev= 30
  3285.8  408.32  4217.3  399.30  4260.5  391.27  4360.9  389.03  4390.6  392.91
  4509.7  383.26  4656.3  382.15  4694.1  385.61  4713.8  381.55  4714.1  381.05
  4717.8  381.55  4775.4  385.28  4818.9  381.94  5174.7  383.79  5285.3  388.50
  5412.5  382.66  5478.9  386.43  5537.9  382.01  5595.6  386.36  5704.9  382.58
  5726.1  386.31  5762.5  382.20  5820.1  386.79  5835.4  383.41  5950.6  386.40
  5987.1  382.71  6008.3  386.31  6096.4  385.84  6296.1  401.46  6578.6  401.09
#Mann=3,-1,0
  3285.8    0.05       0  4713.8    0.04       0  4717.8    0.05       0
Bank Sta=4713.8,4717.8
Exp/Cntr=0.3,0.1

Type RM Length L Ch R = 1,4351,0,0,0
BEGIN DESCRIPTION:
Kings Creek 18 8.0
END DESCRIPTION:
XS GIS Cut Line= 5
      2629447.04      6891566.66      2629731.55      6891187.09
      2629761.93      6890687.95      2629835.72      6889945.77
      2629212.97      6888945.55
#Sta/Elev= 30
  3804.9  394.48  3908.6  392.89  4014.9  385.24  4150.3  379.54  4535.8  374.50
  4585.9  376.13  4616.0  373.96  4624.0  371.65  4624.2  371.15  4628.0  371.65
  4656.0  375.71  4696.1  377.46  4716.2  376.43  4947.1  379.14  4972.1  378.31
  5027.5  373.04  5072.9  377.99  5173.7  384.61  5298.8  388.86  5380.3  386.14
  5476.1  379.54  5566.1  376.92  5789.9  375.06  6080.7  377.00  6363.9  385.44
  6427.6  389.40  6458.3  389.15  6574.0  394.56  6595.2  396.92  6703.4  398.85
#Mann=3,-1,0
  3804.9    0.05       0  4624.0    0.04       0  4628.0    0.05       0
Bank Sta=4624,4628
Exp/Cntr=0.3,0.1

Chan Stop Cuts=-1