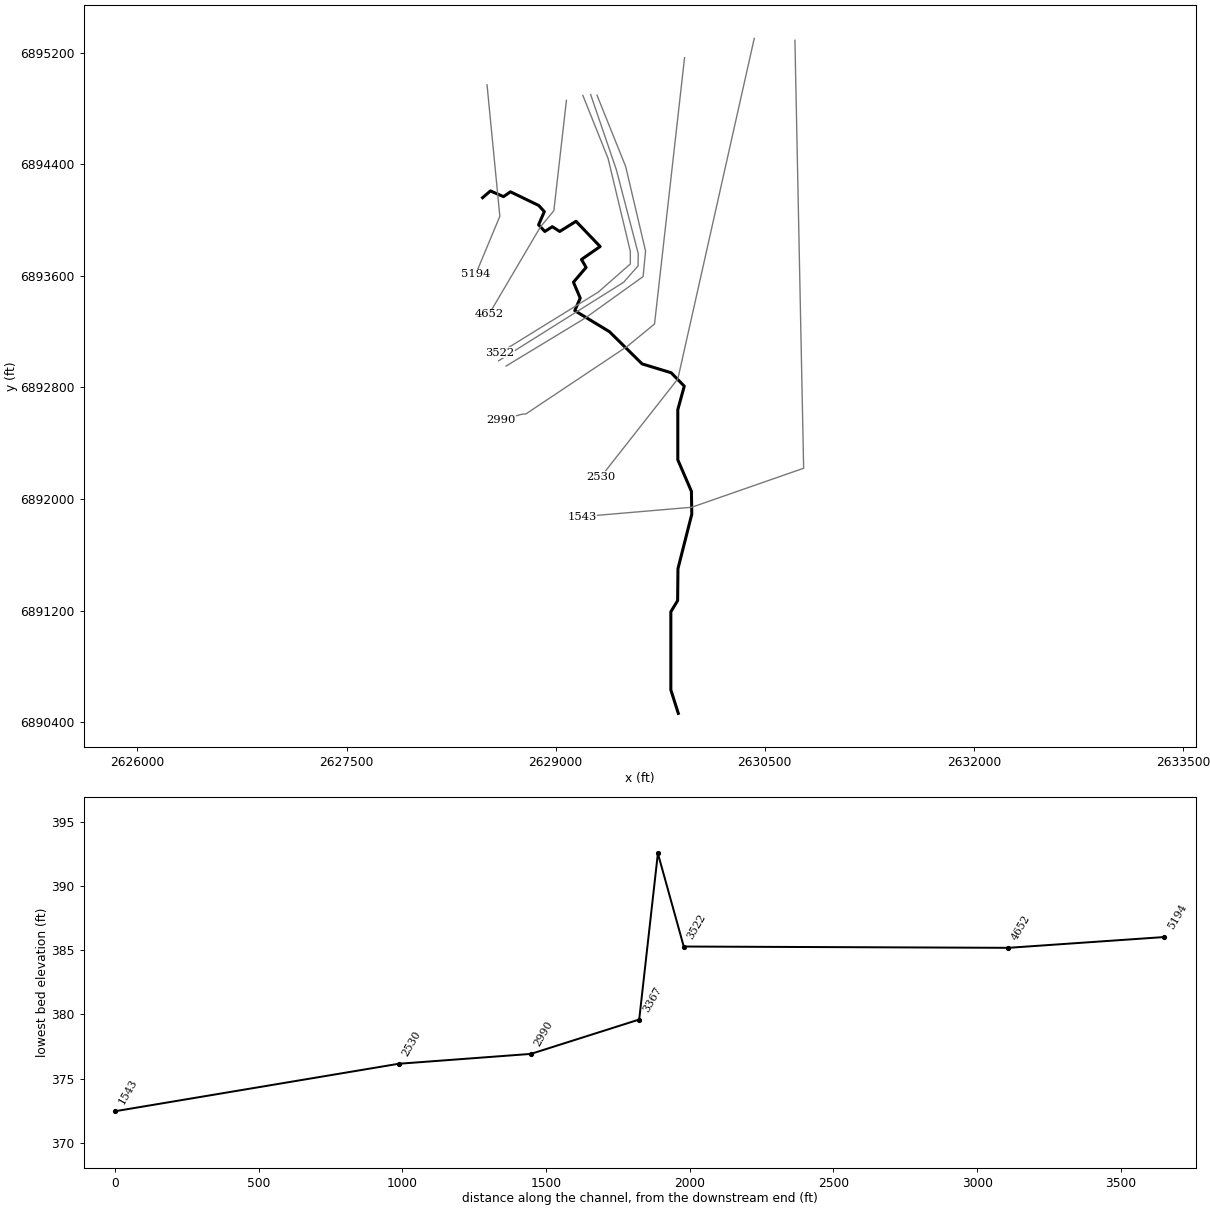
--- Kings Creek 18_1.prj (project) ---

Proj Title=Kings Creek 18_1 Base Level Engineering
Current Plan=p01
Default Exp/Contr=0.3,0.1
English Units
Geom File=g01
Flow File=f01
Plan File=p01
BEGIN DESCRIPTION:
Kings Creek 18_1
END DESCRIPTION:

--- Kings Creek 18_1.p01 (plan) ---

Plan Title=Multiple Run
Short Identifier=Multiple
Geom File=g01
Flow File=f01
Subcritical Flow
K Sum by GR= 0
Std Step Tol= 0.01
Critical Tol= 0.01
Num of Std Step Trials= 20
Max Error Tol= 0.3
Flow Tol Ratio= 0.001
Split Flow NTrial= 30
Split Flow Tol= 0.02
Split Flow Ratio= 0.02
Log Output Level= 0
Friction Slope Method= 1
Unsteady Friction Slope Method= 2
Unsteady Bridges Friction Slope Method= 1
Parabolic Critical Depth
Global Vel Dist=  1 , 1 , 1
Global Log Level= 0
CheckData=True
Encroach Param= -1, 0, 0, 0
BEGIN DESCRIPTION:
Multiple Run
END DESCRIPTION:

--- Kings Creek 18_1.f01 (steady flow) ---

Flow Title=Multiple
Number of Profiles=7
Profile Names=10-year,25-year,50-year,1pct_min,100-year,1pct_plu,500-year
River Rch & RM= Kings Creek 18_1,Reach-1,5194
     419     551     655     386     771    1538    1068
River Rch & RM= Kings Creek 18_1,Reach-1,2990
     456     602     717     424     846    1688    1178
Boundary for River Rch & Prof#=Kings Creek 18_1,Reach-1,1
Up Type=0
Dn Type=3
Dn Slope=0.005
Boundary for River Rch & Prof#=Kings Creek 18_1,Reach-1,2
Up Type=0
Dn Type=3
Dn Slope=0.005
Boundary for River Rch & Prof#=Kings Creek 18_1,Reach-1,3
Up Type=0
Dn Type=3
Dn Slope=0.005
Boundary for River Rch & Prof#=Kings Creek 18_1,Reach-1,4
Up Type=0
Dn Type=3
Dn Slope=0.005
Boundary for River Rch & Prof#=Kings Creek 18_1,Reach-1,5
Up Type=0
Dn Type=3
Dn Slope=0.005
Boundary for River Rch & Prof#=Kings Creek 18_1,Reach-1,6
Up Type=0
Dn Type=3
Dn Slope=0.005
Boundary for River Rch & Prof#=Kings Creek 18_1,Reach-1,7
Up Type=0
Dn Type=3
Dn Slope=0.005

--- Kings Creek 18_1.g01 (geometry) ---

Geom Title=Existing Conditions

River Reach=Kings Creek 18_1,Reach-1
Reach XY= 30
      2628476.00      6894161.00      2628532.06      6894209.67
      2628626.08      6894168.80      2628675.92      6894203.24
      2628878.86      6894105.17      2628918.74      6894061.30
      2628877.66      6893966.66      2628922.34      6893918.88
      2628975.99      6893952.94      2629029.33      6893919.01
      2629146.00      6893991.79      2629319.02      6893810.79
      2629185.19      6893717.95      2629218.42      6893661.02
      2629127.64      6893554.96      2629176.19      6893440.80
      2629137.10      6893350.92      2629385.68      6893200.24
      2629619.94      6892969.14      2629828.44      6892905.48
      2629922.55      6892809.52      2629876.07      6892640.97
      2629876.07      6892281.03      2629973.74      6892055.06
      2629976.36      6891890.85      2629877.22      6891500.50
      2629874.78      6891271.50      2629826.07      6891190.97
      2629826.07      6890631.03      2629879.62      6890462.50

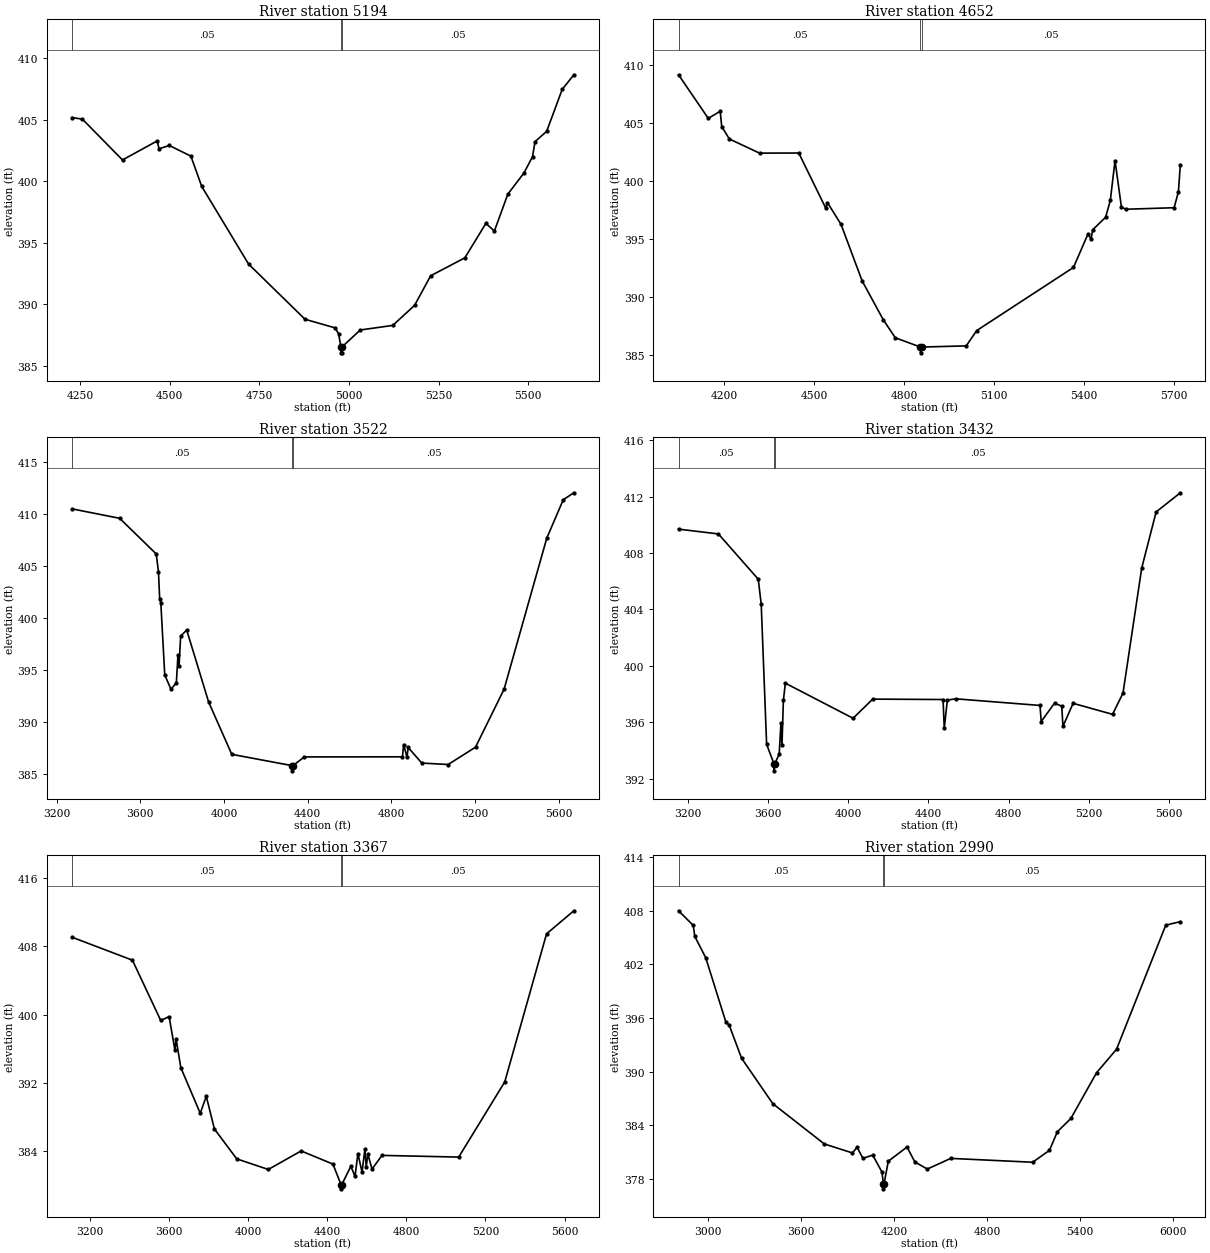
Type RM Length L Ch R = 1,5194,542,542,542
BEGIN DESCRIPTION:
Kings Creek 18_1 9.0
END DESCRIPTION:
XS GIS Cut Line= 3
      2628507.82      6894970.74      2628599.71      6894027.91
      2628426.02      6893611.04
#Sta/Elev= 30
  4228.0  405.17  4256.8  405.04  4368.6  401.72  4465.4  403.27  4470.4  402.63
  4499.0  402.90  4559.3  402.03  4589.4  399.57  4720.1  393.25  4877.5  388.76
  4961.2  388.06  4971.2  387.57  4977.3  386.53  4977.6  386.03  4981.1  386.03
  4981.3  386.53  5031.5  387.89  5122.0  388.26  5182.8  389.89  5227.7  392.30
  5323.1  393.76  5381.6  396.56  5405.4  395.94  5442.8  398.94  5487.7  400.66
  5511.6  401.98  5518.6  403.21  5551.1  404.05  5594.4  407.46  5626.9  408.65
#Mann=3,-1,0
  4228.0    0.05       0  4977.3    0.04       0  4981.3    0.05       0
Bank Sta=4977.3,4981.3
Exp/Cntr=0.3,0.1

Type RM Length L Ch R = 1,4652,1130,1130,1130
BEGIN DESCRIPTION:
Mapping XS a8ede71a
END DESCRIPTION:
XS GIS Cut Line= 4
      2629077.27      6894859.61      2628986.99      6894067.94
      2628889.77      6893949.88      2628522.05      6893325.45
#Sta/Elev= 30
  4047.8  409.18  4147.0  405.42  4186.8  406.03  4191.9  404.71  4217.5  403.64
  4318.1  402.42  4449.0  402.43  4539.5  397.65  4544.5  398.16  4589.9  396.28
  4660.4  391.40  4730.8  388.05  4771.1  386.49  4855.0  385.69  4855.3  385.19
  4859.0  385.69  5007.8  385.79  5042.7  387.11  5365.7  392.56  5414.4  395.46
  5424.2  394.99  5430.0  395.81  5473.0  396.89  5488.6  398.34  5504.3  401.78
  5525.7  397.75  5541.4  397.58  5701.5  397.71  5715.8  399.08  5722.2  401.41
#Mann=3,-1,0
  4047.8    0.05       0  4855.0    0.04       0  4859.0    0.05       0
Bank Sta=4855,4859
Exp/Cntr=0.3,0.1

Type RM Length L Ch R = 1,3522,90,90,90
BEGIN DESCRIPTION:
Mapping XS d6ce62a6
END DESCRIPTION:
XS GIS Cut Line= 6
      2629195.32      6894894.33      2629375.88      6894442.94
      2629535.60      6893776.27      2629535.60      6893685.99
      2629306.44      6893484.60      2628599.57      6893048.03
#Sta/Elev= 30
  3273.9  410.52  3501.4  409.61  3676.0  406.18  3686.8  404.48  3692.6  401.80
  3698.0  401.48  3716.8  394.53  3746.5  393.15  3772.3  393.76  3779.8  396.41
  3784.9  395.34  3792.9  398.27  3821.8  398.85  3926.6  391.91  4037.1  386.88
  4325.6  385.79  4325.9  385.29  4329.6  385.79  4383.5  386.63  4852.8  386.64
  4858.5  387.82  4874.4  386.59  4880.1  387.54  4945.1  386.04  5071.3  385.90
  5202.0  387.57  5338.6  393.16  5542.3  407.69  5621.2  411.40  5671.9  412.07
#Mann=3,-1,0
  3273.9    0.05       0  4325.6    0.04       0  4329.6    0.05       0
Bank Sta=4325.6,4329.6
Exp/Cntr=0.3,0.1

Type RM Length L Ch R = 1,3432,65,65,65
BEGIN DESCRIPTION:
Mapping XS adb8593f
END DESCRIPTION:
XS GIS Cut Line= 6
      2629250.89      6894901.25      2629434.88      6894363.11
      2629592.17      6893760.68      2629591.16      6893672.10
      2629488.00      6893554.78      2628591.12      6892991.52
#Sta/Elev= 30
  3153.8  409.70  3352.7  409.36  3551.4  406.15  3566.2  404.38  3593.2  394.43
  3629.8  393.05  3630.1  392.55  3633.8  393.05  3655.9  393.73  3664.6  395.92
  3669.9  394.38  3676.8  397.55  3686.7  398.77  4024.4  396.28  4122.7  397.64
  4473.4  397.61  4479.3  395.56  4494.7  397.57  4537.0  397.66  4956.9  397.19
  4962.9  396.05  5029.3  397.35  5065.4  397.14  5071.4  395.71  5122.1  397.34
  5318.7  396.56  5370.9  398.06  5464.3  406.94  5536.2  410.92  5656.9  412.28
#Mann=3,-1,0
  3153.8    0.05       0  3629.8    0.04       0  3633.8    0.05       0
Bank Sta=3629.8,3633.8
Exp/Cntr=0.3,0.1

Type RM Length L Ch R = 1,3367,377,377,377
BEGIN DESCRIPTION:
Mapping XS b3baa221
END DESCRIPTION:
XS GIS Cut Line= 6
      2629296.33      6894896.81      2629501.94      6894385.29
      2629644.86      6893778.51      2629627.31      6893595.47
      2629211.09      6893297.10      2628644.46      6892953.61
#Sta/Elev= 30
  3110.4  409.08  3415.5  406.39  3558.5  399.33  3600.9  399.78  3630.5  395.82
  3635.9  397.18  3660.1  393.80  3758.3  388.45  3788.8  390.45  3829.7  386.62
  3942.7  383.11  4102.3  381.87  4268.1  384.04  4429.0  382.50  4469.7  380.10
  4469.9  379.60  4473.7  380.10  4519.6  382.25  4540.5  381.05  4555.2  383.73
  4576.1  381.55  4590.8  384.29  4597.0  382.16  4605.6  383.65  4626.5  381.91
  4676.8  383.52  5064.7  383.32  5297.4  392.13  5508.7  409.48  5646.7  412.18
#Mann=3,-1,0
  3110.4    0.05       0  4469.7    0.04       0  4473.7    0.05       0
Bank Sta=4469.7,4473.7
Exp/Cntr=0.3,0.1

Type RM Length L Ch R = 1,2990,460,460,460
BEGIN DESCRIPTION:
Mapping XS b78839ab
END DESCRIPTION:
XS GIS Cut Line= 6
      2629924.50      6895165.18      2629709.22      6893255.44
      2629514.77      6893095.71      2628785.60      6892609.60
      2628764.77      6892609.60      2628605.07      6892567.94
#Sta/Elev= 30
  2809.6  407.97  2904.4  406.34  2914.4  405.11  2984.9  402.73  3115.7  395.50
  3135.8  395.22  3216.3  391.50  3417.6  386.43  3749.7  381.93  3930.8  380.93
  3961.0  381.56  3998.8  380.32  4061.7  380.69  4122.0  378.78  4130.1  377.42
  4130.3  376.92  4134.1  377.42  4162.3  380.01  4283.0  381.59  4333.4  379.92
  4413.9  379.13  4564.8  380.32  5093.2  379.89  5201.4  381.22  5252.5  383.30
  5339.6  384.78  5504.9  389.88  5634.1  392.51  5951.3  406.36  6045.3  406.76
#Mann=3,-1,0
  2809.6    0.05       0  4130.1    0.04       0  4134.1    0.05       0
Bank Sta=4130.1,4134.1
Exp/Cntr=0.3,0.1

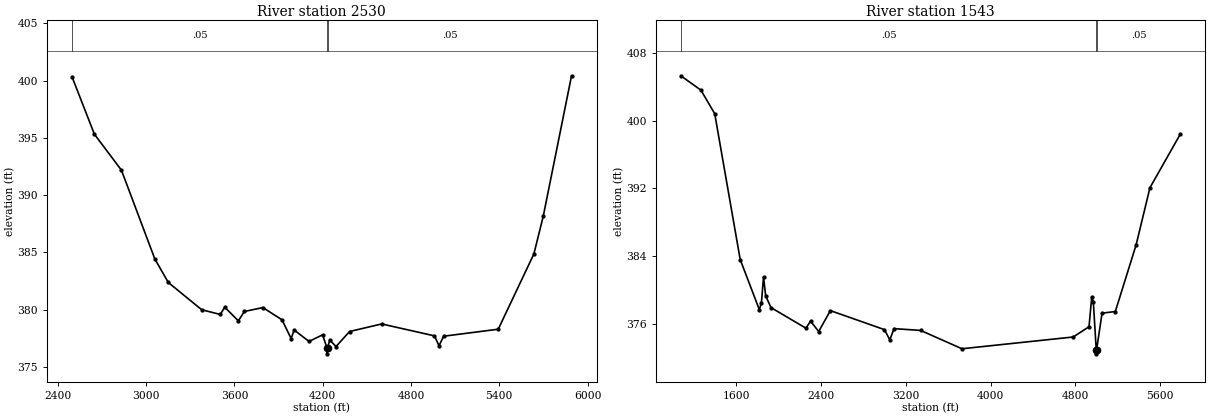
Type RM Length L Ch R = 1,2530,987,987,987
BEGIN DESCRIPTION:
Kings Creek 18_1 3.0
END DESCRIPTION:
XS GIS Cut Line= 3
      2630424.50      6895304.09      2629876.35      6892861.34
      2629326.01      6892161.01
#Sta/Elev= 30
  2496.5  400.35  2648.9  395.33  2832.5  392.19  3059.4  384.44  3151.2  382.38
  3378.1  380.00  3504.0  379.59  3534.8  380.22  3627.0  379.03  3668.0  379.85
  3793.7  380.19  3923.7  379.12  3985.7  377.48  4006.2  378.23  4107.3  377.23
  4199.1  377.81  4229.7  376.65  4229.9  376.15  4233.7  376.65  4247.5  377.36
  4290.9  376.79  4382.7  378.10  4600.7  378.76  4959.4  377.72  4990.1  376.86
  5022.2  377.69  5392.7  378.30  5634.9  384.87  5699.1  388.20  5890.7  400.43
#Mann=3,-1,0
  2496.5    0.05       0  4229.7    0.04       0  4233.7    0.05       0
Bank Sta=4229.7,4233.7
Exp/Cntr=0.3,0.1

Type RM Length L Ch R = 1,1543,0,0,0
BEGIN DESCRIPTION:
Kings Creek 18_1 2.0
END DESCRIPTION:
XS GIS Cut Line= 4
      2630716.16      6895290.15      2630778.66      6892220.71
      2629976.20      6891940.94      2629189.68      6891873.60
#Sta/Elev= 30
  1080.1  405.32  1269.3  403.62  1399.3  400.84  1639.4  383.60  1819.4  377.69
  1839.4  378.44  1859.4  381.54  1879.4  379.32  1929.4  377.92  2259.5  375.48
  2302.4  376.32  2379.5  375.09  2489.5  377.56  2999.6  375.31  3049.7  374.10
  3089.7  375.43  3339.7  375.22  3729.8  373.05  4777.8  374.44  4927.6  375.65
  4953.4  379.18  4968.4  378.58  4995.5  372.95  4995.7  372.45  4999.5  372.95
  5050.4  377.26  5175.5  377.45  5371.6  385.33  5502.0  392.09  5789.4  398.45
#Mann=3,-1,0
  1080.1    0.05       0  4995.5    0.04       0  4999.5    0.05       0
Bank Sta=4995.5,4999.5
Exp/Cntr=0.3,0.1

Chan Stop Cuts=-1