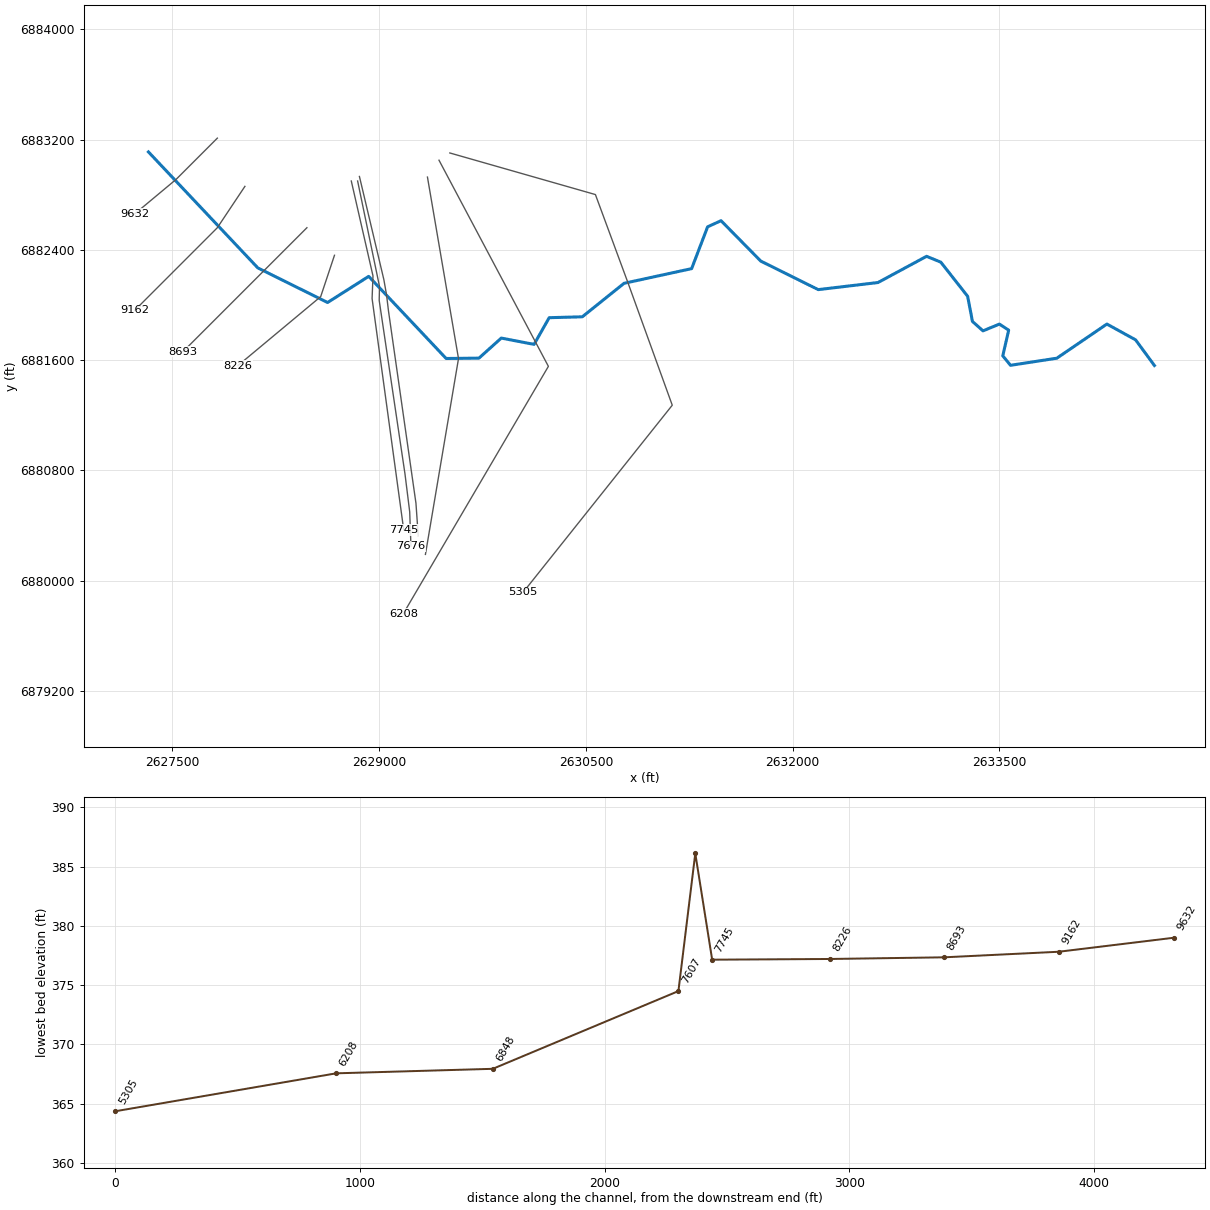
--- Kings Creek 20.prj (project) ---

Proj Title=Kings Creek 20 Base Level Engineering
Current Plan=p01
Default Exp/Contr=0.3,0.1
English Units
Geom File=g01
Flow File=f01
Plan File=p01
BEGIN DESCRIPTION:
Kings Creek 20
END DESCRIPTION:

--- Kings Creek 20.p01 (plan) ---

Plan Title=Multiple Run
Short Identifier=Multiple
Geom File=g01
Flow File=f01
Subcritical Flow
K Sum by GR= 0
Std Step Tol= 0.01
Critical Tol= 0.01
Num of Std Step Trials= 20
Max Error Tol= 0.3
Flow Tol Ratio= 0.001
Split Flow NTrial= 30
Split Flow Tol= 0.02
Split Flow Ratio= 0.02
Log Output Level= 0
Friction Slope Method= 1
Unsteady Friction Slope Method= 2
Unsteady Bridges Friction Slope Method= 1
Parabolic Critical Depth
Global Vel Dist=  1 , 1 , 1
Global Log Level= 0
CheckData=True
Encroach Param= -1, 0, 0, 0
BEGIN DESCRIPTION:
Multiple Run
END DESCRIPTION:

--- Kings Creek 20.f01 (steady flow) ---

Flow Title=Multiple
Number of Profiles=7
Profile Names=10-year,25-year,50-year,1pct_min,100-year,1pct_plu,500-year
River Rch & RM= Kings Creek 20,Reach-1,9632
     661     901    1098     664    1325    2644    1930
River Rch & RM= Kings Creek 20,Reach-1,8226
     586     788     952     570    1137    2268    1623
River Rch & RM= Kings Creek 20,Reach-1,6848
    1074    1491    1837    1121    2236    4461    3315
Boundary for River Rch & Prof#=Kings Creek 20,Reach-1,1
Up Type=0
Dn Type=3
Dn Slope=0.005
Boundary for River Rch & Prof#=Kings Creek 20,Reach-1,2
Up Type=0
Dn Type=3
Dn Slope=0.005
Boundary for River Rch & Prof#=Kings Creek 20,Reach-1,3
Up Type=0
Dn Type=3
Dn Slope=0.005
Boundary for River Rch & Prof#=Kings Creek 20,Reach-1,4
Up Type=0
Dn Type=3
Dn Slope=0.005
Boundary for River Rch & Prof#=Kings Creek 20,Reach-1,5
Up Type=0
Dn Type=3
Dn Slope=0.005
Boundary for River Rch & Prof#=Kings Creek 20,Reach-1,6
Up Type=0
Dn Type=3
Dn Slope=0.005
Boundary for River Rch & Prof#=Kings Creek 20,Reach-1,7
Up Type=0
Dn Type=3
Dn Slope=0.005

--- Kings Creek 20.g01 (geometry) ---

Geom Title=Existing Conditions

River Reach=Kings Creek 20,Reach-1
Reach XY= 30
      2627326.00      6883111.00      2628119.95      6882269.16
      2628626.10      6882018.31      2628924.42      6882207.93
      2629486.29      6881612.00      2629724.54      6881614.54
      2629886.48      6881760.07      2630124.52      6881714.45
      2630233.97      6881908.07      2630474.53      6881914.55
      2630777.26      6882157.52      2631267.72      6882264.07
      2631383.73      6882567.51      2631481.01      6882611.88
      2631769.55      6882318.74      2632186.68      6882111.75
      2632620.07      6882163.24      2632972.62      6882353.40
      2633076.00      6882311.00      2633270.53      6882063.45
      2633305.48      6881880.71      2633382.03      6881812.62
      2633501.13      6881861.53      2633568.36      6881817.55
      2633525.56      6881631.00      2633581.80      6881562.54
      2633917.69      6881614.09      2634281.04      6881861.85
      2634489.21      6881747.37      2634626.00      6881561.00

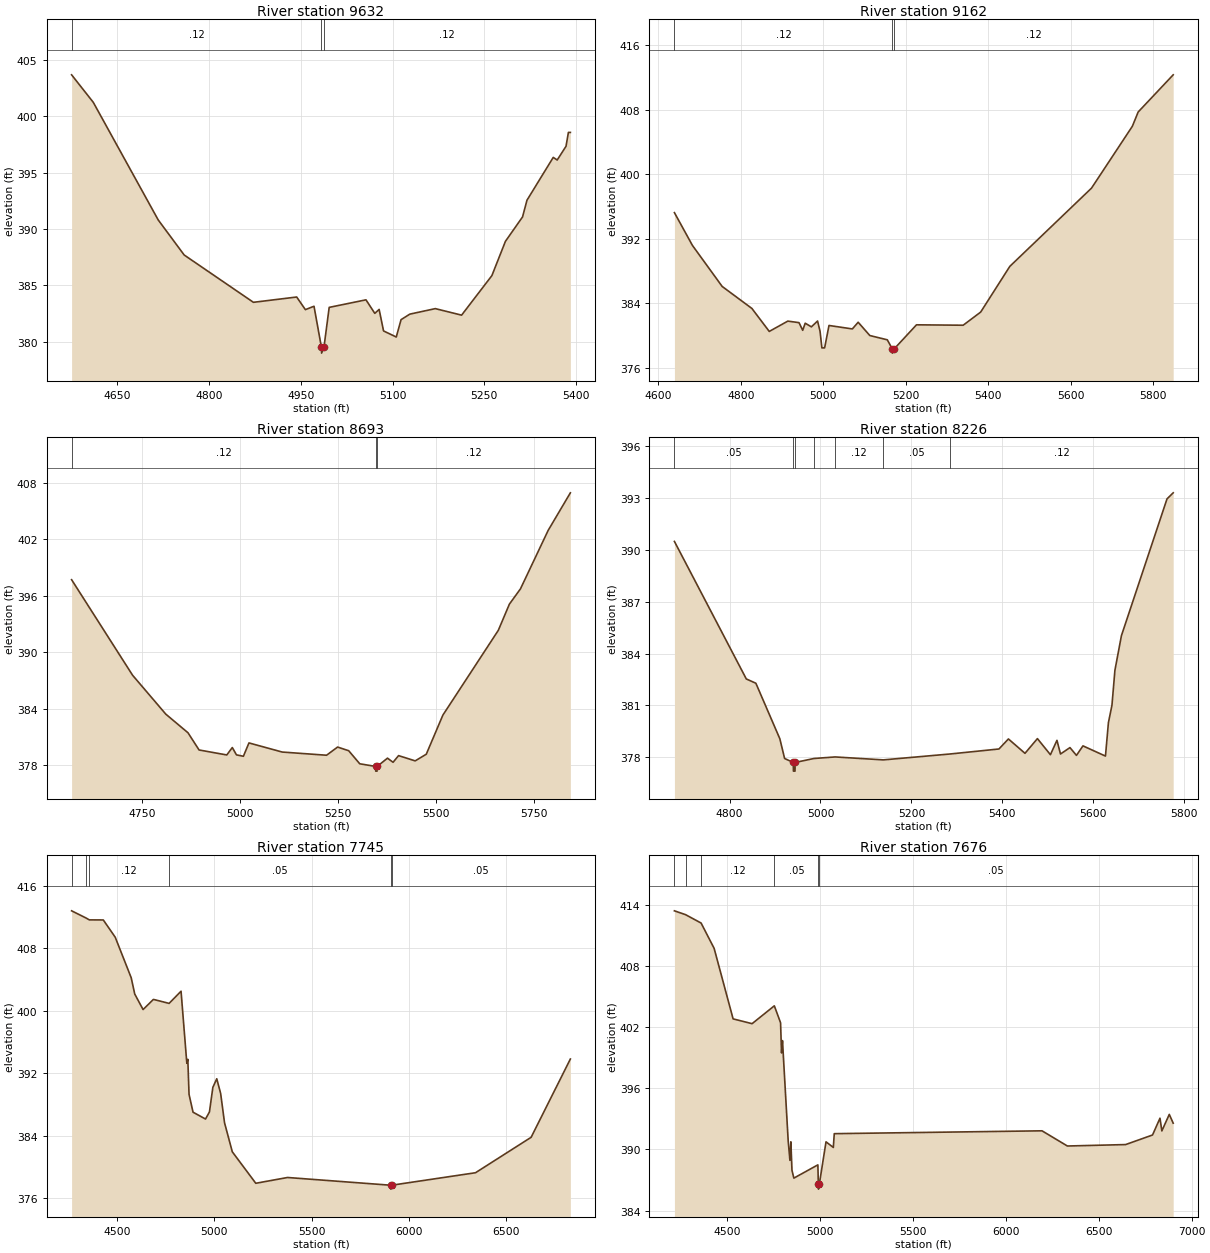
Type RM Length L Ch R = 1,9632,470,470,470
BEGIN DESCRIPTION:
Kings Creek 20 14.0
END DESCRIPTION:
XS GIS Cut Line= 3
      2627826.03      6883211.03      2627526.00      6882911.00
      2627226.02      6882661.01
#Sta/Elev= 30
  4575.7  403.69  4611.1  401.25  4717.2  390.81  4759.6  387.70  4872.7  383.50
  4943.4  383.97  4957.6  382.85  4971.7  383.15  4983.9  379.49  4984.1  378.99
  4987.9  379.49  4996.5  383.05  5056.6  383.72  5071.0  382.52  5078.1  382.87
  5085.3  380.96  5106.1  380.42  5113.9  381.96  5128.2  382.45  5169.9  382.94
  5212.8  382.36  5262.3  385.87  5284.4  388.91  5312.4  391.08  5319.6  392.56
  5362.5  396.36  5369.0  396.13  5383.4  397.35  5387.3  398.58  5390.5  398.58
#Mann=3,-1,0
  4575.7    0.12       0  4983.9    0.07       0  4987.9    0.12       0
Bank Sta=4983.9,4987.9
Exp/Cntr=0.3,0.1

Type RM Length L Ch R = 1,9162,469,469,469
BEGIN DESCRIPTION:
Kings Creek 20 13.0
END DESCRIPTION:
XS GIS Cut Line= 3
      2628026.00      6882861.00      2627826.00      6882561.00
      2627225.99      6881960.99
#Sta/Elev= 30
  4639.2  395.23  4682.8  391.17  4754.9  386.08  4827.0  383.35  4869.1  380.50
  4914.1  381.78  4941.2  381.59  4950.2  380.64  4956.2  381.52  4971.2  381.07
  4986.2  381.79  4992.2  380.52  4996.7  378.46  5003.3  378.46  5013.9  381.24
  5070.5  380.81  5084.6  381.64  5112.9  379.99  5155.3  379.46  5167.5  378.31
  5167.7  377.81  5171.5  378.31  5226.0  381.32  5339.2  381.27  5381.6  382.90
  5452.3  388.57  5650.3  398.27  5749.3  405.94  5763.4  407.71  5848.3  412.32
#Mann=3,-1,0
  4639.2    0.12       0  5167.5    0.07       0  5171.5    0.12       0
Bank Sta=5167.5,5171.5
Exp/Cntr=0.3,0.1

Type RM Length L Ch R = 1,8693,467,467,467
BEGIN DESCRIPTION:
Kings Creek 20 12.0
END DESCRIPTION:
XS GIS Cut Line= 3
      2628476.01      6882561.01      2628176.00      6882261.00
      2627576.00      6881661.00
#Sta/Elev= 30
  4570.9  397.70  4726.5  387.54  4811.3  383.40  4867.9  381.42  4896.2  379.59
  4966.9  379.06  4981.0  379.85  4991.6  379.07  5009.3  378.92  5023.5  380.34
  5108.3  379.37  5221.5  379.03  5249.7  379.90  5278.0  379.51  5306.3  378.12
  5346.7  377.84  5347.0  377.34  5350.5  377.34  5350.7  377.84  5377.0  378.72
  5391.2  378.28  5405.3  378.99  5447.7  378.43  5476.0  379.14  5518.4  383.30
  5659.9  392.32  5688.1  395.10  5716.4  396.73  5787.1  402.95  5843.7  406.94
#Mann=3,-1,0
  4570.9    0.12       0  5346.7    0.07       0  5350.7    0.12       0
Bank Sta=5346.7,5350.7
Exp/Cntr=0.3,0.1

Type RM Length L Ch R = 1,8226,481,481,481
BEGIN DESCRIPTION:
Kings Creek 20 11.0
END DESCRIPTION:
XS GIS Cut Line= 3
      2628676.00      6882360.99      2628576.00      6882061.00
      2627976.03      6881561.02
#Sta/Elev= 30
  4678.7  390.48  4836.8  382.53  4857.9  382.28  4910.6  379.07  4921.1  377.93
  4940.2  377.70  4940.5  377.20  4944.0  377.20  4944.2  377.70  4985.5  377.93
  5032.1  378.02  5138.2  377.85  5284.8  378.19  5392.6  378.48  5413.4  379.06
  5449.9  378.23  5477.2  379.08  5505.8  378.15  5520.2  378.98  5528.0  378.19
  5548.8  378.56  5563.1  378.11  5577.4  378.66  5626.9  378.07  5633.4  380.00
  5641.2  381.01  5647.7  383.03  5662.0  385.03  5762.3  392.94  5775.9  393.29
#Mann=7,-1,0
  4678.7    0.05       0  4940.2    0.07       0  4944.2    0.05       0
  4985.5     0.1       0  5032.1    0.12       0  5138.2    0.05       0
  5284.8    0.12       0
Bank Sta=4940.2,4944.2
Exp/Cntr=0.3,0.1

Type RM Length L Ch R = 1,7745,69,69,69
BEGIN DESCRIPTION:
Mapping XS dbbb4897
END DESCRIPTION:
XS GIS Cut Line= 4
      2628798.03      6882899.97      2628955.49      6882211.08
      2628948.93      6882047.05      2629178.56      6880367.49
#Sta/Elev= 30
  4265.6  412.80  4339.2  411.89  4356.7  411.64  4428.7  411.63  4490.2  409.41
  4572.3  404.22  4590.4  402.14  4633.3  400.15  4686.5  401.45  4767.2  400.94
  4828.7  402.50  4858.4  393.26  4863.5  393.77  4869.8  389.28  4890.3  387.00
  4954.5  386.12  4974.8  387.03  4992.3  390.18  5012.4  391.28  5032.4  389.40
  5052.4  385.64  5092.4  381.92  5213.2  377.89  5376.4  378.63  5906.8  377.64
  5907.6  377.14  5912.3  377.64  6343.6  379.24  6629.7  383.78  6831.6  393.81
#Mann=6,-1,0
  4265.6    0.12       0  4339.2    0.05       0  4356.7    0.12       0
  4767.2    0.05       0  5906.8    0.03       0  5912.3    0.05       0
Bank Sta=5906.8,5912.3
Exp/Cntr=0.3,0.1

Type RM Length L Ch R = 1,7676,69,69,69
BEGIN DESCRIPTION:
Mapping XS 23caac38
END DESCRIPTION:
XS GIS Cut Line= 6
      2628843.95      6882900.01      2629002.80      6882134.32
      2629000.45      6882033.88      2629187.52      6880775.20
      2629221.81      6880499.59      2629231.02      6880250.02
#Sta/Elev= 30
  4218.0  413.41  4278.3  413.03  4361.5  412.21  4431.5  409.73  4533.6  402.81
  4635.7  402.34  4755.3  404.09  4788.9  402.43  4794.1  399.47  4799.2  400.68
  4829.8  390.87  4839.2  388.93  4844.3  390.75  4850.2  387.96  4860.4  387.19
  4989.6  388.49  4992.0  386.61  4992.8  386.11  4997.5  386.61  5033.3  390.75
  5072.7  390.20  5077.7  391.55  6195.1  391.83  6331.6  390.34  6644.7  390.48
  6789.6  391.42  6829.7  393.07  6839.7  391.82  6879.7  393.44  6900.7  392.58
#Mann=6,-1,0
  4218.0    0.12       0  4278.3    0.05       0  4361.5    0.12       0
  4755.3    0.05       0  4992.0    0.03       0  4997.5    0.05       0
Bank Sta=4992,4997.5
Exp/Cntr=0.3,0.1

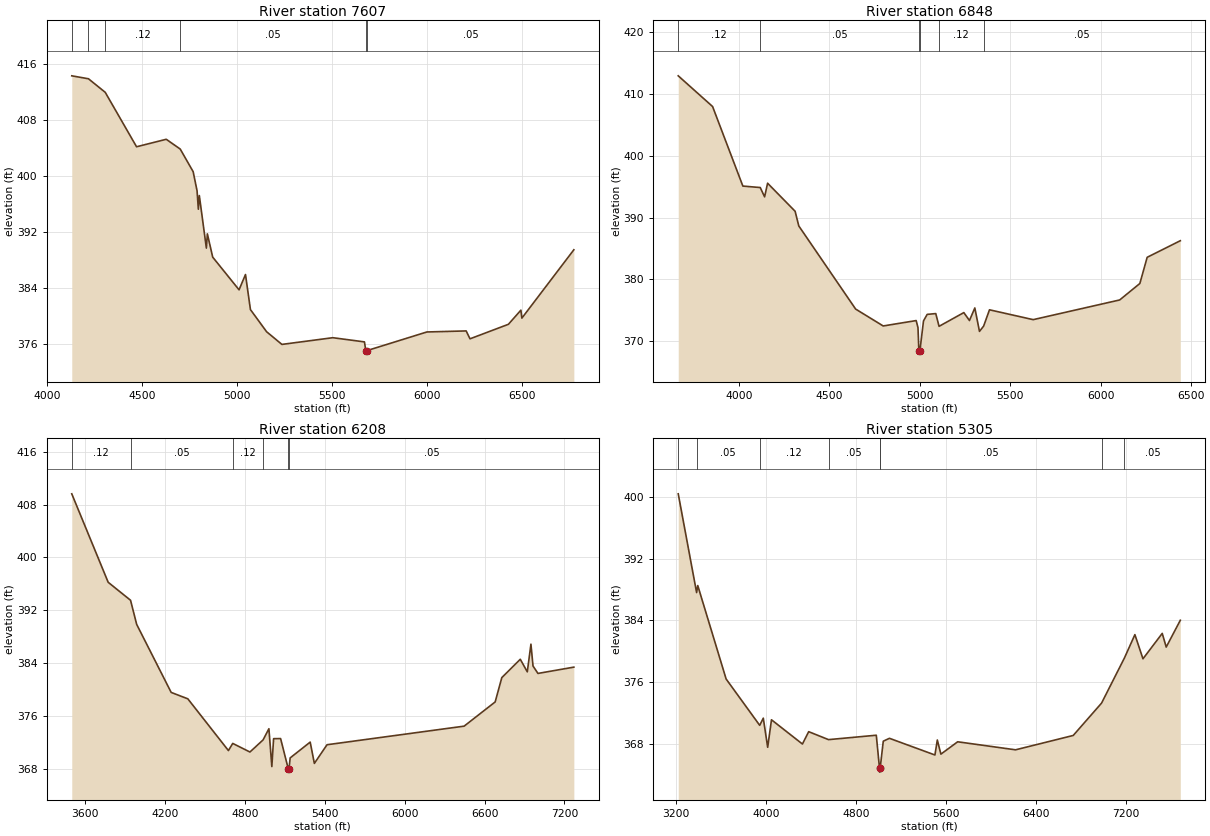
Type RM Length L Ch R = 1,7607,759,759,759
BEGIN DESCRIPTION:
Mapping XS 7d872e65
END DESCRIPTION:
XS GIS Cut Line= 6
      2628857.07      6882932.79      2629034.22      6882184.83
      2629053.90      6882073.30      2629067.73      6881958.36
      2629267.38      6880560.79      2629283.54      6880328.08
#Sta/Elev= 30
  4130.2  414.31  4218.0  413.89  4306.3  411.95  4471.2  404.16  4627.5  405.23
  4701.1  403.83  4769.2  400.59  4789.7  397.86  4796.5  395.22  4801.6  397.18
  4838.7  389.66  4843.9  391.70  4872.0  388.37  5010.7  383.69  5044.6  385.88
  5070.7  380.86  5155.8  377.69  5236.3  375.88  5504.3  376.84  5670.7  376.24
  5678.0  374.99  5678.8  374.49  5683.5  374.99  5999.3  377.66  6206.1  377.81
  6226.3  376.68  6428.6  378.76  6494.2  380.78  6499.3  379.64  6772.9  389.42
#Mann=6,-1,0
  4130.2    0.12       0  4218.0    0.05       0  4306.3    0.12       0
  4701.1    0.05       0  5678.0    0.03       0  5683.5    0.05       0
Bank Sta=5678,5683.5
Exp/Cntr=0.3,0.1

Type RM Length L Ch R = 1,6848,640,640,640
BEGIN DESCRIPTION:
Kings Creek 20 8.0
END DESCRIPTION:
XS GIS Cut Line= 3
      2629350.71      6882928.26      2629576.00      6881611.00
      2629336.02      6880190.31
#Sta/Elev= 30
  3663.5  412.89  3853.5  407.93  4021.0  395.08  4117.2  394.84  4141.2  393.34
  4157.8  395.54  4310.0  391.01  4330.3  388.64  4644.8  375.21  4797.2  372.48
  4979.6  373.35  4989.7  372.21  4994.6  368.43  4995.4  367.93  5000.1  368.43
  5020.2  373.29  5040.5  374.35  5088.0  374.48  5106.2  372.42  5243.3  374.64
  5274.4  373.36  5304.1  375.39  5329.8  371.60  5352.8  372.46  5385.2  375.09
  5626.9  373.50  6105.3  376.68  6216.9  379.34  6257.4  383.57  6440.7  386.25
#Mann=6,-1,0
  3663.5    0.12       0  4117.2    0.05       0  4994.6    0.03       0
  5000.1    0.05       0  5106.2    0.12       0  5352.8    0.05       0
Bank Sta=4994.6,5000.1
Exp/Cntr=0.3,0.1

Type RM Length L Ch R = 1,6208,903,903,903
BEGIN DESCRIPTION:
Kings Creek 20 7.0
END DESCRIPTION:
XS GIS Cut Line= 3
      2629434.42      6883050.91      2630228.31      6881554.99
      2629175.98      6879760.97
#Sta/Elev= 30
  3497.6  409.62  3771.2  396.25  3939.3  393.53  3985.5  389.88  4244.7  379.60
  4369.9  378.63  4674.9  370.81  4707.4  371.89  4836.6  370.59  4935.4  372.42
  4979.2  374.11  5001.2  368.39  5014.5  372.61  5067.2  372.62  5124.7  368.05
  5125.5  367.55  5130.3  368.05  5139.0  369.70  5289.5  372.09  5320.8  368.87
  5416.0  371.69  6446.4  374.50  6679.7  378.16  6729.7  381.84  6868.4  384.61
  6921.2  382.71  6948.5  386.89  6964.2  383.59  7001.3  382.47  7271.0  383.42
#Mann=6,-1,0
  3497.6    0.12       0  3939.3    0.05       0  4707.4    0.12       0
  4935.4    0.05       0  5124.7    0.03       0  5130.3    0.05       0
Bank Sta=5124.7,5130.3
Exp/Cntr=0.3,0.1

Type RM Length L Ch R = 1,5305,0,0,0
BEGIN DESCRIPTION:
Kings Creek 20 6.0
END DESCRIPTION:
XS GIS Cut Line= 5
      2629513.17      6883103.36      2630569.47      6882801.56
      2630805.76      6882161.45      2631127.15      6881272.87
      2630045.09      6879915.38
#Sta/Elev= 30
  3219.1  400.40  3382.4  387.61  3392.6  388.52  3644.8  376.41  3943.2  370.41
  3975.0  371.34  4014.0  367.57  4047.8  371.13  4322.8  367.99  4378.4  369.59
  4554.6  368.56  4979.2  369.13  5007.8  364.85  5008.7  364.35  5013.4  364.85
  5041.3  368.36  5096.2  368.73  5500.3  366.57  5521.5  368.51  5553.4  366.68
  5702.3  368.28  6216.9  367.24  6729.3  369.10  6981.1  373.29  7184.8  379.15
  7277.3  382.16  7349.1  379.03  7520.3  382.32  7555.7  380.55  7680.9  384.02
#Mann=8,-1,0
  3219.1    0.12       0  3382.4    0.05       0  3943.2    0.12       0
  4554.6    0.05       0  5007.8    0.03       0  5013.4    0.05       0
  6981.1    0.12       0  7184.8    0.05       0
Bank Sta=5007.8,5013.4
Exp/Cntr=0.3,0.1

Chan Stop Cuts=-1