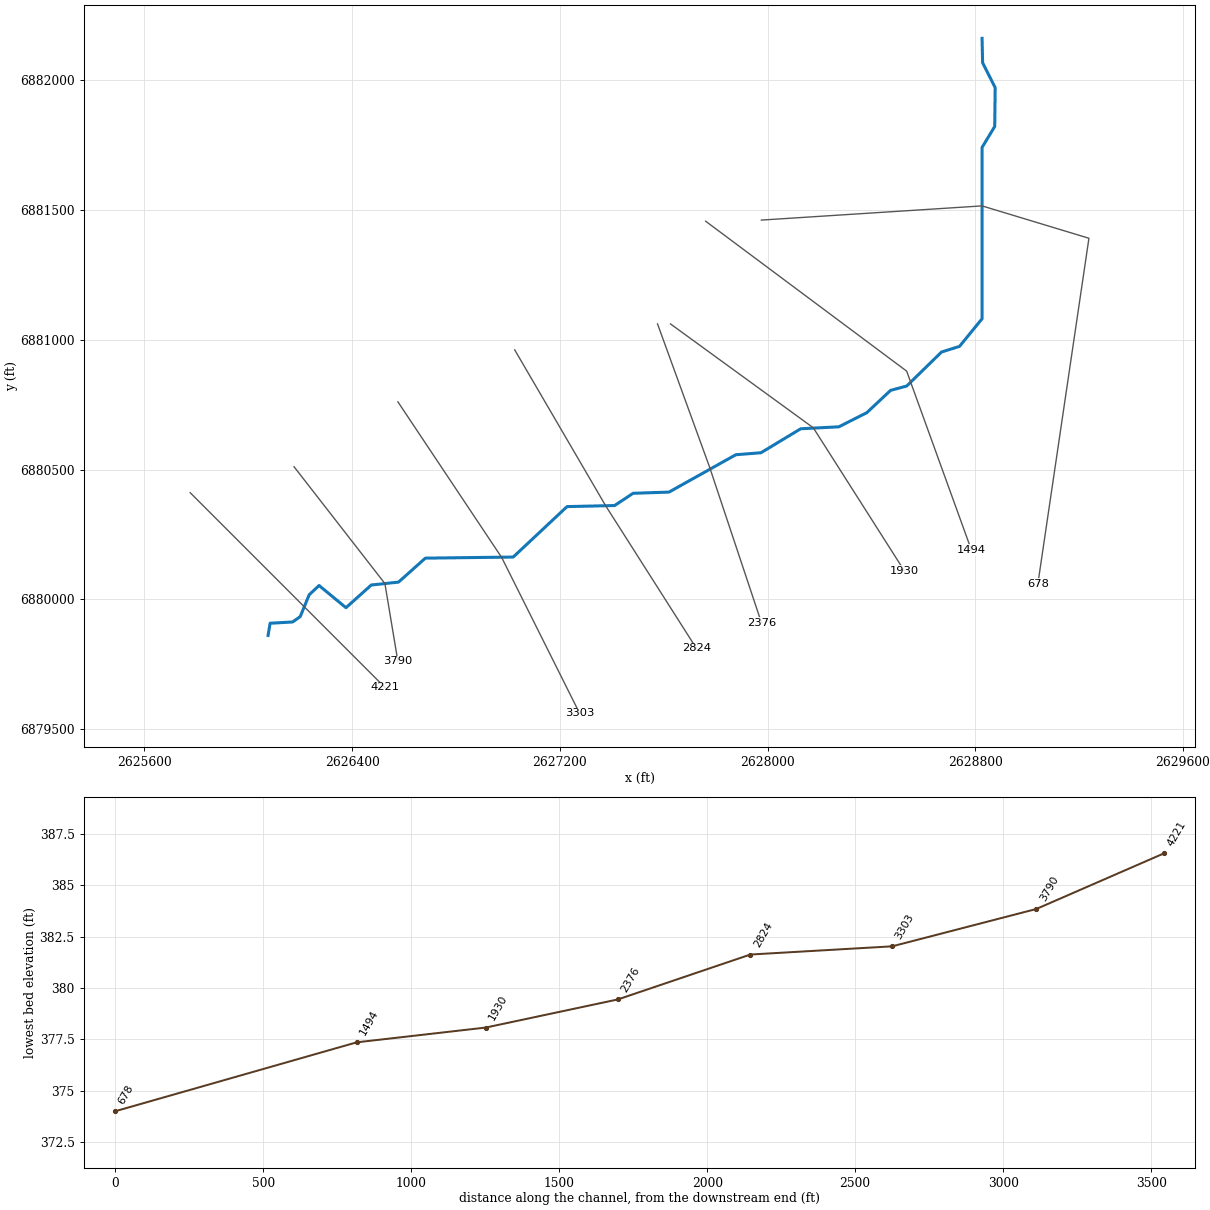
--- Kings Creek 20_1.prj (project) ---

Proj Title=Kings Creek 20_1 Base Level Engineering
Current Plan=p01
Default Exp/Contr=0.3,0.1
English Units
Geom File=g01
Flow File=f01
Plan File=p01
BEGIN DESCRIPTION:
Kings Creek 20_1
END DESCRIPTION:

--- Kings Creek 20_1.p01 (plan) ---

Plan Title=Multiple Run
Short Identifier=Multiple
Geom File=g01
Flow File=f01
Subcritical Flow
K Sum by GR= 0
Std Step Tol= 0.01
Critical Tol= 0.01
Num of Std Step Trials= 20
Max Error Tol= 0.3
Flow Tol Ratio= 0.001
Split Flow NTrial= 30
Split Flow Tol= 0.02
Split Flow Ratio= 0.02
Log Output Level= 0
Friction Slope Method= 1
Unsteady Friction Slope Method= 2
Unsteady Bridges Friction Slope Method= 1
Parabolic Critical Depth
Global Vel Dist=  1 , 1 , 1
Global Log Level= 0
CheckData=True
Encroach Param= -1, 0, 0, 0
BEGIN DESCRIPTION:
Multiple Run
END DESCRIPTION:

--- Kings Creek 20_1.f01 (steady flow) ---

Flow Title=Multiple
Number of Profiles=7
Profile Names=10-year,25-year,50-year,1pct_min,100-year,1pct_plu,500-year
River Rch & RM= Kings Creek 20_1,Reach-1,4221
     555     745     899     538    1073    2142    1530
Boundary for River Rch & Prof#=Kings Creek 20_1,Reach-1,1
Up Type=0
Dn Type=3
Dn Slope=0.005
Boundary for River Rch & Prof#=Kings Creek 20_1,Reach-1,2
Up Type=0
Dn Type=3
Dn Slope=0.005
Boundary for River Rch & Prof#=Kings Creek 20_1,Reach-1,3
Up Type=0
Dn Type=3
Dn Slope=0.005
Boundary for River Rch & Prof#=Kings Creek 20_1,Reach-1,4
Up Type=0
Dn Type=3
Dn Slope=0.005
Boundary for River Rch & Prof#=Kings Creek 20_1,Reach-1,5
Up Type=0
Dn Type=3
Dn Slope=0.005
Boundary for River Rch & Prof#=Kings Creek 20_1,Reach-1,6
Up Type=0
Dn Type=3
Dn Slope=0.005
Boundary for River Rch & Prof#=Kings Creek 20_1,Reach-1,7
Up Type=0
Dn Type=3
Dn Slope=0.005

--- Kings Creek 20_1.g01 (geometry) ---

Geom Title=Existing Conditions

River Reach=Kings Creek 20_1,Reach-1
Reach XY= 30
      2626076.00      6879861.00      2626083.77      6879908.15
      2626170.26      6879913.02      2626199.89      6879933.73
      2626234.17      6880017.69      2626272.42      6880053.50
      2626375.99      6879968.11      2626473.57      6880055.45
      2626578.42      6880066.54      2626681.86      6880158.93
      2627020.15      6880163.06      2627227.46      6880357.46
      2627410.78      6880361.52      2627481.94      6880408.73
      2627620.07      6880413.25      2627877.58      6880557.17
      2627974.42      6880564.83      2628127.56      6880657.24
      2628274.44      6880664.76      2628382.05      6880719.16
      2628473.72      6880805.13      2628535.68      6880821.78
      2628669.95      6880952.84      2628739.24      6880974.62
      2628826.04      6881080.98      2628826.07      6881740.97
      2628874.78      6881821.51      2628876.46      6881971.19
      2628828.10      6882066.87      2628826.00      6882161.00

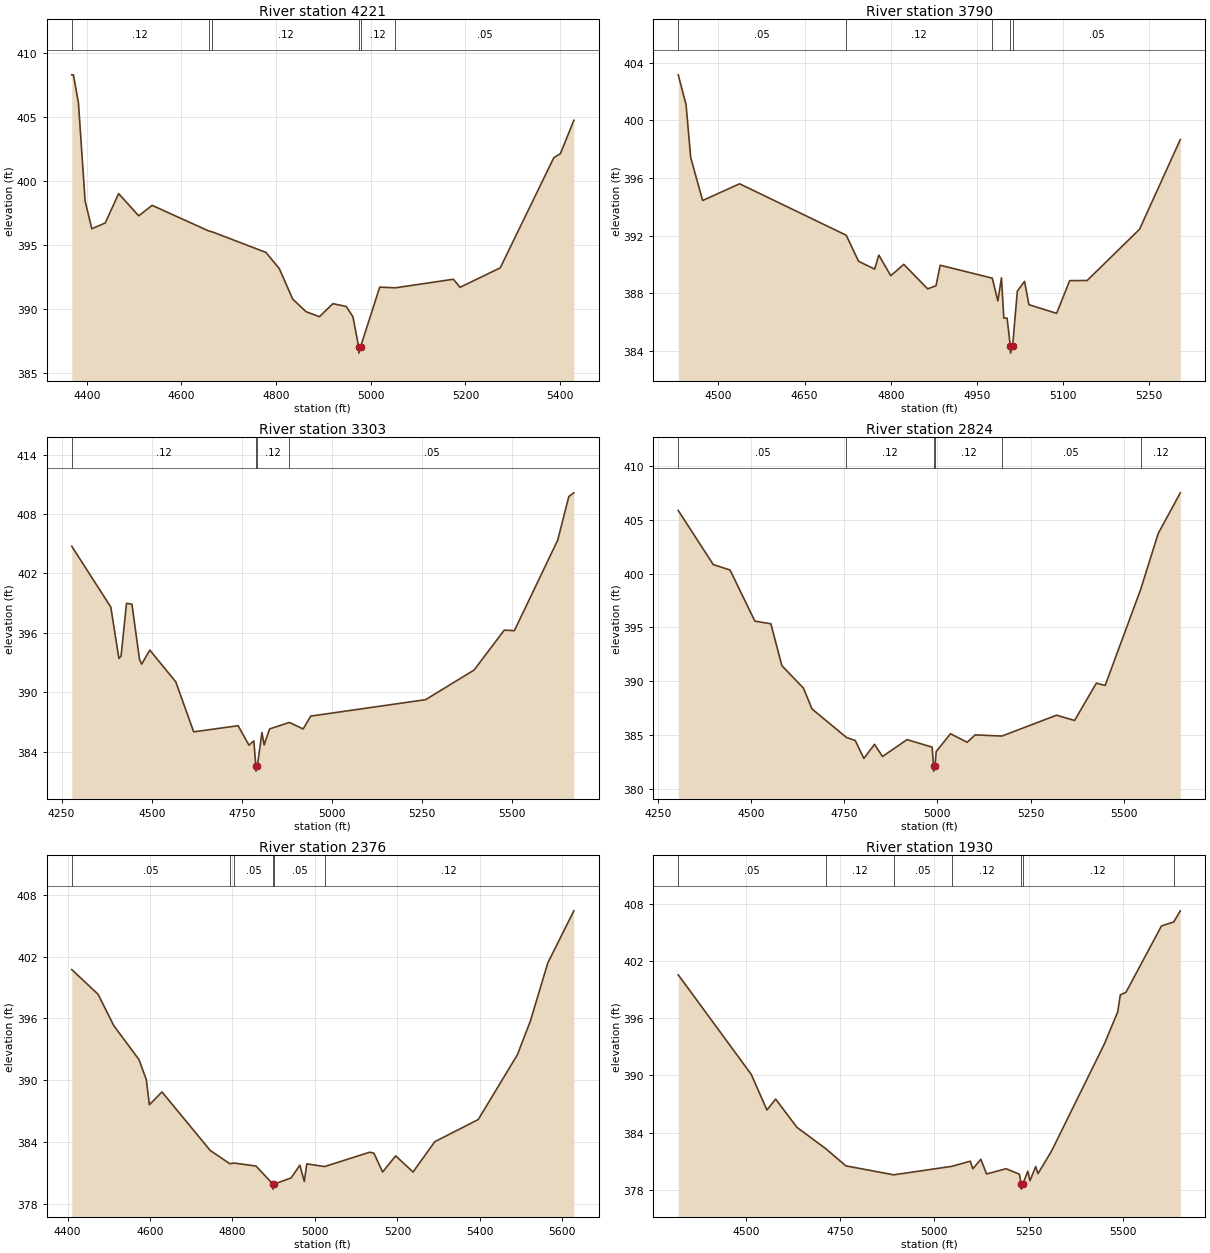
Type RM Length L Ch R = 1,4221,431,431,431
BEGIN DESCRIPTION:
Kings Creek 20_1 7.0
END DESCRIPTION:
XS GIS Cut Line= 3
      2625776.03      6880410.97      2626226.00      6879961.00
      2626525.99      6879661.01
#Sta/Elev= 30
  4368.3  408.33  4371.8  408.33  4382.4  406.14  4396.5  398.45  4410.7  396.29
  4439.0  396.74  4467.3  399.04  4509.7  397.30  4538.0  398.12  4657.4  396.12
  4665.5  396.04  4778.4  394.44  4806.7  393.17  4835.0  390.79  4863.2  389.80
  4891.5  389.41  4919.8  390.43  4948.1  390.21  4962.2  389.41  4974.4  387.06
  4974.6  386.56  4978.4  387.06  5018.8  391.72  5052.1  391.67  5174.4  392.34
  5188.5  391.71  5273.4  393.23  5386.5  401.84  5400.6  402.17  5428.9  404.77
#Mann=6,-1,0
  4368.3    0.12       0  4657.4    0.05       0  4665.5    0.12       0
  4974.4    0.07       0  4978.4    0.12       0  5052.1    0.05       0
Bank Sta=4974.4,4978.4
Exp/Cntr=0.3,0.1

Type RM Length L Ch R = 1,3790,487,487,487
BEGIN DESCRIPTION:
Kings Creek 20_1 6.0
END DESCRIPTION:
XS GIS Cut Line= 3
      2626176.00      6880511.00      2626526.00      6880061.00
      2626576.00      6879761.02
#Sta/Elev= 30
  4429.9  403.16  4443.5  401.10  4451.6  397.42  4472.4  394.44  4536.7  395.60
  4722.4  392.03  4743.9  390.22  4771.9  389.68  4779.2  390.65  4800.0  389.22
  4822.6  390.01  4864.2  388.31  4878.7  388.52  4886.0  389.95  4976.7  389.05
  4986.4  387.47  4992.7  389.08  4996.8  386.28  5002.5  386.28  5008.1  384.35
  5008.4  383.85  5012.1  384.35  5020.3  388.15  5032.9  388.83  5040.5  387.21
  5088.7  386.61  5111.5  388.88  5141.9  388.89  5233.2  392.45  5304.1  398.67
#Mann=5,-1,0
  4429.9    0.05       0  4722.4    0.12       0  4976.7    0.05       0
  5008.1    0.03       0  5012.1    0.05       0
Bank Sta=5008.1,5012.1
Exp/Cntr=0.3,0.1

Type RM Length L Ch R = 1,3303,479,479,479
BEGIN DESCRIPTION:
Kings Creek 20_1 5.0
END DESCRIPTION:
XS GIS Cut Line= 3
      2626576.00      6880761.00      2626976.00      6880161.00
      2627275.99      6879561.02
#Sta/Elev= 30
  4278.4  404.75  4386.6  398.61  4409.1  393.42  4415.1  393.66  4430.1  398.98
  4445.2  398.90  4466.2  393.32  4472.2  392.84  4494.7  394.26  4566.8  391.05
  4616.4  386.00  4739.6  386.62  4769.7  384.65  4783.2  385.09  4788.7  382.53
  4788.9  382.03  4792.7  382.53  4805.7  385.94  4811.7  384.67  4826.7  386.29
  4881.7  386.95  4919.9  386.29  4940.9  387.59  5259.4  389.25  5393.6  392.24
  5477.5  396.28  5505.4  396.22  5625.6  405.37  5656.4  409.78  5670.3  410.15
#Mann=4,-1,0
  4278.4    0.12       0  4788.7    0.03       0  4792.7    0.12       0
  4881.7    0.05       0
Bank Sta=4788.7,4792.7
Exp/Cntr=0.3,0.1

Type RM Length L Ch R = 1,2824,448,448,448
BEGIN DESCRIPTION:
Kings Creek 20_1 4.0
END DESCRIPTION:
XS GIS Cut Line= 3
      2627025.98      6880961.04      2627376.00      6880361.00
      2627726.01      6879810.99
#Sta/Elev= 30
  4304.9  405.87  4398.8  400.84  4443.9  400.33  4510.4  395.58  4553.4  395.33
  4582.8  391.44  4640.7  389.35  4663.8  387.41  4756.1  384.76  4779.6  384.48
  4802.8  382.81  4831.3  384.12  4852.8  382.99  4918.5  384.56  4985.9  383.86
  4989.7  382.13  4990.0  381.63  4993.7  382.13  4996.7  383.45  5035.1  385.11
  5080.0  384.31  5101.2  385.00  5172.9  384.89  5319.6  386.83  5367.9  386.34
  5426.3  389.81  5450.0  389.60  5545.2  398.53  5592.2  403.73  5651.5  407.51
#Mann=6,-1,0
  4304.9    0.05       0  4756.1    0.12       0  4989.7    0.07       0
  4993.7    0.12       0  5172.9    0.05       0  5545.2    0.12       0
Bank Sta=4989.7,4993.7
Exp/Cntr=0.3,0.1

Type RM Length L Ch R = 1,2376,446,446,446
BEGIN DESCRIPTION:
Kings Creek 20_1 3.0
END DESCRIPTION:
XS GIS Cut Line= 3
      2627575.99      6881061.03      2627776.00      6880511.00
      2627975.99      6879911.02
#Sta/Elev= 30
  4410.2  400.74  4474.1  398.34  4512.0  395.31  4573.2  392.01  4591.1  390.05
  4598.4  387.62  4629.0  388.87  4746.1  383.19  4793.7  381.90  4804.0  381.97
  4857.1  381.68  4897.7  379.94  4898.0  379.44  4901.7  379.94  4942.3  380.53
  4963.5  381.77  4974.2  380.18  4980.2  381.89  5023.5  381.63  5132.5  383.02
  5143.0  382.93  5164.1  381.10  5195.7  382.67  5237.9  381.10  5290.6  384.04
  5396.0  386.19  5490.9  392.47  5522.5  395.75  5564.7  401.38  5627.9  406.44
#Mann=6,-1,0
  4410.2    0.05       0  4793.7    0.12       0  4804.0    0.05       0
  4897.7    0.03       0  4901.7    0.05       0  5023.5    0.12       0
Bank Sta=4897.7,4901.7
Exp/Cntr=0.3,0.1

Type RM Length L Ch R = 1,1930,436,436,436
BEGIN DESCRIPTION:
Kings Creek 20_1 2.0
END DESCRIPTION:
XS GIS Cut Line= 3
      2627626.02      6881060.98      2628176.00      6880661.00
      2628526.02      6880110.97
#Sta/Elev= 30
  4320.5  400.54  4514.1  390.11  4555.8  386.37  4579.0  387.51  4635.4  384.55
  4712.3  382.30  4765.2  380.51  4892.1  379.57  5046.3  380.46  5095.4  381.00
  5102.1  380.20  5123.3  381.20  5138.5  379.66  5190.2  380.21  5225.8  379.63
  5230.5  378.57  5230.8  378.07  5234.5  378.57  5247.8  379.95  5253.7  378.95
  5268.9  380.44  5274.9  379.69  5311.3  382.09  5451.0  393.29  5486.5  396.66
  5493.3  398.43  5508.5  398.72  5602.5  405.66  5635.2  406.09  5652.5  407.25
#Mann=7,-1,0
  4320.5    0.05       0  4712.3    0.12       0  4892.1    0.05       0
  5046.3    0.12       0  5230.5    0.03       0  5234.5    0.12       0
  5635.2    0.05       0
Bank Sta=5230.5,5234.5
Exp/Cntr=0.3,0.1

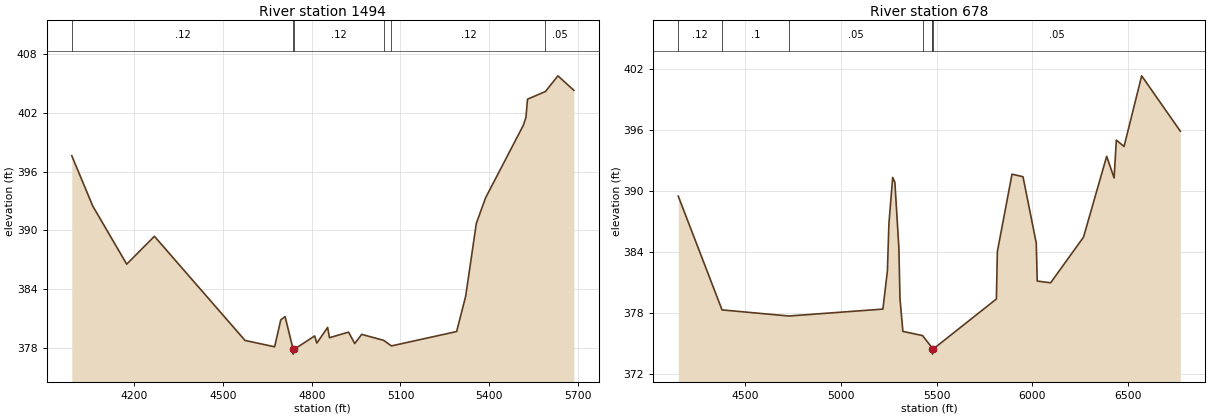
Type RM Length L Ch R = 1,1494,816,816,816
BEGIN DESCRIPTION:
Mapping XS fa018cef
END DESCRIPTION:
XS GIS Cut Line= 3
      2627761.42      6881456.56      2628535.59      6880879.21
      2628784.91      6880190.30
#Sta/Elev= 30
  3988.1  397.64  4059.2  392.49  4173.9  386.55  4267.7  389.40  4574.2  378.75
  4674.3  378.10  4695.1  380.85  4709.7  381.19  4736.9  377.85  4737.2  377.35
  4740.9  377.85  4809.8  379.21  4817.1  378.48  4853.6  380.08  4859.8  379.03
  4924.5  379.60  4945.3  378.43  4968.8  379.37  5043.1  378.76  5069.5  378.19
  5290.0  379.66  5320.6  383.27  5356.6  390.72  5388.0  393.34  5515.6  400.75
  5524.5  401.56  5529.8  403.42  5590.6  404.21  5632.6  405.81  5686.5  404.33
#Mann=6,-1,0
  3988.1    0.12       0  4736.9    0.07       0  4740.9    0.12       0
  5043.1    0.05       0  5069.5    0.12       0  5590.6    0.05       0
Bank Sta=4736.9,4740.9
Exp/Cntr=0.3,0.1

Type RM Length L Ch R = 1,678,0,0,0
BEGIN DESCRIPTION:
Kings Creek 20_1 1.0
END DESCRIPTION:
XS GIS Cut Line= 4
      2627976.05      6881461.00      2628825.99      6881515.62
      2629237.61      6881390.96      2629040.89      6880059.80
#Sta/Elev= 30
  4148.3  389.50  4377.6  378.33  4727.1  377.73  5219.4  378.41  5242.9  382.16
  5250.8  386.80  5270.6  391.33  5282.1  390.84  5303.0  384.40  5308.7  379.44
  5323.9  376.22  5426.9  375.81  5474.5  374.66  5478.6  374.49  5478.8  373.99
  5482.6  374.49  5813.2  379.40  5818.3  384.05  5895.0  391.65  5952.4  391.40
  6021.9  384.89  6027.0  381.16  6097.2  380.99  6269.1  385.47  6390.4  393.40
  6429.3  391.28  6440.9  394.99  6481.3  394.37  6573.5  401.30  6775.7  395.87
#Mann=7,-1,0
  4148.3    0.12       0  4377.6     0.1       0  4727.1    0.05       0
  5426.9    0.12       0  5474.5    0.05       0  5478.6    0.03       0
  5482.6    0.05       0
Bank Sta=5478.6,5482.6
Exp/Cntr=0.3,0.1

Chan Stop Cuts=-1