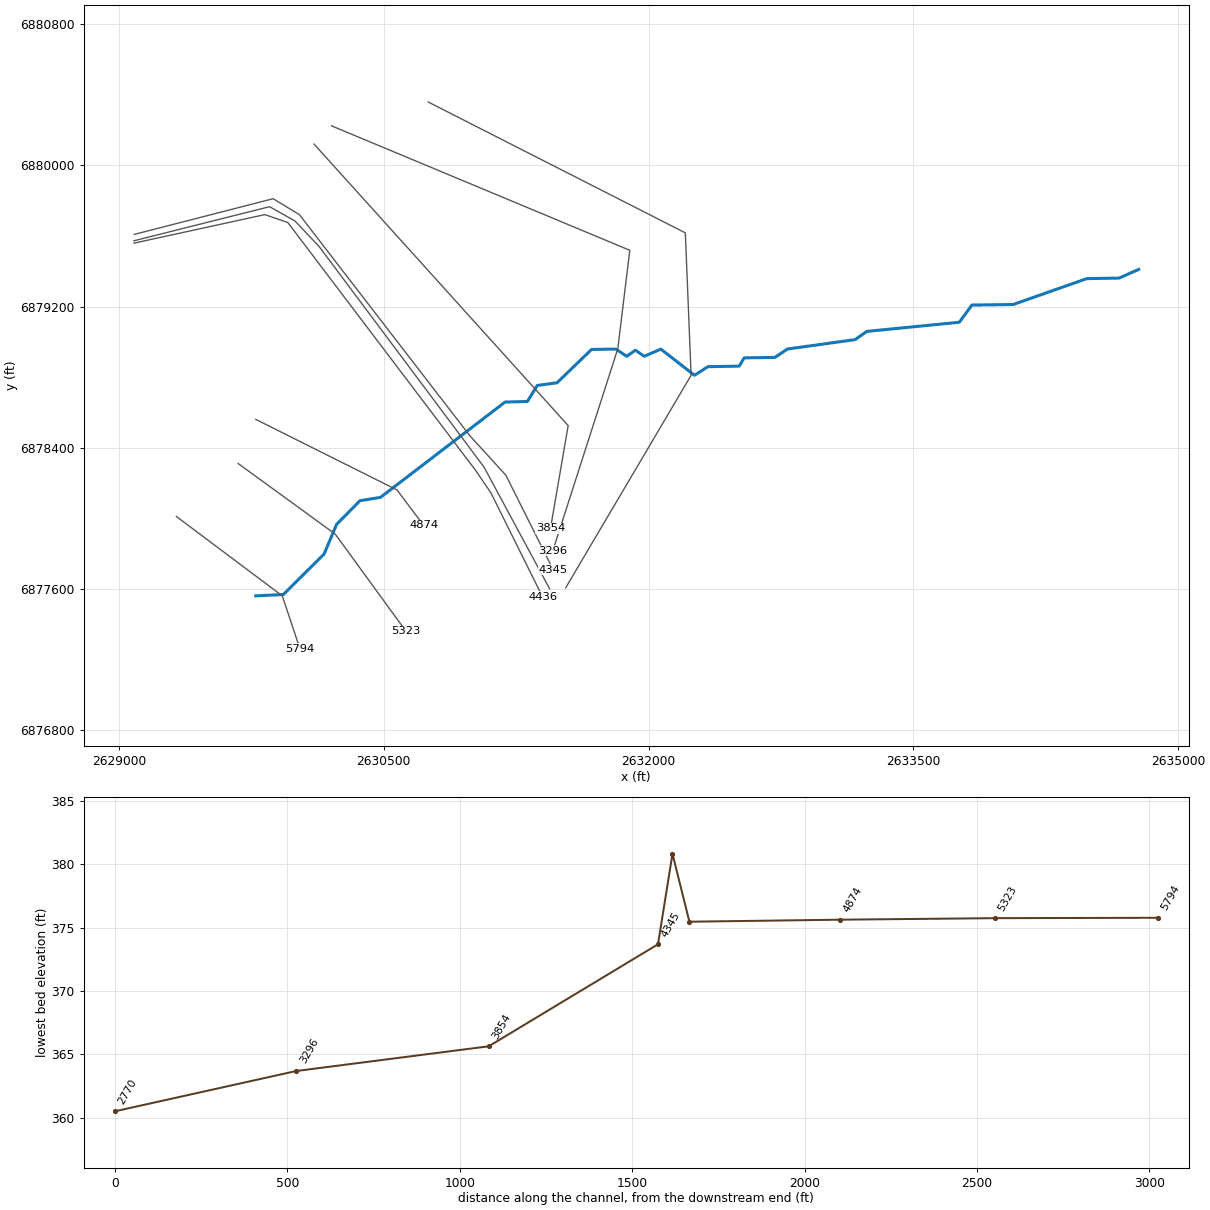
--- Kings Creek 21.prj (project) ---

Proj Title=Kings Creek 21 Base Level Engineering
Current Plan=p01
Default Exp/Contr=0.3,0.1
English Units
Geom File=g01
Flow File=f01
Plan File=p01
BEGIN DESCRIPTION:
Kings Creek 21
END DESCRIPTION:

--- Kings Creek 21.p01 (plan) ---

Plan Title=Multiple Run
Short Identifier=Multiple
Geom File=g01
Flow File=f01
Subcritical Flow
K Sum by GR= 0
Std Step Tol= 0.01
Critical Tol= 0.01
Num of Std Step Trials= 20
Max Error Tol= 0.3
Flow Tol Ratio= 0.001
Split Flow NTrial= 30
Split Flow Tol= 0.02
Split Flow Ratio= 0.02
Log Output Level= 0
Friction Slope Method= 1
Unsteady Friction Slope Method= 2
Unsteady Bridges Friction Slope Method= 1
Parabolic Critical Depth
Global Vel Dist=  1 , 1 , 1
Global Log Level= 0
CheckData=True
Encroach Param= -1, 0, 0, 0
BEGIN DESCRIPTION:
Multiple Run
END DESCRIPTION:

--- Kings Creek 21.f01 (steady flow) ---

Flow Title=Multiple
Number of Profiles=7
Profile Names=10-year,25-year,50-year,1pct_min,100-year,1pct_plu,500-year
River Rch & RM= Kings Creek 21,Reach-1,5794
     456     605     723     430     857    1711    1204
River Rch & RM= Kings Creek 21,Reach-1,4436
     512     683     820     489     975    1945    1377
Boundary for River Rch & Prof#=Kings Creek 21,Reach-1,1
Up Type=0
Dn Type=3
Dn Slope=0.005
Boundary for River Rch & Prof#=Kings Creek 21,Reach-1,2
Up Type=0
Dn Type=3
Dn Slope=0.005
Boundary for River Rch & Prof#=Kings Creek 21,Reach-1,3
Up Type=0
Dn Type=3
Dn Slope=0.005
Boundary for River Rch & Prof#=Kings Creek 21,Reach-1,4
Up Type=0
Dn Type=3
Dn Slope=0.005
Boundary for River Rch & Prof#=Kings Creek 21,Reach-1,5
Up Type=0
Dn Type=3
Dn Slope=0.005
Boundary for River Rch & Prof#=Kings Creek 21,Reach-1,6
Up Type=0
Dn Type=3
Dn Slope=0.005
Boundary for River Rch & Prof#=Kings Creek 21,Reach-1,7
Up Type=0
Dn Type=3
Dn Slope=0.005

--- Kings Creek 21.g01 (geometry) ---

Geom Title=Existing Conditions

River Reach=Kings Creek 21,Reach-1
Reach XY= 30
      2629776.00      6877561.00      2629932.20      6877568.79
      2630162.38      6877797.79      2630234.14      6877967.06
      2630366.21      6878100.48      2630482.03      6878119.19
      2631187.82      6878659.37      2631314.15      6878662.66
      2631369.57      6878753.21      2631482.17      6878768.86
      2631677.47      6878957.47      2631815.56      6878959.64
      2631876.10      6878918.78      2631926.00      6878952.97
      2631975.91      6878918.81      2632069.95      6878959.35
      2632260.58      6878811.03      2632336.50      6878859.76
      2632514.03      6878862.97      2632541.96      6878910.04
      2632715.49      6878912.22      2632786.51      6878959.78
      2633170.06      6879013.27      2633236.51      6879059.78
      2633760.16      6879111.68      2633831.68      6879208.99
      2634065.50      6879212.22      2634481.94      6879358.74
      2634665.54      6879362.12      2634776.00      6879411.00

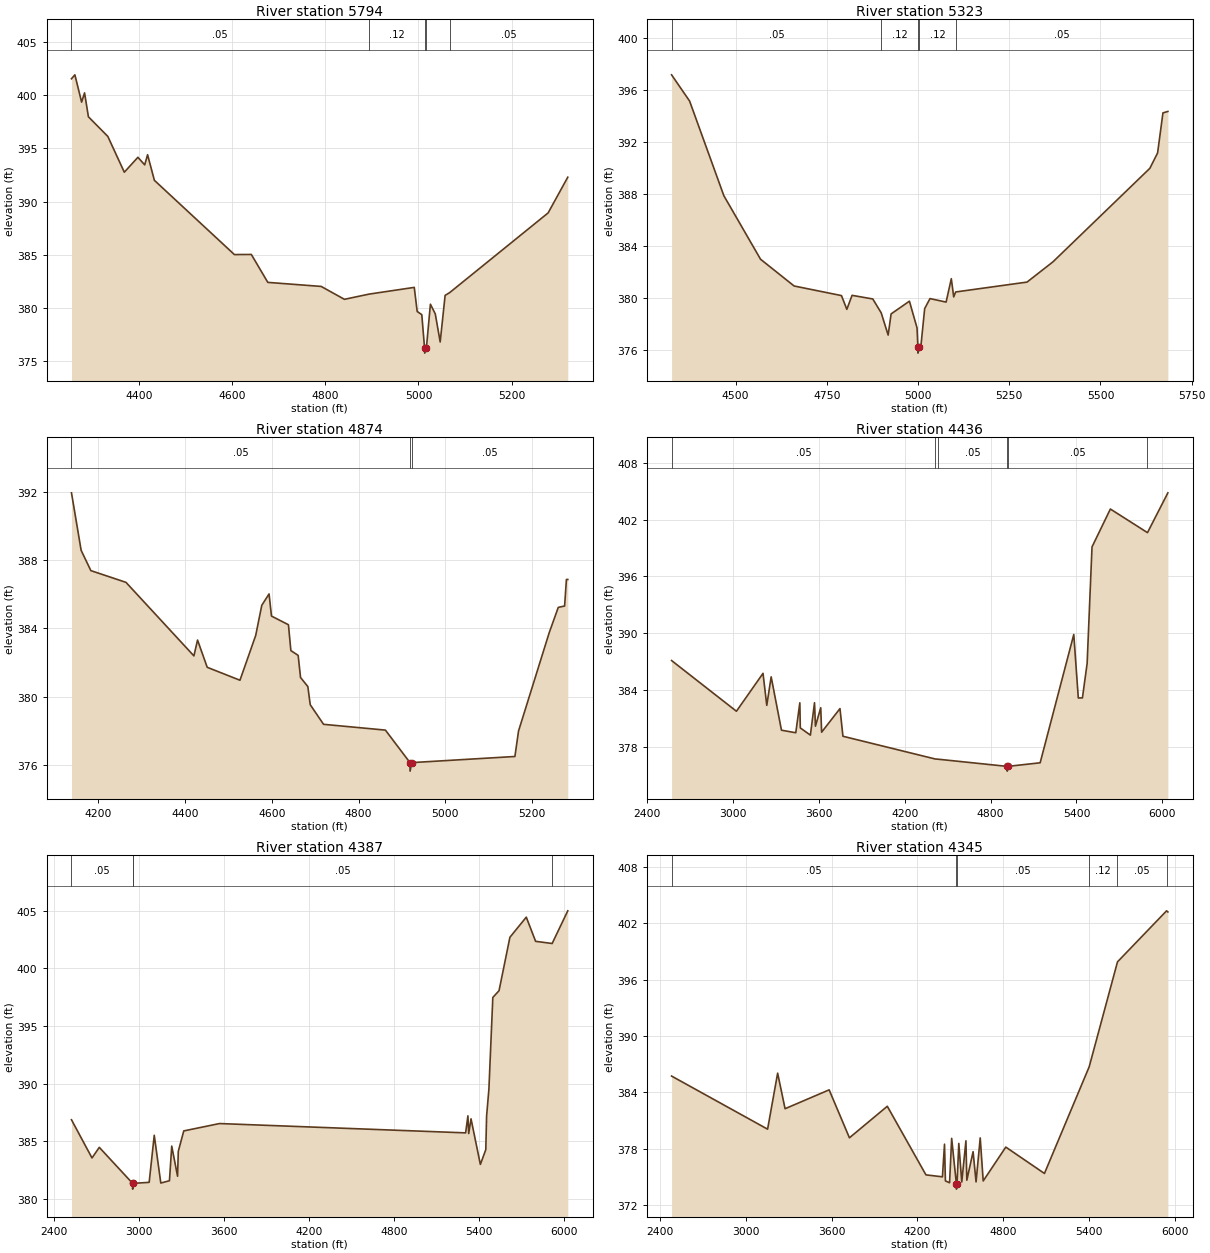
Type RM Length L Ch R = 1,5794,471,471,471
BEGIN DESCRIPTION:
Kings Creek 21 12.0
END DESCRIPTION:
XS GIS Cut Line= 3
      2629326.02      6878010.98      2629926.00      6877561.00
      2630026.00      6877261.00
#Sta/Elev= 30
  4254.6  401.52  4261.9  401.89  4276.4  399.33  4282.7  400.20  4291.0  397.95
  4332.7  396.11  4368.1  392.75  4397.3  394.15  4411.9  393.44  4418.1  394.39
  4432.7  391.99  4604.6  385.02  4641.0  385.03  4676.4  382.41  4791.0  382.03
  4841.0  380.82  4894.0  381.31  4991.0  381.94  4997.3  379.68  5007.2  379.38
  5013.1  376.27  5013.4  375.77  5017.1  376.27  5025.7  380.36  5036.2  379.45
  5046.7  376.82  5057.3  381.19  5067.1  381.45  5278.6  388.93  5320.8  392.28
#Mann=5,-1,0
  4254.6    0.05       0  4894.0    0.12       0  5013.1    0.07       0
  5017.1    0.12       0  5067.1    0.05       0
Bank Sta=5013.1,5017.1
Exp/Cntr=0.3,0.1

Type RM Length L Ch R = 1,5323,449,449,449
BEGIN DESCRIPTION:
Kings Creek 21 11.0
END DESCRIPTION:
XS GIS Cut Line= 3
      2629676.03      6878310.98      2630226.00      6877911.00
      2630625.99      6877361.01
#Sta/Elev= 30
  4324.7  397.17  4374.1  395.15  4468.0  387.86  4568.5  382.97  4660.5  380.91
  4790.3  380.17  4805.0  379.11  4819.3  380.19  4876.1  379.91  4899.2  378.84
  4918.2  377.13  4926.3  378.76  4976.5  379.74  4997.4  377.68  4999.7  376.24
  4999.9  375.74  5003.7  376.24  5007.8  376.24  5018.3  379.17  5032.9  379.94
  5077.0  379.67  5091.3  381.47  5097.9  380.07  5103.3  380.45  5298.8  381.21
  5369.9  382.77  5635.4  389.97  5656.6  391.15  5671.3  394.24  5684.8  394.35
#Mann=5,-1,0
  4324.7    0.05       0  4899.2    0.12       0  4999.7    0.07       0
  5003.7    0.12       0  5103.3    0.05       0
Bank Sta=4999.7,5003.7
Exp/Cntr=0.3,0.1

Type RM Length L Ch R = 1,4874,438,438,438
BEGIN DESCRIPTION:
Kings Creek 21 10.0
END DESCRIPTION:
XS GIS Cut Line= 3
      2629776.03      6878560.99      2630576.00      6878161.00
      2630726.00      6877961.00
#Sta/Elev= 30
  4137.8  391.97  4160.1  388.59  4182.5  387.40  4263.5  386.71  4420.1  382.39
  4428.5  383.32  4450.8  381.72  4526.3  380.96  4562.6  383.59  4576.6  385.36
  4593.4  386.03  4599.0  384.73  4638.1  384.22  4643.7  382.70  4660.5  382.42
  4666.0  381.12  4682.8  380.59  4688.4  379.52  4719.1  378.37  4861.7  378.03
  4918.4  376.12  4918.6  375.62  4922.4  376.12  5160.3  376.48  5168.7  377.98
  5239.5  383.76  5260.3  385.24  5274.9  385.32  5279.1  386.88  5282.2  386.88
#Mann=3,-1,0
  4137.8    0.05       0  4918.4    0.03       0  4922.4    0.05       0
Bank Sta=4918.4,4922.4
Exp/Cntr=0.3,0.1

Type RM Length L Ch R = 1,4436,49,49,49
BEGIN DESCRIPTION:
Mapping XS d908763e
END DESCRIPTION:
XS GIS Cut Line= 6
      2629085.68      6879559.86      2629827.06      6879721.62
      2629957.37      6879676.68      2631022.32      6878270.23
      2631107.70      6878144.41      2631399.71      6877555.89
#Sta/Elev= 30
  2569.0  387.13  3022.4  381.78  3208.3  385.78  3234.6  382.40  3265.3  385.41
  3337.3  379.78  3437.4  379.51  3465.7  382.67  3469.0  380.02  3539.5  379.26
  3568.4  382.68  3574.8  380.20  3611.8  382.15  3618.1  379.57  3746.4  382.06
  3767.2  379.14  4412.8  376.74  4430.8  376.72  4915.6  375.96  4915.8  375.46
  4919.6  375.96  5146.0  376.34  5381.1  389.88  5412.8  383.18  5441.6  383.19
  5474.5  386.83  5508.6  399.12  5637.0  403.12  5896.5  400.63  6039.0  404.83
#Mann=6,-1,0
  2569.0    0.05       0  4412.8    0.12       0  4430.8    0.05       0
  4915.6    0.03       0  4919.6    0.05       0  5896.5    0.12       0
Bank Sta=4915.6,4919.6
Exp/Cntr=0.3,0.1

Type RM Length L Ch R = 1,4387,42,42,42
BEGIN DESCRIPTION:
Mapping XS de389662
END DESCRIPTION:
XS GIS Cut Line= 6
      2629085.60      6879573.32      2629854.02      6879766.55
      2629997.81      6879685.67      2630134.91      6879540.38
      2631068.24      6878291.07      2631440.20      6877600.74
#Sta/Elev= 30
  2522.3  386.85  2667.1  383.53  2718.6  384.45  2953.8  381.32  2954.0  380.82
  2957.8  381.32  3070.4  381.41  3106.3  385.50  3152.6  381.35  3213.6  381.55
  3229.7  384.56  3270.8  381.94  3276.0  384.11  3314.6  385.88  3566.9  386.52
  5303.3  385.71  5319.4  387.19  5325.0  385.65  5341.4  386.93  5407.3  382.97
  5445.6  384.25  5451.2  387.16  5467.5  389.50  5495.2  397.48  5539.1  398.07
  5615.7  402.71  5731.2  404.46  5797.2  402.36  5913.8  402.17  6024.0  405.01
#Mann=4,-1,0
  2522.3    0.05       0  2953.8    0.03       0  2957.8    0.05       0
  5913.8    0.12       0
Bank Sta=2953.8,2957.8
Exp/Cntr=0.3,0.1

Type RM Length L Ch R = 1,4345,491,491,491
BEGIN DESCRIPTION:
Mapping XS 900a823a
END DESCRIPTION:
XS GIS Cut Line= 6
      2629087.79      6879609.54      2629874.14      6879811.74
      2630022.43      6879721.87      2630988.52      6878468.20
      2631192.38      6878244.46      2631460.31      6877708.84
#Sta/Elev= 30
  2480.4  385.73  3151.8  380.07  3222.0  386.04  3274.0  382.25  3582.2  384.26
  3724.1  379.15  3988.9  382.51  4259.1  375.20  4374.4  374.99  4388.9  378.47
  4395.2  374.56  4424.3  374.36  4438.9  379.09  4472.3  374.18  4472.5  373.68
  4476.3  374.18  4488.8  378.55  4509.6  374.44  4538.7  378.83  4545.0  374.63
  4588.7  377.67  4609.5  374.45  4638.6  379.14  4659.4  374.55  4817.5  378.16
  5087.7  375.35  5400.6  386.72  5598.5  397.90  5941.7  403.34  5950.8  403.22
#Mann=6,-1,0
  2480.4    0.05       0  4472.3    0.03       0  4476.3    0.05       0
  5400.6    0.12       0  5598.5    0.05       0  5941.7    0.12       0
Bank Sta=4472.3,4476.3
Exp/Cntr=0.3,0.1

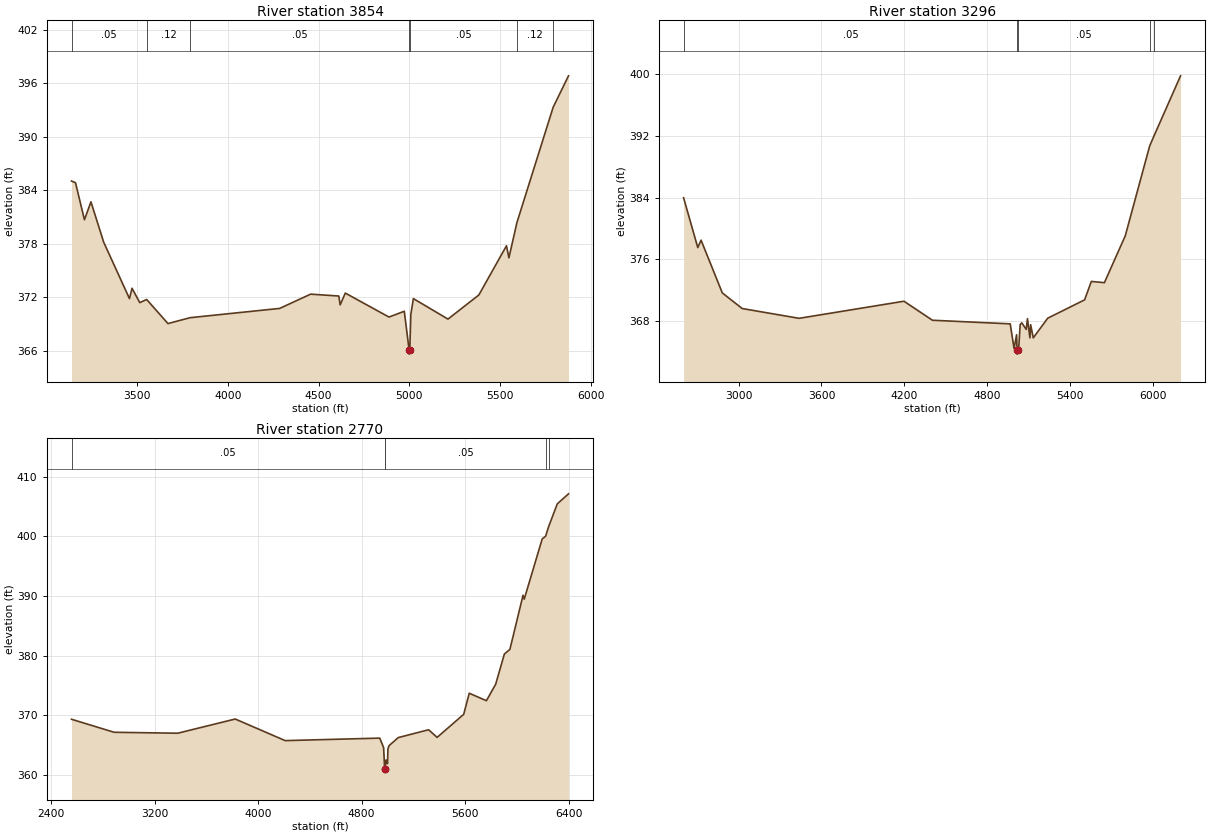
Type RM Length L Ch R = 1,3854,558,558,558
BEGIN DESCRIPTION:
Kings Creek 21 7.0
END DESCRIPTION:
XS GIS Cut Line= 3
      2630105.65      6880121.54      2631545.00      6878525.96
      2631445.04      6877944.15
#Sta/Elev= 30
  3137.9  385.05  3159.8  384.87  3209.2  380.71  3245.0  382.72  3315.3  378.19
  3457.3  371.86  3471.5  373.02  3514.1  371.41  3552.2  371.76  3669.5  369.06
  3791.8  369.72  4285.3  370.76  4455.7  372.36  4611.2  372.15  4618.6  371.16
  4647.0  372.48  4887.7  369.79  4972.1  370.44  4998.5  366.13  4998.8  365.63
  5002.5  366.13  5008.0  370.08  5022.2  371.86  5212.8  369.56  5383.1  372.27
  5535.3  377.79  5548.6  376.43  5592.8  380.39  5792.3  393.32  5877.1  396.86
#Mann=7,-1,0
  3137.9    0.05       0  3552.2    0.12       0  3791.8    0.05       0
  4998.5    0.04       0  5002.5    0.05       0  5592.8    0.12       0
  5792.3    0.05       0
Bank Sta=4998.5,5002.5
Exp/Cntr=0.3,0.1

Type RM Length L Ch R = 1,3296,526,526,526
BEGIN DESCRIPTION:
Kings Creek 21 6.0
END DESCRIPTION:
XS GIS Cut Line= 4
      2630204.55      6880224.87      2631894.06      6879519.41
      2631826.00      6878961.00      2631458.18      6877816.37
#Sta/Elev= 30
  2602.3  383.99  2705.0  377.52  2728.8  378.48  2882.5  371.63  3026.5  369.60
  3438.3  368.33  4196.9  370.55  4402.8  368.08  4965.5  367.61  4993.2  364.43
  5011.8  366.19  5015.0  364.18  5015.3  363.68  5019.0  364.18  5027.2  364.55
  5037.7  367.53  5049.1  367.74  5081.2  366.89  5090.3  368.29  5108.1  365.79
  5113.3  367.50  5132.3  365.79  5236.5  368.34  5503.8  370.73  5552.4  373.12
  5646.9  372.96  5797.9  379.04  5974.3  390.70  6008.6  392.13  6198.0  399.82
#Mann=5,-1,0
  2602.3    0.05       0  5015.0    0.03       0  5019.0    0.05       0
  5974.3    0.12       0  6008.6    0.05       0
Bank Sta=5015,5019
Exp/Cntr=0.3,0.1

Type RM Length L Ch R = 1,2770,0,0,0
BEGIN DESCRIPTION:
Kings Creek 21 5.0
END DESCRIPTION:
XS GIS Cut Line= 4
      2630752.70      6880359.70      2632208.60      6879618.27
      2632241.34      6878810.95      2631530.80      6877606.40
#Sta/Elev= 30
  2558.2  369.36  2887.3  367.18  3378.6  367.02  3823.4  369.40  4209.3  365.78
  4939.9  366.20  4969.9  364.61  4977.9  361.00  4978.2  360.50  4981.9  361.00
  4988.3  362.54  5000.0  361.93  5003.2  364.37  5011.6  364.93  5083.2  366.29
  5317.4  367.60  5383.1  366.32  5588.7  370.19  5631.6  373.72  5764.3  372.47
  5835.9  375.24  5902.9  380.29  5945.8  381.08  6047.2  390.14  6056.5  389.49
  6195.6  399.60  6221.2  400.02  6246.2  401.71  6311.9  405.46  6398.5  407.14
#Mann=5,-1,0
  2558.2    0.05       0  4977.9    0.03       0  4981.9    0.05       0
  6221.2    0.12       0  6246.2    0.05       0
Bank Sta=4977.9,4981.9
Exp/Cntr=0.3,0.1

Chan Stop Cuts=-1