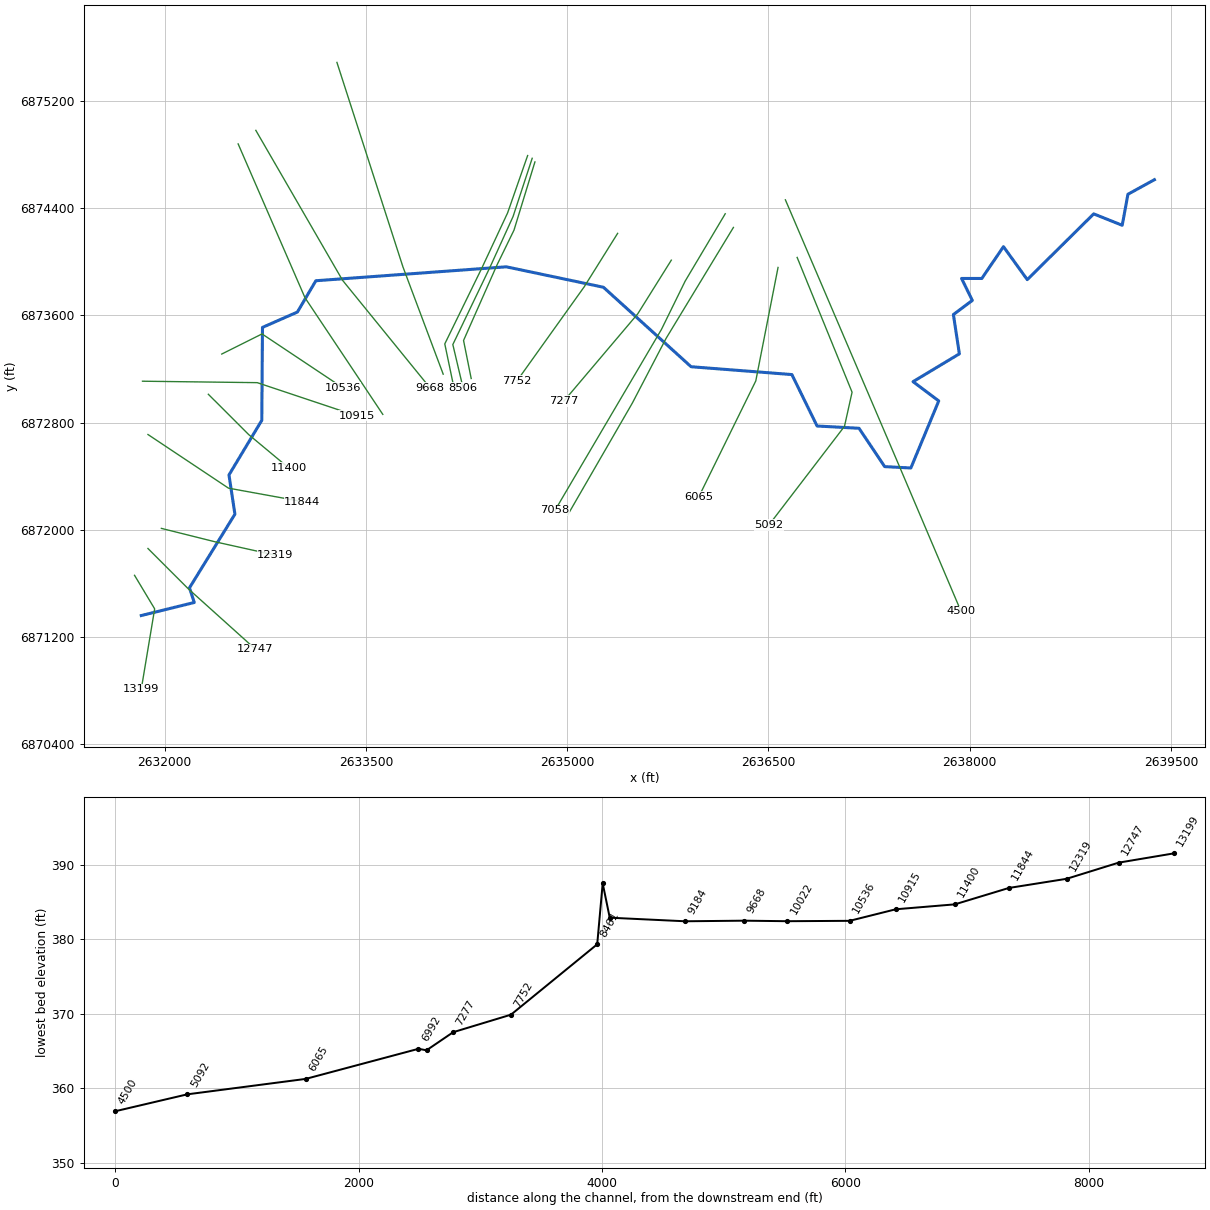
--- Kings Creek 23.prj (project) ---

Proj Title=Kings Creek 23 Base Level Engineering
Current Plan=p01
Default Exp/Contr=0.3,0.1
English Units
Geom File=g01
Flow File=f01
Plan File=p01
BEGIN DESCRIPTION:
Kings Creek 23
END DESCRIPTION:

--- Kings Creek 23.p01 (plan) ---

Plan Title=Multiple Run
Short Identifier=Multiple
Geom File=g01
Flow File=f01
Subcritical Flow
K Sum by GR= 0
Std Step Tol= 0.01
Critical Tol= 0.01
Num of Std Step Trials= 20
Max Error Tol= 0.3
Flow Tol Ratio= 0.001
Split Flow NTrial= 30
Split Flow Tol= 0.02
Split Flow Ratio= 0.02
Log Output Level= 0
Friction Slope Method= 1
Unsteady Friction Slope Method= 2
Unsteady Bridges Friction Slope Method= 1
Parabolic Critical Depth
Global Vel Dist=  1 , 1 , 1
Global Log Level= 0
CheckData=True
Encroach Param= -1, 0, 0, 0
BEGIN DESCRIPTION:
Multiple Run
END DESCRIPTION:

--- Kings Creek 23.f01 (steady flow) ---

Flow Title=Multiple
Number of Profiles=7
Profile Names=10-year,25-year,50-year,1pct_min,100-year,1pct_plu,500-year
River Rch & RM= Kings Creek 23,Reach-1,13199
     568     765     924     554    1106    2207    1584
River Rch & RM= Kings Creek 23,Reach-1,10022
     924    1280    1577     962    1920    3831    2850
River Rch & RM= Kings Creek 23,Reach-1,9184
     950    1316    1621     989    1973    3937    2925
River Rch & RM= Kings Creek 23,Reach-1,8506
    1058    1473    1819    1112    2219    4427    3306
Boundary for River Rch & Prof#=Kings Creek 23,Reach-1,1
Up Type=0
Dn Type=3
Dn Slope=0.005
Boundary for River Rch & Prof#=Kings Creek 23,Reach-1,2
Up Type=0
Dn Type=3
Dn Slope=0.005
Boundary for River Rch & Prof#=Kings Creek 23,Reach-1,3
Up Type=0
Dn Type=3
Dn Slope=0.005
Boundary for River Rch & Prof#=Kings Creek 23,Reach-1,4
Up Type=0
Dn Type=3
Dn Slope=0.005
Boundary for River Rch & Prof#=Kings Creek 23,Reach-1,5
Up Type=0
Dn Type=3
Dn Slope=0.005
Boundary for River Rch & Prof#=Kings Creek 23,Reach-1,6
Up Type=0
Dn Type=3
Dn Slope=0.005
Boundary for River Rch & Prof#=Kings Creek 23,Reach-1,7
Up Type=0
Dn Type=3
Dn Slope=0.005

--- Kings Creek 23.g01 (geometry) ---

Geom Title=Existing Conditions

River Reach=Kings Creek 23,Reach-1
Reach XY= 30
      2631826.00      6871361.00      2632220.99      6871458.39
      2632185.43      6871567.61      2632524.04      6872116.89
      2632479.74      6872409.44      2632724.34      6872817.05
      2632729.29      6873509.64      2632989.56      6873623.99
      2633127.25      6873857.55      2634546.15      6873961.36
      2635270.15      6873808.94      2635923.30      6873216.36
      2636674.38      6873157.88      2636862.19      6872774.35
      2637174.75      6872757.49      2637366.20      6872471.48
      2637560.97      6872461.33      2637768.79      6872961.34
      2637577.48      6873105.12      2637922.54      6873312.50
      2637877.97      6873605.32      2638019.00      6873710.78
      2637938.96      6873874.70      2638089.73      6873874.40
      2638251.01      6874111.67      2638428.51      6873865.95
      2638923.43      6874356.05      2639136.00      6874271.04
      2639178.67      6874502.50      2639376.00      6874611.00

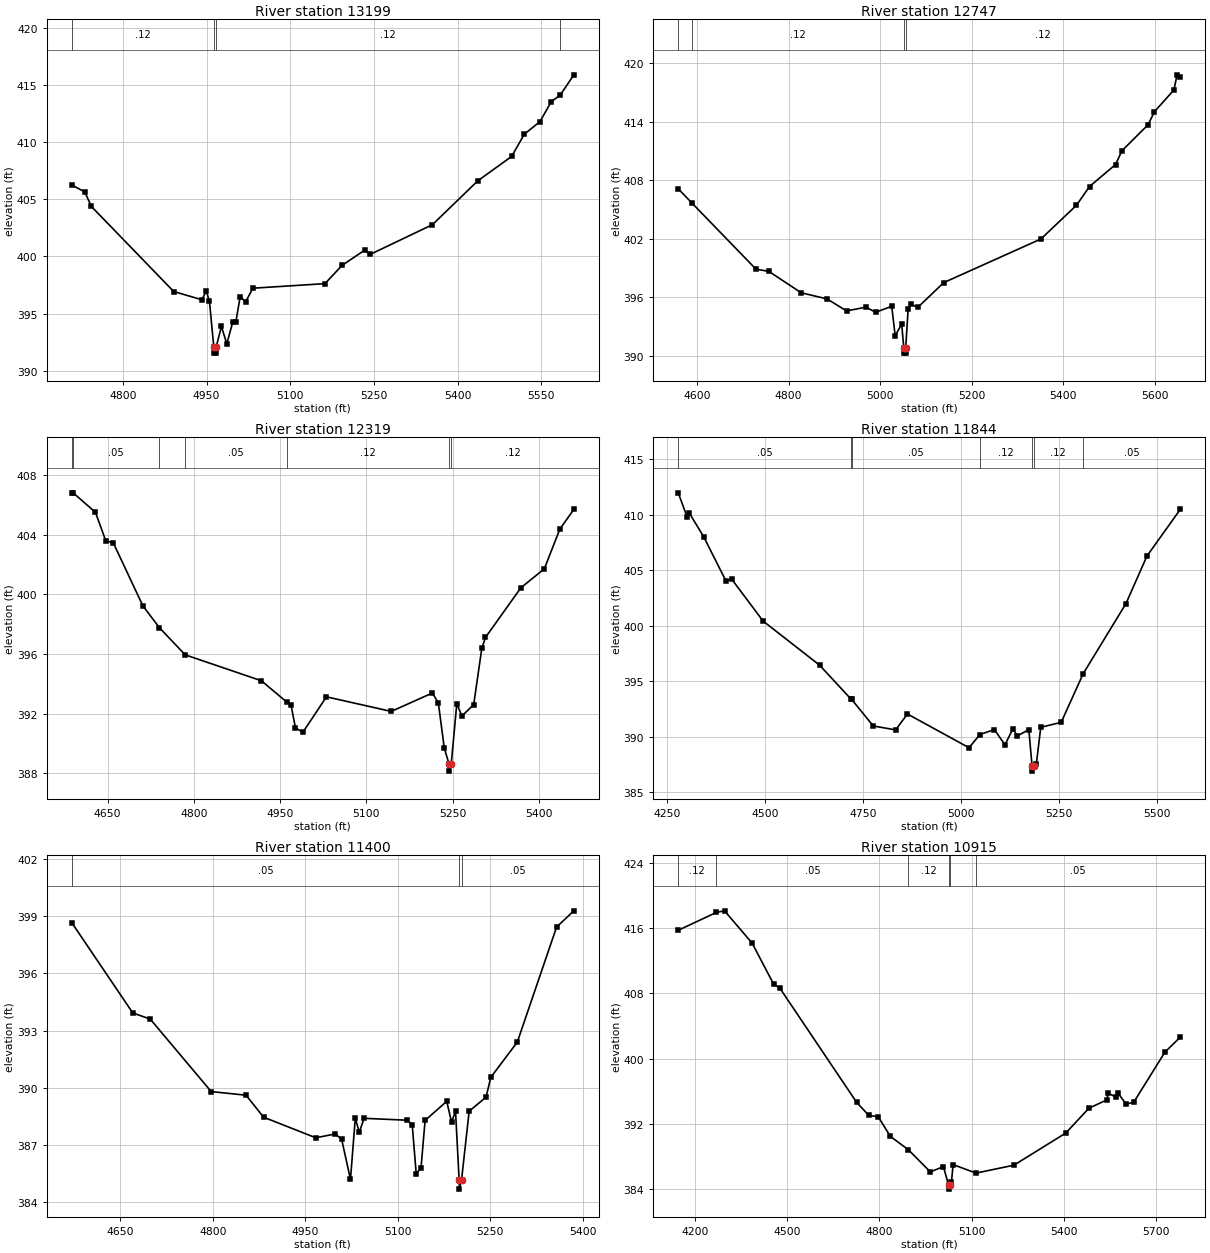
Type RM Length L Ch R = 1,13199,452,452,452
BEGIN DESCRIPTION:
Kings Creek 23 23.0
END DESCRIPTION:
XS GIS Cut Line= 3
      2631776.00      6871661.00      2631926.00      6871411.00
      2631826.00      6870811.02
#Sta/Elev= 30
  4708.4  406.25  4731.7  405.65  4743.4  404.38  4891.1  396.93  4941.6  396.21
  4949.4  396.98  4955.2  396.06  4963.0  392.04  4963.2  391.54  4966.7  391.54
  4967.0  392.04  4976.6  393.87  4986.3  392.35  4997.0  394.28  5002.5  394.28
  5010.1  396.46  5020.2  396.04  5032.9  397.22  5162.2  397.62  5192.6  399.21
  5233.1  400.54  5243.3  400.18  5354.8  402.78  5435.9  406.61  5496.7  408.75
  5519.5  410.70  5547.4  411.79  5567.7  413.54  5583.8  414.12  5608.2  415.89
#Mann=4,-1,0
  4708.4    0.12       0  4963.0    0.07       0  4967.0    0.12       0
  5583.8    0.05       0
Bank Sta=4963,4967
Exp/Cntr=0.3,0.1

Type RM Length L Ch R = 1,12747,428,428,428
BEGIN DESCRIPTION:
Kings Creek 23 22.0
END DESCRIPTION:
XS GIS Cut Line= 3
      2631875.97      6871861.03      2632176.00      6871561.00
      2632676.01      6871110.99
#Sta/Elev= 30
  4558.8  407.13  4587.9  405.71  4728.6  398.90  4756.8  398.67  4827.5  396.48
  4884.1  395.85  4926.5  394.62  4969.0  395.01  4990.2  394.48  5025.3  395.10
  5032.8  392.07  5047.0  393.28  5051.7  390.80  5052.0  390.30  5055.5  390.30
  5055.7  390.80  5061.2  394.84  5067.9  395.31  5082.1  394.98  5138.9  397.52
  5351.2  401.99  5428.9  405.44  5457.4  407.36  5514.2  409.61  5528.4  411.03
  5585.2  413.68  5599.4  415.03  5642.0  417.26  5648.7  418.80  5655.8  418.62
#Mann=4,-1,0
  4558.8    0.05       0  4587.9    0.12       0  5051.7    0.07       0
  5055.7    0.12       0
Bank Sta=5051.7,5055.7
Exp/Cntr=0.3,0.1

Type RM Length L Ch R = 1,12319,475,475,475
BEGIN DESCRIPTION:
Kings Creek 23 21.0
END DESCRIPTION:
XS GIS Cut Line= 3
      2631976.02      6872010.99      2632376.00      6871911.00
      2632826.04      6871810.99
#Sta/Elev= 30
  4587.7  406.82  4590.1  406.82  4628.9  405.51  4646.9  403.59  4659.8  403.47
  4711.4  399.23  4740.2  397.76  4785.0  395.94  4917.5  394.20  4962.2  392.75
  4969.1  392.56  4976.8  391.03  4989.7  390.74  5030.7  393.12  5143.4  392.14
  5215.1  393.38  5225.4  392.69  5235.6  389.68  5243.8  388.63  5244.1  388.13
  5247.8  388.63  5257.4  392.66  5266.3  391.83  5286.8  392.60  5300.9  396.37
  5307.3  397.11  5368.8  400.44  5409.7  401.72  5436.6  404.38  5461.0  405.71
#Mann=7,-1,0
  4587.7    0.12       0  4590.1    0.05       0  4740.2    0.12       0
  4785.0    0.05       0  4962.2    0.12       0  5243.8    0.07       0
  5247.8    0.12       0
Bank Sta=5243.8,5247.8
Exp/Cntr=0.3,0.1

Type RM Length L Ch R = 1,11844,444,444,444
BEGIN DESCRIPTION:
Kings Creek 23 20.0
END DESCRIPTION:
XS GIS Cut Line= 3
      2631876.04      6872710.98      2632476.00      6872311.00
      2633026.02      6872211.00
#Sta/Elev= 30
  4279.5  411.99  4302.0  409.82  4308.0  410.15  4344.1  408.05  4401.1  404.05
  4416.2  404.19  4495.8  400.43  4640.0  396.45  4720.9  393.36  4721.6  393.37
  4776.7  390.97  4833.8  390.62  4863.9  392.05  5020.9  389.01  5048.7  390.20
  5085.7  390.65  5112.4  389.27  5132.7  390.71  5144.1  390.08  5173.4  390.64
  5181.5  387.40  5181.8  386.90  5185.5  387.40  5192.4  387.50  5203.8  390.85
  5255.9  391.30  5311.9  395.68  5421.1  402.01  5474.5  406.29  5559.6  410.50
#Mann=7,-1,0
  4279.5    0.05       0  4720.9    0.12       0  4721.6    0.05       0
  5048.7    0.12       0  5181.5    0.03       0  5185.5    0.12       0
  5311.9    0.05       0
Bank Sta=5181.5,5185.5
Exp/Cntr=0.3,0.1

Type RM Length L Ch R = 1,11400,485,485,485
BEGIN DESCRIPTION:
Kings Creek 23 19.0
END DESCRIPTION:
XS GIS Cut Line= 3
      2632325.97      6873011.03      2632626.00      6872711.00
      2632925.99      6872461.01
#Sta/Elev= 30
  4571.1  398.66  4670.1  393.93  4698.4  393.61  4797.4  389.81  4854.0  389.62
  4882.3  388.47  4967.1  387.39  4998.7  387.59  5009.1  387.31  5023.4  385.21
  5031.2  388.42  5037.7  387.68  5045.5  388.41  5115.8  388.31  5123.6  388.07
  5130.1  385.50  5137.9  385.82  5144.5  388.30  5179.6  389.30  5187.4  388.22
  5193.9  388.77  5199.7  385.20  5200.0  384.70  5203.7  385.20  5216.0  388.78
  5243.4  389.52  5251.2  390.56  5294.1  392.40  5357.9  398.43  5385.9  399.28
#Mann=3,-1,0
  4571.1    0.05       0  5199.7    0.03       0  5203.7    0.05       0
Bank Sta=5199.7,5203.7
Exp/Cntr=0.3,0.1

Type RM Length L Ch R = 1,10915,379,379,379
BEGIN DESCRIPTION:
Kings Creek 23 18.0
END DESCRIPTION:
XS GIS Cut Line= 3
      2631835.29      6873108.38      2632690.32      6873097.62
      2633429.73      6872850.55
#Sta/Elev= 30
  4144.9  415.71  4269.3  417.90  4295.6  418.09  4385.6  414.13  4455.6  409.11
  4475.6  408.64  4725.7  394.66  4765.7  393.05  4795.7  392.91  4835.7  390.49
  4894.1  388.86  4965.7  386.15  5008.2  386.80  5025.1  384.54  5025.3  384.04
  5029.1  384.54  5034.5  384.91  5039.8  387.04  5114.5  386.00  5237.9  386.97
  5406.6  390.90  5482.1  393.94  5540.0  394.95  5545.3  395.76  5571.6  395.28
  5576.8  395.78  5603.2  394.44  5628.1  394.68  5729.5  400.80  5779.6  402.64
#Mann=6,-1,0
  4144.9    0.12       0  4269.3    0.05       0  4894.1    0.12       0
  5025.1    0.07       0  5029.1    0.12       0  5114.5    0.05       0
Bank Sta=5025.1,5029.1
Exp/Cntr=0.3,0.1

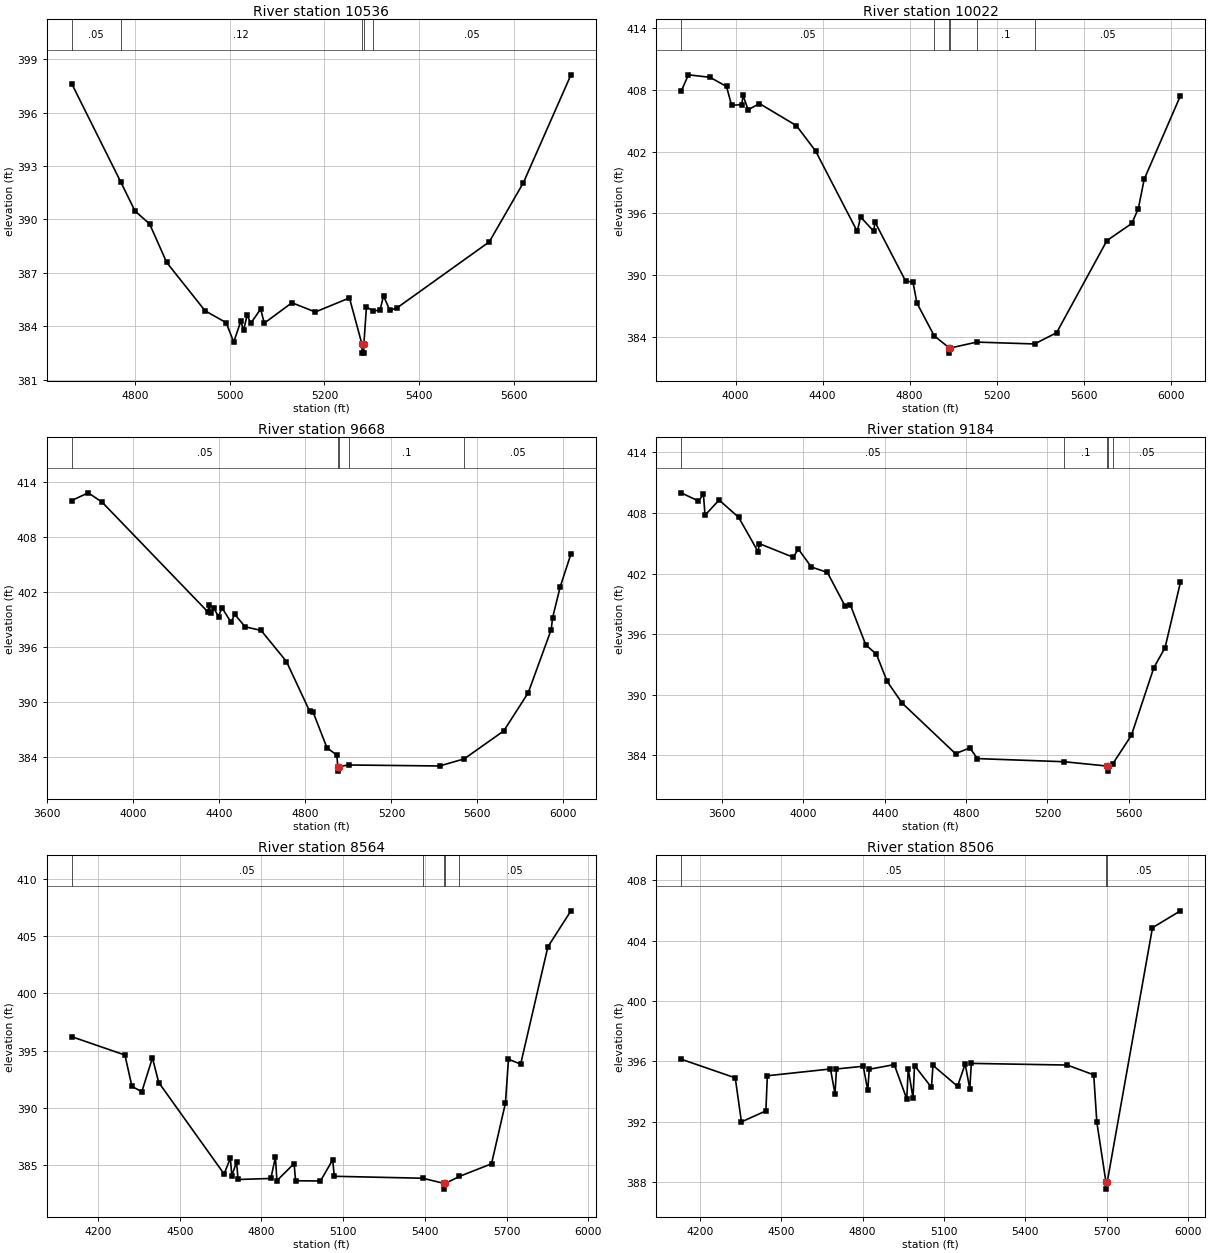
Type RM Length L Ch R = 1,10536,514,514,514
BEGIN DESCRIPTION:
Kings Creek 23 17.0
END DESCRIPTION:
XS GIS Cut Line= 3
      2632426.04      6873311.02      2632726.00      6873461.00
      2633326.02      6873060.99
#Sta/Elev= 30
  4665.0  397.63  4768.8  392.11  4799.1  390.47  4829.9  389.75  4866.2  387.58
  4947.3  384.87  4992.0  384.20  5007.9  383.11  5022.9  384.28  5028.9  383.78
  5036.4  384.64  5043.9  384.16  5065.0  384.97  5072.5  384.17  5131.1  385.32
  5180.6  384.80  5252.8  385.59  5279.3  382.99  5279.6  382.49  5283.1  382.49
  5283.3  382.99  5288.8  385.09  5302.7  384.86  5317.4  384.90  5324.9  385.70
  5338.4  384.89  5353.4  385.03  5548.7  388.74  5620.8  392.06  5721.5  398.12
#Mann=5,-1,0
  4665.0    0.05       0  4768.8    0.12       0  5279.3    0.07       0
  5283.3    0.12       0  5302.7    0.05       0
Bank Sta=5279.3,5283.3
Exp/Cntr=0.3,0.1

Type RM Length L Ch R = 1,10022,354,354,354
BEGIN DESCRIPTION:
Kings Creek 23 16.0
END DESCRIPTION:
XS GIS Cut Line= 3
      2632548.07      6874877.93      2633046.18      6873730.92
      2633625.97      6872861.04
#Sta/Elev= 30
  3749.5  407.84  3783.1  409.44  3882.4  409.20  3958.2  408.31  3981.7  406.48
  4028.6  406.55  4034.0  407.46  4057.5  406.05  4109.9  406.65  4279.5  404.51
  4367.6  402.06  4559.3  394.25  4574.7  395.65  4635.1  394.26  4640.6  395.17
  4781.3  389.45  4815.6  389.32  4833.7  387.30  4913.1  384.12  4982.8  382.94
  4983.4  382.44  4987.8  382.94  5108.6  383.51  5374.5  383.33  5476.0  384.42
  5707.4  393.36  5821.6  395.02  5851.6  396.45  5878.7  399.31  6045.4  407.41
#Mann=6,-1,0
  3749.5    0.05       0  4913.1    0.12       0  4982.8    0.07       0
  4987.8    0.12       0  5108.6     0.1       0  5374.5    0.05       0
Bank Sta=4982.8,4987.8
Exp/Cntr=0.3,0.1

Type RM Length L Ch R = 1,9668,484,484,484
BEGIN DESCRIPTION:
Kings Creek 23 15.0
END DESCRIPTION:
XS GIS Cut Line= 3
      2632679.98      6874978.69      2633326.00      6873861.00
      2633975.98      6873061.03
#Sta/Elev= 30
  3713.2  411.96  3790.4  412.80  3855.0  411.78  4345.8  399.86  4353.1  400.56
  4358.9  399.73  4374.7  400.23  4396.2  399.33  4412.0  400.29  4455.1  398.69
  4470.8  399.60  4519.7  398.22  4594.3  397.82  4712.0  394.44  4819.7  389.04
  4835.5  388.96  4900.2  385.06  4946.4  384.24  4950.7  383.01  4951.3  382.51
  4955.7  383.01  5001.8  383.18  5423.7  383.07  5538.2  383.84  5722.5  386.89
  5836.0  391.03  5943.0  397.91  5949.5  399.21  5984.6  402.55  6034.9  406.16
#Mann=5,-1,0
  3713.2    0.05       0  4950.7    0.03       0  4955.7    0.05       0
  5001.8     0.1       0  5538.2    0.05       0
Bank Sta=4950.7,4955.7
Exp/Cntr=0.3,0.1

Type RM Length L Ch R = 1,9184,620,620,620
BEGIN DESCRIPTION:
Kings Creek 23 14.0
END DESCRIPTION:
XS GIS Cut Line= 3
      2633284.16      6875485.61      2633776.00      6873961.00
      2634076.01      6873160.98
#Sta/Elev= 30
  3398.1  409.99  3483.6  409.18  3508.0  409.84  3515.7  407.77  3585.0  409.28
  3681.2  407.56  3777.3  404.14  3782.6  404.96  3949.3  403.61  3974.8  404.42
  4038.9  402.64  4117.5  402.11  4204.4  398.79  4231.2  398.86  4306.6  394.93
  4359.1  394.00  4411.7  391.31  4485.2  389.17  4747.9  384.16  4818.6  384.73
  4855.9  383.67  5282.7  383.36  5495.0  382.93  5495.7  382.43  5500.2  382.93
  5522.4  383.18  5613.3  385.98  5723.7  392.68  5778.8  394.66  5854.5  401.14
#Mann=5,-1,0
  3398.1    0.05       0  5282.7     0.1       0  5495.0    0.03       0
  5500.2     0.1       0  5522.4    0.05       0
Bank Sta=5495,5500.2
Exp/Cntr=0.3,0.1

Type RM Length L Ch R = 1,8564,58,58,58
BEGIN DESCRIPTION:
Mapping XS 2ec80218
END DESCRIPTION:
XS GIS Cut Line= 5
      2634705.38      6874791.14      2634556.09      6874363.63
      2634366.11      6873956.52      2634087.92      6873386.57
      2634148.86      6873095.38
#Sta/Elev= 30
  4102.9  396.21  4298.6  394.61  4324.3  391.87  4360.7  391.41  4399.6  394.36
  4422.8  392.21  4662.9  384.23  4685.8  385.61  4691.3  384.08  4708.6  385.28
  4714.1  383.75  4834.5  383.84  4851.3  385.70  4856.8  383.65  4919.9  385.14
  4925.4  383.64  5016.7  383.62  5061.7  385.47  5067.3  384.03  5392.4  383.86
  5470.1  383.41  5470.9  382.91  5475.4  383.41  5527.2  384.02  5644.9  385.12
  5696.0  390.41  5707.2  394.24  5752.0  393.82  5851.9  404.05  5936.7  407.19
#Mann=5,-1,0
  4102.9    0.05       0  5392.4     0.1       0  5470.1    0.04       0
  5475.4     0.1       0  5527.2    0.05       0
Bank Sta=5470.1,5475.4
Exp/Cntr=0.3,0.1

Type RM Length L Ch R = 1,8506,45,45,45
BEGIN DESCRIPTION:
Mapping XS a9278a8d
END DESCRIPTION:
XS GIS Cut Line= 5
      2634739.29      6874770.75      2634596.80      6874336.49
      2634427.17      6873963.31      2634147.88      6873381.72
      2634223.62      6873060.87
#Sta/Elev= 30
  4130.5  396.14  4330.2  394.90  4353.0  391.98  4443.2  392.71  4448.5  395.04
  4681.4  395.49  4698.1  393.84  4703.6  395.49  4802.3  395.67  4818.9  394.07
  4824.4  395.47  4916.7  395.78  4962.8  393.50  4968.3  395.50  4985.9  393.55
  4991.4  395.72  5053.9  394.27  5059.5  395.73  5150.1  394.34  5178.2  395.82
  5195.3  394.17  5200.9  395.86  5554.7  395.75  5652.4  395.10  5663.9  391.96
  5697.2  388.02  5697.9  387.52  5702.5  388.02  5869.1  404.86  5972.3  405.98
#Mann=3,-1,0
  4130.5    0.05       0  5697.2    0.04       0  5702.5    0.05       0
Bank Sta=5697.2,5702.5
Exp/Cntr=0.3,0.1

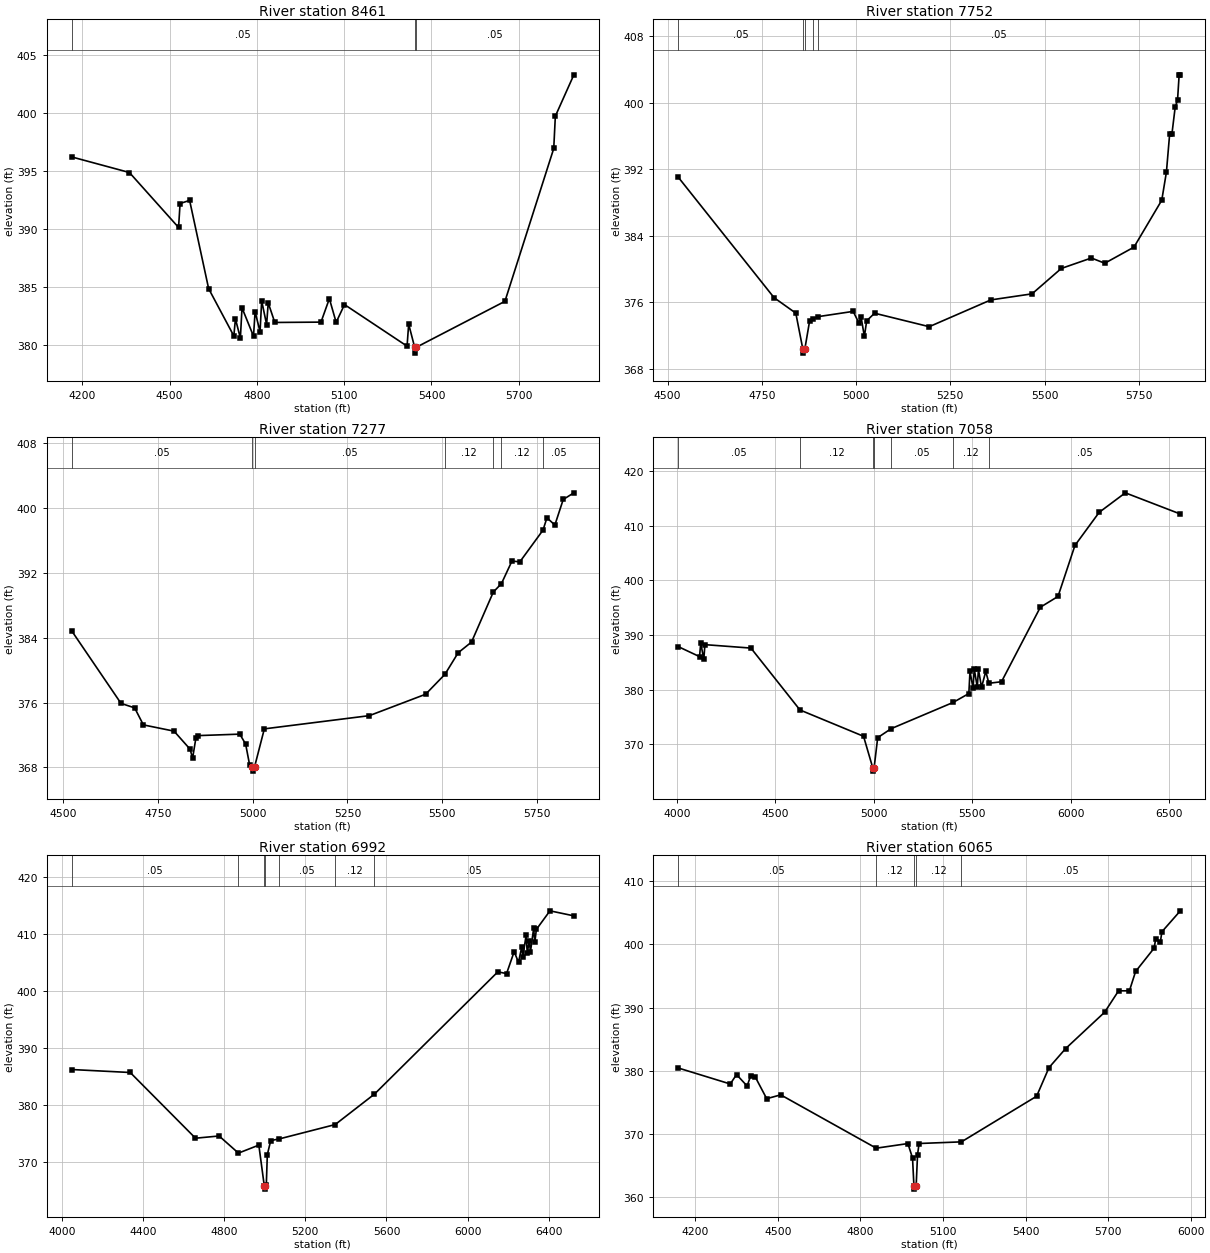
Type RM Length L Ch R = 1,8461,709,709,709
BEGIN DESCRIPTION:
Mapping XS 6cb6c2db
END DESCRIPTION:
XS GIS Cut Line= 5
      2634759.65      6874743.61      2634603.59      6874234.71
      2634474.67      6873970.09      2634227.75      6873412.10
      2634284.69      6873128.69
#Sta/Elev= 30
  4163.5  396.23  4361.6  394.89  4530.6  390.16  4535.8  392.22  4568.6  392.49
  4634.0  384.89  4720.6  380.82  4726.1  382.29  4743.1  380.63  4748.7  383.24
  4788.2  380.80  4793.7  382.91  4810.7  381.18  4816.3  383.84  4833.3  381.80
  4838.8  383.67  4861.4  381.98  5020.2  382.01  5049.0  384.03  5072.3  381.99
  5101.0  383.52  5316.1  379.94  5321.6  381.84  5342.2  379.84  5343.0  379.34
  5347.5  379.84  5652.5  383.80  5820.3  396.96  5825.8  399.74  5889.4  403.30
#Mann=3,-1,0
  4163.5    0.05       0  5342.2    0.04       0  5347.5    0.05       0
Bank Sta=5342.2,5347.5
Exp/Cntr=0.3,0.1

Type RM Length L Ch R = 1,7752,475,475,475
BEGIN DESCRIPTION:
Kings Creek 23 11.0
END DESCRIPTION:
XS GIS Cut Line= 3
      2635376.01      6874211.02      2635126.00      6873811.00
      2634625.97      6873110.96
#Sta/Elev= 30
  4528.3  391.05  4782.5  376.56  4840.2  374.70  4858.8  370.39  4859.6  369.89
  4864.2  370.39  4876.8  373.75  4885.7  374.02  4899.7  374.28  4992.4  374.91
  5007.4  373.53  5013.5  374.19  5022.1  371.90  5028.3  373.78  5049.2  374.69
  5194.2  373.07  5357.6  376.29  5467.0  377.02  5544.4  380.07  5624.3  381.33
  5659.9  380.70  5737.4  382.64  5811.1  388.28  5823.4  391.65  5832.0  396.23
  5838.1  396.26  5846.7  399.48  5852.9  400.29  5857.2  403.36  5860.3  403.36
#Mann=5,-1,0
  4528.3    0.05       0  4858.8    0.03       0  4864.2    0.05       0
  4885.7    0.12       0  4899.7    0.05       0
Bank Sta=4858.8,4864.2
Exp/Cntr=0.3,0.1

Type RM Length L Ch R = 1,7277,219,219,219
BEGIN DESCRIPTION:
Kings Creek 23 10.0
END DESCRIPTION:
XS GIS Cut Line= 3
      2635776.02      6874011.03      2635526.00      6873611.00
      2634976.00      6872961.00
#Sta/Elev= 30
  4523.4  384.82  4653.2  375.89  4689.1  375.34  4712.1  373.24  4792.9  372.47
  4835.3  370.24  4841.8  369.13  4850.7  371.67  4856.6  371.92  4966.2  372.10
  4981.6  370.88  4992.2  368.28  4999.5  368.04  5000.3  367.54  5005.0  368.04
  5030.9  372.75  5307.7  374.38  5456.0  377.02  5506.8  379.47  5541.7  382.13
  5576.9  383.45  5634.4  389.62  5655.8  390.66  5683.5  393.44  5704.3  393.34
  5765.3  397.25  5775.7  398.77  5796.6  397.88  5818.6  401.03  5846.6  401.85
#Mann=7,-1,0
  4523.4    0.05       0  4999.5    0.04       0  5005.0    0.05       0
  5506.8    0.12       0  5634.4    0.05       0  5655.8    0.12       0
  5765.3    0.05       0
Bank Sta=4999.5,5005
Exp/Cntr=0.3,0.1

Type RM Length L Ch R = 1,7058,66,66,66
BEGIN DESCRIPTION:
Mapping XS d112291d
END DESCRIPTION:
XS GIS Cut Line= 4
      2636177.74      6874356.84      2635879.19      6873854.74
      2635702.78      6873495.13      2634909.23      6872145.43
#Sta/Elev= 30
  4007.4  387.87  4115.7  386.04  4121.6  388.54  4137.2  385.52  4143.0  388.23
  4376.7  387.60  4625.7  376.29  4948.7  371.48  4996.4  365.61  4997.2  365.11
  5002.0  365.61  5020.6  371.23  5088.9  372.87  5403.3  377.66  5483.6  379.29
  5489.4  383.34  5505.1  380.23  5510.9  383.83  5526.5  380.42  5532.3  383.75
  5548.0  380.42  5569.5  383.34  5585.4  381.17  5649.5  381.45  5846.8  395.07
  5936.5  397.04  6022.6  406.37  6145.6  412.41  6278.4  415.98  6557.8  412.11
#Mann=7,-1,0
  4007.4    0.05       0  4625.7    0.12       0  4996.4    0.07       0
  5002.0    0.12       0  5088.9    0.05       0  5403.3    0.12       0
  5585.4    0.05       0
Bank Sta=4996.4,5002
Exp/Cntr=0.3,0.1

Type RM Length L Ch R = 1,6992,927,927,927
BEGIN DESCRIPTION:
Mapping XS 8945249d
END DESCRIPTION:
XS GIS Cut Line= 4
      2636238.80      6874255.07      2635736.70      6873427.28
      2635485.65      6872945.54      2635003.92      6872110.99
#Sta/Elev= 30
  4048.6  386.26  4336.8  385.74  4658.5  374.23  4774.9  374.62  4870.2  371.62
  4970.7  373.02  4997.9  365.81  4998.8  365.31  5003.5  365.81  5007.5  365.97
  5012.6  371.36  5029.3  373.81  5071.8  374.11  5347.1  376.62  5540.8  381.96
  6148.9  403.37  6192.0  403.07  6229.3  406.90  6250.8  405.05  6266.6  407.70
  6272.4  406.02  6288.2  409.79  6293.9  406.68  6303.9  408.82  6309.7  406.88
  6325.5  411.00  6331.2  408.52  6338.8  410.80  6405.9  414.06  6523.6  413.18
#Mann=7,-1,0
  4048.6    0.05       0  4870.2    0.12       0  4997.9    0.07       0
  5003.5    0.12       0  5071.8    0.05       0  5347.1    0.12       0
  5540.8    0.05       0
Bank Sta=4997.9,5003.5
Exp/Cntr=0.3,0.1

Type RM Length L Ch R = 1,6065,973,973,973
BEGIN DESCRIPTION:
Kings Creek 23 7.0
END DESCRIPTION:
XS GIS Cut Line= 3
      2636571.27      6873956.49      2636405.41      6873110.40
      2635981.00      6872246.74
#Sta/Elev= 30
  4137.8  380.44  4326.8  377.91  4349.7  379.40  4388.0  377.59  4401.2  379.20
  4418.5  378.95  4459.3  375.58  4510.2  376.19  4857.3  367.75  4972.4  368.48
  4989.2  366.19  4994.3  361.77  4995.2  361.27  5000.0  361.77  5002.4  361.77
  5007.4  366.72  5013.0  368.49  5166.9  368.75  5440.1  375.97  5485.1  380.50
  5545.3  383.50  5687.4  389.27  5737.9  392.65  5777.3  392.65  5799.8  395.71
  5867.2  399.41  5872.8  400.87  5889.7  400.33  5895.3  401.99  5962.3  405.31
#Mann=5,-1,0
  4137.8    0.05       0  4857.3    0.12       0  4994.3    0.07       0
  5000.0    0.12       0  5166.9    0.05       0
Bank Sta=4994.3,5000
Exp/Cntr=0.3,0.1

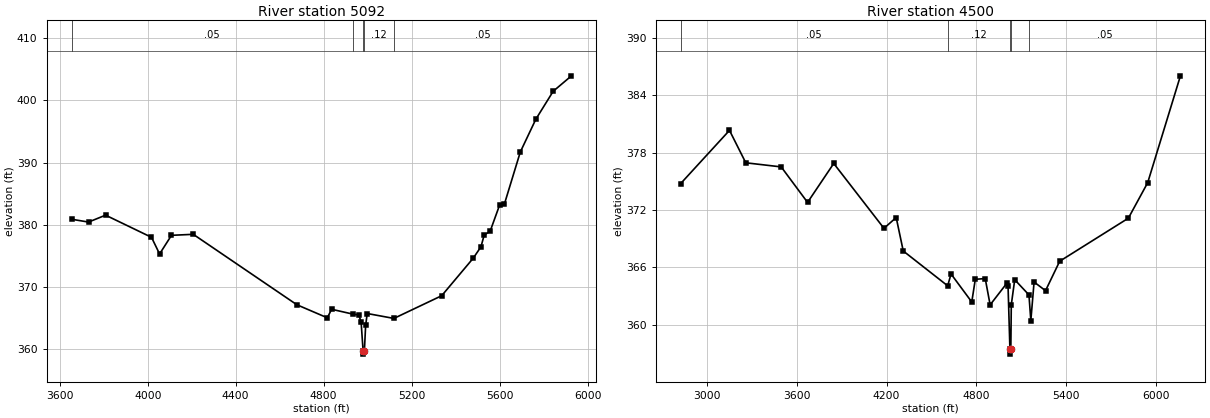
Type RM Length L Ch R = 1,5092,592,592,592
BEGIN DESCRIPTION:
Kings Creek 23 6.0
END DESCRIPTION:
XS GIS Cut Line= 4
      2636713.76      6874031.16      2637122.94      6873026.50
      2637066.37      6872771.90      2636503.40      6872036.31
#Sta/Elev= 30
  3654.4  380.88  3731.1  380.43  3808.6  381.54  4017.3  377.98  4054.1  375.30
  4108.1  378.30  4207.2  378.46  4678.0  367.14  4816.5  365.04  4836.1  366.41
  4933.0  365.63  4959.9  365.50  4970.2  364.33  4979.2  359.70  4980.1  359.20
  4985.0  359.70  4990.7  363.81  4997.9  365.73  5119.1  364.94  5336.4  368.59
  5479.7  374.62  5515.0  376.46  5529.5  378.34  5556.7  378.96  5600.2  383.22
  5621.0  383.27  5693.7  391.69  5764.3  396.96  5843.3  401.46  5926.3  403.94
#Mann=5,-1,0
  3654.4    0.05       0  4933.0    0.12       0  4979.2    0.07       0
  4985.0    0.12       0  5119.1    0.05       0
Bank Sta=4979.2,4985
Exp/Cntr=0.3,0.1

Type RM Length L Ch R = 1,4500,0,0,0
BEGIN DESCRIPTION:
Kings Creek 23 5.0
END DESCRIPTION:
XS GIS Cut Line= 3
      2636626.02      6874460.96      2637481.02      6872460.84
      2637935.07      6871391.77
#Sta/Elev= 30
  2824.8  374.75  3151.0  380.32  3259.8  376.93  3496.3  376.50  3672.3  372.79
  3847.0  376.86  4182.3  370.08  4264.0  371.21  4311.1  367.71  4607.7  364.07
  4630.1  365.31  4768.5  362.38  4792.1  364.75  4858.4  364.83  4891.1  362.08
  5002.6  364.34  5010.7  364.04  5023.3  357.43  5024.3  356.93  5029.2  357.43
  5032.4  362.10  5055.3  364.71  5150.3  363.12  5162.8  360.43  5184.5  364.47
  5260.9  363.56  5355.5  366.64  5813.9  371.14  5943.0  374.85  6161.5  386.02
#Mann=5,-1,0
  2824.8    0.05       0  4607.7    0.12       0  5023.3    0.07       0
  5029.2    0.12       0  5150.3    0.05       0
Bank Sta=5023.3,5029.2
Exp/Cntr=0.3,0.1

Chan Stop Cuts=-1