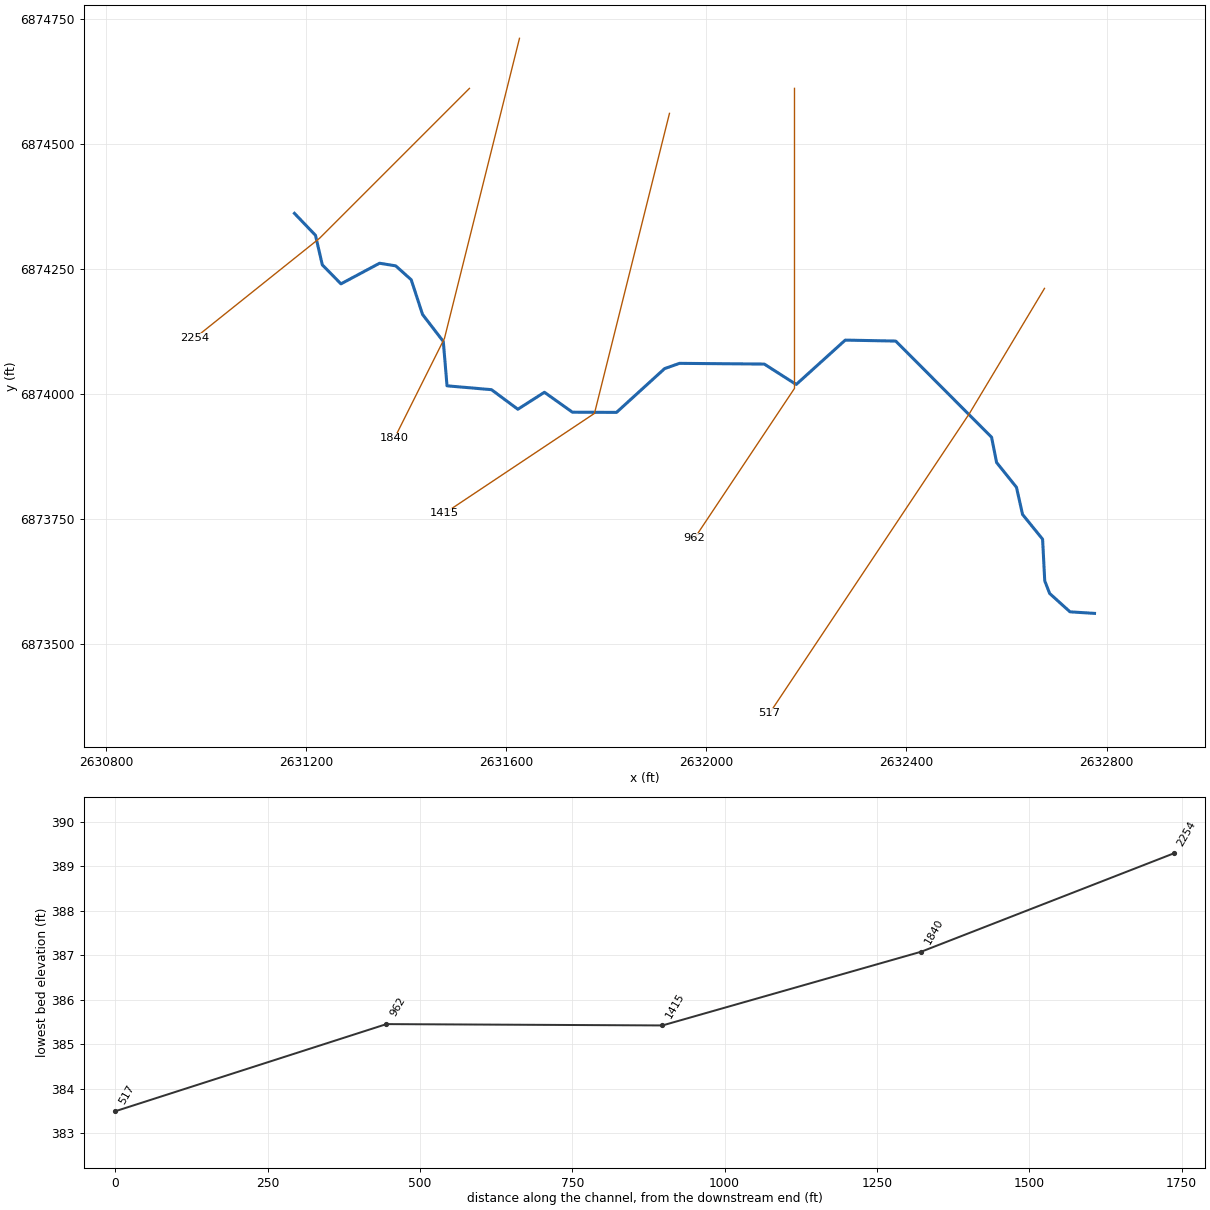
--- Kings Creek 23_1.prj (project) ---

Proj Title=Kings Creek 23_1 Base Level Engineering
Current Plan=p01
Default Exp/Contr=0.3,0.1
English Units
Geom File=g01
Flow File=f01
Plan File=p01
BEGIN DESCRIPTION:
Kings Creek 23_1
END DESCRIPTION:

--- Kings Creek 23_1.p01 (plan) ---

Plan Title=Multiple Run
Short Identifier=Multiple
Geom File=g01
Flow File=f01
Subcritical Flow
K Sum by GR= 0
Std Step Tol= 0.01
Critical Tol= 0.01
Num of Std Step Trials= 20
Max Error Tol= 0.3
Flow Tol Ratio= 0.001
Split Flow NTrial= 30
Split Flow Tol= 0.02
Split Flow Ratio= 0.02
Log Output Level= 0
Friction Slope Method= 1
Unsteady Friction Slope Method= 2
Unsteady Bridges Friction Slope Method= 1
Parabolic Critical Depth
Global Vel Dist=  1 , 1 , 1
Global Log Level= 0
CheckData=True
Encroach Param= -1, 0, 0, 0
BEGIN DESCRIPTION:
Multiple Run
END DESCRIPTION:

--- Kings Creek 23_1.f01 (steady flow) ---

Flow Title=Multiple
Number of Profiles=7
Profile Names=10-year,25-year,50-year,1pct_min,100-year,1pct_plu,500-year
River Rch & RM= Kings Creek 23_1,Reach-1,2254
     423     555     660     389     777    1551    1077
Boundary for River Rch & Prof#=Kings Creek 23_1,Reach-1,1
Up Type=0
Dn Type=3
Dn Slope=0.005
Boundary for River Rch & Prof#=Kings Creek 23_1,Reach-1,2
Up Type=0
Dn Type=3
Dn Slope=0.005
Boundary for River Rch & Prof#=Kings Creek 23_1,Reach-1,3
Up Type=0
Dn Type=3
Dn Slope=0.005
Boundary for River Rch & Prof#=Kings Creek 23_1,Reach-1,4
Up Type=0
Dn Type=3
Dn Slope=0.005
Boundary for River Rch & Prof#=Kings Creek 23_1,Reach-1,5
Up Type=0
Dn Type=3
Dn Slope=0.005
Boundary for River Rch & Prof#=Kings Creek 23_1,Reach-1,6
Up Type=0
Dn Type=3
Dn Slope=0.005
Boundary for River Rch & Prof#=Kings Creek 23_1,Reach-1,7
Up Type=0
Dn Type=3
Dn Slope=0.005

--- Kings Creek 23_1.g01 (geometry) ---

Geom Title=Existing Conditions

River Reach=Kings Creek 23_1,Reach-1
Reach XY= 30
      2631176.00      6874361.00      2631218.06      6874317.08
      2631231.71      6874258.05      2631268.99      6874220.01
      2631346.23      6874261.27      2631378.54      6874255.99
      2631409.51      6874228.22      2631432.15      6874158.85
      2631473.63      6874104.94      2631481.11      6874016.10
      2631570.01      6874008.41      2631622.78      6873969.27
      2631675.90      6874003.20      2631731.89      6873963.35
      2631820.10      6873962.98      2631916.21      6874050.50
      2631945.99      6874061.04      2632115.57      6874059.61
      2632179.41      6874018.81      2632277.50      6874107.52
      2632378.43      6874105.60      2632570.17      6873913.30
      2632580.19      6873862.74      2632619.92      6873813.20
      2632632.12      6873758.82      2632672.17      6873709.41
      2632676.46      6873626.11      2632686.26      6873600.90
      2632726.99      6873564.12      2632776.00      6873561.00

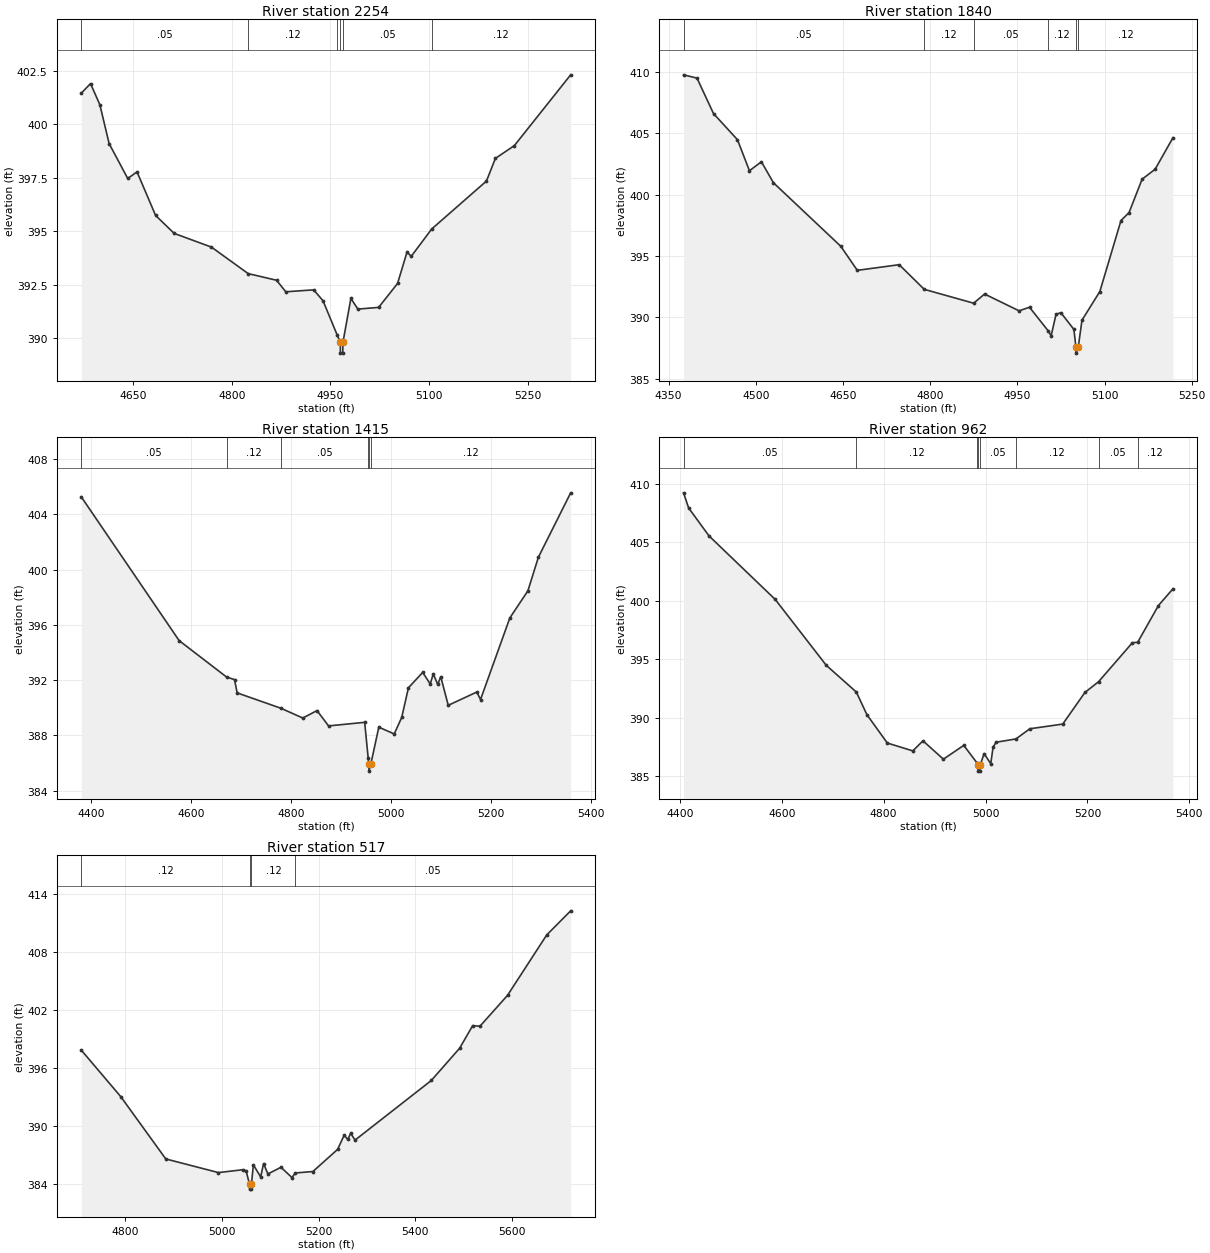
Type RM Length L Ch R = 1,2254,414,414,414
BEGIN DESCRIPTION:
Kings Creek 23_1 5.0
END DESCRIPTION:
XS GIS Cut Line= 3
      2631525.98      6874610.98      2631226.00      6874311.00
      2630976.00      6874111.00
#Sta/Elev= 30
  4571.2  401.45  4585.3  401.90  4599.5  400.91  4613.6  399.09  4641.9  397.46
  4656.0  397.77  4684.3  395.73  4712.6  394.89  4769.2  394.25  4825.1  393.01
  4868.2  392.70  4882.3  392.16  4924.7  392.25  4938.9  391.74  4960.3  390.15
  4965.2  389.79  4965.4  389.29  4968.9  389.29  4969.2  389.79  4981.3  391.85
  4991.9  391.35  5023.5  391.43  5052.3  392.55  5066.7  394.02  5073.1  393.82
  5104.3  395.10  5187.5  397.34  5201.1  398.40  5230.0  399.00  5315.6  402.31
#Mann=6,-1,0
  4571.2    0.05       0  4825.1    0.12       0  4960.3    0.05       0
  4965.2    0.03       0  4969.2    0.05       0  5104.3    0.12       0
Bank Sta=4965.2,4969.2
Exp/Cntr=0.3,0.1

Type RM Length L Ch R = 1,1840,425,425,425
BEGIN DESCRIPTION:
Kings Creek 23_1 4.0
END DESCRIPTION:
XS GIS Cut Line= 3
      2631626.01      6874711.03      2631476.00      6874111.00
      2631376.00      6873911.01
#Sta/Elev= 30
  4375.6  409.77  4398.8  409.50  4427.2  406.61  4468.4  404.48  4489.0  401.95
  4509.6  402.68  4530.3  400.97  4646.2  395.79  4674.6  393.83  4746.7  394.29
  4789.8  392.28  4874.8  391.15  4893.6  391.90  4952.9  390.53  4970.9  390.82
  5003.3  388.88  5008.1  388.49  5016.5  390.24  5024.8  390.38  5047.2  389.02
  5050.8  387.58  5051.0  387.08  5054.8  387.58  5061.2  389.77  5091.9  392.10
  5128.3  397.89  5142.2  398.54  5164.6  401.26  5187.0  402.07  5217.7  404.64
#Mann=6,-1,0
  4375.6    0.05       0  4789.8    0.12       0  4874.8    0.05       0
  5003.3    0.12       0  5050.8    0.03       0  5054.8    0.12       0
Bank Sta=5050.8,5054.8
Exp/Cntr=0.3,0.1

Type RM Length L Ch R = 1,1415,453,453,453
BEGIN DESCRIPTION:
Kings Creek 23_1 3.0
END DESCRIPTION:
XS GIS Cut Line= 3
      2631925.99      6874560.98      2631776.00      6873961.00
      2631476.00      6873761.00
#Sta/Elev= 30
  4380.1  405.26  4575.9  394.86  4671.0  392.22  4686.7  392.04  4691.9  391.08
  4779.3  389.97  4823.3  389.26  4851.7  389.80  4874.8  388.69  4947.0  388.95
  4954.0  386.39  4955.3  385.92  4955.6  385.42  4959.3  385.92  4975.3  388.60
  5006.1  388.11  5021.1  389.30  5034.6  391.45  5063.1  392.56  5078.2  391.72
  5084.2  392.45  5093.2  391.69  5099.2  392.25  5114.2  390.18  5171.3  391.14
  5178.8  390.60  5237.4  396.50  5273.5  398.46  5294.5  400.89  5359.1  405.55
#Mann=6,-1,0
  4380.1    0.05       0  4671.0    0.12       0  4779.3    0.05       0
  4954.0    0.12       0  4955.3    0.07       0  4959.3    0.12       0
Bank Sta=4955.3,4959.3
Exp/Cntr=0.3,0.1

Type RM Length L Ch R = 1,962,445,445,445
BEGIN DESCRIPTION:
Kings Creek 23_1 2.0
END DESCRIPTION:
XS GIS Cut Line= 3
      2632176.00      6874611.04      2632176.00      6874011.00
      2631976.00      6873711.00
#Sta/Elev= 30
  4407.3  409.23  4417.3  407.94  4457.3  405.55  4587.3  400.12  4687.3  394.50
  4746.4  392.21  4767.3  390.27  4807.3  387.85  4857.3  387.18  4877.3  388.04
  4917.3  386.47  4957.3  387.65  4983.0  386.17  4985.3  385.95  4985.6  385.45
  4989.1  385.45  4989.3  385.95  4997.3  386.94  5010.3  386.09  5014.9  387.51
  5020.9  387.92  5059.7  388.20  5087.0  389.07  5151.6  389.47  5195.1  392.17
  5221.9  393.09  5288.3  396.42  5298.7  396.46  5339.4  399.60  5367.9  401.03
#Mann=8,-1,0
  4407.3    0.05       0  4746.4    0.12       0  4983.0    0.05       0
  4985.3    0.03       0  4989.3    0.05       0  5059.7    0.12       0
  5221.9    0.05       0  5298.7    0.12       0
Bank Sta=4985.3,4989.3
Exp/Cntr=0.3,0.1

Type RM Length L Ch R = 1,517,0,0,0
BEGIN DESCRIPTION:
Kings Creek 23_1 1.0
END DESCRIPTION:
XS GIS Cut Line= 3
      2632675.99      6874210.99      2632526.00      6873961.00
      2632126.02      6873361.04
#Sta/Elev= 30
  4708.7  397.86  4790.3  393.06  4883.6  386.61  4992.5  385.20  5043.8  385.50
  5049.8  385.38  5056.8  383.99  5057.1  383.49  5060.6  383.49  5060.8  383.99
  5064.8  386.00  5079.9  384.75  5085.9  386.13  5094.9  385.06  5121.9  385.75
  5144.5  384.69  5151.7  385.16  5188.0  385.31  5239.1  387.60  5252.6  389.06
  5260.1  388.63  5266.1  389.26  5275.2  388.56  5432.9  394.72  5491.5  398.05
  5518.5  400.39  5533.6  400.33  5590.6  403.52  5671.8  409.77  5721.3  412.26
#Mann=4,-1,0
  4708.7    0.12       0  5056.8    0.07       0  5060.8    0.12       0
  5151.7    0.05       0
Bank Sta=5056.8,5060.8
Exp/Cntr=0.3,0.1

Chan Stop Cuts=-1