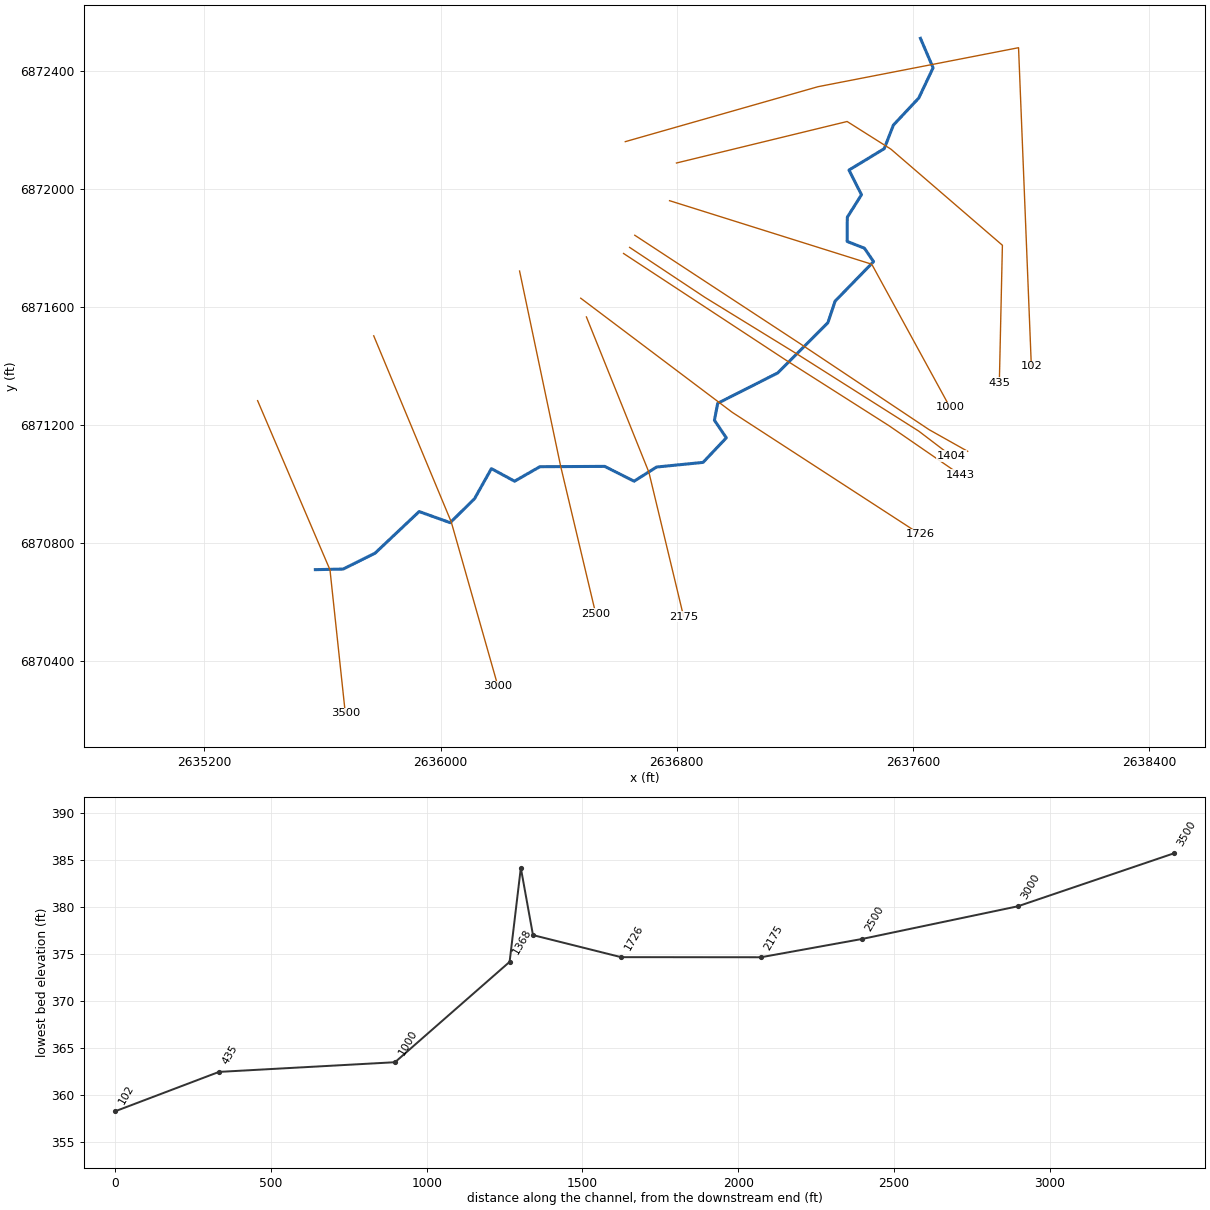
--- Kings Creek 23_2.prj (project) ---

Proj Title=Kings Creek 23_2 Base Level Engineering
Current Plan=p01
Default Exp/Contr=0.3,0.1
English Units
Geom File=g01
Flow File=f01
Plan File=p01
BEGIN DESCRIPTION:
Kings Creek 23_2
END DESCRIPTION:

--- Kings Creek 23_2.p01 (plan) ---

Plan Title=Multiple Run
Short Identifier=Multiple
Geom File=g01
Flow File=f01
Subcritical Flow
K Sum by GR= 0
Std Step Tol= 0.01
Critical Tol= 0.01
Num of Std Step Trials= 20
Max Error Tol= 0.3
Flow Tol Ratio= 0.001
Split Flow NTrial= 30
Split Flow Tol= 0.02
Split Flow Ratio= 0.02
Log Output Level= 0
Friction Slope Method= 1
Unsteady Friction Slope Method= 2
Unsteady Bridges Friction Slope Method= 1
Parabolic Critical Depth
Global Vel Dist=  1 , 1 , 1
Global Log Level= 0
CheckData=True
Encroach Param= -1, 0, 0, 0
BEGIN DESCRIPTION:
Multiple Run
END DESCRIPTION:

--- Kings Creek 23_2.f01 (steady flow) ---

Flow Title=Multiple
Number of Profiles=7
Profile Names=10-year,25-year,50-year,1pct_min,100-year,1pct_plu,500-year
River Rch & RM= Kings Creek 23_2,Reach-1,3500
     422     559     669     398     794    1584    1116
River Rch & RM= Kings Creek 23_2,Reach-1,102
    1058    1473    1819    1112    2219    4427    3306
Boundary for River Rch & Prof#=Kings Creek 23_2,Reach-1,1
Up Type=0
Dn Type=3
Dn Slope=0.005
Boundary for River Rch & Prof#=Kings Creek 23_2,Reach-1,2
Up Type=0
Dn Type=3
Dn Slope=0.005
Boundary for River Rch & Prof#=Kings Creek 23_2,Reach-1,3
Up Type=0
Dn Type=3
Dn Slope=0.005
Boundary for River Rch & Prof#=Kings Creek 23_2,Reach-1,4
Up Type=0
Dn Type=3
Dn Slope=0.005
Boundary for River Rch & Prof#=Kings Creek 23_2,Reach-1,5
Up Type=0
Dn Type=3
Dn Slope=0.005
Boundary for River Rch & Prof#=Kings Creek 23_2,Reach-1,6
Up Type=0
Dn Type=3
Dn Slope=0.005
Boundary for River Rch & Prof#=Kings Creek 23_2,Reach-1,7
Up Type=0
Dn Type=3
Dn Slope=0.005

--- Kings Creek 23_2.g01 (geometry) ---

Geom Title=Existing Conditions

River Reach=Kings Creek 23_2,Reach-1
Reach XY= 30
      2635576.00      6870711.00      2635670.14      6870713.07
      2635778.30      6870766.83      2635927.65      6870907.84
      2636032.75      6870870.14      2636115.22      6870951.31
      2636172.34      6871053.28      2636250.96      6871010.69
      2636336.50      6871059.76      2636555.97      6871060.91
      2636655.82      6871010.72      2636731.93      6871058.70
      2636889.37      6871074.37      2636968.19      6871157.58
      2636927.97      6871217.09      2636938.99      6871274.56
      2637142.68      6871377.64      2637312.37      6871547.79
      2637336.78      6871620.68      2637467.09      6871754.48
      2637436.12      6871800.10      2637377.55      6871822.87
      2637378.15      6871904.95      2637426.20      6871981.21
      2637383.72      6872064.66      2637503.13      6872137.16
      2637534.18      6872217.02      2637620.18      6872308.72
      2637668.72      6872411.03      2637626.00      6872511.00

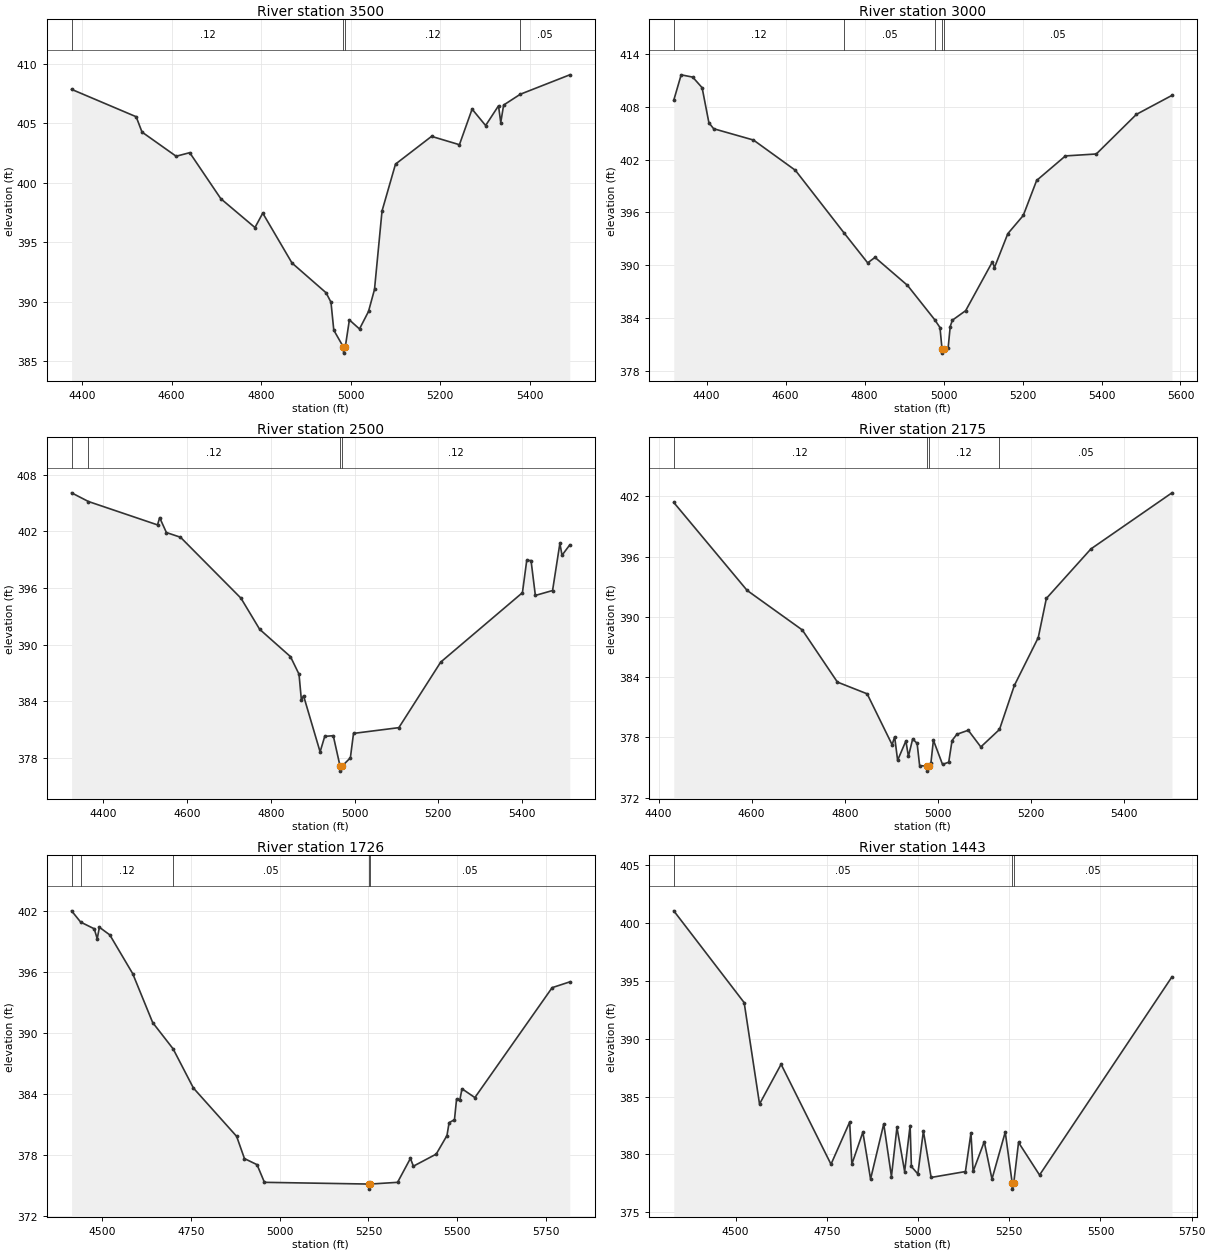
Type RM Length L Ch R = 1,3500,500,500,500
BEGIN DESCRIPTION:
Kings Creek 23_2 7.0
END DESCRIPTION:
XS GIS Cut Line= 3
      2635380.37      6871283.54      2635625.56      6870710.38
      2635677.51      6870224.14
#Sta/Elev= 30
  4376.6  407.85  4520.8  405.55  4533.9  404.26  4610.1  402.23  4640.4  402.53
  4709.9  398.66  4786.1  396.24  4803.5  397.45  4868.8  393.26  4944.9  390.76
  4955.8  389.97  4962.1  387.62  4983.7  386.19  4984.0  385.69  4987.7  386.19
  4996.9  388.48  5019.5  387.72  5039.6  389.19  5053.0  391.04  5069.8  397.63
  5099.9  401.57  5180.4  403.90  5242.6  403.20  5270.9  406.19  5301.1  404.81
  5329.9  406.47  5334.9  405.06  5341.3  406.53  5378.6  407.44  5489.0  409.07
#Mann=4,-1,0
  4376.6    0.12       0  4983.7    0.07       0  4987.7    0.12       0
  5378.6    0.05       0
Bank Sta=4983.7,4987.7
Exp/Cntr=0.3,0.1

Type RM Length L Ch R = 1,3000,500,500,500
BEGIN DESCRIPTION:
Kings Creek 23_2 6.0
END DESCRIPTION:
XS GIS Cut Line= 3
      2635773.76      6871503.17      2636036.46      6870872.38
      2636194.64      6870316.03
#Sta/Elev= 30
  4316.7  408.72  4335.4  411.60  4364.7  411.34  4388.5  410.14  4405.7  406.16
  4417.8  405.49  4518.5  404.21  4624.7  400.78  4748.0  393.68  4807.8  390.29
  4826.3  390.91  4908.6  387.74  4977.3  383.86  4990.9  382.96  4996.0  380.56
  4996.3  380.06  5000.0  380.56  5011.6  380.67  5016.8  383.07  5022.2  383.79
  5055.9  384.87  5123.7  390.41  5128.9  389.76  5162.7  393.60  5201.8  395.66
  5235.7  399.63  5308.6  402.41  5386.8  402.63  5488.4  407.12  5578.4  409.27
#Mann=5,-1,0
  4316.7    0.12       0  4748.0    0.05       0  4977.3    0.12       0
  4996.0    0.03       0  5000.0    0.05       0
Bank Sta=4996,5000
Exp/Cntr=0.3,0.1

Type RM Length L Ch R = 1,2500,325,325,325
BEGIN DESCRIPTION:
Kings Creek 23_2 5.0
END DESCRIPTION:
XS GIS Cut Line= 3
      2636267.84      6871722.69      2636407.06      6871061.18
      2636525.99      6870561.03
#Sta/Elev= 30
  4324.0  406.09  4364.2  405.17  4529.3  402.69  4534.4  403.46  4550.5  401.88
  4584.2  401.38  4728.6  394.92  4773.3  391.62  4846.9  388.72  4867.3  386.86
  4873.0  384.11  4878.1  384.58  4917.7  378.62  4928.7  380.26  4949.1  380.34
  4965.5  377.08  4965.8  376.58  4969.5  377.08  4990.0  377.99  4997.5  380.58
  5105.8  381.19  5205.8  388.14  5401.0  395.50  5411.3  398.92  5421.6  398.91
  5431.9  395.21  5473.0  395.73  5490.5  400.73  5495.6  399.47  5514.1  400.57
#Mann=4,-1,0
  4324.0    0.05       0  4364.2    0.12       0  4965.5    0.07       0
  4969.5    0.12       0
Bank Sta=4965.5,4969.5
Exp/Cntr=0.3,0.1

Type RM Length L Ch R = 1,2175,449,449,449
BEGIN DESCRIPTION:
Kings Creek 23_2 4.0
END DESCRIPTION:
XS GIS Cut Line= 3
      2636494.26      6871567.21      2636706.00      6871040.80
      2636823.64      6870551.64
#Sta/Elev= 30
  4432.6  401.39  4590.2  392.63  4708.8  388.69  4784.2  383.50  4848.1  382.33
  4901.8  377.26  4907.2  378.05  4913.6  375.71  4931.4  377.64  4936.8  376.09
  4945.9  377.83  4955.5  377.40  4960.9  375.18  4976.2  375.13  4976.5  374.63
  4980.2  375.13  4985.1  375.42  4990.5  377.71  5010.1  375.30  5023.4  375.52
  5030.6  377.68  5040.9  378.30  5065.4  378.70  5092.4  377.04  5132.5  378.78
  5164.4  383.16  5215.8  387.93  5233.2  391.83  5328.9  396.76  5503.1  402.35
#Mann=4,-1,0
  4432.6    0.12       0  4976.2    0.07       0  4980.2    0.12       0
  5132.5    0.05       0
Bank Sta=4976.2,4980.2
Exp/Cntr=0.3,0.1

Type RM Length L Ch R = 1,1726,283,283,283
BEGIN DESCRIPTION:
Kings Creek 23_2 3.0
END DESCRIPTION:
XS GIS Cut Line= 3
      2636475.07      6871630.60      2636988.11      6871244.13
      2637625.04      6870830.63
#Sta/Elev= 30
  4414.8  402.06  4440.3  400.95  4478.6  400.29  4486.9  399.31  4493.1  400.44
  4522.3  399.69  4586.8  395.87  4643.0  391.05  4700.5  388.46  4757.6  384.60
  4879.2  379.84  4901.2  377.65  4936.6  377.05  4957.4  375.31  5251.5  375.14
  5251.8  374.64  5255.5  375.14  5332.0  375.31  5368.2  377.67  5376.5  376.90
  5440.7  378.09  5471.0  379.92  5477.0  381.19  5492.1  381.48  5498.1  383.54
  5507.2  383.41  5513.2  384.53  5549.5  383.66  5766.9  394.49  5816.5  395.06
#Mann=5,-1,0
  4414.8    0.05       0  4440.3    0.12       0  4700.5    0.05       0
  5251.5    0.04       0  5255.5    0.05       0
Bank Sta=5251.5,5255.5
Exp/Cntr=0.3,0.1

Type RM Length L Ch R = 1,1443,39,39,39
BEGIN DESCRIPTION:
Mapping XS acedd154
END DESCRIPTION:
XS GIS Cut Line= 4
      2636620.09      6871782.17      2637166.73      6871423.08
      2637518.98      6871198.93      2637761.23      6871032.09
#Sta/Elev= 30
  4330.3  401.06  4523.3  393.12  4565.4  384.35  4624.5  387.79  4761.3  379.14
  4812.5  382.79  4818.5  379.15  4848.7  381.92  4869.8  377.86  4905.9  382.63
  4927.0  378.08  4942.1  382.33  4963.2  378.51  4978.2  382.49  4981.7  378.95
  4999.4  378.30  5014.6  382.01  5035.8  378.00  5129.8  378.51  5145.0  381.85
  5150.9  378.52  5181.4  381.09  5202.6  377.86  5239.0  381.92  5258.2  377.49
  5258.4  376.99  5262.2  377.49  5275.4  381.03  5333.0  378.21  5696.0  395.35
#Mann=3,-1,0
  4330.3    0.05       0  5258.2    0.04       0  5262.2    0.05       0
Bank Sta=5258.2,5262.2
Exp/Cntr=0.3,0.1

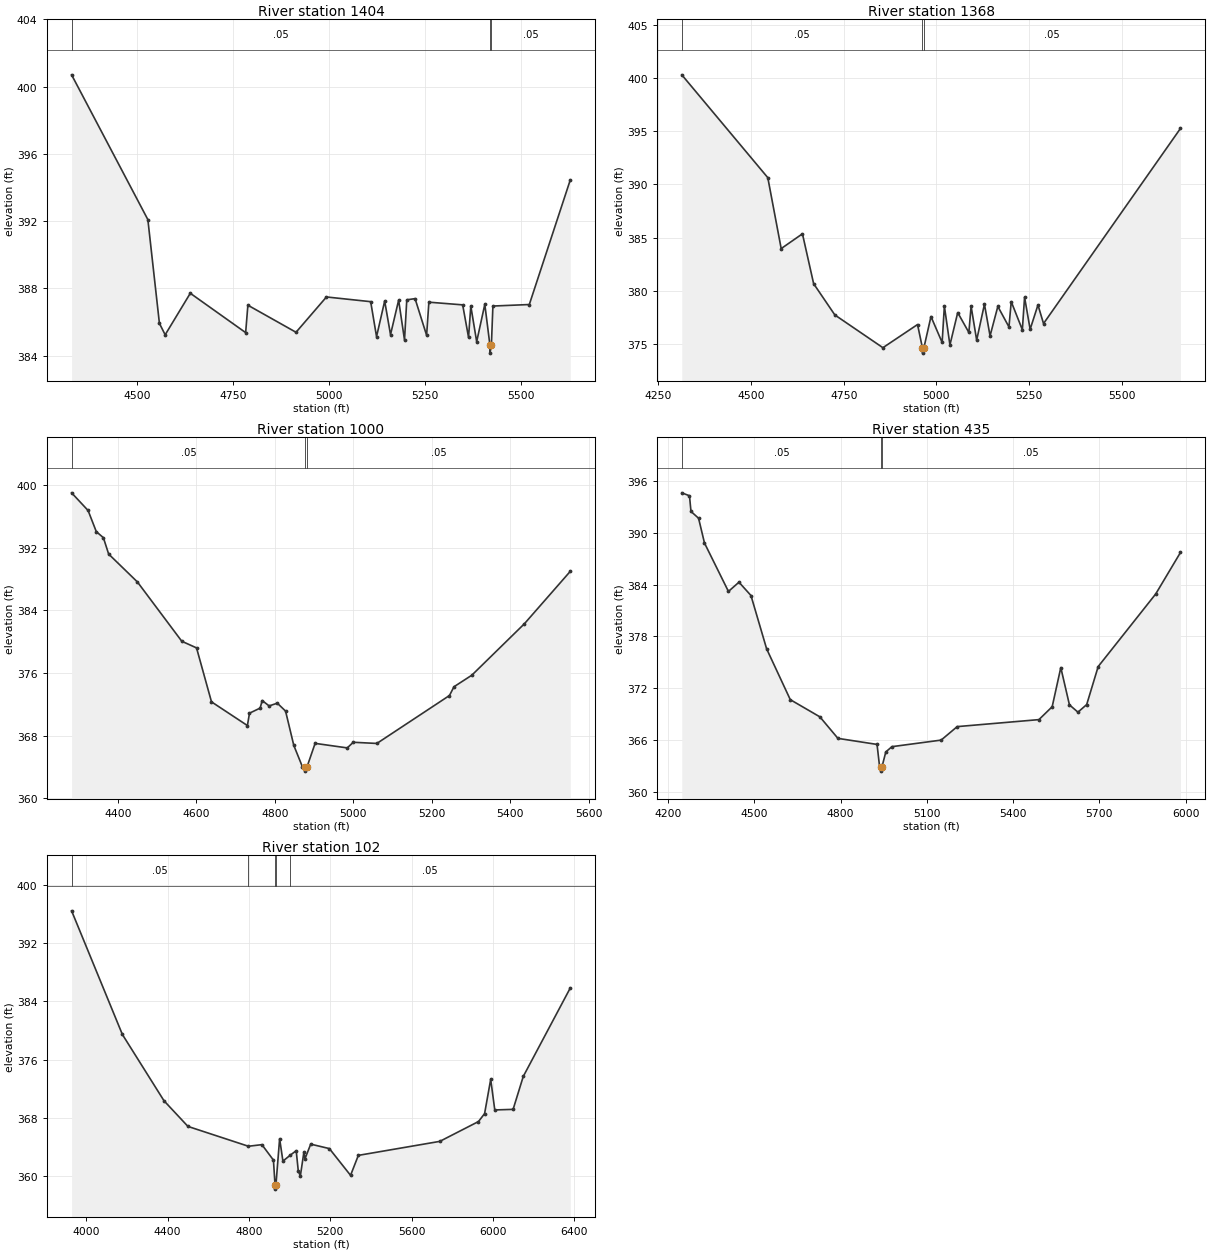
Type RM Length L Ch R = 1,1404,36,36,36
BEGIN DESCRIPTION:
Mapping XS d7a186d1
END DESCRIPTION:
XS GIS Cut Line= 5
      2636640.64      6871802.79      2636895.89      6871633.35
      2637207.12      6871442.03      2637620.29      6871180.23
      2637730.96      6871096.01
#Sta/Elev= 30
  4328.3  400.70  4527.1  392.09  4557.2  385.92  4572.2  385.24  4637.7  387.71
  4782.0  385.37  4787.8  387.00  4913.3  385.39  4992.6  387.49  5107.9  387.21
  5123.2  385.13  5144.4  387.25  5159.6  385.25  5180.8  387.30  5196.1  384.93
  5202.0  387.32  5223.6  387.39  5253.7  385.21  5259.6  387.18  5347.7  387.02
  5363.0  385.09  5368.9  386.95  5384.2  384.83  5405.4  387.05  5418.6  384.65
  5418.9  384.15  5422.6  384.65  5426.5  386.95  5521.4  387.04  5628.2  394.45
#Mann=3,-1,0
  4328.3    0.05       0  5418.6    0.04       0  5422.6    0.05       0
Bank Sta=5418.6,5422.6
Exp/Cntr=0.3,0.1

Type RM Length L Ch R = 1,1368,368,368,368
BEGIN DESCRIPTION:
Mapping XS de8a2660
END DESCRIPTION:
XS GIS Cut Line= 4
      2636658.20      6871843.86      2637216.27      6871477.91
      2637655.43      6871185.14      2637785.83      6871111.93
#Sta/Elev= 30
  4313.4  400.31  4545.3  390.64  4581.4  383.97  4638.7  385.36  4668.9  380.67
  4726.1  377.73  4855.7  374.65  4949.1  376.83  4962.2  374.64  4962.5  374.14
  4966.2  374.64  4985.3  377.58  5015.4  375.14  5021.4  378.56  5036.4  374.91
  5057.4  377.95  5087.5  376.08  5093.5  378.55  5108.5  375.36  5129.5  378.74
  5144.6  375.76  5165.6  378.53  5195.6  376.60  5201.7  378.98  5231.7  376.34
  5237.7  379.40  5252.7  376.38  5273.8  378.67  5288.8  376.92  5658.1  395.27
#Mann=3,-1,0
  4313.4    0.05       0  4962.2    0.04       0  4966.2    0.05       0
Bank Sta=4962.2,4966.2
Exp/Cntr=0.3,0.1

Type RM Length L Ch R = 1,1000,565,565,565
BEGIN DESCRIPTION:
Kings Creek 23_2 2.0
END DESCRIPTION:
XS GIS Cut Line= 3
      2636775.97      6871961.01      2637460.95      6871745.76
      2637726.01      6871260.99
#Sta/Elev= 30
  4282.0  399.04  4324.0  396.78  4344.9  394.08  4363.0  393.30  4376.4  391.21
  4449.7  387.64  4562.7  380.06  4600.3  379.21  4638.4  372.31  4729.9  369.28
  4735.2  370.86  4762.3  371.51  4767.6  372.48  4785.2  371.79  4806.1  372.14
  4827.1  371.13  4848.1  366.74  4870.0  364.01  4877.5  363.95  4877.8  363.45
  4881.5  363.95  4902.4  367.00  4984.3  366.42  4999.6  367.14  5059.7  366.99
  5244.7  373.12  5256.2  374.24  5301.7  375.72  5435.3  382.28  5552.5  389.00
#Mann=3,-1,0
  4282.0    0.05       0  4877.5    0.04       0  4881.5    0.05       0
Bank Sta=4877.5,4881.5
Exp/Cntr=0.3,0.1

Type RM Length L Ch R = 1,435,333,333,333
BEGIN DESCRIPTION:
Mapping XS 6285bd07
END DESCRIPTION:
XS GIS Cut Line= 5
      2636799.36      6872088.64      2637377.49      6872229.26
      2637525.92      6872135.51      2637903.53      6871809.99
      2637893.14      6871344.91
#Sta/Elev= 30
  4247.6  394.62  4274.3  394.28  4279.5  392.47  4305.9  391.68  4326.5  388.81
  4409.8  383.21  4446.4  384.28  4488.1  382.74  4542.6  376.57  4624.9  370.69
  4727.8  368.70  4790.6  366.21  4926.6  365.51  4935.4  362.96  4939.8  362.92
  4940.1  362.42  4943.8  362.92  4957.1  364.64  4978.3  365.25  5149.5  366.01
  5205.4  367.57  5489.6  368.38  5535.7  369.87  5565.7  374.40  5595.7  370.09
  5625.3  369.24  5655.7  370.12  5695.7  374.52  5895.8  382.92  5981.9  387.72
#Mann=3,-1,0
  4247.6    0.05       0  4939.8    0.03       0  4943.8    0.05       0
Bank Sta=4939.8,4943.8
Exp/Cntr=0.3,0.1

Type RM Length L Ch R = 1,102,0,0,0
BEGIN DESCRIPTION:
Kings Creek 23_2 1.0
END DESCRIPTION:
XS GIS Cut Line= 4
      2636625.98      6872161.00      2637278.81      6872347.15
      2637958.22      6872479.26      2638001.59      6871400.22
#Sta/Elev= 30
  3928.6  396.40  4178.2  379.44  4382.7  370.35  4500.5  366.83  4797.6  364.11
  4863.9  364.33  4920.6  362.21  4928.6  358.73  4928.8  358.23  4932.6  358.73
  4951.0  365.15  4967.2  362.07  5003.4  362.89  5032.5  363.50  5042.6  360.74
  5052.8  360.02  5070.5  363.35  5075.6  362.39  5103.8  364.40  5195.5  363.79
  5299.6  360.12  5337.9  362.86  5738.2  364.78  5928.4  367.50  5958.4  368.59
  5988.4  373.29  6008.4  369.09  6098.5  369.17  6148.5  373.69  6379.5  385.82
#Mann=5,-1,0
  3928.6    0.05       0  4797.6    0.12       0  4928.6    0.07       0
  4932.6    0.12       0  5003.4    0.05       0
Bank Sta=4928.6,4932.6
Exp/Cntr=0.3,0.1

Chan Stop Cuts=-1