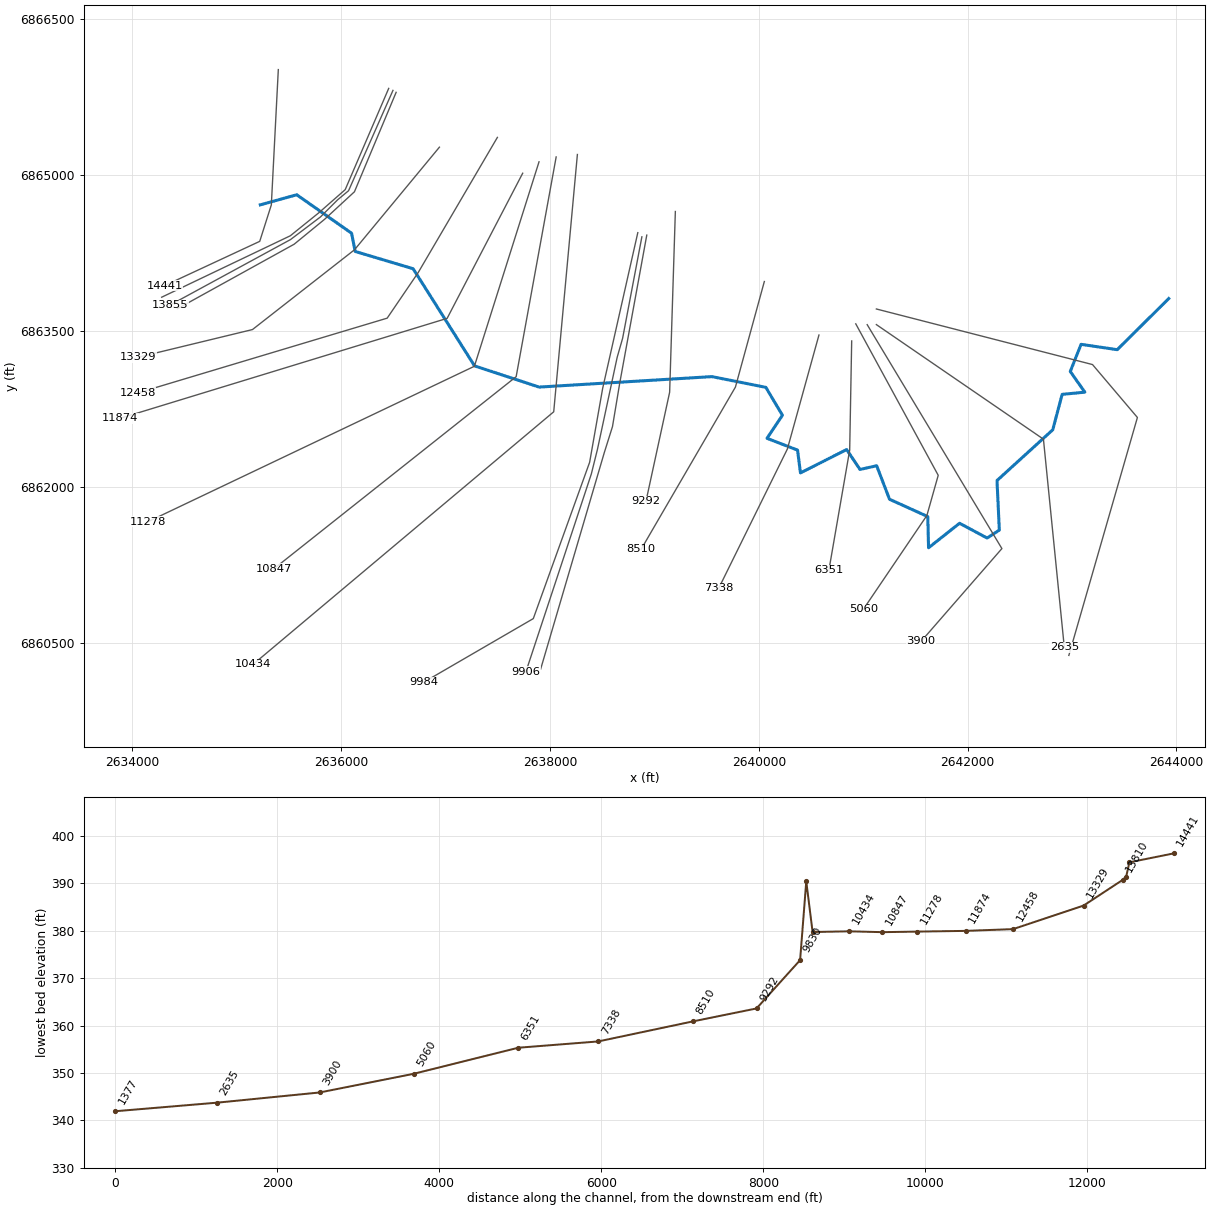
--- Kings Creek 25.prj (project) ---

Proj Title=Kings Creek 25 Base Level Engineering
Current Plan=p01
Default Exp/Contr=0.3,0.1
English Units
Geom File=g01
Flow File=f01
Plan File=p01
Y Axis Title=Elevation
X Axis Title(PF)=Main Channel Distance
X Axis Title(XS)=Station
BEGIN DESCRIPTION:
Kings Creek 25
END DESCRIPTION:
DSS Export Rating Curves= 0
DSS Export Rating Curve Sorted= 0
DSS Export Volume Flow Curves= 0
DXF OffsetX= 0
DXF OffsetY= 0
DXF ScaleX= 1
DXF ScaleY= 10

--- Kings Creek 25.p01 (plan) ---

Plan Title=Multiple Run
Short Identifier=Multiple
Geom File=g01
Flow File=f01
Subcritical Flow
K Sum by GR= 0
Std Step Tol= 0.01
Critical Tol= 0.01
Num of Std Step Trials= 20
Max Error Tol= 0.3
Flow Tol Ratio= 0.001
Split Flow NTrial= 30
Split Flow Tol= 0.02
Split Flow Ratio= 0.02
Log Output Level= 0
Friction Slope Method= 1
Unsteady Friction Slope Method= 2
Unsteady Bridges Friction Slope Method= 1
Parabolic Critical Depth
Global Vel Dist=  1 , 1 , 1
Global Log Level= 0
CheckData=True
Encroach Param= -1, 0, 0, 0
BEGIN DESCRIPTION:
Multiple Run
END DESCRIPTION:

--- Kings Creek 25.f01 (steady flow) ---

Flow Title=Multiple
Number of Profiles=7
Profile Names=10-year,25-year,50-year,1pct_min,100-year,1pct_plu,500-year
River Rch & RM= Kings Creek 25,Reach-1,14441
     477     638     768     460     917    1830    1306
River Rch & RM= Kings Creek 25,Reach-1,13895
     805    1110    1363     830    1657    3306    2447
River Rch & RM= Kings Creek 25,Reach-1,10847
    1080    1512    1877    1154    2302    4593    3466
River Rch & RM= Kings Creek 25,Reach-1,9830
    1136    1588    1967    1206    2406    4802    3606
River Rch & RM= Kings Creek 25,Reach-1,1377
    1263    1772    2202    1353    2700    5387    4065
Boundary for River Rch & Prof#=Kings Creek 25,Reach-1,1
Up Type=0
Dn Type=3
Dn Slope=0.005
Boundary for River Rch & Prof#=Kings Creek 25,Reach-1,2
Up Type=0
Dn Type=3
Dn Slope=0.005
Boundary for River Rch & Prof#=Kings Creek 25,Reach-1,3
Up Type=0
Dn Type=3
Dn Slope=0.005
Boundary for River Rch & Prof#=Kings Creek 25,Reach-1,4
Up Type=0
Dn Type=3
Dn Slope=0.005
Boundary for River Rch & Prof#=Kings Creek 25,Reach-1,5
Up Type=0
Dn Type=3
Dn Slope=0.005
Boundary for River Rch & Prof#=Kings Creek 25,Reach-1,6
Up Type=0
Dn Type=3
Dn Slope=0.005
Boundary for River Rch & Prof#=Kings Creek 25,Reach-1,7
Up Type=0
Dn Type=3
Dn Slope=0.005

--- Kings Creek 25.g01 (geometry) ---

Geom Title=Existing Conditions
Program Version=4.10

River Reach=Kings Creek 25  ,Reach-1
Reach XY= 30
        2635226.        6864711.      2635574.37      6864807.88
      2636100.02      6864438.33       2636134.1      6864263.48
      2636689.41      6864097.48      2637277.47      6863164.54
      2637896.03      6862961.06      2639550.88      6863061.52
       2640067.5      6862958.33      2640226.47      6862690.54
      2640078.49      6862469.15      2640371.04      6862355.89
        2640399.      6862137.15      2640841.72      6862361.25
      2640968.98      6862170.01      2641128.75       6862205.7
      2641252.16      6861883.56      2641618.38       6861717.5
      2641625.75      6861417.97      2641922.67      6861653.38
      2642186.64      6861511.56      2642303.63      6861587.61
       2642281.3      6862063.67      2642815.52       6862551.2
      2642905.11      6862891.17       2643122.6      6862912.21
        2642983.      6863110.78      2643086.48      6863371.56
      2643432.68      6863320.28        2643926.        6863811.

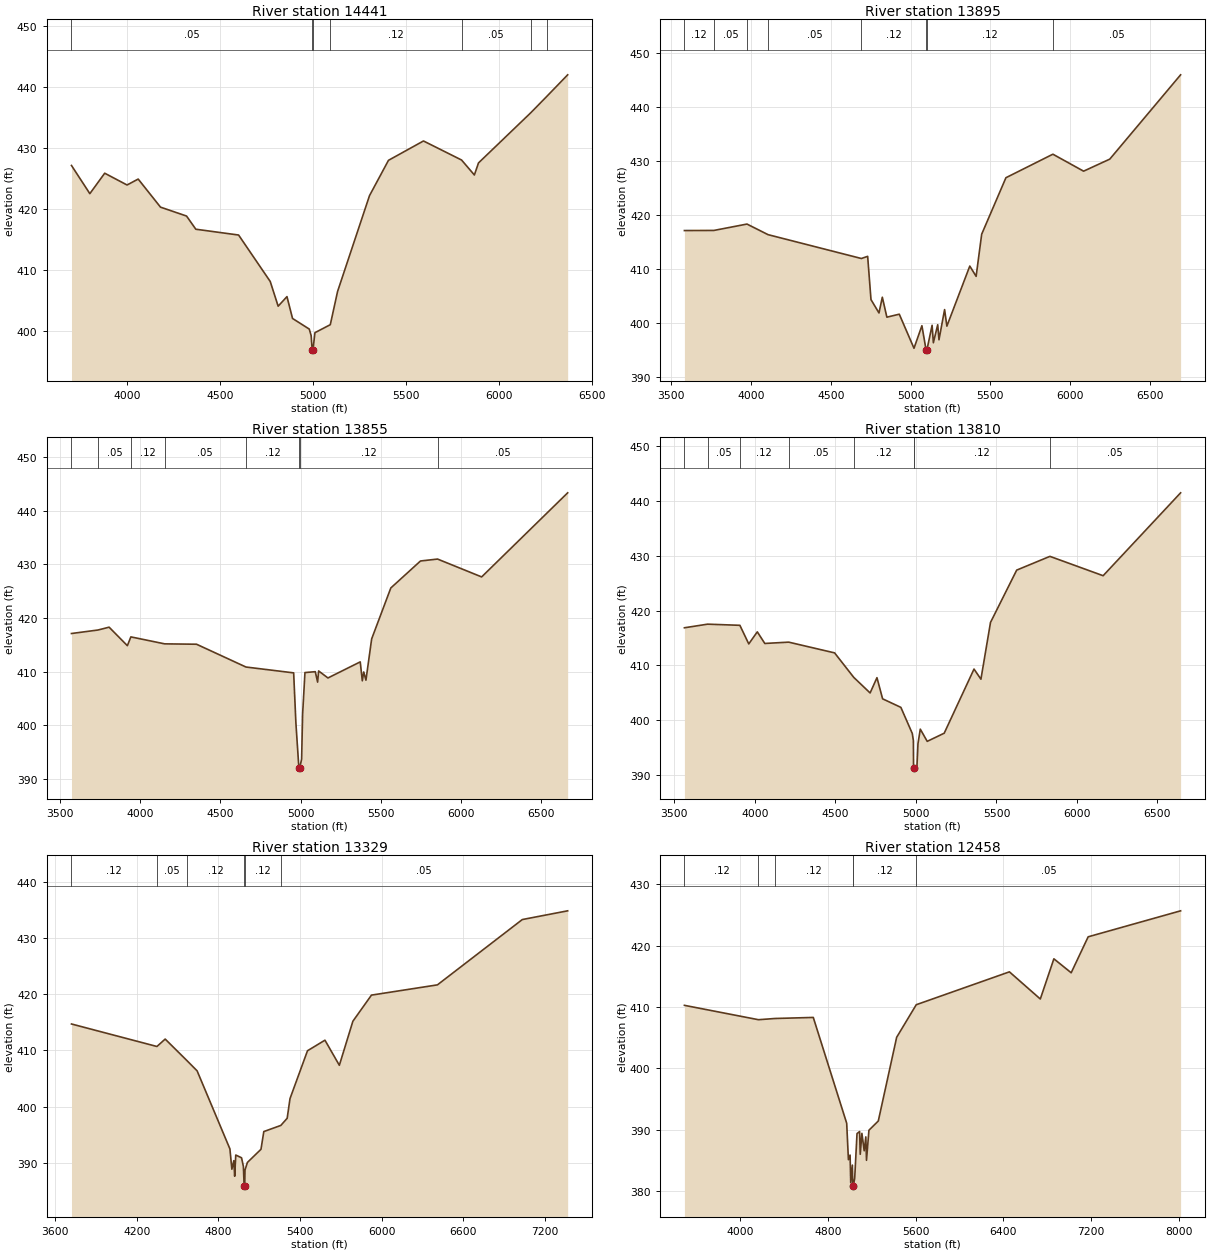
Type RM Length L Ch R = 1 ,14441   ,546,546,546
BEGIN DESCRIPTION:
Kings Creek 25 22.0
END DESCRIPTION:
XS GIS Cut Line= 4
      2635398.05      6866009.76      2635331.22      6864710.47
       2635220.1      6864360.42      2634310.81      6863936.08
#Sta/Elev= 30
    3699  427.09  3797.9  422.47    3878  425.82  3998.2  423.89  4058.2  424.86
  4178.4  420.26  4318.6   418.8  4368.6  416.64  4598.9  415.69  4769.2  408.08
  4811.9  404.03  4859.3   405.6  4889.3  402.02  4979.4  400.28  4989.5  399.21
  4995.2  396.84  4995.5  396.34  4999.2  396.84  5009.9  399.69  5092.6     401
  5131.8  406.44  5303.7  422.14  5405.9  427.93  5594.3   431.1  5799.5  427.98
  5868.4  425.53  5890.5   427.5  6172.9  435.75  6260.1  438.46  6370.7  441.94
#Mann= 7 ,-1 , 0
    3699     .05       0  4995.2     .03       0  4999.2     .05       0
  5092.6     .12       0  5799.5     .05       0  6172.9     .12       0
  6260.1     .05       0
Bank Sta=4995.2,4999.2
XS Rating Curve= 0 ,0
Exp/Cntr=0.3,0.1

Type RM Length L Ch R = 1 ,13895   ,40,40,40
BEGIN DESCRIPTION:
Mapping XS 28173ad6
END DESCRIPTION:
XS GIS Cut Line= 5
      2636455.35      6865829.18      2636038.68      6864856.95
      2635786.94      6864635.59       2635513.5      6864414.24
      2634280.92      6863823.99
#Sta/Elev= 30
  3581.6  417.13  3766.5  417.15    3974  418.33  4106.1  416.37  4691.2  411.96
  4730.6  412.36  4751.5  404.36  4801.7  401.89  4822.6   404.8  4851.1  401.11
  4928.9  401.66  5021.2  395.36  5070.8  399.53  5097.5  394.96  5097.8  394.46
  5101.5  394.96  5134.7  399.61  5142.7  396.38  5169.9  399.71  5177.9  396.93
  5213.1  402.51  5227.4  399.45  5371.1  410.56  5410.8  408.66  5445.6  416.45
  5597.7   426.9  5892.2  431.25  6084.7  428.11  6248.9  430.34    6693  445.93
#Mann= 8 ,-1 , 0
  3581.6     .12       0  3766.5     .05       0    3974     .12       0
  4106.1     .05       0  4691.2     .12       0  5097.5     .07       0
  5101.5     .12       0  5892.2     .05       0
Bank Sta=5097.5,5101.5
XS Rating Curve= 0 ,0
Exp/Cntr=0.3,0.1

Type RM Length L Ch R = 1 ,13855   ,45,45,45
BEGIN DESCRIPTION:
Mapping XS 3885a118
END DESCRIPTION:
XS GIS Cut Line= 6
      2636496.13      6865810.05       2636070.8      6864846.53
      2635966.63      6864759.73       2635801.7       6864594.8
      2635515.24      6864377.78      2634360.86      6863748.51
#Sta/Elev= 30
  3570.8  417.12  3736.1  417.77  3805.6   418.3  3919.6  414.85  3941.4  416.49
  4152.2  415.19  4351.2  415.12  4659.6  410.87  4957.2  409.78  4971.3  400.39
    4990  391.96  4990.3  391.46    4994  391.96  5006.9  393.69  5013.1  402.05
  5027.7  409.84  5092.2     410  5106.7  408.05    5113  410.14  5171.2  408.83
  5372.7  411.83  5385.6   408.3  5394.5  409.95  5408.3  408.42  5443.9  416.11
  5563.5  425.61  5748.6  430.64  5855.2     431  6130.3  427.67    6667  443.35
#Mann= 8 ,-1 , 0
  3570.8     .12       0  3736.1     .05       0  3941.4     .12       0
  4152.2     .05       0  4659.6     .12       0    4990     .07       0
    4994     .12       0  5855.2     .05       0
Bank Sta=4990,4994
XS Rating Curve= 0 ,0
Exp/Cntr=0.3,0.1

Type RM Length L Ch R = 1 ,13810   ,481,481,481
BEGIN DESCRIPTION:
Mapping XS 0635b4b0
END DESCRIPTION:
XS GIS Cut Line= 5
      2636526.53      6865791.43      2636127.22      6864836.55
      2635840.76      6864571.79      2635549.96      6864333.08
      2634430.61      6863712.66
#Sta/Elev= 30
  3562.4  416.88  3706.4  417.54  3906.8  417.33    3962  413.94    4015  416.14
  4061.5  414.02  4209.8  414.26    4495   412.3  4613.7  407.84  4715.5  404.99
    4758  407.78  4793.1  403.92  4906.5  402.36  4977.4   397.6  4984.2   396.3
  4985.3  391.23  4985.6  390.73  4989.3  391.23  5006.2  391.53  5012.7  395.73
  5027.1  398.39  5070.1  396.16  5175.6  397.65  5360.7  409.35  5403.6   407.5
  5463.1  417.86  5625.7   427.4    5832  429.91  6162.5  426.38  6643.5   441.5
#Mann= 8 ,-1 , 0
  3562.4     .12       0  3706.4     .05       0  3906.8     .12       0
  4209.8     .05       0  4613.7     .12       0  4985.3     .08       0
  4989.3     .12       0    5832     .05       0
Bank Sta=4985.3,4989.3
XS Rating Curve= 0 ,0
Exp/Cntr=0.3,0.1

Type RM Length L Ch R = 1 ,13329   ,871,871,871
BEGIN DESCRIPTION:
Mapping XS 86077eef
END DESCRIPTION:
XS GIS Cut Line= 4
       2636941.1      6865264.84      2636127.99      6864279.71
      2635150.66      6863513.49      2634056.01      6863247.65
#Sta/Elev= 30
  3720.6  414.68  4348.5  410.68  4409.1     412  4569.1  408.17  4643.7  406.35
  4884.7  392.48    4899  388.87  4913.3  390.39  4919.8  387.62  4927.7  391.39
  4970.3   390.9  4983.7  389.36  4989.5  385.83  4989.8  385.33  4993.5  385.83
  4995.6  388.72  5013.2  390.07    5113  392.41  5133.8  395.56  5258.8  396.65
  5305.4  397.92  5326.3  401.42  5454.7  409.92    5583   411.8  5688.8  407.34
  5788.3  415.17  5924.8  419.81  6409.3  421.63  7033.1  433.24  7366.3  434.79
#Mann= 6 ,-1 , 0
  3720.6     .12       0  4348.5     .05       0  4569.1     .12       0
  4989.5     .07       0  4993.5     .12       0  5258.8     .05       0
Bank Sta=4989.5,4993.5
XS Rating Curve= 0 ,0
Exp/Cntr=0.3,0.1

Type RM Length L Ch R = 1 ,12458   ,584,584,584
BEGIN DESCRIPTION:
Mapping XS 4acf80cd
END DESCRIPTION:
XS GIS Cut Line= 4
      2637496.23      6865358.65      2636737.84      6864060.79
      2636440.73      6863622.95      2634049.59      6862904.04
#Sta/Elev= 30
    3489  410.27  4165.1  407.93  4316.5  408.13  4665.3   408.3  4970.3  391.08
    4986  385.15  5001.2   385.9  5007.2   381.4  5022.2  384.27  5026.2  380.86
  5026.5  380.36  5030.2  380.86  5043.2  382.11  5064.5   389.4    5088  389.73
    5094  386.03    5109  389.44    5130   386.6  5144.9  388.86    5151  385.05
  5173.2  389.94  5258.8  391.45  5426.4  405.07  5605.2  410.37  6455.6  415.72
  6737.6   411.3  6861.5  417.84  7019.5  415.57  7174.4  421.42  8018.2  425.65
#Mann= 6 ,-1 , 0
    3489     .12       0  4165.1     .05       0  4316.5     .12       0
  5026.2     .07       0  5030.2     .12       0  5605.2     .05       0
Bank Sta=5026.2,5030.2
XS Rating Curve= 0 ,0
Exp/Cntr=0.3,0.1

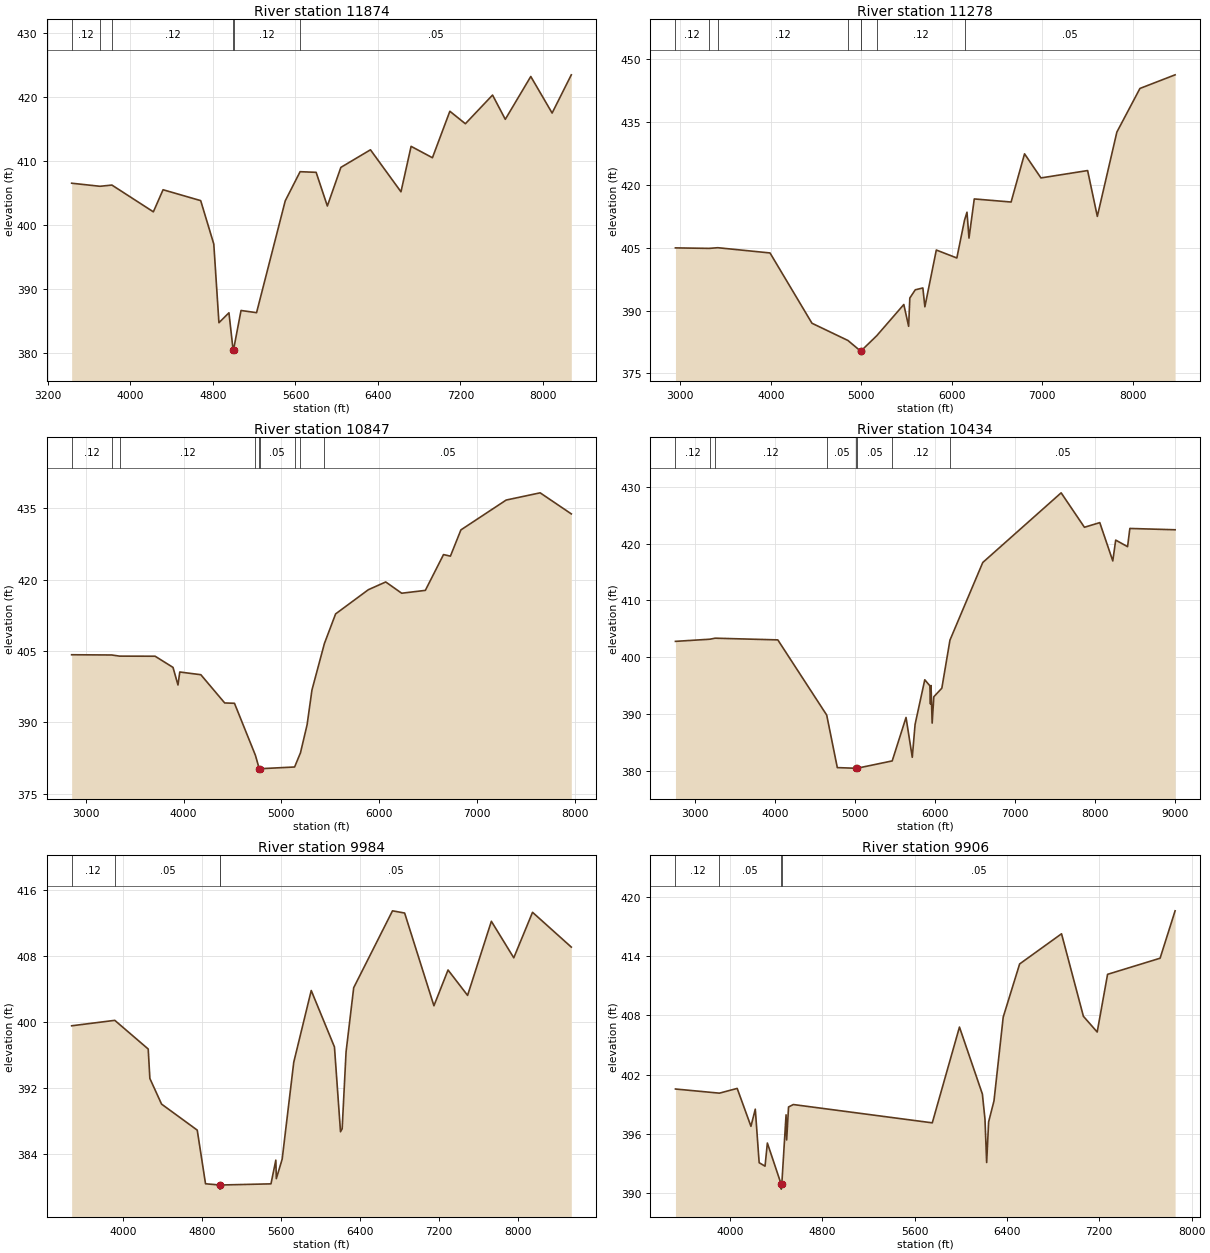
Type RM Length L Ch R = 1 ,11874   ,596,596,596
BEGIN DESCRIPTION:
Kings Creek 25 16.0
END DESCRIPTION:
XS GIS Cut Line= 3
      2637738.61      6865014.65       2637014.9      6863621.06
      2633884.02      6862661.25
#Sta/Elev= 30
  3429.7  406.53  3704.5  406.05  3820.2  406.24  4222.1  402.06  4316.2  405.51
    4681  403.81    4808  397.03  4857.9  384.74    4955  386.29  4995.2  380.49
  4995.5  379.99  4999.2  380.49  5072.1  386.65  5222.8  386.31  5500.9  403.78
    5645  408.33  5800.5  408.23  5909.2  402.97  6040.2     409  6327.2  411.75
  6623.1  405.19  6721.3  412.29  6928.2  410.51  7097.2  417.77  7247.6  415.82
  7511.1   420.3  7634.6  416.51  7881.8   423.2  8088.7  417.49  8274.7  423.46
#Mann= 6 ,-1 , 0
  3429.7     .12       0  3704.5     .05       0  3820.2     .12       0
  4995.2     .07       0  4999.2     .12       0    5645     .05       0
Bank Sta=4995.2,4999.2
XS Rating Curve= 0 ,0
Exp/Cntr=0.3,0.1

Type RM Length L Ch R = 1 ,11278   ,431,431,431
BEGIN DESCRIPTION:
Kings Creek 25 15.0
END DESCRIPTION:
XS GIS Cut Line= 3
      2637894.99       6865124.1        2637276.        6863161.
      2634150.41      6861668.55
#Sta/Elev= 30
  2945.5  404.95  3317.6  404.83  3413.4  404.99  3990.8  403.74  4454.3  386.97
  4851.7  382.86  4991.2  380.34  4991.6  379.84  4995.5  380.34  5169.9  383.99
  5469.3  391.44  5522.6  386.24  5535.8  392.99  5596.2  394.95  5679.8  395.39
    5702  390.89  5828.6  404.44  6055.4  402.54    6140  411.54  6167.4  413.46
  6189.6  407.28    6248  416.63    6655  415.89  6803.5  427.39    6985  421.64
  7500.7   423.4    7608  412.47  7823.9  432.58  8078.9  442.99  8467.5  446.24
#Mann= 8 ,-1 , 0
  2945.5     .12       0  3317.6     .05       0  3413.4     .12       0
  4851.7      .1       0  4991.2     .07       0  4995.5      .1       0
  5169.9     .12       0    6140     .05       0
Bank Sta=4991.2,4995.5
XS Rating Curve= 0 ,0
Exp/Cntr=0.3,0.1

Type RM Length L Ch R = 1 ,10847   ,413,413,413
BEGIN DESCRIPTION:
Kings Creek 25 14.0
END DESCRIPTION:
XS GIS Cut Line= 3
      2638059.18      6865170.99        2637676.        6863061.
      2635354.68       6861215.4
#Sta/Elev= 30
  2855.5   404.2  3265.8  404.15  3345.7  403.91  3709.2  403.89  3892.2  401.54
    3943  397.84  3961.4  400.57  4176.8     400  4420.7  394.06  4520.8  393.99
  4735.1  383.04  4774.2  380.22  4774.6  379.72  4778.7  380.22  5135.8  380.59
  5195.6  383.56  5263.5  389.47  5313.2  396.78  5440.5  406.56  5555.1  412.79
  5889.9  417.88  6067.7  419.51    6231  417.14  6472.9  417.74  6658.8  425.27
  6729.2  424.94  6836.6  430.46  7299.5  436.74  7647.1  438.26  7965.6  433.83
#Mann= 9 ,-1 , 0
  2855.5     .12       0  3265.8     .05       0  3345.7     .12       0
  4735.1     .05       0  4774.2     .03       0  4778.7     .05       0
  5135.8      .1       0  5195.6     .12       0  5440.5     .05       0
Bank Sta=4774.2,4778.7
XS Rating Curve= 0 ,0
Exp/Cntr=0.3,0.1

Type RM Length L Ch R = 1 ,10434   ,450,450,450
BEGIN DESCRIPTION:
Kings Creek 25 13.0
END DESCRIPTION:
XS GIS Cut Line= 3
      2638262.47      6865194.49      2638035.73      6862723.81
      2635159.74       6860301.1
#Sta/Elev= 30
  2757.1  402.77  3188.2  403.15  3252.8  403.33  4035.9  403.03  4646.5  389.78
  4779.1  380.52  5017.3   380.4  5018.1   379.9  5022.8   380.4  5464.8   381.7
  5637.5  389.36  5715.5  382.34  5750.6  388.14  5871.6     396  5935.3  394.94
    5943  391.72  5949.6  394.99  5963.9  388.36  5984.7  393.01  6084.8  394.52
  6186.2  402.99  6595.9  416.67  7575.1  428.95  7865.9  422.88  8057.6   423.7
  8220.2  416.95  8256.6  420.62  8404.9  419.46  8433.5  422.67  8998.6  422.44
#Mann= 8 ,-1 , 0
  2757.1     .12       0  3188.2     .05       0  3252.8     .12       0
  4646.5     .05       0  5017.3     .03       0  5022.8     .05       0
  5464.8     .12       0  6186.2     .05       0
Bank Sta=5017.3,5022.8
XS Rating Curve= 0 ,0
Exp/Cntr=0.3,0.1

Type RM Length L Ch R = 1 ,9984    ,78,78,78
BEGIN DESCRIPTION:
Mapping XS 8394e88b
END DESCRIPTION:
XS GIS Cut Line= 5
      2638841.04      6864443.88      2638504.85      6862950.55
      2638379.75      6862239.05      2637840.26      6860737.88
      2636792.53        6860128.
#Sta/Elev= 30
    3480  399.57    3917  400.23  4255.5  396.75  4272.2  393.18  4390.5  390.07
    4752  386.91    4836   380.4  4980.9  380.25  4981.7  379.75  4986.4  380.25
  5498.8  380.39    5548  383.27  5553.1  381.02  5612.4   383.4  5729.6  395.15
  5906.6  403.85  6141.8     397  6203.2  386.71  6219.8  387.07  6259.3  396.39
  6336.7  404.19  6729.7  413.52  6852.6  413.25  7149.2     402  7292.2  406.34
  7490.2  403.26    7731  412.25    7958  407.82    8148  413.34  8540.6  409.12
#Mann= 4 ,-1 , 0
    3480     .12       0    3917     .05       0  4980.9     .03       0
  4986.4     .05       0
Bank Sta=4980.9,4986.4
XS Rating Curve= 0 ,0
Exp/Cntr=0.3,0.1

Type RM Length L Ch R = 1 ,9906    ,76,76,76
BEGIN DESCRIPTION:
Kings Creek 25 500.0
END DESCRIPTION:
XS GIS Cut Line= 6
      2638880.08      6864403.85      2638695.62      6863429.48
      2638643.54      6863247.19      2638454.74      6862363.95
      2638396.14       6862127.4      2637768.97      6860226.36
#Sta/Elev= 30
  3526.6  400.56  3907.5  400.14  4061.6  400.62  4180.9  396.79  4218.5  398.52
  4252.1  393.11    4303  392.76  4323.2   395.1  4442.7  390.94  4443.5  390.44
  4448.2  390.94  4485.2  397.95  4490.3  395.41  4506.6  398.74  4547.9  398.99
  5752.3  397.14  5987.9  406.82  6186.5  400.05    6209  397.51  6223.5  393.13
  6240.6  397.24  6287.1  399.36    6367  407.83  6509.3   413.2  6872.4  416.25
  7061.9  407.91  7181.4  406.32  7271.4  412.15  7726.5  413.78  7856.6  418.57
#Mann= 4 ,-1 , 0
  3526.6     .12       0  3907.5     .05       0  4442.7     .03       0
  4448.2     .05       0
Bank Sta=4442.7,4448.2
XS Rating Curve= 0 ,0
Exp/Cntr=0.3,0.1

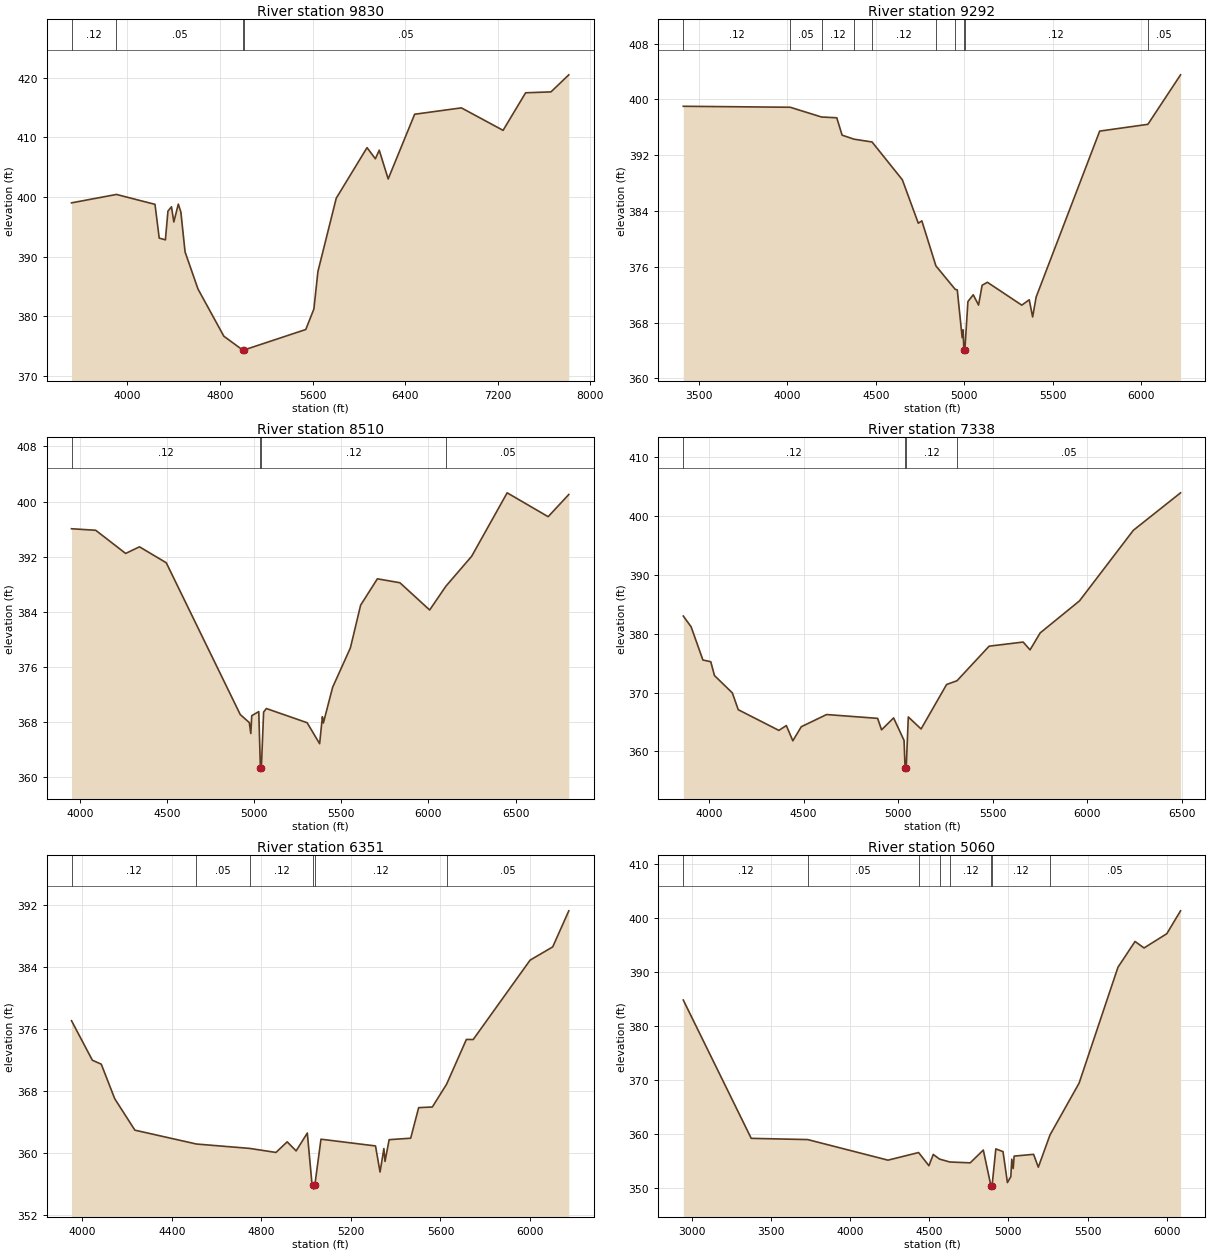
Type RM Length L Ch R = 1 ,9830    ,538,538,538
BEGIN DESCRIPTION:
Mapping XS 88e6744b
END DESCRIPTION:
XS GIS Cut Line= 5
      2638927.05      6864420.45      2638669.04      6863005.28
      2638598.59      6862581.69      2638520.49      6862332.88
      2637910.64      6860253.14
#Sta/Elev= 30
  3516.6  399.02  3904.7  400.43  4237.7  398.77  4274.2  393.11  4327.5  392.82
  4349.6  397.63  4380.1  398.36  4400.4  395.81  4439.2  398.81  4461.4  397.46
  4497.6  390.79  4609.2  384.57  4832.5  376.66  4996.8  374.32  4997.6  373.82
  5002.3  374.32  5540.3  377.78  5610.4  381.22  5645.3  387.51  5803.6   399.8
  6069.6  408.28  6141.6  406.41    6175  407.85  6252.2  403.03  6480.9  413.88
  6884.7  414.95  7244.8  411.18  7439.7  417.48  7658.5  417.63  7812.6  420.49
#Mann= 4 ,-1 , 0
  3516.6     .12       0  3904.7     .05       0  4996.8     .03       0
  5002.3     .05       0
Bank Sta=4996.8,5002.3
XS Rating Curve= 0 ,0
Exp/Cntr=0.3,0.1

Type RM Length L Ch R = 1 ,9292    ,782,782,782
BEGIN DESCRIPTION:
Kings Creek 25 11.0
END DESCRIPTION:
XS GIS Cut Line= 3
      2639200.71      6864647.17      2639145.98      6862911.45
      2638919.47      6861864.86
#Sta/Elev= 30
  3413.6  399.02  4017.2  398.88  4194.1  397.48  4280.2  397.37  4310.2  394.88
  4377.8   394.3  4479.4   393.9  4650.4  388.48  4740.4  382.25  4760.4  382.59
  4839.9  376.13    4949  372.76  4960.5  372.69  4988.1  365.84  4993.1  366.96
  4997.8  364.12  4998.6  363.62  5003.3  364.12  5020.6  371.02  5050.6  371.99
  5080.6  370.51  5100.6  373.35  5130.6  373.78  5324.6   370.5  5366.7  371.27
    5386  368.81  5405.7  371.66  5764.5  395.46  6036.5  396.43    6221  403.53
#Mann= 10 ,-1 , 0
  3413.6     .12       0  4017.2     .05       0  4194.1     .12       0
  4377.8     .05       0  4479.4     .12       0  4839.9     .05       0
    4949     .12       0  4997.8     .07       0  5003.3     .12       0
  6036.5     .05       0
Bank Sta=4997.8,5003.3
XS Rating Curve= 0 ,0
Exp/Cntr=0.3,0.1

Type RM Length L Ch R = 1 ,8510    ,1172,1172,1172
BEGIN DESCRIPTION:
Kings Creek 25 9.0
END DESCRIPTION:
XS GIS Cut Line= 3
      2640052.95      6863974.82        2639776.        6862961.
      2638872.35       6861402.5
#Sta/Elev= 30
  3953.2  396.05  4091.9  395.83  4263.6  392.47    4343  393.43  4496.6  391.12
  4921.2   369.1  4973.1  367.94  4981.7  366.35  4986.9  368.94  5027.3  369.53
  5036.6   361.4  5037.4   360.9  5042.2   361.4  5055.1  369.46  5070.8  369.98
  5304.7  367.92  5376.4  364.88  5392.2  368.79  5397.9  367.88    5451  373.06
  5552.8  378.77  5611.6  384.97  5707.7  388.79  5836.9  388.22  6007.5  384.27
  6100.5  387.71  6248.5  392.06  6452.2  401.26  6687.4   397.8  6805.7  401.02
#Mann= 4 ,-1 , 0
  3953.2     .12       0  5036.6     .07       0  5042.2     .12       0
  6100.5     .05       0
Bank Sta=5036.6,5042.2
XS Rating Curve= 0 ,0
Exp/Cntr=0.3,0.1

Type RM Length L Ch R = 1 ,7338    ,987,987,987
BEGIN DESCRIPTION:
Kings Creek 25 7.0
END DESCRIPTION:
XS GIS Cut Line= 3
      2640575.99      6863460.97      2640273.65      6862366.57
      2639615.11       6861027.2
#Sta/Elev= 30
  3864.6     383  3906.1  381.16  3968.3  375.53  4009.8  375.24  4029.5  372.89
  4123.9  369.94  4155.1  367.09  4369.6  363.58  4409.2   364.4  4443.5  361.81
  4488.2   364.2  4621.9  366.27  4891.7  365.62  4912.4  363.67  4976.1   365.7
  5031.4  361.86  5036.7  357.16  5037.6  356.66  5042.6  357.16  5053.8  365.86
  5121.3  363.82  5256.1  371.37  5311.1  372.01  5480.9  377.88  5660.7  378.58
  5697.1  377.25  5750.6  380.13  5958.4  385.57  6243.1  397.56  6492.5  403.92
#Mann= 4 ,-1 , 0
  3864.6     .12       0  5036.7     .07       0  5042.6     .12       0
  5311.1     .05       0
Bank Sta=5036.7,5042.6
XS Rating Curve= 0 ,0
Exp/Cntr=0.3,0.1

Type RM Length L Ch R = 1 ,6351    ,1291,1291,1291
BEGIN DESCRIPTION:
Kings Creek 25 6.0
END DESCRIPTION:
XS GIS Cut Line= 3
      2640889.53      6863403.99      2640870.41      6862356.27
       2640670.8      6861200.28
#Sta/Elev= 30
  3952.1  377.09  4045.1  371.99  4085.1  371.47  4145.1  367.01  4235.1  362.95
  4509.7  361.16  4748.2  360.59  4865.2  360.07  4915.3  361.44  4955.3  360.27
  5005.3  362.58  5025.6  356.15  5032.8  355.83  5033.8  355.33  5038.7  355.83
  5066.2  361.78  5309.8  360.91  5330.1  357.54  5347.2  360.57  5352.3  358.91
  5370.7  361.72  5466.9  361.91  5502.6  365.86  5563.5  365.94  5627.2  368.88
  5715.7  374.67  5746.1  374.66  6000.3  384.92  6101.3  386.63  6173.1  391.29
#Mann= 6 ,-1 , 0
  3952.1     .12       0  4509.7     .05       0  4748.2     .12       0
  5032.8     .07       0  5038.7     .12       0  5627.2     .05       0
Bank Sta=5032.8,5038.7
XS Rating Curve= 0 ,0
Exp/Cntr=0.3,0.1

Type RM Length L Ch R = 1 ,5060    ,1160,1160,1160
BEGIN DESCRIPTION:
Kings Creek 25 5.0
END DESCRIPTION:
XS GIS Cut Line= 4
      2640928.65      6863568.18       2641718.3      6862113.95
      2641609.79      6861728.22      2641000.72      6860826.44
#Sta/Elev= 30
  2944.5  384.87    3374  359.24  3731.3  359.01  4238.5   355.2  4432.1  356.61
  4497.4  354.17  4524.9  356.26  4564.3   355.4  4629.2  354.86  4758.2   354.7
  4841.3  357.07  4890.2  350.33  4891.2  349.83  4896.2  350.33  4920.4  357.29
  4965.9  356.78  4993.7  351.04  5015.2  352.15  5021.3  355.39  5030.2  353.65
  5036.2  355.95  5159.1  356.28    5189   353.9  5262.9  359.87  5446.8  369.47
  5692.6  390.95  5800.5  395.72  5857.4  394.52  6001.3  397.16  6088.2   401.4
#Mann= 8 ,-1 , 0
  2944.5     .12       0  3731.3     .05       0  4432.1     .12       0
  4564.3     .05       0  4629.2     .12       0  4890.2     .07       0
  4896.2     .12       0  5262.9     .05       0
Bank Sta=4890.2,4896.2
XS Rating Curve= 0 ,0
Exp/Cntr=0.3,0.1

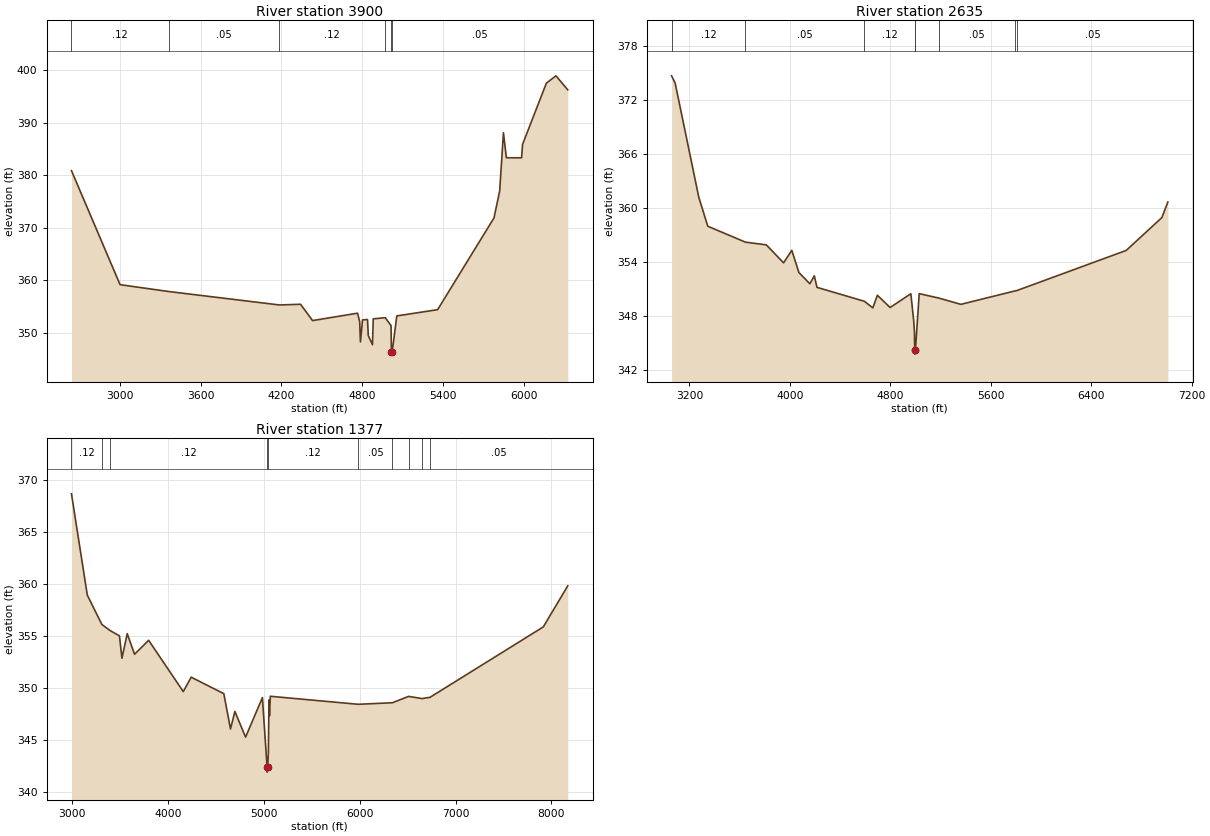
Type RM Length L Ch R = 1 ,3900    ,1265,1265,1265
BEGIN DESCRIPTION:
Kings Creek 25 4.0
END DESCRIPTION:
XS GIS Cut Line= 3
      2641038.09      6863560.39      2642328.16      6861410.28
      2641554.14      6860518.99
#Sta/Elev= 30
  2639.8  380.89  3000.9  359.14    3363  357.83  4184.8  355.27    4342   355.4
  4431.4  352.29  4765.7   353.7  4781.3  352.08  4787.1  348.22  4802.6  352.42
  4839.6  352.49  4845.4  349.42  4876.5  347.69  4882.3  352.62  4971.7  352.84
  5014.5  351.33  5017.3  346.39  5018.3  345.89  5023.4  346.39  5057.3  353.18
  5360.6  354.37  5779.4  371.87  5821.7  376.98  5849.7  388.13  5871.5  383.35
  5984.5  383.34  5992.1  385.92  6168.7  397.58    6240  398.98  6327.7  396.31
#Mann= 6 ,-1 , 0
  2639.8     .12       0    3363     .05       0  4184.8     .12       0
  4971.7     .05       0  5017.3     .05       0  5023.4     .05       0
Bank Sta=5017.3,5023.4
XS Rating Curve= 0 ,0
Exp/Cntr=0.3,0.1

Type RM Length L Ch R = 1 ,2635    ,1258,1258,1258
BEGIN DESCRIPTION:
Kings Creek 25 3.0
END DESCRIPTION:
XS GIS Cut Line= 3
      2641125.98      6863561.01        2642726.        6862461.
        2642926.      6860460.95
#Sta/Elev= 30
  3058.3  374.66  3086.7  373.86  3274.8  361.18  3346.5  357.95  3646.5  356.18
  3812.6  355.88    3950  353.88  4015.6  355.27  4072.5   352.8  4159.1  351.56
  4194.9  352.44  4215.9  351.16  4593.8  349.61    4661  348.88  4696.9  350.28
  4798.4  348.92  4963.6  350.45  4986.5   347.4  4992.5  346.09  4993.8  344.24
  4994.8  343.74  5000.1  344.24  5030.1  350.46  5188.6  349.96  5361.8  349.27
  5789.3  350.75    5807   350.8  6678.3  355.26  6962.2  358.91    7010  360.64
#Mann= 8 ,-1 , 0
  3058.3     .12       0  3646.5     .05       0  4593.8     .12       0
  4993.8     .07       0  5000.1     .12       0  5188.6     .05       0
  5789.3     .12       0    5807     .05       0
Bank Sta=4993.8,5000.1
XS Rating Curve= 0 ,0
Exp/Cntr=0.3,0.1

Type RM Length L Ch R = 1 ,1377    ,0,0,0
BEGIN DESCRIPTION:
Kings Creek 25 2.0
END DESCRIPTION:
XS GIS Cut Line= 4
      2641125.99        6863711.      2643196.02      6863177.29
      2643626.05      6862669.08      2642969.42      6860384.53
#Sta/Elev= 30
  2991.4  368.64  3156.6  358.92  3308.7   356.1  3394.1  355.52  3492.2  355.01
  3518.1  352.86  3573.5  355.22  3649.7  353.24  3796.9  354.58  4158.4  349.66
    4241  351.04  4581.8  349.46  4651.3  346.07  4697.1  347.75  4808.8  345.29
  4984.5  349.08  5032.9  342.43    5034  341.93  5039.4  342.43  5046.5  343.71
  5052.9  348.85  5058.1  347.33  5067.1  349.21  5984.9  348.44  6342.1  348.59
  6510.7   349.2  6650.3  348.99  6734.3  349.11  7916.7  355.87  8171.9  359.81
#Mann= 10 ,-1 , 0
  2991.4     .12       0  3308.7     .05       0  3394.1     .12       0
  5032.9     .07       0  5039.4     .12       0  5984.9     .05       0
  6342.1     .12       0  6510.7     .05       0  6650.3     .12       0
  6734.3     .05       0
Bank Sta=5032.9,5039.4
XS Rating Curve= 0 ,0
Exp/Cntr=0.3,0.1

Chan Stop Cuts=-1
Use User Specified Reach Order=0
Composite Channel Slope=5