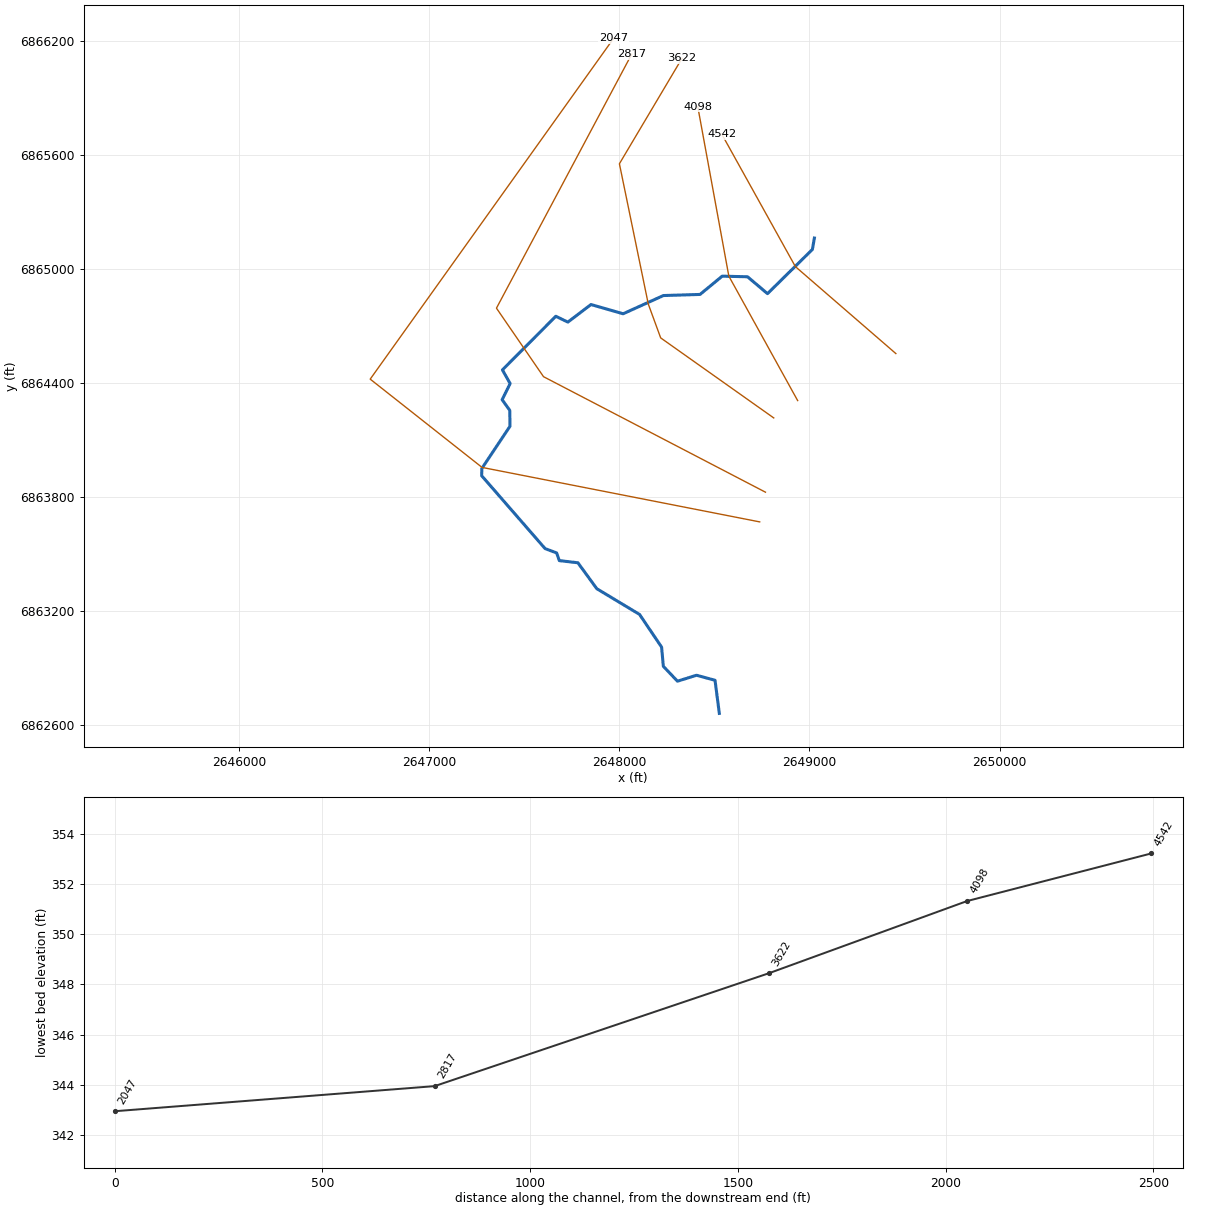
--- Kings Creek 26.prj (project) ---

Proj Title=Kings Creek 26 Base Level Engineering
Current Plan=p01
Default Exp/Contr=0.3,0.1
English Units
Geom File=g01
Flow File=f01
Plan File=p01
BEGIN DESCRIPTION:
Kings Creek 26
END DESCRIPTION:

--- Kings Creek 26.p01 (plan) ---

Plan Title=Multiple Run
Short Identifier=Multiple
Geom File=g01
Flow File=f01
Subcritical Flow
K Sum by GR= 0
Std Step Tol= 0.01
Critical Tol= 0.01
Num of Std Step Trials= 20
Max Error Tol= 0.3
Flow Tol Ratio= 0.001
Split Flow NTrial= 30
Split Flow Tol= 0.02
Split Flow Ratio= 0.02
Log Output Level= 0
Friction Slope Method= 1
Unsteady Friction Slope Method= 2
Unsteady Bridges Friction Slope Method= 1
Parabolic Critical Depth
Global Vel Dist=  1 , 1 , 1
Global Log Level= 0
CheckData=True
Encroach Param= -1, 0, 0, 0
BEGIN DESCRIPTION:
Multiple Run
END DESCRIPTION:

--- Kings Creek 26.f01 (steady flow) ---

Flow Title=Multiple
Number of Profiles=7
Profile Names=10-year,25-year,50-year,1pct_min,100-year,1pct_plu,500-year
River Rch & RM= Kings Creek 26,Reach-1,4542
     353     457     538     314     627    1250     850
River Rch & RM= Kings Creek 26,Reach-1,3622
     628     844    1017     608    1213    2419    1724
Boundary for River Rch & Prof#=Kings Creek 26,Reach-1,1
Up Type=0
Dn Type=3
Dn Slope=0.005
Boundary for River Rch & Prof#=Kings Creek 26,Reach-1,2
Up Type=0
Dn Type=3
Dn Slope=0.005
Boundary for River Rch & Prof#=Kings Creek 26,Reach-1,3
Up Type=0
Dn Type=3
Dn Slope=0.005
Boundary for River Rch & Prof#=Kings Creek 26,Reach-1,4
Up Type=0
Dn Type=3
Dn Slope=0.005
Boundary for River Rch & Prof#=Kings Creek 26,Reach-1,5
Up Type=0
Dn Type=3
Dn Slope=0.005
Boundary for River Rch & Prof#=Kings Creek 26,Reach-1,6
Up Type=0
Dn Type=3
Dn Slope=0.005
Boundary for River Rch & Prof#=Kings Creek 26,Reach-1,7
Up Type=0
Dn Type=3
Dn Slope=0.005

--- Kings Creek 26.g01 (geometry) ---

Geom Title=Existing Conditions

River Reach=Kings Creek 26,Reach-1
Reach XY= 30
      2649026.00      6865161.00      2649015.49      6865101.21
      2648779.34      6864868.60      2648674.53      6864957.45
      2648541.17      6864960.63      2648424.53      6864864.55
      2648231.94      6864858.74      2648019.88      6864762.82
      2647850.96      6864811.49      2647729.33      6864719.02
      2647666.00      6864749.76      2647385.15      6864467.73
      2647425.71      6864395.64      2647383.59      6864311.01
      2647423.64      6864255.10      2647425.05      6864171.49
      2647276.81      6863949.06      2647276.00      6863911.00
      2647609.51      6863527.70      2647670.20      6863504.95
      2647684.48      6863464.50      2647782.14      6863453.13
      2647881.62      6863316.62      2648106.37      6863181.47
      2648222.37      6863009.50      2648231.52      6862908.54
      2648305.92      6862830.27      2648405.94      6862861.54
      2648503.35      6862835.05      2648526.00      6862661.00

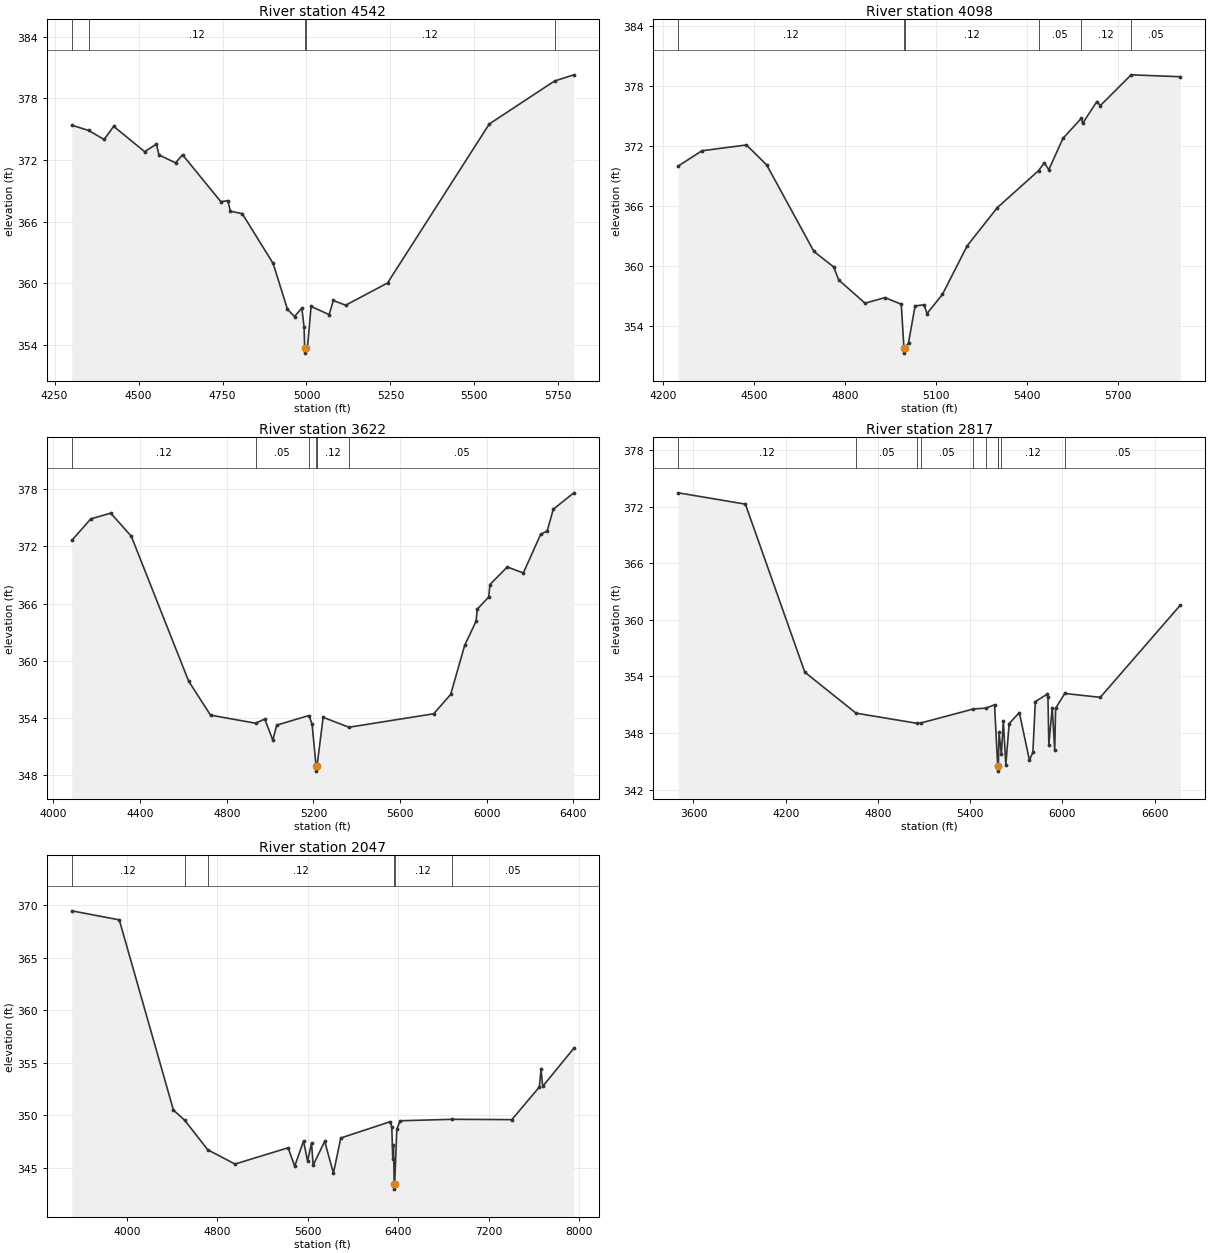
Type RM Length L Ch R = 1,4542,444,444,444
BEGIN DESCRIPTION:
Kings Creek 26 8.0
END DESCRIPTION:
XS GIS Cut Line= 3
      2649454.47      6864553.58      2648926.00      6865011.00
      2648539.25      6865707.03
#Sta/Elev= 30
  4301.1  375.39  4351.2  374.88  4397.4  374.00  4425.9  375.28  4518.0  372.82
  4553.1  373.54  4560.8  372.50  4610.1  371.73  4631.0  372.52  4745.0  367.95
  4765.9  368.05  4773.5  367.02  4808.7  366.79  4900.8  361.94  4943.5  357.48
  4964.4  356.78  4986.3  357.60  4992.9  355.75  4994.7  353.72  4995.0  353.22
  4998.7  353.72  5002.9  353.72  5013.8  357.76  5067.5  356.97  5080.1  358.34
  5116.7  357.88  5241.4  360.04  5544.5  375.51  5738.8  379.69  5796.3  380.29
#Mann=5,-1,0
  4301.1    0.05       0  4351.2    0.12       0  4994.7    0.07       0
  4998.7    0.12       0  5738.8    0.05       0
Bank Sta=4994.7,4998.7
Exp/Cntr=0.3,0.1

Type RM Length L Ch R = 1,4098,476,476,476
BEGIN DESCRIPTION:
Kings Creek 26 7.0
END DESCRIPTION:
XS GIS Cut Line= 3
      2648937.96      6864306.18      2648576.00      6864961.00
      2648412.77      6865851.36
#Sta/Elev= 30
  4251.3  370.02  4329.4  371.55  4476.0  372.13  4542.5  370.14  4698.2  361.48
  4763.5  359.93  4779.6  358.64  4866.6  356.31  4931.9  356.87  4985.8  356.21
  4994.6  351.82  4994.9  351.32  4998.6  351.82  5009.7  352.36  5031.2  356.04
  5060.5  356.15  5070.7  355.28  5121.5  357.20  5202.8  362.05  5302.0  365.86
  5437.8  369.56  5457.0  370.35  5471.6  369.65  5518.0  372.78  5579.0  374.80
  5582.9  374.28  5629.8  376.47  5641.2  376.06  5742.8  379.14  5904.7  378.95
#Mann=6,-1,0
  4251.3    0.12       0  4994.6    0.07       0  4998.6    0.12       0
  5437.8    0.05       0  5579.0    0.12       0  5742.8    0.05       0
Bank Sta=4994.6,4998.6
Exp/Cntr=0.3,0.1

Type RM Length L Ch R = 1,3622,805,805,805
BEGIN DESCRIPTION:
Mapping XS e4a6fccf
END DESCRIPTION:
XS GIS Cut Line= 5
      2648812.11      6864215.05      2648217.46      6864636.07
      2648152.35      6864814.02      2648000.44      6865551.87
      2648329.89      6866106.72
#Sta/Elev= 30
  4085.0  372.63  4172.7  374.89  4264.9  375.49  4359.7  373.07  4624.3  357.88
  4725.2  354.32  4933.3  353.47  4975.6  353.91  5012.6  351.70  5030.6  353.27
  5179.6  354.28  5194.0  353.35  5212.4  348.95  5212.7  348.45  5216.4  348.95
  5245.0  354.09  5363.9  353.05  5755.0  354.46  5833.4  356.49  5897.7  361.62
  5950.3  364.15  5956.2  365.43  6008.8  366.70  6014.6  368.01  6094.5  369.85
  6168.6  369.22  6248.4  373.26  6278.7  373.63  6306.9  375.90  6401.7  377.62
#Mann=6,-1,0
  4085.0    0.12       0  4933.3    0.05       0  5179.6    0.12       0
  5212.4    0.03       0  5216.4    0.12       0  5363.9    0.05       0
Bank Sta=5212.4,5216.4
Exp/Cntr=0.3,0.1

Type RM Length L Ch R = 1,2817,770,770,770
BEGIN DESCRIPTION:
Mapping XS 355d9473
END DESCRIPTION:
XS GIS Cut Line= 4
      2648768.65      6863824.45      2647601.14      6864432.08
      2647353.74      6864792.32      2648064.71      6866127.55
#Sta/Elev= 30
  3501.1  373.48  3937.9  372.28  4324.5  354.45  4657.7  350.10  5056.4  349.02
  5081.9  349.07  5420.2  350.54  5503.7  350.64  5558.7  350.99  5579.3  344.45
  5579.6  343.95  5583.3  344.45  5587.9  348.08  5603.0  345.72  5615.6  349.29
  5631.9  344.62  5653.8  349.00  5719.7  350.16  5785.6  345.12  5807.9  345.94
  5823.9  351.33  5898.5  352.09  5906.1  351.79  5911.8  346.77  5933.8  350.70
  5950.1  346.20  5955.7  350.62  6015.4  352.19  6246.3  351.78  6767.0  361.56
#Mann=10,-1,0
  3501.1    0.12       0  4657.7    0.05       0  5056.4    0.12       0
  5081.9    0.05       0  5420.2    0.12       0  5503.7    0.05       0
  5579.3    0.05       0  5583.3    0.05       0  5603.0    0.12       0
  6015.4    0.05       0
Bank Sta=5579.3,5583.3
Exp/Cntr=0.3,0.1

Type RM Length L Ch R = 1,2047,0,0,0
BEGIN DESCRIPTION:
Kings Creek 26 6.0
END DESCRIPTION:
XS GIS Cut Line= 4
      2648738.30      6863668.19      2647277.95      6863954.74
      2646689.68      6864419.06      2647970.07      6866211.60
#Sta/Elev= 30
  3511.8  369.46  3932.0  368.60  4410.9  350.48  4511.6  349.50  4714.2  346.70
  4955.4  345.34  5425.5  346.89  5483.2  345.13  5561.8  347.53  5597.1  345.63
  5632.3  347.33  5646.7  345.23  5748.6  347.50  5826.1  344.48  5891.2  347.82
  6329.4  349.38  6342.3  348.83  6350.9  345.81  6357.0  347.13  6363.6  343.45
  6363.9  342.95  6367.6  343.45  6386.5  348.63  6415.4  349.46  6874.6  349.60
  7404.0  349.57  7647.3  352.68  7662.1  354.39  7676.8  352.74  7952.3  356.37
#Mann=6,-1,0
  3511.8    0.12       0  4511.6    0.05       0  4714.2    0.12       0
  6363.6    0.07       0  6367.6    0.12       0  6874.6    0.05       0
Bank Sta=6363.6,6367.6
Exp/Cntr=0.3,0.1

Chan Stop Cuts=-1