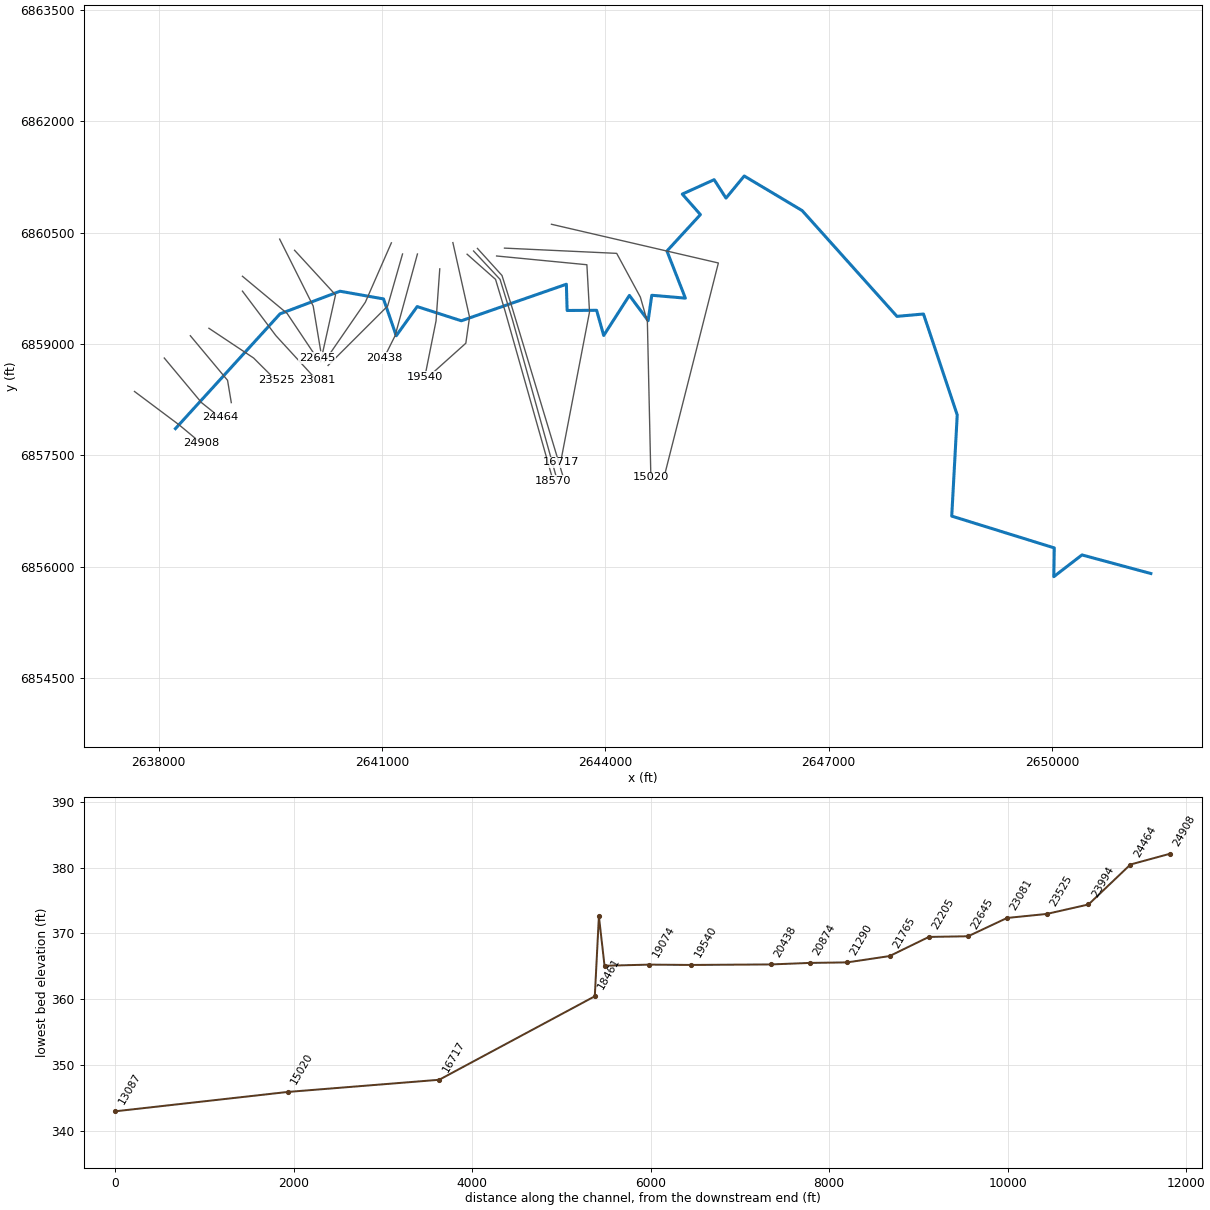
--- Kings Creek 27.prj (project) ---

Proj Title=Kings Creek 27 Base Level Engineering
Current Plan=p01
Default Exp/Contr=0.3,0.1
English Units
Geom File=g01
Flow File=f01
Plan File=p01
BEGIN DESCRIPTION:
Kings Creek 27
END DESCRIPTION:

--- Kings Creek 27.p01 (plan) ---

Plan Title=Multiple Run
Short Identifier=Multiple
Geom File=g01
Flow File=f01
Subcritical Flow
K Sum by GR= 0
Std Step Tol= 0.01
Critical Tol= 0.01
Num of Std Step Trials= 20
Max Error Tol= 0.3
Flow Tol Ratio= 0.001
Split Flow NTrial= 30
Split Flow Tol= 0.02
Split Flow Ratio= 0.02
Log Output Level= 0
Friction Slope Method= 1
Unsteady Friction Slope Method= 2
Unsteady Bridges Friction Slope Method= 1
Parabolic Critical Depth
Global Vel Dist=  1 , 1 , 1
Global Log Level= 0
CheckData=True
Encroach Param= -1, 0, 0, 0
BEGIN DESCRIPTION:
Multiple Run
END DESCRIPTION:

--- Kings Creek 27.f01 (steady flow) ---

Flow Title=Multiple
Number of Profiles=7
Profile Names=10-year,25-year,50-year,1pct_min,100-year,1pct_plu,500-year
River Rch & RM= Kings Creek 27,Reach-1,24908
     640     872    1063     643    1283    2559    1867
River Rch & RM= Kings Creek 27,Reach-1,23081
     766    1049    1282     777    1550    3092    2266
River Rch & RM= Kings Creek 27,Reach-1,19074
    1073    1497    1853    1136    2266    4521    3391
River Rch & RM= Kings Creek 27,Reach-1,18570
    1111    1555    1929    1184    2363    4715    3552
River Rch & RM= Kings Creek 27,Reach-1,18461
    1081    1506    1861    1139    2272    4533    3390
River Rch & RM= Kings Creek 27,Reach-1,13087
    1185    1646    2030    1238    2470    4928    3660
Boundary for River Rch & Prof#=Kings Creek 27,Reach-1,1
Up Type=0
Dn Type=3
Dn Slope=0.005
Boundary for River Rch & Prof#=Kings Creek 27,Reach-1,2
Up Type=0
Dn Type=3
Dn Slope=0.005
Boundary for River Rch & Prof#=Kings Creek 27,Reach-1,3
Up Type=0
Dn Type=3
Dn Slope=0.005
Boundary for River Rch & Prof#=Kings Creek 27,Reach-1,4
Up Type=0
Dn Type=3
Dn Slope=0.005
Boundary for River Rch & Prof#=Kings Creek 27,Reach-1,5
Up Type=0
Dn Type=3
Dn Slope=0.005
Boundary for River Rch & Prof#=Kings Creek 27,Reach-1,6
Up Type=0
Dn Type=3
Dn Slope=0.005
Boundary for River Rch & Prof#=Kings Creek 27,Reach-1,7
Up Type=0
Dn Type=3
Dn Slope=0.005

--- Kings Creek 27.g01 (geometry) ---

Geom Title=Existing Conditions

River Reach=Kings Creek 27,Reach-1
Reach XY= 30
      2638226.00      6857861.00      2639631.10      6859405.89
      2640436.54      6859709.92      2641020.38      6859606.26
      2641191.22      6859110.83      2641472.56      6859503.23
      2642065.51      6859312.19      2643476.21      6859803.98
      2643486.32      6859450.82      2643882.57      6859453.31
      2643977.64      6859114.09      2644322.59      6859653.62
      2644574.57      6859313.98      2644623.25      6859655.58
      2645074.46      6859616.83      2644826.86      6860250.69
      2645276.37      6860740.95      2645033.20      6861017.08
      2645460.80      6861211.15      2645620.10      6860962.97
      2645864.87      6861260.65      2646643.21      6860794.73
      2647915.95      6859371.62      2648272.49      6859403.30
      2648725.49      6858045.79      2648651.84      6856683.71
      2650029.03      6856255.54      2650022.34      6855868.72
      2650400.87      6856161.30      2651326.00      6855911.00

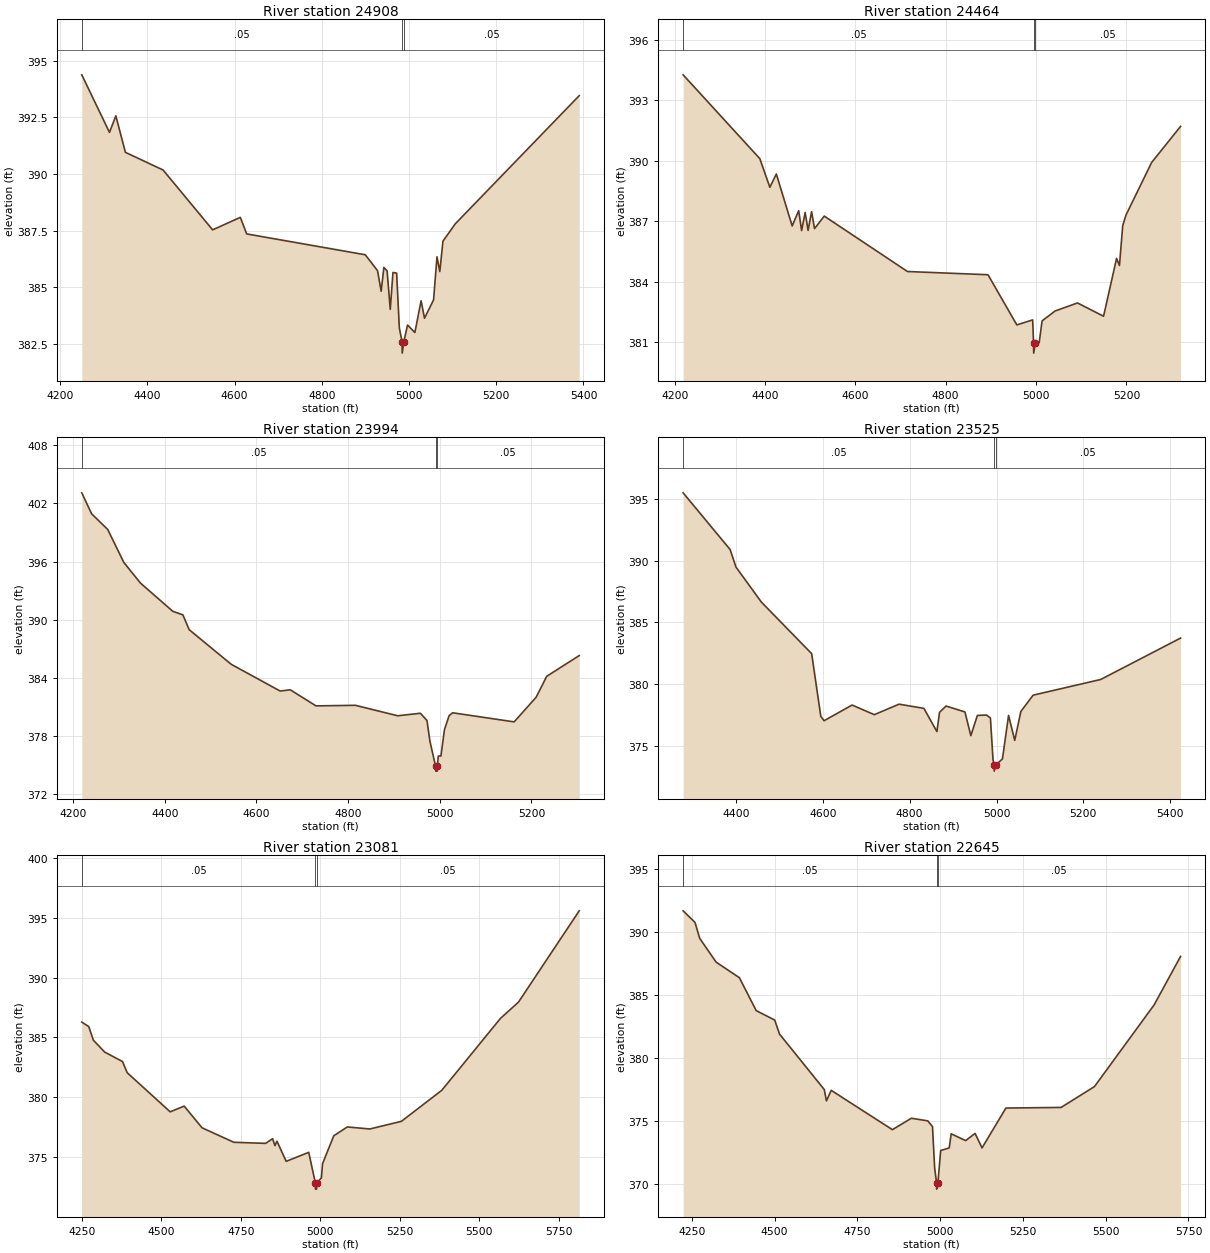
Type RM Length L Ch R = 1,24908,444,444,444
BEGIN DESCRIPTION:
Kings Creek 27 27.0
END DESCRIPTION:
XS GIS Cut Line= 3
      2637676.01      6858360.99      2638276.00      6857911.00
      2638576.00      6857661.00
#Sta/Elev= 30
  4249.7  394.38  4313.2  391.84  4327.8  392.57  4349.7  390.96  4436.1  390.18
  4549.7  387.54  4613.2  388.09  4627.8  387.36  4899.7  386.44  4927.8  385.74
  4936.1  384.83  4942.4  385.88  4949.7  385.73  4957.0  384.03  4963.2  385.66
  4971.6  385.63  4977.8  383.21  4984.1  382.60  4984.4  382.10  4988.1  382.60
  4996.6  383.34  5013.4  383.01  5027.7  384.41  5035.5  383.64  5056.3  384.45
  5064.1  386.35  5070.6  385.70  5077.8  387.04  5105.8  387.80  5390.2  393.46
#Mann=3,-1,0
  4249.7    0.05       0  4984.1    0.04       0  4988.1    0.05       0
Bank Sta=4984.1,4988.1
Exp/Cntr=0.3,0.1

Type RM Length L Ch R = 1,24464,470,470,470
BEGIN DESCRIPTION:
Kings Creek 27 26.0
END DESCRIPTION:
XS GIS Cut Line= 3
      2638076.02      6858810.97      2638576.00      6858211.00
      2638825.96      6858011.03
#Sta/Elev= 30
  4218.8  394.27  4388.6  390.11  4410.8  388.69  4425.1  389.35  4460.2  386.77
  4474.6  387.53  4481.1  386.54  4488.9  387.44  4495.4  386.55  4503.2  387.48
  4509.7  386.64  4531.2  387.26  4715.4  384.51  4893.7  384.35  4957.5  381.86
  4992.6  382.11  4994.5  380.96  4994.8  380.46  4998.5  380.96  5007.0  380.98
  5013.4  382.06  5042.2  382.55  5091.8  382.95  5149.5  382.29  5178.3  385.16
  5184.7  384.81  5191.9  386.78  5199.1  387.31  5255.9  389.92  5319.9  391.71
#Mann=3,-1,0
  4218.8    0.05       0  4994.5    0.04       0  4998.5    0.05       0
Bank Sta=4994.5,4998.5
Exp/Cntr=0.3,0.1

Type RM Length L Ch R = 1,23994,469,469,469
BEGIN DESCRIPTION:
Kings Creek 27 25.0
END DESCRIPTION:
XS GIS Cut Line= 3
      2638426.02      6859110.97      2638926.00      6858511.00
      2638976.00      6858211.02
#Sta/Elev= 30
  4219.0  403.10  4240.4  400.94  4275.6  399.32  4310.7  395.92  4347.2  393.78
  4417.5  390.88  4439.6  390.51  4453.3  388.98  4545.0  385.41  4651.8  382.65
  4673.9  382.78  4729.9  381.12  4815.8  381.18  4908.2  380.10  4957.7  380.36
  4972.0  379.61  4978.5  377.47  4990.8  374.89  4991.1  374.39  4994.6  374.39
  4994.8  374.89  4996.7  375.95  5002.5  375.95  5010.1  378.66  5020.3  380.11
  5027.9  380.41  5162.2  379.47  5210.3  382.02  5233.2  384.17  5304.1  386.31
#Mann=3,-1,0
  4219.0    0.05       0  4990.8    0.04       0  4994.8    0.05       0
Bank Sta=4990.8,4994.8
Exp/Cntr=0.3,0.1

Type RM Length L Ch R = 1,23525,444,444,444
BEGIN DESCRIPTION:
Kings Creek 27 24.0
END DESCRIPTION:
XS GIS Cut Line= 3
      2638675.98      6859211.02      2639276.00      6858811.00
      2639576.00      6858511.00
#Sta/Elev= 30
  4278.4  395.48  4386.6  390.89  4400.1  389.47  4458.7  386.63  4574.4  382.46
  4595.4  377.39  4602.9  377.03  4667.5  378.30  4718.6  377.52  4775.7  378.37
  4832.8  378.03  4862.8  376.15  4868.8  377.71  4883.9  378.22  4927.4  377.74
  4940.9  375.82  4956.0  377.46  4977.0  377.49  4986.0  377.26  4992.0  373.87
  4994.5  373.45  4994.8  372.95  4998.5  373.45  5013.7  373.94  5027.8  377.46
  5042.0  375.44  5056.1  377.78  5084.4  379.10  5240.0  380.37  5423.8  383.72
#Mann=3,-1,0
  4278.4    0.05       0  4994.5    0.04       0  4998.5    0.05       0
Bank Sta=4994.5,4998.5
Exp/Cntr=0.3,0.1

Type RM Length L Ch R = 1,23081,436,436,436
BEGIN DESCRIPTION:
Kings Creek 27 23.0
END DESCRIPTION:
XS GIS Cut Line= 3
      2639125.99      6859711.02      2639576.00      6859111.00
      2640126.03      6858510.97
#Sta/Elev= 30
  4249.7  386.28  4271.6  385.91  4286.2  384.77  4321.6  383.78  4377.8  382.99
  4392.4  382.06  4527.8  378.79  4571.6  379.27  4627.8  377.46  4727.8  376.25
  4827.8  376.16  4849.7  376.55  4857.0  375.97  4863.3  376.34  4892.4  374.66
  4963.3  375.41  4984.2  372.84  4984.4  372.34  4987.9  372.34  4988.2  372.84
  5003.1  373.28  5006.8  374.47  5042.0  376.79  5084.5  377.53  5155.4  377.36
  5254.7  378.00  5381.7  380.59  5566.1  386.59  5622.8  387.95  5813.7  395.57
#Mann=3,-1,0
  4249.7    0.05       0  4984.2    0.04       0  4988.2    0.05       0
Bank Sta=4984.2,4988.2
Exp/Cntr=0.3,0.1

Type RM Length L Ch R = 1,22645,440,440,440
BEGIN DESCRIPTION:
Kings Creek 27 22.0
END DESCRIPTION:
XS GIS Cut Line= 3
      2639125.98      6859911.01      2639726.00      6859411.00
      2640126.02      6858810.97
#Sta/Elev= 30
  4223.9  391.70  4259.7  390.78  4274.0  389.51  4323.5  387.62  4393.8  386.38
  4444.6  383.76  4500.5  383.01  4514.9  381.90  4650.2  377.48  4656.7  376.58
  4671.1  377.42  4855.9  374.29  4913.2  375.20  4962.6  374.99  4977.0  374.54
  4983.5  371.24  4989.3  370.06  4989.5  369.56  4993.3  370.06  5001.7  372.63
  5027.5  372.84  5033.5  373.96  5077.1  373.42  5105.6  373.99  5126.6  372.84
  5198.7  376.01  5365.5  376.06  5466.2  377.72  5646.4  384.22  5726.1  388.07
#Mann=3,-1,0
  4223.9    0.05       0  4989.3    0.04       0  4993.3    0.05       0
Bank Sta=4989.3,4993.3
Exp/Cntr=0.3,0.1

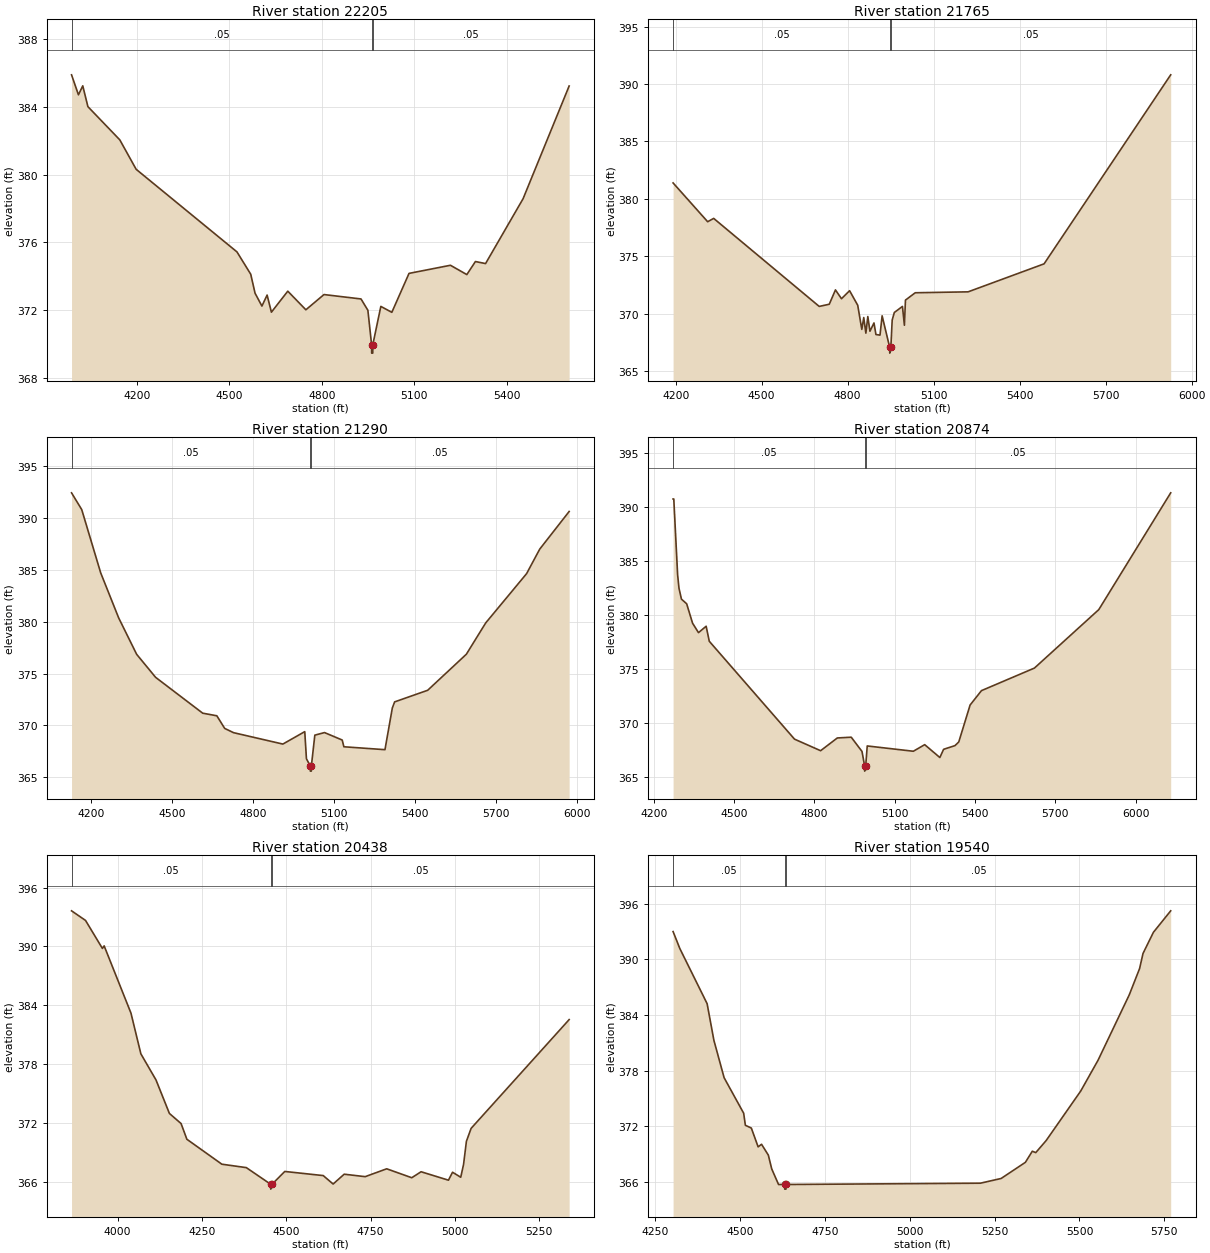
Type RM Length L Ch R = 1,22205,440,440,440
BEGIN DESCRIPTION:
Kings Creek 27 21.0
END DESCRIPTION:
XS GIS Cut Line= 3
      2639625.99      6860411.02      2640076.00      6859511.00
      2640176.00      6858911.02
#Sta/Elev= 30
  3987.9  385.90  4010.3  384.72  4024.3  385.25  4041.0  384.02  4144.4  382.06
  4197.5  380.32  4524.6  375.44  4569.3  374.12  4583.3  373.00  4605.6  372.24
  4622.4  372.89  4636.4  371.88  4689.5  373.12  4748.2  372.02  4806.9  372.92
  4927.1  372.66  4949.4  371.99  4961.4  369.96  4961.7  369.46  4965.2  369.46
  4965.4  369.96  4991.4  372.22  5027.1  371.87  5082.9  374.17  5217.2  374.65
  5270.4  374.10  5298.3  374.87  5331.2  374.75  5452.9  378.58  5602.4  385.24
#Mann=3,-1,0
  3987.9    0.05       0  4961.4    0.04       0  4965.4    0.05       0
Bank Sta=4961.4,4965.4
Exp/Cntr=0.3,0.1

Type RM Length L Ch R = 1,21765,475,475,475
BEGIN DESCRIPTION:
Kings Creek 27 20.0
END DESCRIPTION:
XS GIS Cut Line= 3
      2639825.97      6860261.03      2640376.00      6859661.00
      2640176.01      6858761.04
#Sta/Elev= 30
  4191.0  381.38  4311.6  378.00  4332.6  378.29  4700.7  370.62  4735.8  370.81
  4757.4  372.06  4778.4  371.29  4806.7  371.99  4835.1  370.72  4849.3  368.62
  4856.1  369.65  4863.5  368.29  4870.3  369.74  4877.7  368.46  4891.8  369.18
  4898.6  368.17  4912.8  368.12  4920.2  369.80  4946.6  367.05  4946.8  366.55
  4950.6  367.05  4955.3  369.43  4962.7  370.09  4991.1  370.62  4997.9  368.98
  5001.6  371.17  5035.7  371.81  5220.1  371.89  5485.2  374.33  5926.9  390.80
#Mann=3,-1,0
  4191.0    0.05       0  4946.6    0.03       0  4950.6    0.05       0
Bank Sta=4946.6,4950.6
Exp/Cntr=0.3,0.1

Type RM Length L Ch R = 1,21290,416,416,416
BEGIN DESCRIPTION:
Kings Creek 27 19.0
END DESCRIPTION:
XS GIS Cut Line= 3
      2641126.01      6860361.02      2640776.00      6859561.00
      2640225.98      6858760.97
#Sta/Elev= 30
  4126.5  392.44  4164.3  390.82  4234.5  384.72  4301.2  380.37  4367.8  376.86
  4438.0  374.64  4612.6  371.18  4664.9  370.93  4694.1  369.71  4726.9  369.30
  4909.7  368.20  4990.8  369.40  4997.0  366.78  5011.2  366.09  5011.5  365.59
  5015.0  365.59  5015.3  366.09  5028.1  369.06  5064.0  369.31  5129.6  368.59
  5135.7  367.94  5288.0  367.66  5315.3  371.68  5323.8  372.27  5446.3  373.39
  5589.7  376.87  5661.4  379.89  5812.8  384.64  5861.6  387.01  5970.6  390.64
#Mann=3,-1,0
  4126.5    0.05       0  5011.2    0.03       0  5015.3    0.05       0
Bank Sta=5011.2,5015.3
Exp/Cntr=0.3,0.1

Type RM Length L Ch R = 1,20874,436,436,436
BEGIN DESCRIPTION:
Kings Creek 27 18.0
END DESCRIPTION:
XS GIS Cut Line= 3
      2641275.99      6860210.97      2641076.00      6859511.00
      2640276.03      6858711.03
#Sta/Elev= 30
  4272.1  390.70  4274.7  390.70  4289.0  383.68  4294.2  382.43  4303.3  381.43
  4322.8  381.00  4344.9  379.20  4367.0  378.33  4395.6  378.92  4407.3  377.53
  4725.8  368.47  4823.3  367.40  4885.7  368.58  4937.7  368.65  4978.0  367.33
  4987.6  366.01  4987.9  365.51  4991.8  366.01  4997.5  367.84  5169.8  367.35
  5212.2  367.96  5268.8  366.77  5282.9  367.53  5325.3  367.87  5339.5  368.21
  5381.9  371.63  5424.3  372.96  5622.3  375.05  5862.7  380.46  6131.4  391.27
#Mann=3,-1,0
  4272.1    0.05       0  4987.6    0.03       0  4991.8    0.05       0
Bank Sta=4987.6,4991.8
Exp/Cntr=0.3,0.1

Type RM Length L Ch R = 1,20438,898,898,898
BEGIN DESCRIPTION:
Kings Creek 27 17.0
END DESCRIPTION:
XS GIS Cut Line= 3
      2641476.00      6860210.99      2641176.00      6859111.00
      2641025.99      6858810.98
#Sta/Elev= 30
  3863.2  393.63  3904.7  392.65  3954.7  389.80  3959.9  390.06  4039.4  383.21
  4068.8  379.06  4113.7  376.40  4153.4  372.99  4188.0  371.96  4205.2  370.36
  4308.9  367.82  4381.5  367.47  4453.6  365.78  4453.9  365.28  4457.9  365.78
  4495.5  367.08  4609.5  366.66  4638.9  365.80  4671.7  366.80  4733.9  366.55
  4797.8  367.35  4872.1  366.44  4899.7  367.05  4980.9  366.19  4993.0  367.00
  5017.3  366.49  5025.7  367.80  5034.1  370.15  5048.1  371.47  5338.8  382.55
#Mann=3,-1,0
  3863.2    0.05       0  4453.6    0.03       0  4457.9    0.05       0
Bank Sta=4453.6,4457.9
Exp/Cntr=0.3,0.1

Type RM Length L Ch R = 1,19540,466,466,466
BEGIN DESCRIPTION:
Kings Creek 27 16.0
END DESCRIPTION:
XS GIS Cut Line= 3
      2641776.00      6860011.00      2641726.00      6859311.00
      2641576.01      6858561.03
#Sta/Elev= 30
  4302.3  392.99  4322.3  391.15  4402.6  385.21  4422.6  381.25  4452.7  377.22
  4510.3  373.39  4515.3  372.09  4532.9  371.79  4552.9  369.76  4563.0  370.04
  4583.0  368.87  4593.0  367.38  4613.1  365.70  4630.9  365.70  4631.3  365.20
  4634.9  365.20  4635.3  365.70  5208.0  365.84  5269.2  366.35  5340.6  368.09
  5361.0  369.29  5371.2  369.14  5401.8  370.44  5503.8  375.79  5554.8  379.11
  5646.6  386.15  5677.2  389.00  5687.3  390.63  5717.9  392.91  5768.9  395.23
#Mann=3,-1,0
  4302.3    0.05       0  4630.9    0.03       0  4635.3    0.05       0
Bank Sta=4630.9,4635.3
Exp/Cntr=0.3,0.1

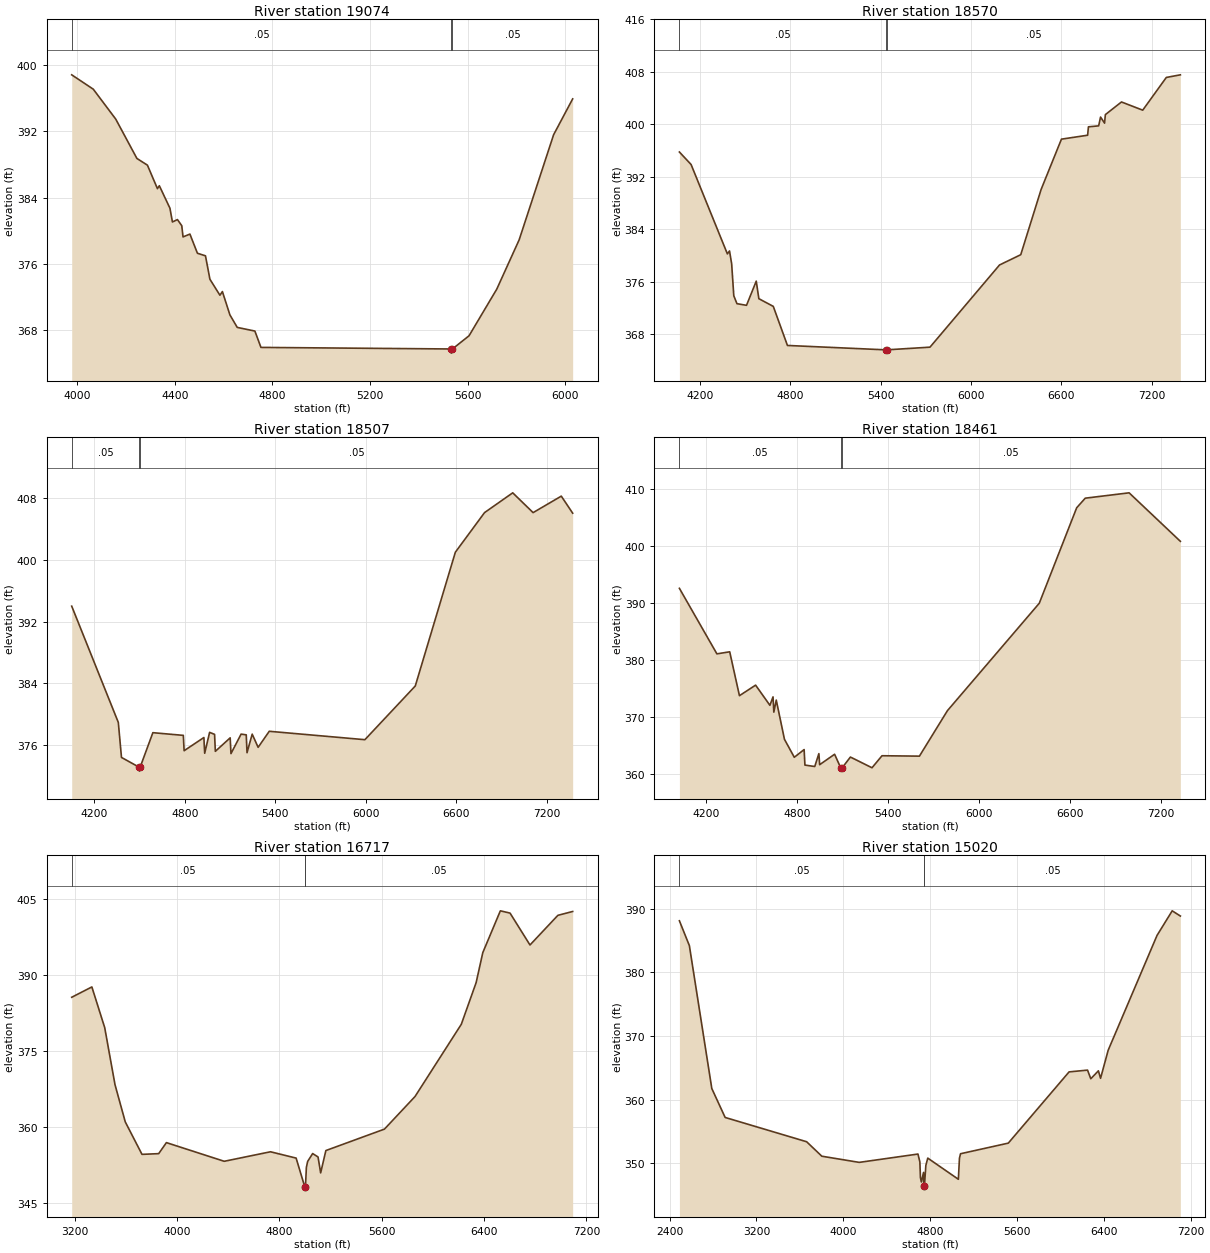
Type RM Length L Ch R = 1,19074,504,504,504
BEGIN DESCRIPTION:
Kings Creek 27 15.0
END DESCRIPTION:
XS GIS Cut Line= 4
      2641952.17      6860364.09      2642176.00      6859361.00
      2642125.78      6859009.92      2641626.00      6858561.00
#Sta/Elev= 30
  3976.9  398.80  4065.3  397.07  4157.3  393.47  4244.2  388.72  4287.4  387.91
  4328.4  385.08  4336.2  385.43  4379.7  382.72  4389.9  381.06  4410.4  381.35
  4428.2  380.61  4433.4  379.26  4461.6  379.60  4492.4  377.29  4525.4  376.98
  4543.6  374.16  4584.6  372.23  4594.8  372.67  4625.6  369.86  4655.7  368.35
  4728.0  367.91  4752.9  365.94  5532.2  365.75  5533.2  365.25  5538.0  365.75
  5606.1  367.34  5719.8  372.96  5811.7  378.91  5953.0  391.58  6031.1  395.90
#Mann=3,-1,0
  3976.9    0.05       0  5532.2    0.03       0  5538.0    0.05       0
Bank Sta=5532.2,5538
Exp/Cntr=0.3,0.1

Type RM Length L Ch R = 1,18570,63,63,63
BEGIN DESCRIPTION:
Mapping XS 7e419612
END DESCRIPTION:
XS GIS Cut Line= 4
      2642143.18      6860207.81      2642525.08      6859869.30
      2642655.29      6859435.27      2643297.67      6857160.92
#Sta/Elev= 30
  4063.4  395.75  4141.1  393.84  4382.0  380.21  4396.2  380.66  4410.4  378.69
  4424.6  373.82  4445.5  372.62  4509.1  372.37  4573.7  376.06  4591.0  373.38
  4686.8  372.21  4780.8  366.25  5433.7  365.58  5434.6  365.08  5439.5  365.58
  5727.5  365.99  6189.2  378.52  6330.2  380.09  6465.3  390.03  6600.4  397.71
  6774.4  398.31  6779.6  399.59  6847.6  399.74  6860.2  401.08  6886.8  400.15
  6892.0  401.45  6999.1  403.38  7140.2  402.13  7296.9  407.12  7390.2  407.52
#Mann=3,-1,0
  4063.4    0.05       0  5433.7    0.03       0  5439.5    0.05       0
Bank Sta=5433.7,5439.5
Exp/Cntr=0.3,0.1

Type RM Length L Ch R = 1,18507,46,46,46
BEGIN DESCRIPTION:
Mapping XS d9bc69a8
END DESCRIPTION:
XS GIS Cut Line= 4
      2642229.93      6860251.26      2642585.85      6859869.30
      2642750.78      6859331.10      2643349.73      6857178.36
#Sta/Elev= 30
  4051.0  394.01  4359.8  378.92  4380.8  374.38  4498.5  373.10  4499.4  372.60
  4504.3  373.10  4588.8  377.59  4790.6  377.24  4795.8  375.25  4926.8  376.96
  4932.1  374.92  4964.8  377.63  4997.6  377.37  5002.8  375.17  5101.0  376.92
  5106.3  374.87  5173.3  377.40  5207.5  377.31  5212.7  374.99  5246.9  377.40
  5286.3  375.69  5360.0  377.77  5993.7  376.68  6327.6  383.65  6593.1  401.01
  6786.5  406.15  6973.3  408.72  7108.3  406.15  7295.1  408.29  7370.5  406.08
#Mann=3,-1,0
  4051.0    0.05       0  4498.5    0.04       0  4504.3    0.05       0
Bank Sta=4498.5,4504.3
Exp/Cntr=0.3,0.1

Type RM Length L Ch R = 1,18461,1744,1744,1744
BEGIN DESCRIPTION:
Mapping XS e8f19319
END DESCRIPTION:
XS GIS Cut Line= 4
      2642282.06      6860285.93      2642611.89      6859921.38
      2642750.78      6859478.67      2643427.86      6857230.41
#Sta/Elev= 30
  4025.7  392.52  4272.9  381.02  4357.4  381.38  4421.6  373.68  4528.2  375.53
  4622.5  371.99  4643.1  373.47  4648.3  370.79  4664.4  372.91  4718.4  366.03
  4783.3  362.87  4848.1  364.22  4853.4  361.50  4918.2  361.25  4945.4  363.51
  4950.6  361.57  5049.1  363.40  5090.8  360.94  5091.7  360.44  5096.6  360.94
  5153.3  362.91  5295.8  361.03  5361.8  363.14  5608.5  363.07  5793.5  371.06
  6398.9  389.90  6645.6  406.66  6702.1  408.34  6991.3  409.28  7329.3  400.77
#Mann=3,-1,0
  4025.7    0.05       0  5090.8    0.04       0  5096.6    0.05       0
Bank Sta=5090.8,5096.6
Exp/Cntr=0.3,0.1

Type RM Length L Ch R = 1,16717,1697,1697,1697
BEGIN DESCRIPTION:
Mapping XS 6e2f7ae2
END DESCRIPTION:
XS GIS Cut Line= 4
      2642539.12      6860184.14      2643751.76      6860066.41
      2643787.08      6859430.67      2643398.60      6857405.87
#Sta/Elev= 30
  3175.5  385.66  3333.1  387.70  3433.6  379.65  3514.0  368.39  3594.3  361.03
  3725.0  354.62  3855.6  354.76  3915.8  356.94  4368.0  353.25  4729.8  355.13
  4930.1  353.88  4997.2  348.25  4998.2  347.75  5003.2  348.25  5010.2  352.03
  5020.2  353.22  5059.3  354.78  5101.5  354.10  5121.9  350.96  5162.6  355.37
  5620.8  359.61  5859.5  366.04  6221.6  380.32  6337.6  388.56  6389.6  394.48
  6527.0  402.74  6602.7  402.29  6758.6  395.99  6976.8  401.85  7092.3  402.61
#Mann=3,-1,0
  3175.5    0.05       0  4997.2    0.04       0  5003.2    0.05       0
Bank Sta=4997.2,5003.2
Exp/Cntr=0.3,0.1

Type RM Length L Ch R = 1,15020,1933,1933,1933
BEGIN DESCRIPTION:
Mapping XS 94cfae9d
END DESCRIPTION:
XS GIS Cut Line= 5
      2642645.10      6860290.09      2644152.04      6860219.46
      2644469.91      6859630.81      2644564.09      6859301.17
      2644611.18      6857205.81
#Sta/Elev= 30
  2489.7  388.13  2581.4  384.23  2788.3  361.73  2911.1  357.18  3661.9  353.36
  3802.0  351.08  4146.7  350.11  4687.9  351.42  4705.6  350.17  4710.8  347.71
  4719.1  347.03  4739.4  348.53  4741.6  346.40  4742.6  345.90  4747.6  346.40
  4760.7  349.64  4778.4  350.78  5060.3  347.45  5070.3  350.77  5080.3  351.47
  5520.4  353.14  6080.5  364.35  6250.6  364.63  6280.6  363.27  6350.6  364.52
  6370.6  363.34  6440.6  367.75  6890.8  385.82  7030.8  389.70  7106.0  388.88
#Mann=3,-1,0
  2489.7    0.05       0  4741.6    0.04       0  4747.6    0.05       0
Bank Sta=4741.6,4747.6
Exp/Cntr=0.3,0.1

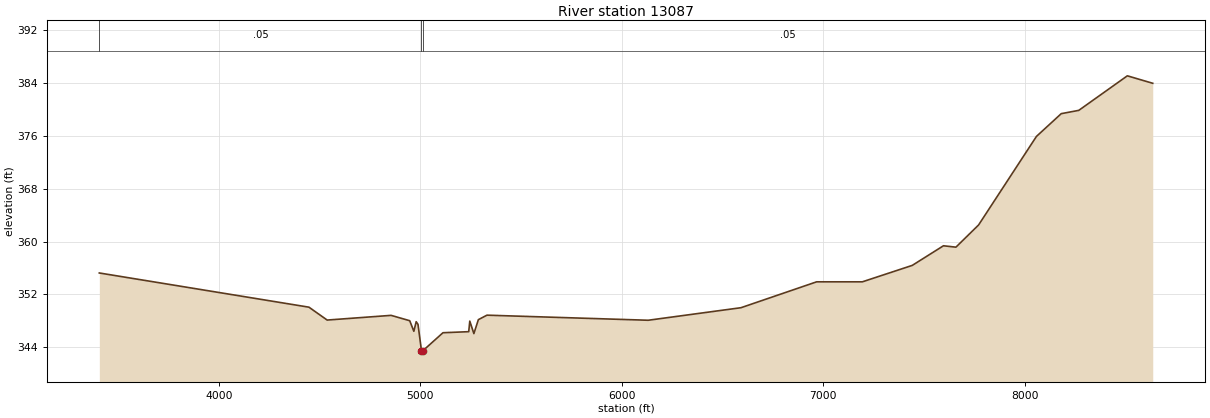
Type RM Length L Ch R = 1,13087,0,0,0
BEGIN DESCRIPTION:
Kings Creek 27 11.0
END DESCRIPTION:
XS GIS Cut Line= 3
      2643275.98      6860611.01      2645517.69      6860089.96
      2644799.97      6857254.35
#Sta/Elev= 30
  3407.8  355.25  4447.8  350.07  4538.2  348.12  4855.4  348.83  4947.8  348.02
  4968.3  346.42  4979.8  347.87  4988.9  347.47  5006.2  343.46  5007.3  342.96
  5012.6  343.46  5112.8  346.20  5240.6  346.36  5245.8  347.96  5266.1  346.07
  5288.4  348.18  5331.0  348.86  6131.1  348.09  6591.3  349.99  6966.7  353.91
  7193.6  353.91  7441.2  356.40  7595.9  359.37  7657.8  359.16  7770.2  362.52
  8057.2  375.93  8180.3  379.38  8267.4  379.88  8508.3  385.11  8634.3  383.98
#Mann=3,-1,0
  3407.8    0.05       0  5006.2    0.03       0  5012.6    0.05       0
Bank Sta=5006.2,5012.6
Exp/Cntr=0.3,0.1

Chan Stop Cuts=-1