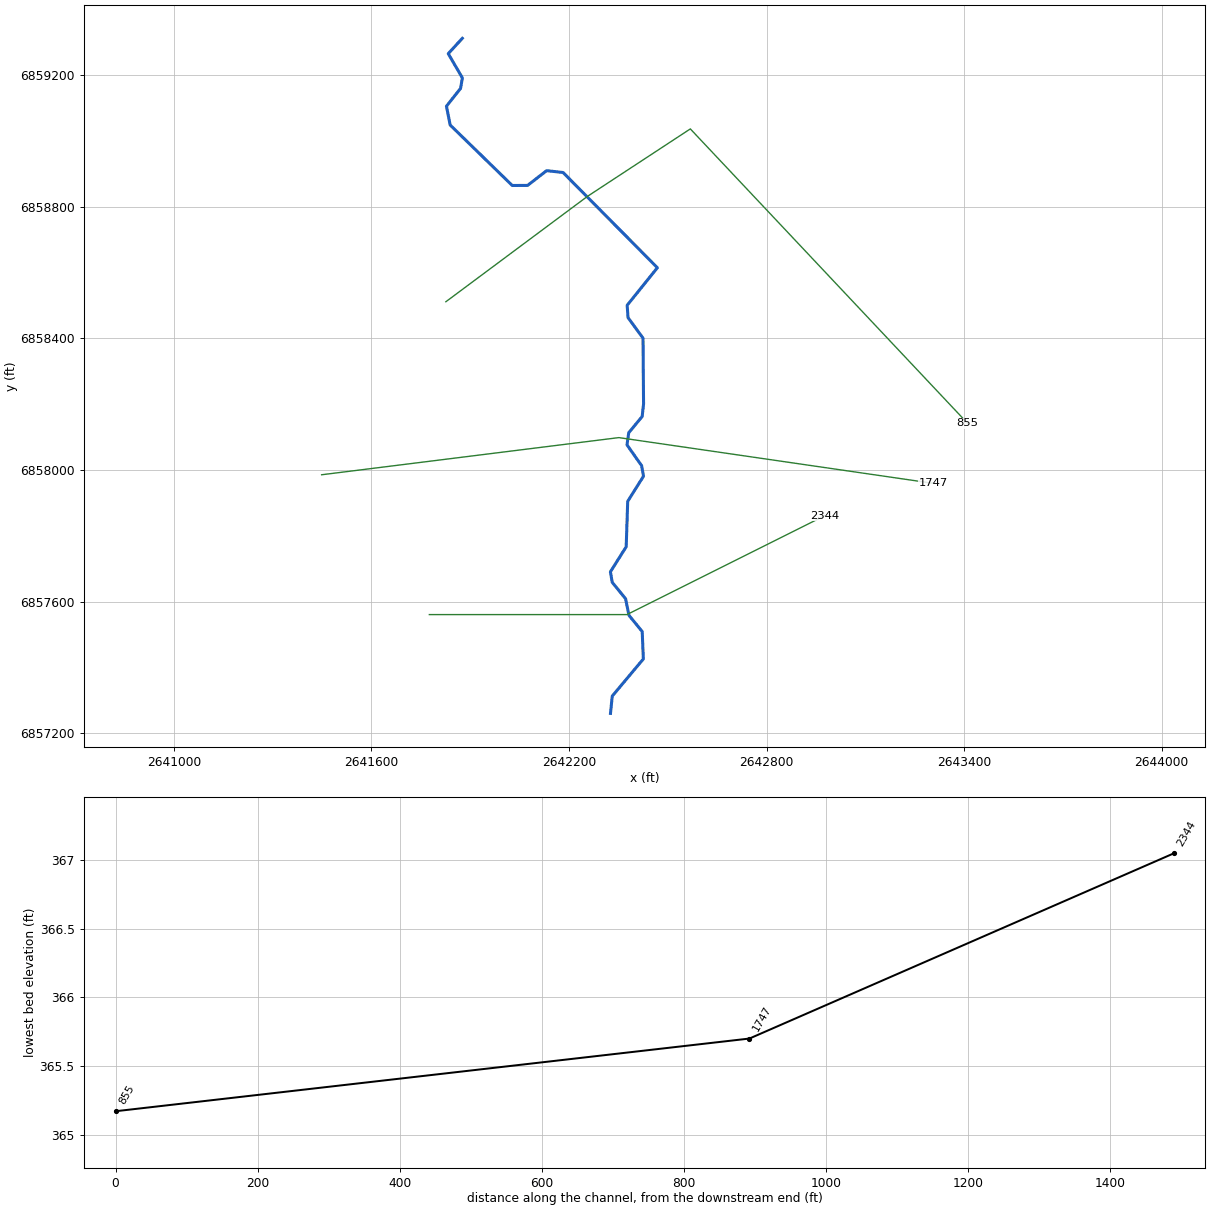
--- Kings Creek 27_1.prj (project) ---

Proj Title=Kings Creek 27_1 Base Level Engineering
Current Plan=p01
Default Exp/Contr=0.3,0.1
English Units
Geom File=g01
Flow File=f01
Plan File=p01
BEGIN DESCRIPTION:
Kings Creek 27_1
END DESCRIPTION:

--- Kings Creek 27_1.p01 (plan) ---

Plan Title=Multiple Run
Short Identifier=Multiple
Geom File=g01
Flow File=f01
Subcritical Flow
K Sum by GR= 0
Std Step Tol= 0.01
Critical Tol= 0.01
Num of Std Step Trials= 20
Max Error Tol= 0.3
Flow Tol Ratio= 0.001
Split Flow NTrial= 30
Split Flow Tol= 0.02
Split Flow Ratio= 0.02
Log Output Level= 0
Friction Slope Method= 1
Unsteady Friction Slope Method= 2
Unsteady Bridges Friction Slope Method= 1
Parabolic Critical Depth
Global Vel Dist=  1 , 1 , 1
Global Log Level= 0
CheckData=True
Encroach Param= -1, 0, 0, 0
BEGIN DESCRIPTION:
Multiple Run
END DESCRIPTION:

--- Kings Creek 27_1.f01 (steady flow) ---

Flow Title=Multiple
Number of Profiles=7
Profile Names=10-year,25-year,50-year,1pct_min,100-year,1pct_plu,500-year
River Rch & RM= Kings Creek 27_1,Reach-1,2344
     530     713     861     516    1030    2056    1476
Boundary for River Rch & Prof#=Kings Creek 27_1,Reach-1,1
Up Type=0
Dn Type=3
Dn Slope=0.005
Boundary for River Rch & Prof#=Kings Creek 27_1,Reach-1,2
Up Type=0
Dn Type=3
Dn Slope=0.005
Boundary for River Rch & Prof#=Kings Creek 27_1,Reach-1,3
Up Type=0
Dn Type=3
Dn Slope=0.005
Boundary for River Rch & Prof#=Kings Creek 27_1,Reach-1,4
Up Type=0
Dn Type=3
Dn Slope=0.005
Boundary for River Rch & Prof#=Kings Creek 27_1,Reach-1,5
Up Type=0
Dn Type=3
Dn Slope=0.005
Boundary for River Rch & Prof#=Kings Creek 27_1,Reach-1,6
Up Type=0
Dn Type=3
Dn Slope=0.005
Boundary for River Rch & Prof#=Kings Creek 27_1,Reach-1,7
Up Type=0
Dn Type=3
Dn Slope=0.005

--- Kings Creek 27_1.g01 (geometry) ---

Geom Title=Existing Conditions

River Reach=Kings Creek 27_1,Reach-1
Reach XY= 30
      2642326.00      6857261.00      2642331.33      6857313.51
      2642425.76      6857426.22      2642422.33      6857509.41
      2642382.12      6857558.82      2642371.78      6857609.28
      2642331.34      6857658.80      2642325.71      6857690.82
      2642373.70      6857766.93      2642378.30      6857905.07
      2642426.28      6857981.18      2642420.59      6858013.20
      2642376.11      6858076.39      2642381.38      6858113.18
      2642422.19      6858162.55      2642426.45      6858200.81
      2642424.76      6858400.50      2642379.34      6858462.75
      2642376.61      6858500.38      2642468.40      6858614.34
      2642182.06      6858903.52      2642132.12      6858909.19
      2642074.26      6858864.37      2642027.63      6858864.13
      2641839.12      6859047.79      2641827.81      6859104.88
      2641870.57      6859158.81      2641876.22      6859190.86
      2641833.27      6859264.44      2641876.00      6859311.00

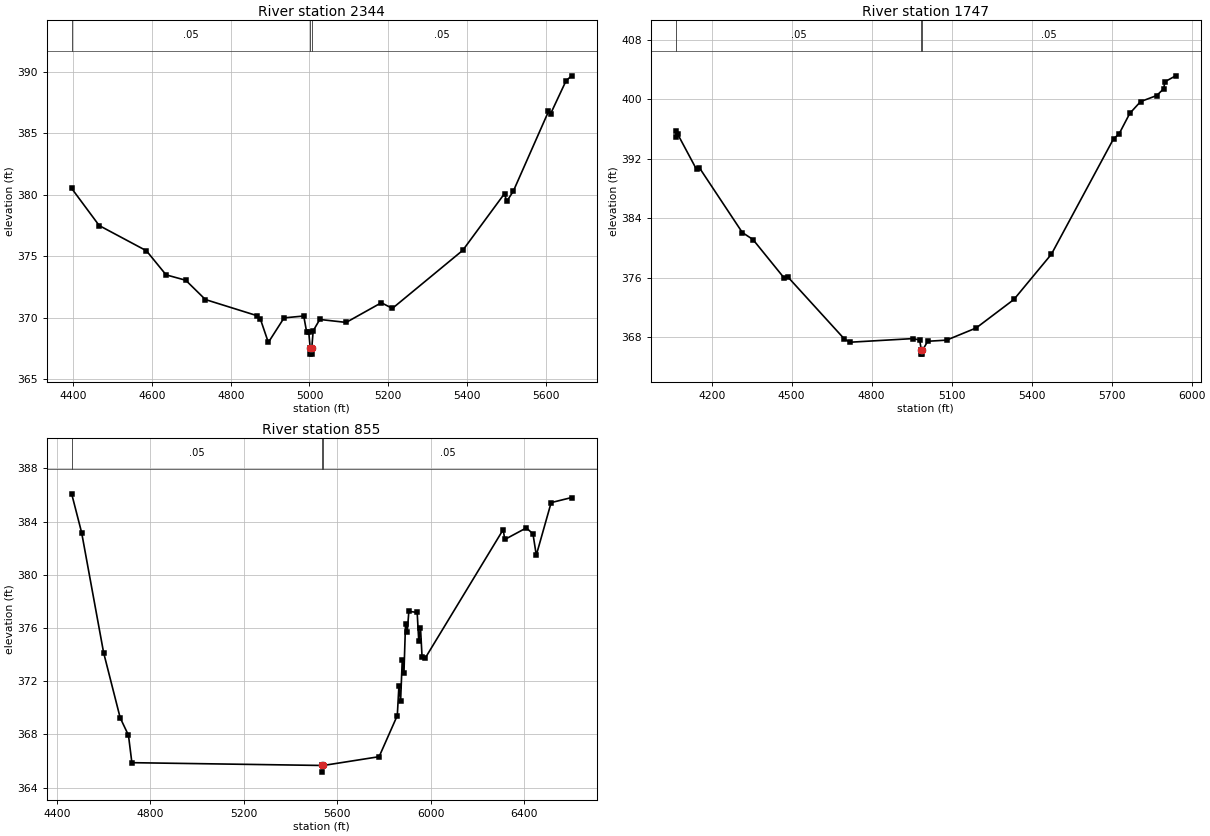
Type RM Length L Ch R = 1,2344,597,597,597
BEGIN DESCRIPTION:
Kings Creek 27_1 3.0
END DESCRIPTION:
XS GIS Cut Line= 3
      2641775.97      6857561.00      2642376.00      6857561.00
      2642976.04      6857861.02
#Sta/Elev= 30
  4395.4  380.53  4465.4  377.51  4585.4  375.46  4635.4  373.50  4685.4  373.06
  4735.4  371.49  4865.4  370.19  4875.4  369.88  4895.4  368.00  4935.4  370.00
  4985.4  370.15  4992.9  368.83  4998.2  368.83  5001.8  367.55  5002.1  367.05
  5005.6  367.05  5005.8  367.55  5009.4  368.95  5026.2  369.87  5093.3  369.63
  5182.7  371.23  5210.7  370.77  5389.5  375.49  5495.8  380.11  5501.3  379.47
  5518.1  380.30  5607.6  386.79  5613.1  386.61  5652.3  389.29  5666.3  389.69
#Mann=3,-1,0
  4395.4    0.05       0  5001.8    0.03       0  5005.8    0.05       0
Bank Sta=5001.8,5005.8
Exp/Cntr=0.3,0.1

Type RM Length L Ch R = 1,1747,892,892,892
BEGIN DESCRIPTION:
Mapping XS c37a4ab6
END DESCRIPTION:
XS GIS Cut Line= 3
      2641448.73      6857985.62      2642351.47      6858098.46
      2643306.35      6857959.57
#Sta/Elev= 30
  4065.4  395.73  4068.1  394.95  4073.1  395.26  4143.3  390.55  4153.7  390.79
  4315.0  382.06  4354.9  381.12  4471.2  375.97  4485.9  376.08  4697.6  367.74
  4718.1  367.30  4954.9  367.79  4980.0  367.60  4986.5  366.20  4986.8  365.70
  4990.3  365.70  4990.5  366.20  5010.1  367.43  5080.8  367.58  5192.0  369.22
  5333.4  373.05  5474.2  379.15  5707.3  394.68  5727.5  395.30  5768.0  398.09
  5808.4  399.67  5869.0  400.49  5894.9  401.39  5899.9  402.35  5940.1  403.14
#Mann=3,-1,0
  4065.4    0.05       0  4986.5    0.03       0  4990.5    0.05       0
Bank Sta=4986.5,4990.5
Exp/Cntr=0.3,0.1

Type RM Length L Ch R = 1,855,0,0,0
BEGIN DESCRIPTION:
Kings Creek 27_1 1.0
END DESCRIPTION:
XS GIS Cut Line= 4
      2641826.04      6858511.03      2642256.02      6858831.05
      2642568.49      6859035.96      2643410.48      6858141.89
#Sta/Elev= 30
  4464.0  386.08  4506.7  383.16  4600.6  374.15  4671.5  369.25  4706.9  367.94
  4721.5  365.88  5536.1  365.67  5536.4  365.17  5540.1  365.67  5778.8  366.33
  5856.5  369.42  5863.4  371.63  5870.7  370.55  5877.6  373.57  5884.9  372.60
  5891.7  376.32  5899.0  375.71  5905.9  377.25  5941.5  377.17  5948.4  374.99
  5955.7  376.03  5962.5  373.80  5976.7  373.76  6309.3  383.39  6316.1  382.65
  6408.4  383.52  6436.7  383.07  6450.9  381.47  6514.4  385.42  6601.8  385.80
#Mann=3,-1,0
  4464.0    0.05       0  5536.1    0.03       0  5540.1    0.05       0
Bank Sta=5536.1,5540.1
Exp/Cntr=0.3,0.1

Chan Stop Cuts=-1