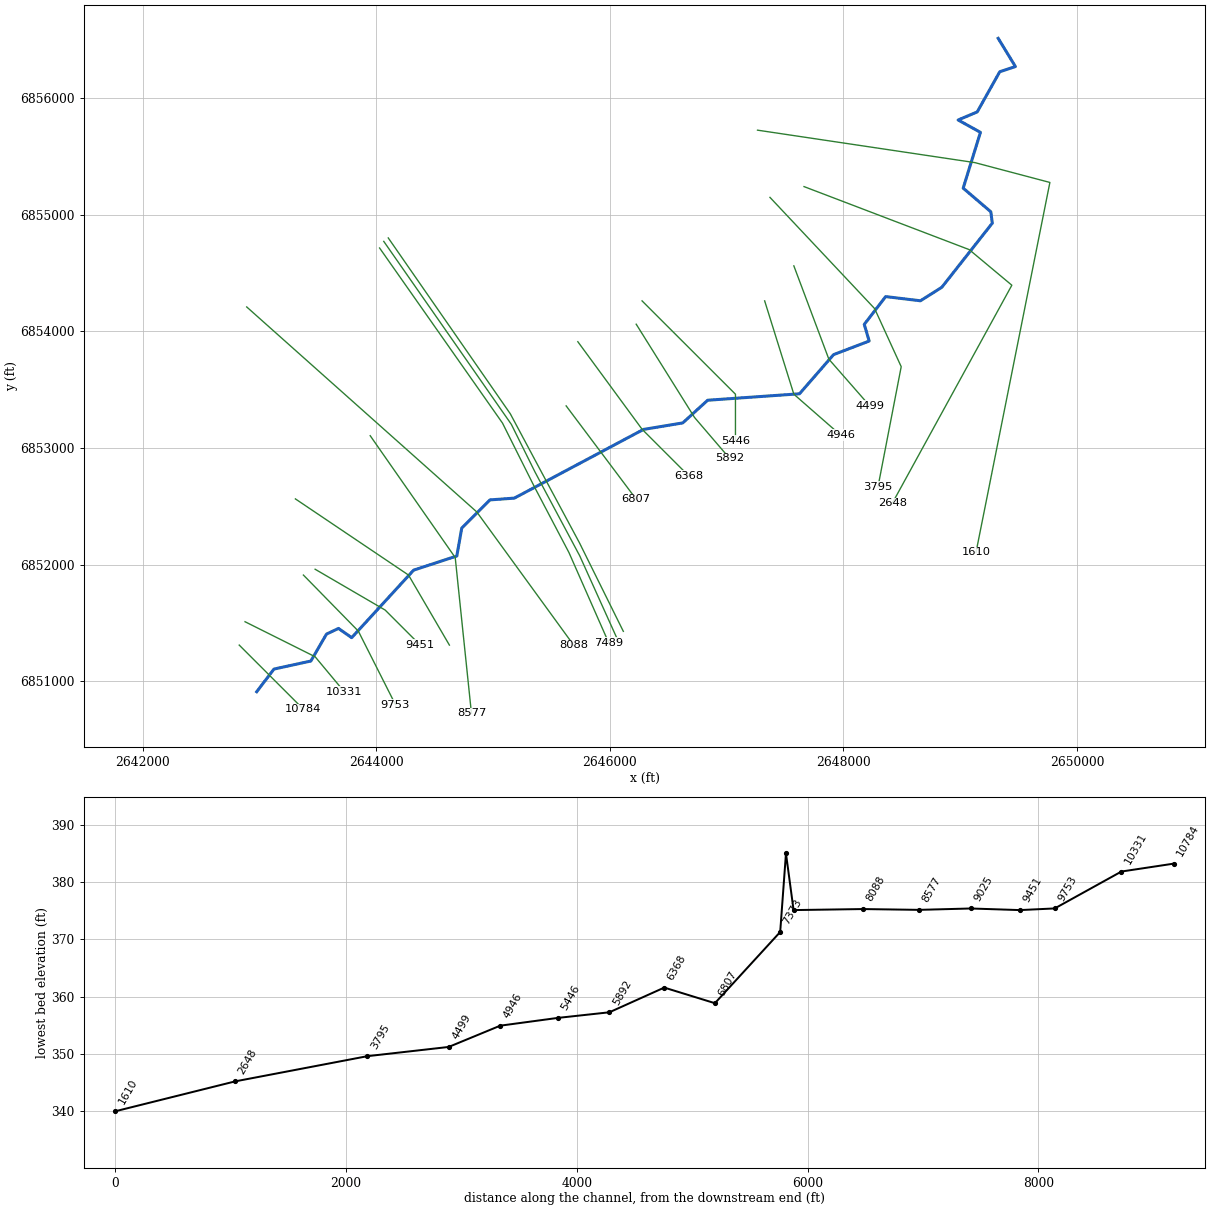
--- Kings Creek 27_2.prj (project) ---

Proj Title=Kings Creek 27_2 Base Level Engineering
Current Plan=p01
Default Exp/Contr=0.3,0.1
English Units
Geom File=g01
Flow File=f01
Plan File=p01
BEGIN DESCRIPTION:
Kings Creek 27_2
END DESCRIPTION:

--- Kings Creek 27_2.p01 (plan) ---

Plan Title=Multiple Run
Short Identifier=Multiple
Geom File=g01
Flow File=f01
Subcritical Flow
K Sum by GR= 0
Std Step Tol= 0.01
Critical Tol= 0.01
Num of Std Step Trials= 20
Max Error Tol= 0.3
Flow Tol Ratio= 0.001
Split Flow NTrial= 30
Split Flow Tol= 0.02
Split Flow Ratio= 0.02
Log Output Level= 0
Friction Slope Method= 1
Unsteady Friction Slope Method= 2
Unsteady Bridges Friction Slope Method= 1
Parabolic Critical Depth
Global Vel Dist=  1 , 1 , 1
Global Log Level= 0
CheckData=True
Encroach Param= -1, 0, 0, 0
BEGIN DESCRIPTION:
Multiple Run
END DESCRIPTION:

--- Kings Creek 27_2.f01 (steady flow) ---

Flow Title=Multiple
Number of Profiles=7
Profile Names=10-year,25-year,50-year,1pct_min,100-year,1pct_plu,500-year
River Rch & RM= Kings Creek 27_2,Reach-1,10784
     499     667     803     480     957    1910    1361
River Rch & RM= Kings Creek 27_2,Reach-1,10331
     703     958    1167     705    1406    2806    2043
River Rch & RM= Kings Creek 27_2,Reach-1,7489
     971    1346    1658    1011    2018    4026    2992
Boundary for River Rch & Prof#=Kings Creek 27_2,Reach-1,1
Up Type=0
Dn Type=3
Dn Slope=0.005
Boundary for River Rch & Prof#=Kings Creek 27_2,Reach-1,2
Up Type=0
Dn Type=3
Dn Slope=0.005
Boundary for River Rch & Prof#=Kings Creek 27_2,Reach-1,3
Up Type=0
Dn Type=3
Dn Slope=0.005
Boundary for River Rch & Prof#=Kings Creek 27_2,Reach-1,4
Up Type=0
Dn Type=3
Dn Slope=0.005
Boundary for River Rch & Prof#=Kings Creek 27_2,Reach-1,5
Up Type=0
Dn Type=3
Dn Slope=0.005
Boundary for River Rch & Prof#=Kings Creek 27_2,Reach-1,6
Up Type=0
Dn Type=3
Dn Slope=0.005
Boundary for River Rch & Prof#=Kings Creek 27_2,Reach-1,7
Up Type=0
Dn Type=3
Dn Slope=0.005

--- Kings Creek 27_2.g01 (geometry) ---

Geom Title=Existing Conditions

River Reach=Kings Creek 27_2,Reach-1
Reach XY= 30
      2642976.00      6850911.00      2643123.45      6851105.27
      2643439.73      6851174.20      2643573.70      6851405.20
      2643676.09      6851453.69      2643789.33      6851374.42
      2644319.83      6851953.14      2644689.71      6852074.47
      2644731.81      6852313.29      2644973.70      6852555.17
      2645182.61      6852570.43      2646287.97      6853159.04
      2646624.42      6853214.82      2646837.83      6853409.36
      2647624.54      6853464.54      2647916.32      6853800.24
      2648221.24      6853916.58      2648179.13      6854059.36
      2648362.27      6854297.62      2648660.16      6854261.68
      2648843.13      6854377.30      2649275.49      6854926.90
      2649262.84      6855024.69      2649026.24      6855227.02
      2649174.04      6855705.35      2648982.87      6855811.00
      2649146.54      6855880.47      2649339.45      6856224.63
      2649473.56      6856269.21      2649326.00      6856511.00

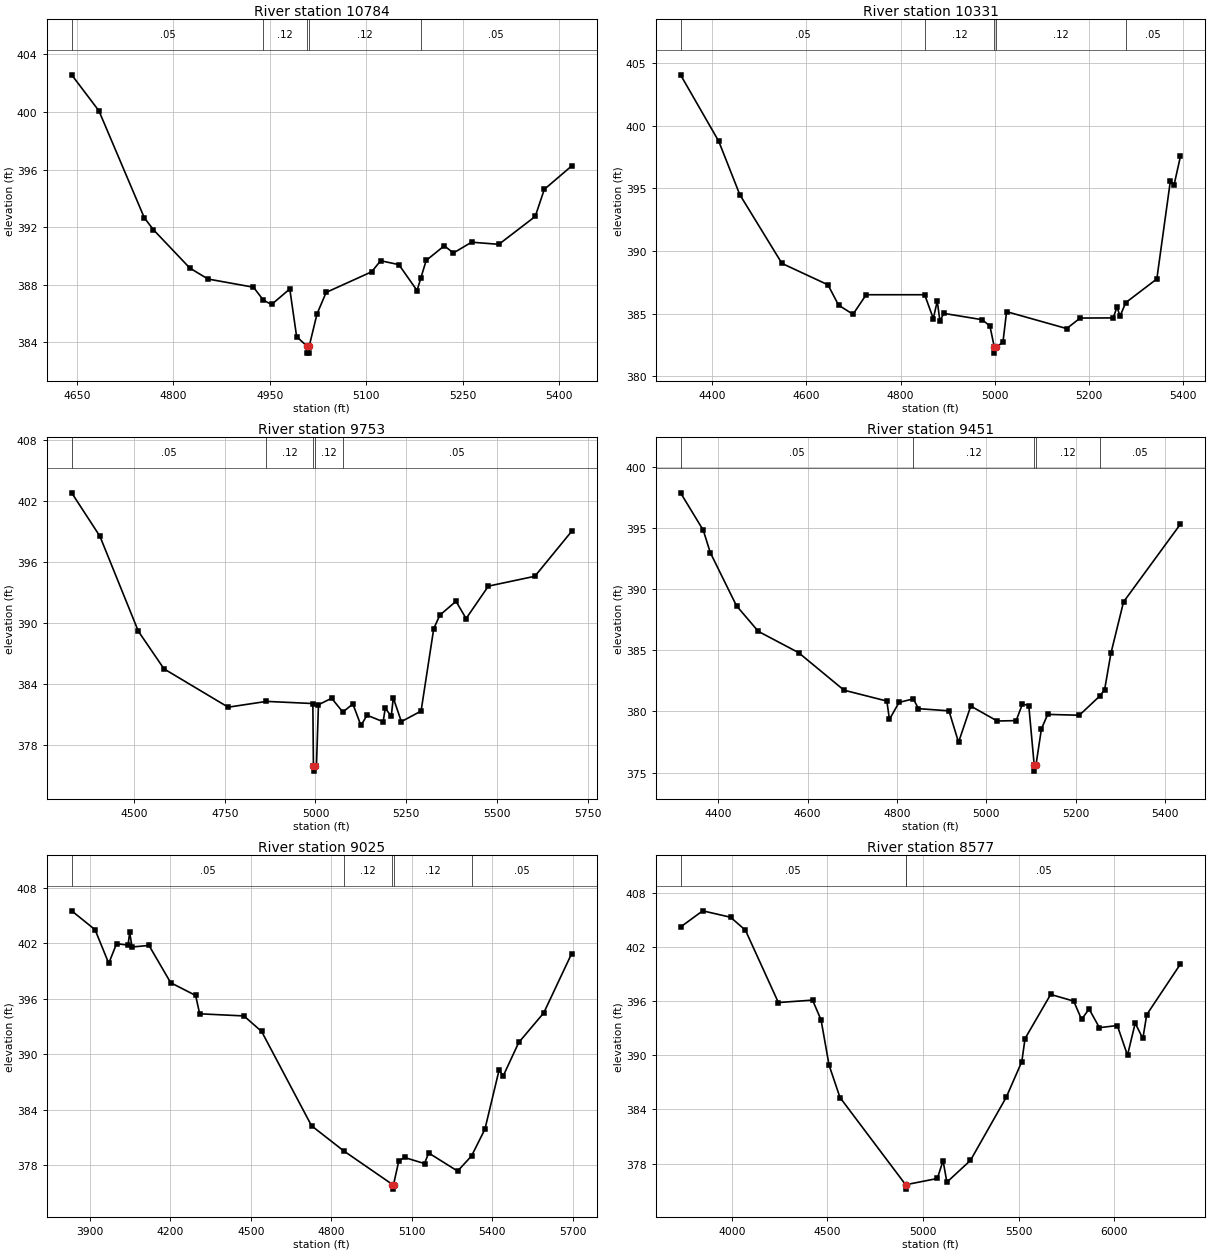
Type RM Length L Ch R = 1,10784,453,453,453
BEGIN DESCRIPTION:
Kings Creek 27_2 20.0
END DESCRIPTION:
XS GIS Cut Line= 3
      2642825.99      6851311.01      2643076.00      6851061.00
      2643375.98      6850761.02
#Sta/Elev= 30
  4641.8  402.58  4684.2  400.08  4754.9  392.64  4769.1  391.81  4825.7  389.15
  4853.9  388.39  4924.7  387.82  4940.1  386.92  4952.9  386.62  4981.2  387.70
  4991.8  384.39  5007.5  383.74  5007.8  383.24  5011.3  383.24  5011.5  383.74
  5023.6  385.97  5037.8  387.46  5108.5  388.89  5122.6  389.66  5150.9  389.39
  5179.2  387.59  5185.2  388.47  5193.4  389.68  5221.6  390.70  5235.8  390.20
  5264.1  390.95  5306.5  390.80  5363.1  392.74  5377.2  394.62  5419.6  396.24
#Mann=5,-1,0
  4641.8    0.05       0  4940.1    0.12       0  5007.5    0.07       0
  5011.5    0.12       0  5185.2    0.05       0
Bank Sta=5007.5,5011.5
Exp/Cntr=0.3,0.1

Type RM Length L Ch R = 1,10331,578,578,578
BEGIN DESCRIPTION:
Kings Creek 27_2 19.0
END DESCRIPTION:
XS GIS Cut Line= 3
      2642875.96      6851511.02      2643476.00      6851211.00
      2643726.01      6850910.99
#Sta/Elev= 30
  4332.9  404.07  4414.0  398.77  4458.7  394.51  4548.2  389.02  4646.0  387.31
  4668.4  385.69  4699.1  384.96  4727.1  386.52  4851.3  386.52  4869.6  384.62
  4878.0  386.01  4883.6  384.43  4892.0  385.03  4973.0  384.53  4989.8  384.03
  4999.0  382.36  4999.2  381.86  5003.0  382.36  5017.4  382.71  5025.2  385.17
  5152.8  383.82  5181.5  384.66  5251.7  384.67  5259.6  385.54  5266.1  384.81
  5278.2  385.89  5344.2  387.78  5372.8  395.56  5380.6  395.25  5394.3  397.56
#Mann=5,-1,0
  4332.9    0.05       0  4851.3    0.12       0  4999.0    0.07       0
  5003.0    0.12       0  5278.2    0.05       0
Bank Sta=4999,5003
Exp/Cntr=0.3,0.1

Type RM Length L Ch R = 1,9753,302,302,302
BEGIN DESCRIPTION:
Kings Creek 27_2 18.0
END DESCRIPTION:
XS GIS Cut Line= 3
      2643376.00      6851911.00      2643846.00      6851430.84
      2644164.00      6850800.73
#Sta/Elev= 30
  4328.1  402.79  4405.9  398.52  4511.9  389.17  4582.6  385.47  4759.5  381.70
  4865.0  382.27  4992.8  382.06  4994.4  375.91  4994.7  375.41  4998.4  375.91
  5002.7  375.91  5008.3  381.94  5044.6  382.58  5075.5  381.22  5103.1  382.02
  5125.4  379.90  5142.1  380.91  5186.6  380.27  5192.3  381.59  5208.9  380.82
  5214.5  382.61  5236.8  380.28  5291.1  381.32  5326.0  389.43  5342.7  390.75
  5387.3  392.12  5415.2  390.42  5476.5  393.61  5604.7  394.58  5705.8  398.99
#Mann=5,-1,0
  4328.1    0.05       0  4865.0    0.12       0  4994.4    0.07       0
  4998.4    0.12       0  5075.5    0.05       0
Bank Sta=4994.4,4998.4
Exp/Cntr=0.3,0.1

Type RM Length L Ch R = 1,9451,426,426,426
BEGIN DESCRIPTION:
Kings Creek 27_2 17.0
END DESCRIPTION:
XS GIS Cut Line= 3
      2643476.00      6851961.00      2644076.00      6851611.00
      2644376.01      6851310.99
#Sta/Elev= 30
  4315.8  397.88  4366.7  394.82  4382.4  392.99  4441.1  388.64  4489.9  386.55
  4580.0  384.81  4681.7  381.74  4777.6  380.85  4783.4  379.35  4804.9  380.74
  4836.9  381.03  4848.3  380.23  4916.6  380.05  4938.1  377.48  4965.4  380.44
  5024.6  379.22  5067.0  379.25  5081.1  380.61  5095.3  380.48  5107.4  375.62
  5107.7  375.12  5111.4  375.62  5123.6  378.58  5137.7  379.76  5208.4  379.69
  5254.2  381.26  5265.0  381.78  5279.1  384.75  5307.4  388.96  5434.7  395.32
#Mann=5,-1,0
  4315.8    0.05       0  4836.9    0.12       0  5107.4    0.07       0
  5111.4    0.12       0  5254.2    0.05       0
Bank Sta=5107.4,5111.4
Exp/Cntr=0.3,0.1

Type RM Length L Ch R = 1,9025,448,448,448
BEGIN DESCRIPTION:
Kings Creek 27_2 16.0
END DESCRIPTION:
XS GIS Cut Line= 3
      2643307.24      6852563.77      2644276.00      6851911.00
      2644626.01      6851310.99
#Sta/Elev= 30
  3832.1  405.48  3919.3  403.44  3970.3  399.80  3999.4  401.93  4042.2  401.77
  4048.3  403.14  4057.2  401.57  4120.2  401.74  4201.1  397.71  4294.1  396.33
  4309.1  394.35  4474.0  394.12  4540.0  392.44  4725.9  382.25  4845.5  379.54
  5027.6  375.90  5027.9  375.40  5031.6  375.90  5051.1  378.44  5072.6  378.82
  5147.0  378.16  5162.3  379.31  5270.3  377.35  5322.1  378.98  5372.0  381.87
  5424.9  388.27  5440.2  387.63  5498.1  391.25  5591.1  394.44  5694.9  400.83
#Mann=5,-1,0
  3832.1    0.05       0  4845.5    0.12       0  5027.6    0.07       0
  5031.6    0.12       0  5322.1    0.05       0
Bank Sta=5027.6,5031.6
Exp/Cntr=0.3,0.1

Type RM Length L Ch R = 1,8577,489,489,489
BEGIN DESCRIPTION:
Kings Creek 27_2 15.0
END DESCRIPTION:
XS GIS Cut Line= 3
      2643947.81      6853105.49      2644676.00      6852061.00
      2644814.99      6850725.59
#Sta/Elev= 30
  3731.0  404.25  3846.9  406.05  3992.5  405.34  4070.3  403.91  4243.0  395.87
  4421.9  396.14  4466.4  393.94  4508.3  388.92  4565.4  385.33  4908.5  375.66
  4908.7  375.16  4912.5  375.66  5074.7  376.34  5104.8  378.31  5124.9  375.93
  5248.2  378.35  5435.3  385.35  5517.0  389.32  5533.8  391.87  5667.8  396.77
  5788.5  396.03  5829.5  394.00  5868.9  395.15  5923.1  393.08  6016.6  393.32
  6070.0  390.02  6110.2  393.58  6150.4  391.88  6170.5  394.52  6346.9  400.14
#Mann=3,-1,0
  3731.0    0.05       0  4908.5    0.03       0  4912.5    0.05       0
Bank Sta=4908.5,4912.5
Exp/Cntr=0.3,0.1

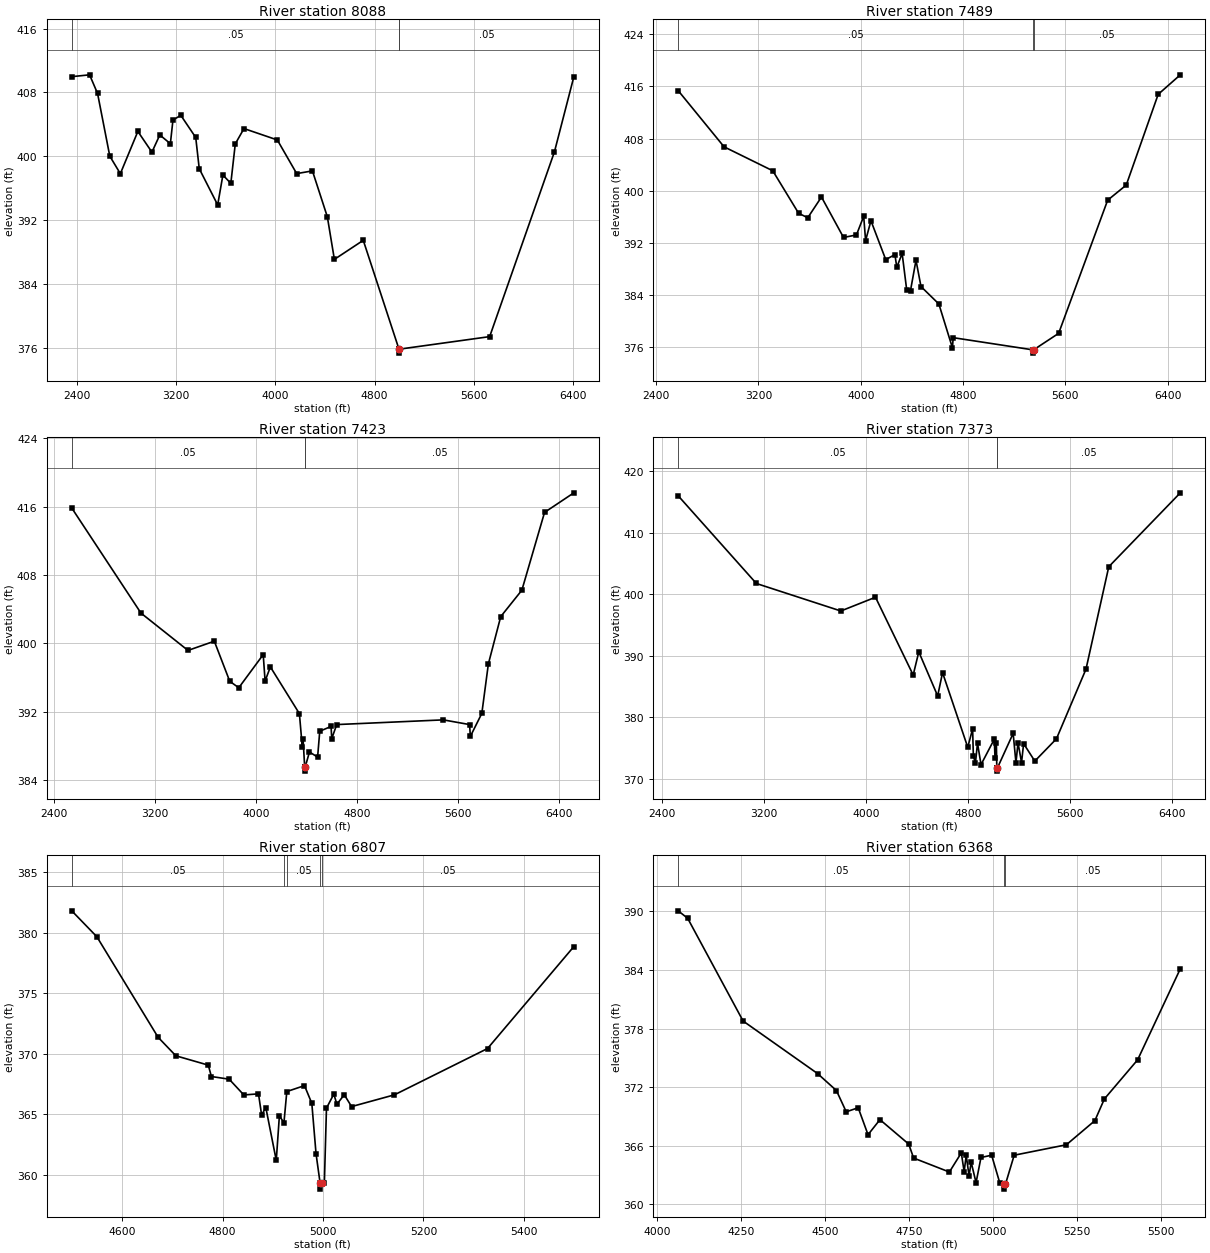
Type RM Length L Ch R = 1,8088,599,599,599
BEGIN DESCRIPTION:
Mapping XS 7f5ea9a2
END DESCRIPTION:
XS GIS Cut Line= 3
      2642890.31      6854208.90      2644860.64      6852451.97
      2645691.96      6851308.02
#Sta/Elev= 30
  2355.6  409.98  2499.5  410.21  2563.9  407.87  2662.6  400.01  2747.8  397.81
  2889.2  403.11  3002.8  400.51  3066.4  402.67  3151.7  401.57  3172.6  404.54
  3236.1  405.13  3356.5  402.35  3384.9  398.44  3533.8  393.89  3575.8  397.64
  3639.9  396.60  3675.9  401.55  3746.1  403.47  4015.3  402.04  4171.7  397.82
  4298.8  398.16  4419.2  392.40  4476.0  387.06  4709.3  389.45  4997.5  375.80
  4997.7  375.30  5001.5  375.80  5729.9  377.37  6253.1  400.56  6409.6  409.97
#Mann=3,-1,0
  2355.6    0.05       0  4997.5    0.03       0  5001.5    0.05       0
Bank Sta=4997.5,5001.5
Exp/Cntr=0.3,0.1

Type RM Length L Ch R = 1,7489,66,66,66
BEGIN DESCRIPTION:
Mapping XS 941a2ee8
END DESCRIPTION:
XS GIS Cut Line= 5
      2644028.37      6854713.99      2645081.15      6853213.08
      2645351.45      6852672.48      2645650.20      6852103.42
      2645991.30      6851328.85
#Sta/Elev= 30
  2573.0  415.33  2931.4  406.73  3312.3  403.06  3514.5  396.55  3586.0  395.86
  3693.2  399.04  3865.8  392.84  3966.9  393.23  4023.5  396.09  4038.3  392.37
  4080.2  395.40  4196.1  389.44  4267.6  390.22  4282.4  388.27  4324.2  390.39
  4360.0  384.79  4389.6  384.71  4432.5  389.35  4471.6  385.32  4611.4  382.65
  4717.6  375.92  4723.2  377.49  5347.6  375.62  5348.0  375.12  5352.0  375.62
  5548.2  378.15  5931.5  398.55  6077.0  400.87  6326.7  414.77  6499.8  417.76
#Mann=3,-1,0
  2573.0    0.05       0  5347.6    0.03       0  5352.0    0.05       0
Bank Sta=5347.6,5352
Exp/Cntr=0.3,0.1

Type RM Length L Ch R = 1,7423,50,50,50
BEGIN DESCRIPTION:
Mapping XS 58125e40
END DESCRIPTION:
XS GIS Cut Line= 5
      2644063.98      6854770.85      2645156.71      6853202.57
      2645360.71      6852791.32      2645742.67      6852074.97
      2646069.87      6851349.45
#Sta/Elev= 30
  2538.8  415.83  3087.1  403.53  3459.7  399.16  3668.3  400.24  3790.5  395.55
  3862.0  394.79  4055.7  398.67  4070.6  395.58  4112.4  397.23  4342.4  391.76
  4365.5  387.81  4371.6  388.75  4384.2  385.53  4384.6  385.03  4388.6  385.53
  4422.2  387.27  4486.7  386.67  4503.6  389.70  4593.2  390.26  4598.8  388.83
  4638.0  390.48  5482.9  391.03  5691.1  390.48  5696.8  389.09  5787.9  391.79
  5839.7  397.58  5937.7  403.12  6105.1  406.21  6284.9  415.32  6517.0  417.61
#Mann=3,-1,0
  2538.8    0.05       0  4384.2    0.03       0  4388.6    0.05       0
Bank Sta=4384.2,4388.6
Exp/Cntr=0.3,0.1

Type RM Length L Ch R = 1,7373,566,566,566
BEGIN DESCRIPTION:
Mapping XS 4fd4772c
END DESCRIPTION:
XS GIS Cut Line= 5
      2644102.67      6854800.27      2645148.30      6853292.29
      2645425.72      6852773.03      2645738.70      6852189.75
      2646115.71      6851428.60
#Sta/Elev= 30
  2530.3  415.95  3142.8  401.73  3804.8  397.27  4076.3  399.50  4371.8  386.88
  4415.7  390.64  4563.6  383.49  4601.9  387.27  4799.4  375.16  4837.6  378.15
  4843.3  373.76  4859.6  372.61  4875.9  375.82  4903.5  372.35  5007.5  376.47
  5013.2  373.36  5023.7  375.88  5027.2  371.79  5027.6  371.29  5031.6  371.79
  5155.3  377.41  5177.2  372.65  5193.4  375.90  5221.0  372.68  5237.3  375.75
  5325.0  372.92  5494.7  376.54  5726.2  387.84  5904.7  404.45  6465.4  416.44
#Mann=3,-1,0
  2530.3    0.05       0  5027.2    0.03       0  5031.6    0.05       0
Bank Sta=5027.2,5031.6
Exp/Cntr=0.3,0.1

Type RM Length L Ch R = 1,6807,439,439,439
BEGIN DESCRIPTION:
Kings Creek 27_2 11.0
END DESCRIPTION:
XS GIS Cut Line= 3
      2645626.00      6853361.00      2645926.00      6852961.00
      2646226.00      6852561.00
#Sta/Elev= 30
  4499.6  381.80  4549.6  379.66  4671.5  371.37  4706.9  369.84  4771.5  369.07
  4777.7  368.13  4813.1  367.91  4842.3  366.61  4871.5  366.70  4877.7  364.96
  4886.1  365.57  4906.9  361.21  4913.1  364.88  4922.2  364.32  4927.9  366.89
  4963.1  367.38  4977.7  365.92  4986.1  361.77  4994.2  359.34  4994.7  358.84
  4998.7  359.34  5002.7  359.34  5006.9  365.52  5021.5  366.68  5027.7  365.84
  5042.3  366.63  5056.9  365.65  5142.3  366.62  5327.7  370.44  5499.6  378.85
#Mann=5,-1,0
  4499.6    0.05       0  4922.2    0.12       0  4927.9    0.05       0
  4994.2    0.03       0  4998.7    0.05       0
Bank Sta=4994.2,4998.7
Exp/Cntr=0.3,0.1

Type RM Length L Ch R = 1,6368,476,476,476
BEGIN DESCRIPTION:
Kings Creek 27_2 10.0
END DESCRIPTION:
XS GIS Cut Line= 3
      2645726.00      6853911.00      2646276.00      6853161.00
      2646675.97      6852761.03
#Sta/Elev= 30
  4062.0  390.05  4090.2  389.28  4255.3  378.77  4476.9  373.40  4533.2  371.66
  4562.5  369.48  4598.1  369.90  4627.4  367.14  4662.9  368.68  4748.6  366.18
  4763.2  364.75  4869.7  363.32  4905.3  365.28  4913.7  363.36  4919.9  365.03
  4928.4  362.92  4934.6  364.33  4949.2  362.23  4963.9  364.81  4995.6  365.04
  5020.3  362.16  5032.1  362.07  5032.6  361.57  5036.8  362.07  5062.8  365.04
  5218.3  366.11  5303.2  368.58  5331.5  370.80  5430.5  374.80  5557.7  384.12
#Mann=3,-1,0
  4062.0    0.05       0  5032.1    0.04       0  5036.8    0.05       0
Bank Sta=5032.1,5036.8
Exp/Cntr=0.3,0.1

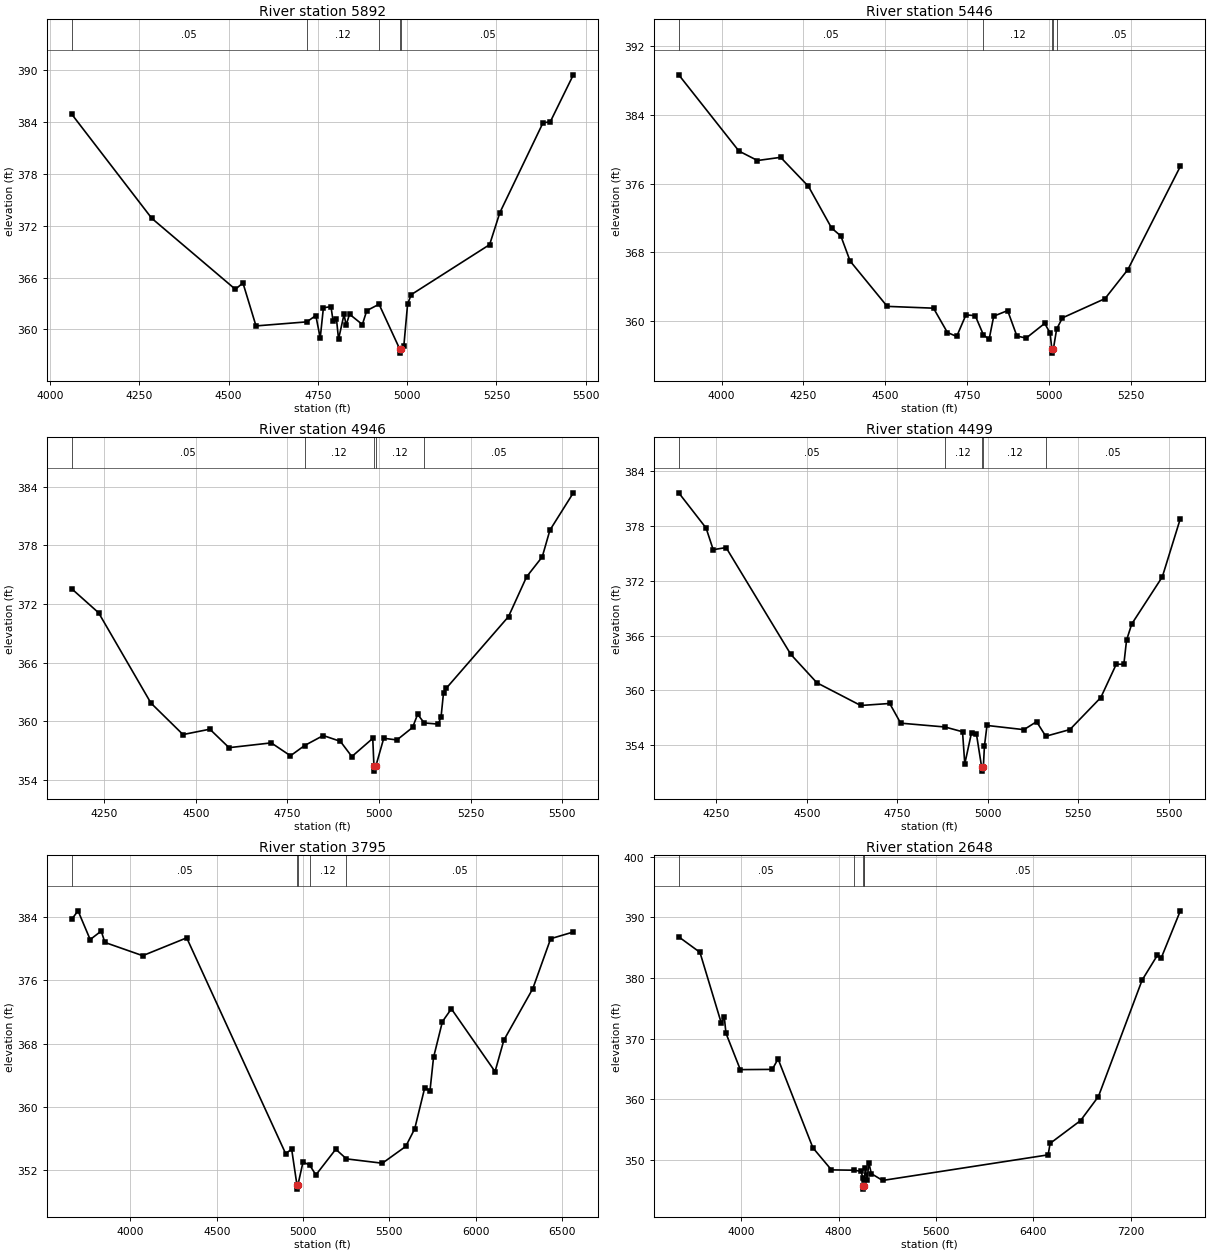
Type RM Length L Ch R = 1,5892,446,446,446
BEGIN DESCRIPTION:
Kings Creek 27_2 9.0
END DESCRIPTION:
XS GIS Cut Line= 3
      2646226.01      6854060.98      2646726.00      6853261.00
      2647026.03      6852910.96
#Sta/Elev= 30
  4061.0  384.91  4285.0  372.86  4519.1  364.64  4540.3  365.38  4576.9  360.40
  4719.1  360.87  4744.4  361.60  4756.7  359.00  4765.6  362.50  4786.8  362.63
  4792.7  360.97  4802.1  361.25  4808.0  358.86  4823.4  361.74  4829.3  360.48
  4838.7  361.76  4874.7  360.56  4887.0  362.17  4921.4  362.91  4979.0  357.75
  4979.5  357.25  4983.7  357.75  4990.8  358.08  5001.4  362.94  5011.5  364.02
  5231.0  369.81  5259.6  373.51  5380.3  383.90  5401.1  384.05  5465.4  389.47
#Mann=5,-1,0
  4061.0    0.05       0  4719.1    0.12       0  4921.4    0.05       0
  4979.0    0.03       0  4983.7    0.05       0
Bank Sta=4979,4983.7
Exp/Cntr=0.3,0.1

Type RM Length L Ch R = 1,5446,500,500,500
BEGIN DESCRIPTION:
Kings Creek 27_2 8.0
END DESCRIPTION:
XS GIS Cut Line= 3
      2646276.02      6854260.98      2647076.00      6853461.00
      2647076.00      6853061.04
#Sta/Elev= 30
  3869.2  388.65  4053.0  379.78  4109.6  378.68  4180.3  379.05  4265.2  375.67
  4335.9  370.82  4364.1  369.90  4392.4  366.98  4505.6  361.71  4647.0  361.50
  4689.4  358.67  4717.7  358.21  4746.0  360.72  4774.3  360.63  4799.3  358.40
  4816.7  357.87  4830.8  360.57  4873.3  361.22  4901.5  358.26  4929.8  358.02
  4986.4  359.73  5003.0  358.60  5008.1  356.77  5008.7  356.27  5013.0  356.77
  5022.8  359.06  5040.5  360.37  5170.5  362.61  5240.5  366.00  5400.5  378.00
#Mann=5,-1,0
  3869.2    0.05       0  4799.3    0.12       0  5008.1    0.07       0
  5013.0    0.12       0  5022.8    0.05       0
Bank Sta=5008.1,5013
Exp/Cntr=0.3,0.1

Type RM Length L Ch R = 1,4946,447,447,447
BEGIN DESCRIPTION:
Kings Creek 27_2 7.0
END DESCRIPTION:
XS GIS Cut Line= 3
      2647326.01      6854260.98      2647576.00      6853461.00
      2647975.97      6853111.03
#Sta/Elev= 30
  4161.2  373.56  4234.5  371.11  4377.5  361.87  4465.0  358.65  4538.3  359.20
  4590.7  357.31  4706.0  357.80  4758.4  356.48  4797.1  357.53  4847.9  358.55
  4894.6  357.96  4926.0  356.40  4983.1  358.26  4986.4  355.41  4987.0  354.91
  4991.4  355.41  5013.1  358.27  5049.2  358.10  5091.9  359.38  5105.6  360.72
  5123.6  359.84  5162.1  359.72  5169.7  360.48  5176.3  362.93  5183.9  363.39
  5353.8  370.72  5403.2  374.79  5445.9  376.83  5466.8  379.56  5530.8  383.38
#Mann=5,-1,0
  4161.2    0.05       0  4797.1    0.12       0  4986.4    0.07       0
  4991.4    0.12       0  5123.6    0.05       0
Bank Sta=4986.4,4991.4
Exp/Cntr=0.3,0.1

Type RM Length L Ch R = 1,4499,704,704,704
BEGIN DESCRIPTION:
Kings Creek 27_2 6.0
END DESCRIPTION:
XS GIS Cut Line= 3
      2647576.01      6854560.98      2647876.00      6853761.00
      2648226.01      6853360.99
#Sta/Elev= 30
  4145.9  381.59  4221.5  377.74  4241.1  375.38  4276.7  375.61  4455.6  363.94
  4527.7  360.84  4648.7  358.36  4728.8  358.58  4759.1  356.43  4881.7  356.01
  4930.0  355.49  4936.2  351.98  4954.9  355.40  4968.2  355.30  4982.6  351.69
  4983.2  351.19  4987.6  351.69  4990.5  353.92  4997.6  356.18  5099.5  355.72
  5134.6  356.59  5160.0  355.00  5226.6  355.73  5312.1  359.23  5354.8  362.87
  5375.7  362.86  5383.2  365.49  5397.5  367.26  5482.0  372.41  5531.8  378.77
#Mann=5,-1,0
  4145.9    0.05       0  4881.7    0.12       0  4982.6    0.07       0
  4987.6    0.12       0  5160.0    0.05       0
Bank Sta=4982.6,4987.6
Exp/Cntr=0.3,0.1

Type RM Length L Ch R = 1,3795,1147,1147,1147
BEGIN DESCRIPTION:
Mapping XS 0b63d39d
END DESCRIPTION:
XS GIS Cut Line= 4
      2647371.59      6855147.86      2648267.85      6854194.70
      2648495.47      6853696.77      2648296.36      6852665.66
#Sta/Elev= 30
  3659.8  383.76  3696.3  384.82  3766.6  381.18  3830.6  382.26  3851.6  380.82
  4070.9  379.14  4325.8  381.40  4898.8  354.09  4933.9  354.63  4964.7  350.08
  4965.4  349.58  4969.8  350.08  4999.8  353.02  5038.3  352.62  5074.3  351.38
  5189.4  354.63  5251.3  353.41  5459.2  352.86  5594.9  354.99  5646.8  357.22
  5704.8  362.41  5735.4  362.06  5755.8  366.25  5807.4  370.80  5859.2  372.41
  6112.2  364.46  6163.2  368.44  6330.8  374.96  6434.4  381.29  6565.8  382.14
#Mann=5,-1,0
  3659.8    0.05       0  4964.7    0.04       0  4969.8    0.05       0
  5038.3    0.12       0  5251.3    0.05       0
Bank Sta=4964.7,4969.8
Exp/Cntr=0.3,0.1

Type RM Length L Ch R = 1,2648,1038,1038,1038
BEGIN DESCRIPTION:
Kings Creek 27_2 4.0
END DESCRIPTION:
XS GIS Cut Line= 4
      2647663.24      6855240.33      2649077.66      6854700.31
      2649442.91      6854395.12      2648418.02      6852524.56
#Sta/Elev= 30
  3486.0  386.76  3660.2  384.21  3835.7  372.55  3860.4  373.51  3874.3  370.86
  3992.0  364.87  4254.7  364.91  4302.5  366.63  4588.8  351.98  4741.3  348.34
  4923.3  348.29  4983.1  348.12  5002.2  346.94  5002.9  345.67  5003.6  345.17
  5008.1  345.67  5011.7  346.73  5019.9  348.73  5034.2  346.67  5048.5  349.50
  5069.3  347.72  5161.7  346.60  6522.3  350.82  6538.4  352.71  6788.7  356.47
  6935.6  360.44  7295.0  379.64  7420.1  383.72  7452.3  383.30  7608.9  391.05
#Mann=5,-1,0
  3486.0    0.05       0  4923.3    0.12       0  5002.9    0.07       0
  5008.1    0.12       0  5011.7    0.05       0
Bank Sta=5002.9,5008.1
Exp/Cntr=0.3,0.1

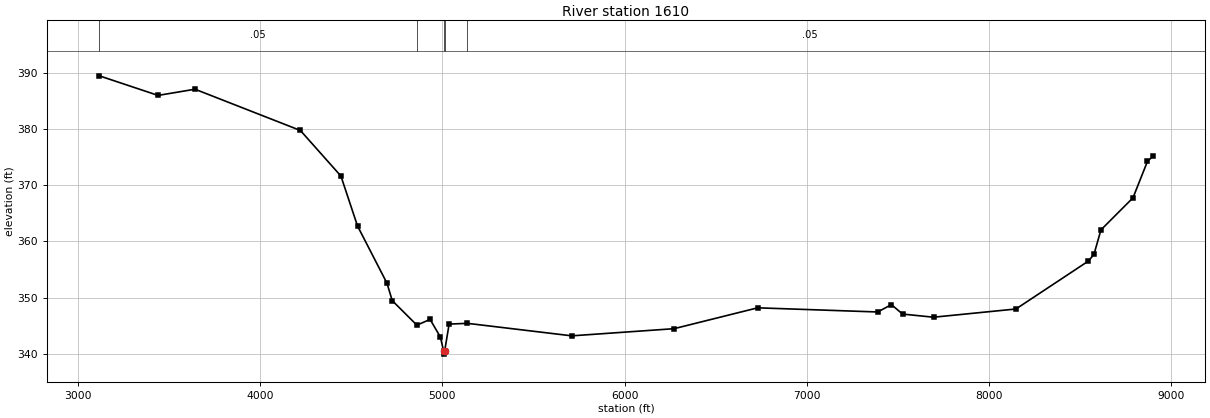
Type RM Length L Ch R = 1,1610,0,0,0
BEGIN DESCRIPTION:
Kings Creek 27_2 3.0
END DESCRIPTION:
XS GIS Cut Line= 4
      2647264.92      6855724.02      2649126.16      6855445.94
      2649768.72      6855275.90      2649135.91      6852104.71
#Sta/Elev= 30
  3118.1  389.41  3440.4  385.93  3643.0  387.03  4221.3  379.70  4443.7  371.60
  4534.7  362.73  4696.5  352.55  4725.3  349.46  4860.5  345.10  4933.0  346.12
  4989.7  342.98  5007.5  340.45  5008.3  339.95  5012.8  340.45  5037.4  345.29
  5138.2  345.42  5710.5  343.20  6271.3  344.47  6730.7  348.18  7389.2  347.44
  7464.4  348.75  7525.6  347.07  7695.4  346.51  8147.6  347.97  8545.3  356.49
  8575.9  357.69  8614.2  362.03  8790.0  367.73  8869.4  374.21  8898.4  375.08
#Mann=5,-1,0
  3118.1    0.05       0  4860.5    0.12       0  5007.5    0.07       0
  5012.8    0.12       0  5138.2    0.05       0
Bank Sta=5007.5,5012.8
Exp/Cntr=0.3,0.1

Chan Stop Cuts=-1