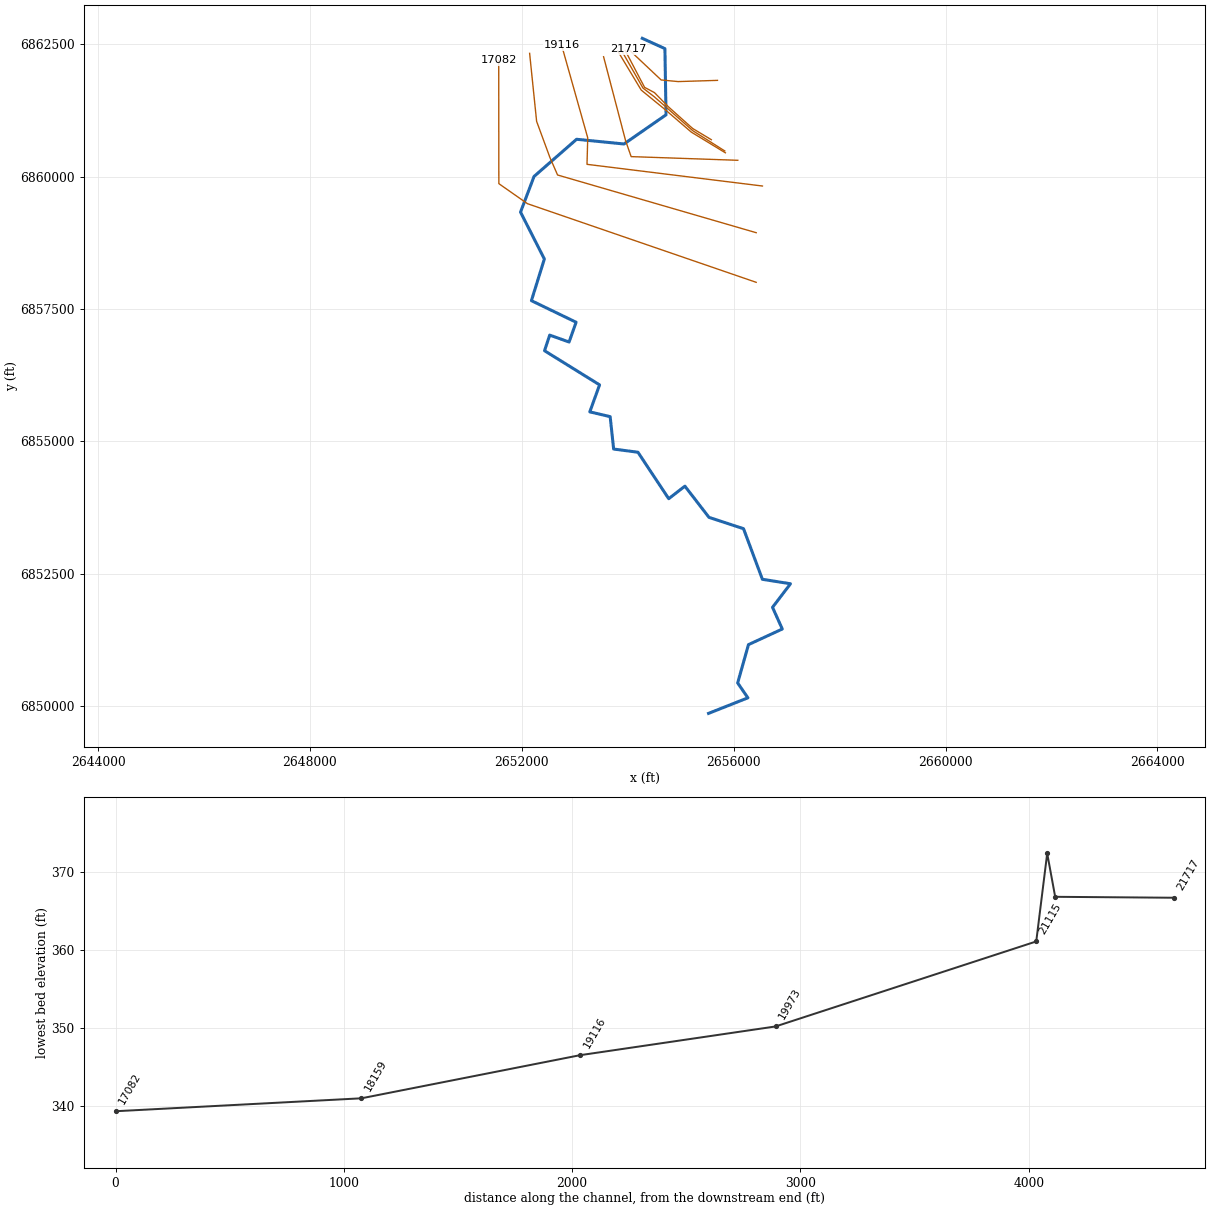
--- Kings Creek 28.prj (project) ---

Proj Title=Kings Creek 28 Base Level Engineering
Current Plan=p01
Default Exp/Contr=0.3,0.1
English Units
Geom File=g01
Flow File=f01
Plan File=p01
BEGIN DESCRIPTION:
Kings Creek 28
END DESCRIPTION:

--- Kings Creek 28.p01 (plan) ---

Plan Title=Multiple Run
Short Identifier=Multiple
Geom File=g01
Flow File=f01
Subcritical Flow
K Sum by GR= 0
Std Step Tol= 0.01
Critical Tol= 0.01
Num of Std Step Trials= 20
Max Error Tol= 0.3
Flow Tol Ratio= 0.001
Split Flow NTrial= 30
Split Flow Tol= 0.02
Split Flow Ratio= 0.02
Log Output Level= 0
Friction Slope Method= 1
Unsteady Friction Slope Method= 2
Unsteady Bridges Friction Slope Method= 1
Parabolic Critical Depth
Global Vel Dist=  1 , 1 , 1
Global Log Level= 0
CheckData=True
Encroach Param= -1, 0, 0, 0
BEGIN DESCRIPTION:
Multiple Run
END DESCRIPTION:

--- Kings Creek 28.f01 (steady flow) ---

Flow Title=Multiple
Number of Profiles=7
Profile Names=10-year,25-year,50-year,1pct_min,100-year,1pct_plu,500-year
River Rch & RM= Kings Creek 28,Reach-1,21717
     286     363     421     242     483     964     637
River Rch & RM= Kings Creek 28,Reach-1,21198
     334     430     504     293     585    1168     788
River Rch & RM= Kings Creek 28,Reach-1,19973
     486     639     758     446     890    1776    1227
Boundary for River Rch & Prof#=Kings Creek 28,Reach-1,1
Up Type=0
Dn Type=3
Dn Slope=0.005
Boundary for River Rch & Prof#=Kings Creek 28,Reach-1,2
Up Type=0
Dn Type=3
Dn Slope=0.005
Boundary for River Rch & Prof#=Kings Creek 28,Reach-1,3
Up Type=0
Dn Type=3
Dn Slope=0.005
Boundary for River Rch & Prof#=Kings Creek 28,Reach-1,4
Up Type=0
Dn Type=3
Dn Slope=0.005
Boundary for River Rch & Prof#=Kings Creek 28,Reach-1,5
Up Type=0
Dn Type=3
Dn Slope=0.005
Boundary for River Rch & Prof#=Kings Creek 28,Reach-1,6
Up Type=0
Dn Type=3
Dn Slope=0.005
Boundary for River Rch & Prof#=Kings Creek 28,Reach-1,7
Up Type=0
Dn Type=3
Dn Slope=0.005

--- Kings Creek 28.g01 (geometry) ---

Geom Title=Existing Conditions

River Reach=Kings Creek 28,Reach-1
Reach XY= 30
      2654274.86      6862614.68      2654701.94      6862420.24
      2654722.84      6861169.34      2653929.42      6860618.76
      2653034.48      6860707.49      2652231.44      6860005.75
      2651975.86      6859331.47      2652425.86      6858445.59
      2652181.39      6857658.56      2653025.02      6857250.72
      2652892.66      6856877.20      2652527.22      6857007.57
      2652429.13      6856712.63      2653468.33      6856067.52
      2653283.79      6855557.57      2653668.19      6855467.23
      2653733.86      6854854.83      2654192.67      6854794.79
      2654773.70      6853916.83      2655079.32      6854153.42
      2655534.34      6853564.16      2656186.00      6853350.37
      2656542.18      6852394.30      2657072.63      6852309.72
      2656733.59      6851864.33      2656918.20      6851454.79
      2656279.48      6851159.74      2656075.47      6850435.88
      2656268.68      6850154.62      2655526.00      6849861.00

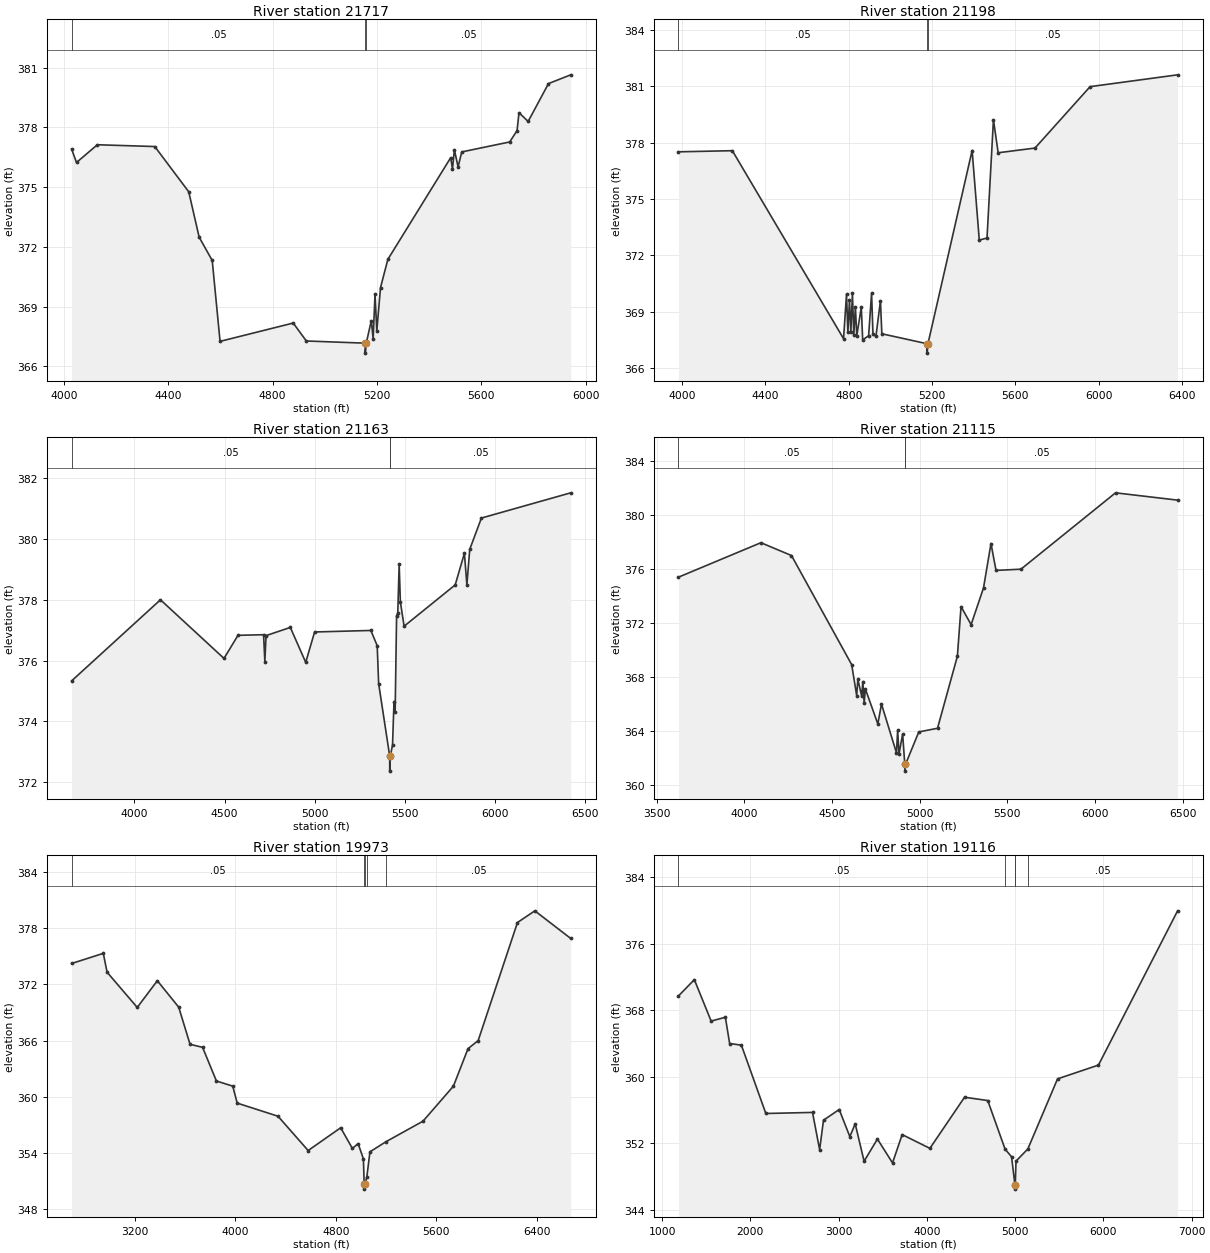
Type RM Length L Ch R = 1,21717,519,519,519
BEGIN DESCRIPTION:
Kings Creek 28 19.0
END DESCRIPTION:
XS GIS Cut Line= 4
      2655694.70      6861820.62      2654951.43      6861797.54
      2654630.81      6861828.28      2654013.92      6862409.52
#Sta/Elev= 30
  4029.9  376.91  4048.6  376.24  4128.6  377.13  4348.7  377.04  4478.8  374.77
  4518.8  372.49  4568.9  371.32  4598.9  367.26  4879.4  368.18  4929.7  367.28
  5155.3  367.17  5155.6  366.67  5159.3  367.17  5178.8  368.30  5185.7  367.39
  5193.0  369.62  5199.8  367.79  5214.0  369.96  5242.3  371.38  5483.0  376.48
  5489.9  375.92  5497.2  376.88  5511.4  376.02  5525.5  376.77  5709.2  377.27
  5737.5  377.84  5744.8  378.74  5780.0  378.30  5857.9  380.20  5943.2  380.64
#Mann=3,-1,0
  4029.9    0.05       0  5155.3    0.03       0  5159.3    0.05       0
Bank Sta=5155.3,5159.3
Exp/Cntr=0.3,0.1

Type RM Length L Ch R = 1,21198,35,35,35
BEGIN DESCRIPTION:
Mapping XS 32965884
END DESCRIPTION:
XS GIS Cut Line= 6
      2655577.93      6860699.83      2655224.87      6860912.12
      2654769.14      6861320.11      2654504.38      6861589.20
      2654317.75      6861689.03      2653953.18      6862383.45
#Sta/Elev= 30
  3982.2  377.51  4240.9  377.57  4775.0  367.56  4789.2  369.92  4795.9  367.89
  4803.4  369.61  4810.1  367.90  4817.6  369.97  4824.3  367.77  4831.8  369.26
  4838.5  367.72  4860.2  369.23  4866.9  367.49  4895.4  367.72  4909.6  369.97
  4916.3  367.83  4930.5  367.68  4952.2  369.58  4958.9  367.82  5176.4  367.29
  5176.6  366.79  5180.4  367.29  5392.5  377.58  5426.9  372.81  5464.0  372.92
  5494.9  379.22  5517.6  377.46  5694.4  377.71  5959.0  380.98  6379.3  381.61
#Mann=3,-1,0
  3982.2    0.05       0  5176.4    0.03       0  5180.4    0.05       0
Bank Sta=5176.4,5180.4
Exp/Cntr=0.3,0.1

Type RM Length L Ch R = 1,21163,48,48,48
BEGIN DESCRIPTION:
Mapping XS 7da13c0b
END DESCRIPTION:
XS GIS Cut Line= 6
      2655832.42      6860486.70      2655229.21      6860868.72
      2654747.43      6861294.06      2654503.03      6861508.81
      2654287.37      6861676.01      2653883.73      6862383.45
#Sta/Elev= 30
  3651.5  375.33  4144.4  378.00  4497.0  376.07  4574.7  376.83  4716.6  376.85
  4723.7  375.96  4730.3  376.82  4865.0  377.09  4950.4  375.94  4999.7  376.94
  5311.9  376.99  5347.0  376.49  5355.1  375.24  5416.3  372.86  5416.6  372.36
  5420.3  372.86  5432.1  373.22  5440.3  374.65  5446.6  374.30  5454.7  377.48
  5461.1  377.55  5469.0  379.17  5475.6  377.93  5496.4  377.13  5779.9  378.49
  5830.9  379.53  5844.7  378.49  5860.5  379.66  5925.4  380.69  6420.9  381.52
#Mann=3,-1,0
  3651.5    0.05       0  5416.3    0.03       0  5420.3    0.05       0
Bank Sta=5416.3,5420.3
Exp/Cntr=0.3,0.1

Type RM Length L Ch R = 1,21115,1142,1142,1142
BEGIN DESCRIPTION:
Mapping XS 3c7bf4c7
END DESCRIPTION:
XS GIS Cut Line= 5
      2655843.38      6860451.90      2655200.98      6860842.54
      2654706.19      6861267.89      2654254.80      6861636.81
      2653812.08      6862374.68
#Sta/Elev= 30
  3623.5  375.41  4093.9  377.96  4268.3  377.01  4611.7  368.94  4640.3  366.65
  4646.8  367.86  4668.8  366.62  4675.4  367.69  4683.0  366.09  4689.6  367.15
  4761.0  364.55  4781.8  366.02  4867.4  362.41  4874.0  364.09  4881.7  362.33
  4902.5  363.81  4914.8  361.56  4915.0  361.06  4918.8  361.56  4994.7  363.96
  5101.5  364.23  5214.9  369.56  5235.7  373.23  5293.2  371.90  5363.9  374.61
  5406.6  377.90  5435.3  375.91  5577.4  376.00  6117.2  381.65  6471.3  381.11
#Mann=3,-1,0
  3623.5    0.05       0  4914.8    0.03       0  4918.8    0.05       0
Bank Sta=4914.8,4918.8
Exp/Cntr=0.3,0.1

Type RM Length L Ch R = 1,19973,857,857,857
BEGIN DESCRIPTION:
Mapping XS 2f470efc
END DESCRIPTION:
XS GIS Cut Line= 4
      2656078.12      6860310.56      2654064.27      6860380.00
      2653960.11      6860678.61      2653543.81      6862267.48
#Sta/Elev= 30
  2695.7  374.23  2948.0  375.31  2978.0  373.30  3218.1  369.54  3378.2  372.39
  3548.3  369.57  3638.4  365.61  3738.4  365.28  3848.5  361.69  3978.6  361.14
  4014.0  359.33  4338.8  357.93  4578.9  354.27  4837.9  356.70  4931.1  354.49
  4976.6  355.01  5018.9  353.38  5025.0  350.65  5025.3  350.15  5029.0  350.65
  5045.9  351.42  5070.8  354.13  5199.7  355.22  5493.2  357.40  5735.6  361.14
  5851.7  365.14  5932.5  366.00  6245.4  378.60  6383.7  379.85  6669.5  376.90
#Mann=5,-1,0
  2695.7    0.05       0  5025.0    0.03       0  5029.0    0.05       0
  5045.9    0.12       0  5199.7    0.05       0
Bank Sta=5025,5029
Exp/Cntr=0.3,0.1

Type RM Length L Ch R = 1,19116,957,957,957
BEGIN DESCRIPTION:
Mapping XS 9994a57d
END DESCRIPTION:
XS GIS Cut Line= 4
      2656543.41      6859824.45      2653230.94      6860234.17
      2653244.83      6860734.17      2652751.78      6862484.14
#Sta/Elev= 30
  1185.0  369.73  1364.7  371.69  1555.2  366.70  1716.4  367.16  1764.8  364.00
  1897.8  363.80  2175.0  355.57  2703.9  355.70  2784.5  351.21  2828.4  354.76
  3006.2  356.05  3127.1  352.78  3187.6  354.33  3288.3  349.82  3439.5  352.49
  3610.8  349.62  3719.8  353.03  4034.0  351.37  4426.9  357.53  4689.6  357.13
  4885.6  351.29  4959.7  350.35  4997.7  346.96  4998.0  346.46  5001.7  346.96
  5009.7  349.83  5144.1  351.30  5480.7  359.74  5944.3  361.40  6841.0  379.98
#Mann=5,-1,0
  1185.0    0.05       0  4885.6    0.12       0  4997.7    0.07       0
  5001.7    0.12       0  5144.1    0.05       0
Bank Sta=4997.7,5001.7
Exp/Cntr=0.3,0.1

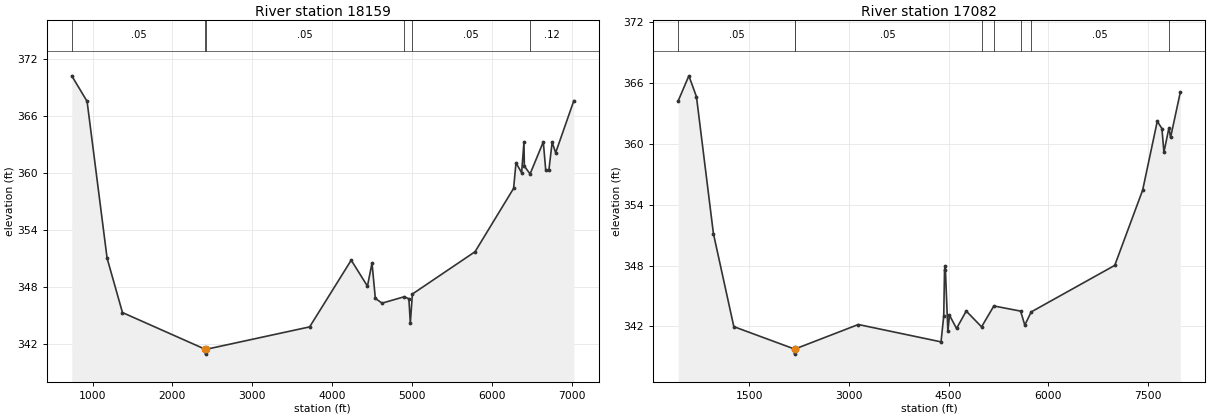
Type RM Length L Ch R = 1,18159,1077,1077,1077
BEGIN DESCRIPTION:
Mapping XS 8deae77f
END DESCRIPTION:
XS GIS Cut Line= 5
      2656425.39      6858942.50      2652675.39      6860032.78
      2652529.55      6860366.11      2652279.55      6861046.67
      2652147.61      6862331.37
#Sta/Elev= 30
   740.1  370.25   931.9  367.56  1182.3  351.04  1374.7  345.31  2414.1  341.43
  2414.4  340.93  2418.1  341.43  3717.9  343.80  4238.6  350.83  4441.8  348.09
  4498.9  350.52  4540.6  346.80  4625.1  346.30  4904.2  346.98  4960.6  346.76
  4978.5  344.19  5004.3  347.26  5788.9  351.72  6271.4  358.39  6301.5  361.08
  6371.9  360.04  6401.1  363.26  6406.2  360.74  6477.7  359.91  6643.3  363.29
  6673.5  360.34  6713.7  360.35  6753.9  363.25  6798.0  362.15  7025.7  367.63
#Mann=6,-1,0
   740.1    0.05       0  2414.1    0.07       0  2418.1    0.05       0
  4904.2    0.12       0  5004.3    0.05       0  6477.7    0.12       0
Bank Sta=2414.1,2418.1
Exp/Cntr=0.3,0.1

Type RM Length L Ch R = 1,17082,0,0,0
BEGIN DESCRIPTION:
Kings Creek 28 13.0
END DESCRIPTION:
XS GIS Cut Line= 4
      2656425.36      6858005.01      2652106.39      6859490.84
      2651566.57      6859869.10      2651564.28      6862197.74
#Sta/Elev= 30
   432.6  364.25   592.6  366.71   706.9  364.65   962.1  351.15  1269.1  341.98
  2183.0  339.77  2183.2  339.27  2187.0  339.77  3142.6  342.19  4387.1  340.48
  4427.9  343.04  4439.9  347.60  4450.5  347.97  4490.4  341.52  4514.0  343.11
  4620.6  341.80  4766.2  343.52  4997.0  341.96  5182.1  344.02  5585.0  343.51
  5647.6  342.13  5743.6  343.43  7001.1  348.02  7421.1  355.44  7641.1  362.23
  7711.1  361.51  7741.1  359.17  7817.1  361.59  7841.1  360.63  7987.8  365.09
#Mann=8,-1,0
   432.6    0.05       0  2183.0    0.07       0  2187.0    0.05       0
  4997.0    0.12       0  5182.1    0.05       0  5585.0    0.12       0
  5743.6    0.05       0  7817.1    0.12       0
Bank Sta=2183,2187
Exp/Cntr=0.3,0.1

Chan Stop Cuts=-1