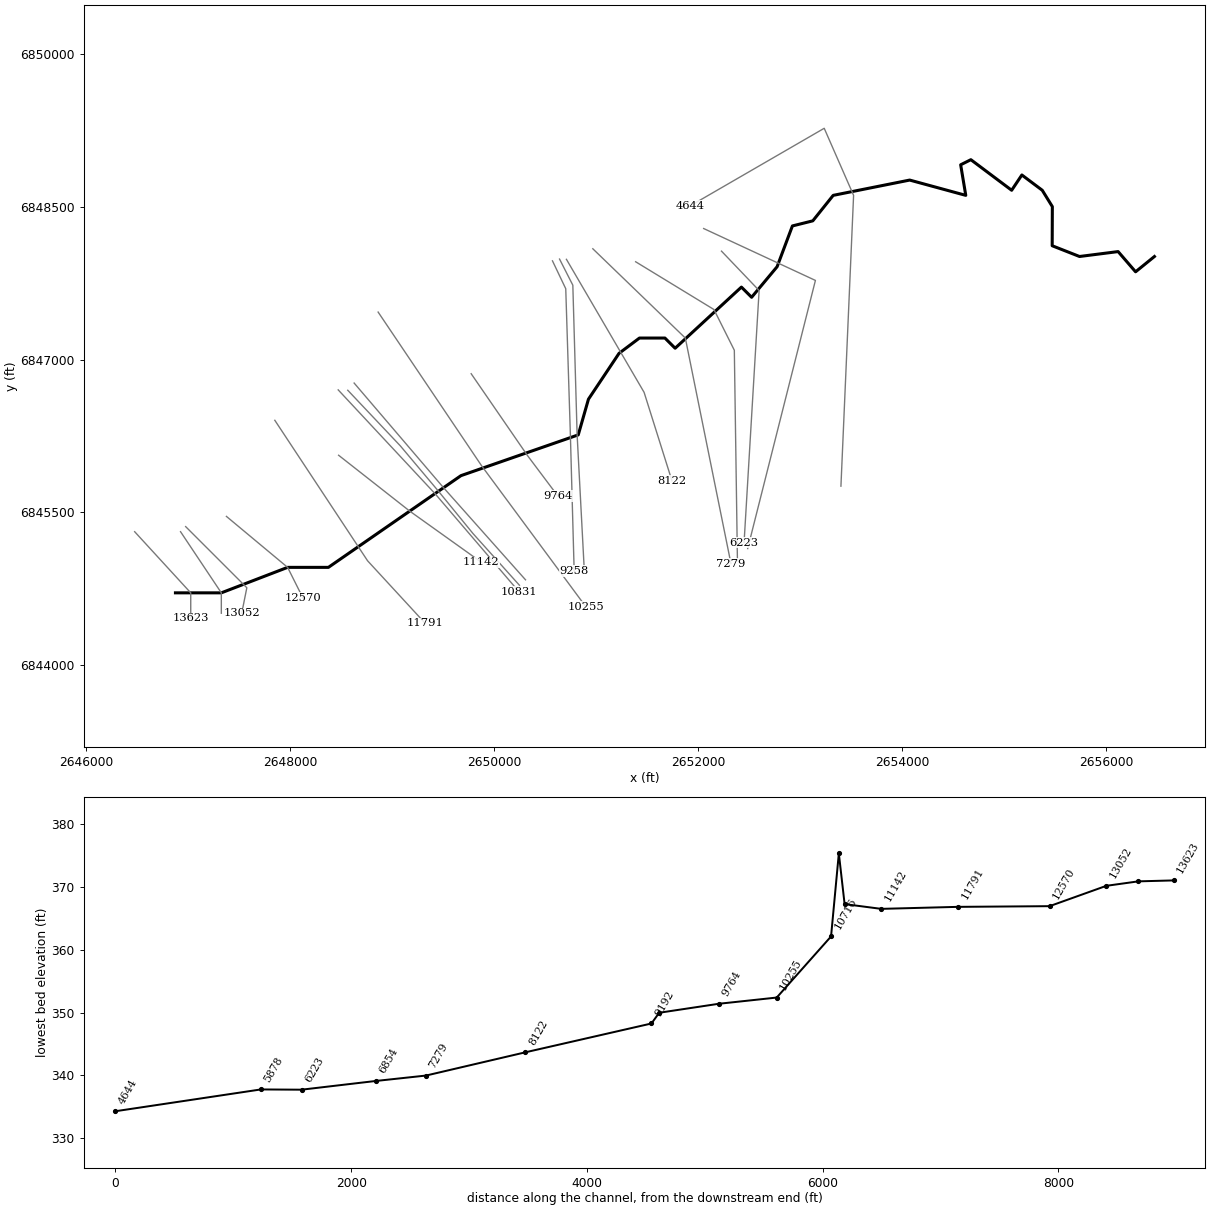
--- Kings Creek 29.prj (project) ---

Proj Title=Kings Creek 29 Base Level Engineering
Current Plan=p01
Default Exp/Contr=0.3,0.1
English Units
Geom File=g01
Flow File=f01
Plan File=p01
BEGIN DESCRIPTION:
Kings Creek 29
END DESCRIPTION:

--- Kings Creek 29.p01 (plan) ---

Plan Title=Multiple Run
Short Identifier=Multiple
Geom File=g01
Flow File=f01
Subcritical Flow
K Sum by GR= 0
Std Step Tol= 0.01
Critical Tol= 0.01
Num of Std Step Trials= 20
Max Error Tol= 0.3
Flow Tol Ratio= 0.001
Split Flow NTrial= 30
Split Flow Tol= 0.02
Split Flow Ratio= 0.02
Log Output Level= 0
Friction Slope Method= 1
Unsteady Friction Slope Method= 2
Unsteady Bridges Friction Slope Method= 1
Parabolic Critical Depth
Global Vel Dist=  1 , 1 , 1
Global Log Level= 0
CheckData=True
Encroach Param= -1, 0, 0, 0
BEGIN DESCRIPTION:
Multiple Run
END DESCRIPTION:

--- Kings Creek 29.f01 (steady flow) ---

Flow Title=Multiple
Number of Profiles=7
Profile Names=10-year,25-year,50-year,1pct_min,100-year,1pct_plu,500-year
River Rch & RM= Kings Creek 29,Reach-1,13623
     730    1008    1239     757    1510    3013    2242
River Rch & RM= Kings Creek 29,Reach-1,11791
     868    1208    1492     915    1825    3642    2731
River Rch & RM= Kings Creek 29,Reach-1,10716
    1074    1501    1860    1141    2276    4542    3414
Boundary for River Rch & Prof#=Kings Creek 29,Reach-1,1
Up Type=0
Dn Type=3
Dn Slope=0.005
Boundary for River Rch & Prof#=Kings Creek 29,Reach-1,2
Up Type=0
Dn Type=3
Dn Slope=0.005
Boundary for River Rch & Prof#=Kings Creek 29,Reach-1,3
Up Type=0
Dn Type=3
Dn Slope=0.005
Boundary for River Rch & Prof#=Kings Creek 29,Reach-1,4
Up Type=0
Dn Type=3
Dn Slope=0.005
Boundary for River Rch & Prof#=Kings Creek 29,Reach-1,5
Up Type=0
Dn Type=3
Dn Slope=0.005
Boundary for River Rch & Prof#=Kings Creek 29,Reach-1,6
Up Type=0
Dn Type=3
Dn Slope=0.005
Boundary for River Rch & Prof#=Kings Creek 29,Reach-1,7
Up Type=0
Dn Type=3
Dn Slope=0.005

--- Kings Creek 29.g01 (geometry) ---

Geom Title=Existing Conditions

River Reach=Kings Creek 29,Reach-1
Reach XY= 30
      2646876.00      6844711.00      2647326.00      6844711.00
      2647976.00      6844961.00      2648376.00      6844961.00
      2649676.00      6845861.00      2650826.00      6846261.00
      2650926.00      6846611.00      2651226.00      6847061.00
      2651426.00      6847211.00      2651676.00      6847211.00
      2651776.00      6847111.00      2652426.00      6847711.00
      2652526.00      6847611.00      2652776.00      6847911.00
      2652926.00      6848311.00      2653126.00      6848361.00
      2653326.00      6848611.00      2654076.00      6848761.00
      2654626.00      6848611.00      2654576.00      6848911.00
      2654676.00      6848961.00      2655076.00      6848661.00
      2655176.00      6848811.00      2655376.00      6848661.00
      2655474.96      6848500.56      2655473.41      6848116.71
      2655741.42      6848011.15      2656119.98      6848059.39
      2656291.21      6847860.89      2656476.00      6848011.00

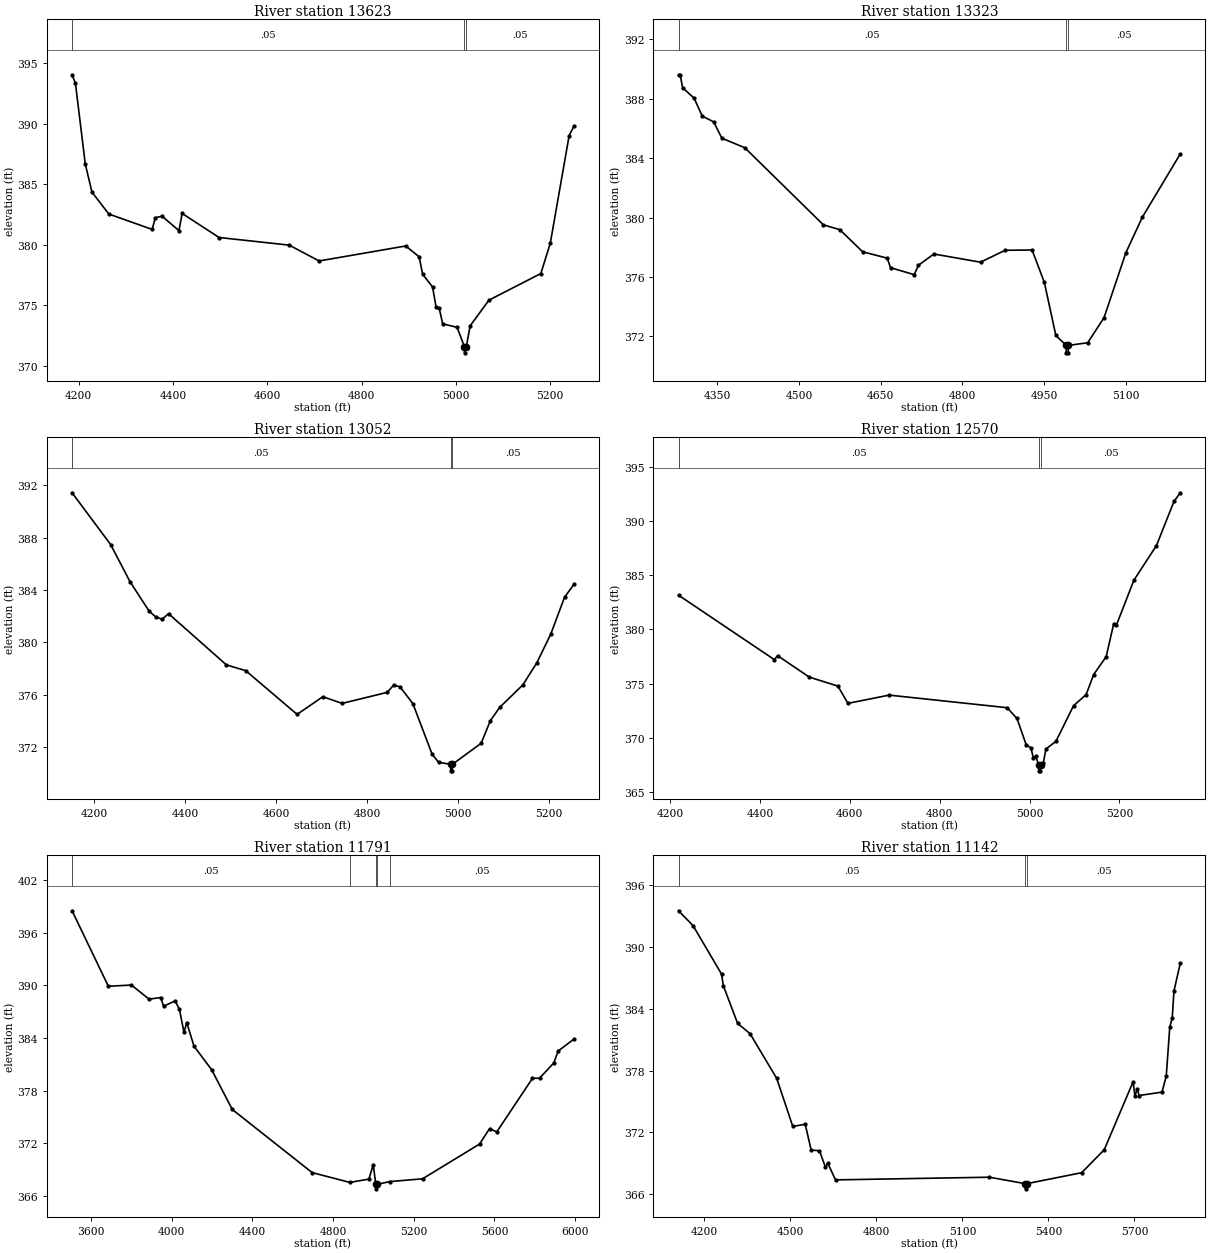
Type RM Length L Ch R = 1,13623,300,300,300
BEGIN DESCRIPTION:
Kings Creek 29 20.0
END DESCRIPTION:
XS GIS Cut Line= 3
      2646476.03      6845310.97      2647026.00      6844711.00
      2647026.00      6844461.00
#Sta/Elev= 30
  4186.1  394.05  4193.2  393.35  4214.1  386.67  4228.3  384.34  4264.1  382.53
  4355.9  381.26  4362.7  382.23  4376.9  382.35  4412.7  381.16  4419.5  382.58
  4497.8  380.59  4646.4  379.96  4709.9  378.65  4893.6  379.89  4922.0  378.99
  4929.4  377.55  4950.4  376.50  4957.8  374.85  4964.5  374.74  4971.9  373.45
  5002.5  373.16  5018.0  371.55  5018.2  371.05  5022.0  371.55  5030.0  373.28
  5070.0  375.41  5180.0  377.61  5200.0  380.11  5240.0  389.02  5250.0  389.79
#Mann=3,-1,0
  4186.1    0.05       0  5018.0    0.04       0  5022.0    0.05       0
Bank Sta=5018,5022
Exp/Cntr=0.3,0.1

Type RM Length L Ch R = 1,13323,271,271,271
BEGIN DESCRIPTION:
Kings Creek 29 19.0
END DESCRIPTION:
XS GIS Cut Line= 3
      2646926.01      6845310.99      2647326.00      6844711.00
      2647326.00      6844511.00
#Sta/Elev= 30
  4278.9  389.61  4281.9  389.61  4286.4  388.74  4307.4  388.04  4322.5  386.83
  4343.5  386.44  4358.5  385.34  4400.6  384.70  4544.8  379.51  4574.8  379.19
  4616.9  377.70  4662.0  377.27  4668.0  376.63  4711.6  376.16  4719.1  376.79
  4747.6  377.55  4833.2  377.00  4878.3  377.80  4927.9  377.82  4950.4  375.64
  4971.5  372.07  4990.5  371.40  4990.7  370.90  4994.2  370.90  4994.5  371.40
  5030.0  371.58  5060.0  373.27  5100.0  377.63  5130.0  380.01  5200.0  384.29
#Mann=3,-1,0
  4278.9    0.05       0  4990.5    0.04       0  4994.5    0.05       0
Bank Sta=4990.5,4994.5
Exp/Cntr=0.3,0.1

Type RM Length L Ch R = 1,13052,482,482,482
BEGIN DESCRIPTION:
Kings Creek 29 18.0
END DESCRIPTION:
XS GIS Cut Line= 3
      2646976.02      6845360.98      2647576.00      6844761.00
      2647525.99      6844510.95
#Sta/Elev= 30
  4151.5  391.42  4236.3  387.47  4278.8  384.64  4321.2  382.37  4335.3  381.95
  4349.5  381.76  4363.6  382.19  4490.9  378.28  4533.3  377.84  4646.4  374.50
  4703.0  375.85  4745.4  375.34  4844.4  376.18  4858.6  376.73  4872.7  376.60
  4901.0  375.32  4943.4  371.45  4957.6  370.84  4983.9  370.69  4984.1  370.19
  4987.6  370.19  4987.9  370.69  5051.0  372.29  5071.4  374.02  5091.8  375.03
  5142.8  376.75  5173.4  378.43  5204.0  380.61  5234.6  383.45  5255.0  384.42
#Mann=3,-1,0
  4151.5    0.05       0  4983.9    0.04       0  4987.9    0.05       0
Bank Sta=4983.9,4987.9
Exp/Cntr=0.3,0.1

Type RM Length L Ch R = 1,12570,779,779,779
BEGIN DESCRIPTION:
Kings Creek 29 17.0
END DESCRIPTION:
XS GIS Cut Line= 3
      2647376.02      6845460.98      2647976.00      6844961.00
      2648126.00      6844661.01
#Sta/Elev= 30
  4219.0  383.14  4431.8  377.21  4439.6  377.56  4509.9  375.59  4573.7  374.76
  4595.8  373.17  4687.6  373.93  4949.9  372.77  4972.0  371.78  4992.8  369.31
  5002.8  369.09  5008.4  368.15  5014.0  368.29  5020.4  367.45  5020.6  366.95
  5024.1  366.95  5024.4  367.45  5030.7  367.69  5036.3  368.96  5058.7  369.67
  5097.8  372.95  5125.8  373.98  5142.5  375.82  5170.5  377.48  5187.3  380.53
  5192.9  380.35  5232.0  384.51  5282.3  387.72  5321.4  391.79  5335.4  392.58
#Mann=3,-1,0
  4219.0    0.05       0  5020.4    0.04       0  5024.4    0.05       0
Bank Sta=5020.4,5024.4
Exp/Cntr=0.3,0.1

Type RM Length L Ch R = 1,11791,649,649,649
BEGIN DESCRIPTION:
Kings Creek 29 15.0
END DESCRIPTION:
XS GIS Cut Line= 3
      2647850.47      6846403.94      2648760.21      6845025.45
      2649326.01      6844410.99
#Sta/Elev= 30
  3507.0  398.48  3686.9  389.89  3801.2  390.03  3888.6  388.42  3945.8  388.61
  3960.8  387.63  4018.0  388.22  4039.1  387.26  4061.7  384.65  4075.2  385.76
  4111.3  383.07  4198.6  380.40  4301.0  375.87  4696.7  368.69  4883.7  367.57
  4978.4  367.95  4999.4  369.60  5012.5  367.34  5012.8  366.84  5016.5  367.34
  5083.2  367.67  5243.9  367.98  5526.9  371.94  5576.2  373.69  5611.9  373.32
  5788.9  379.42  5824.0  379.43  5894.9  381.18  5915.9  382.52  5993.9  383.87
#Mann=5,-1,0
  3507.0    0.05       0  4883.7     0.1       0  5012.5    0.07       0
  5016.5     0.1       0  5083.2    0.05       0
Bank Sta=5012.5,5016.5
Exp/Cntr=0.3,0.1

Type RM Length L Ch R = 1,11142,311,311,311
BEGIN DESCRIPTION:
Kings Creek 29 14.0
END DESCRIPTION:
XS GIS Cut Line= 3
      2648476.02      6846060.98      2649176.00      6845511.00
      2649875.97      6845011.02
#Sta/Elev= 30
  4109.8  393.54  4160.4  392.10  4259.8  387.39  4266.1  386.26  4315.9  382.60
  4359.2  381.60  4452.3  377.25  4508.4  372.58  4551.7  372.80  4572.5  370.28
  4601.4  370.23  4622.2  368.63  4630.3  369.01  4657.5  367.39  5194.2  367.65
  5319.9  367.02  5320.2  366.52  5324.1  367.02  5516.1  368.09  5594.8  370.32
  5695.6  376.93  5701.7  375.57  5710.3  376.20  5716.5  375.59  5796.3  375.92
  5811.1  377.48  5823.4  382.23  5832.0  383.15  5838.1  385.76  5860.2  388.46
#Mann=3,-1,0
  4109.8    0.05       0  5319.9    0.03       0  5324.1    0.05       0
Bank Sta=5319.9,5324.1
Exp/Cntr=0.3,0.1

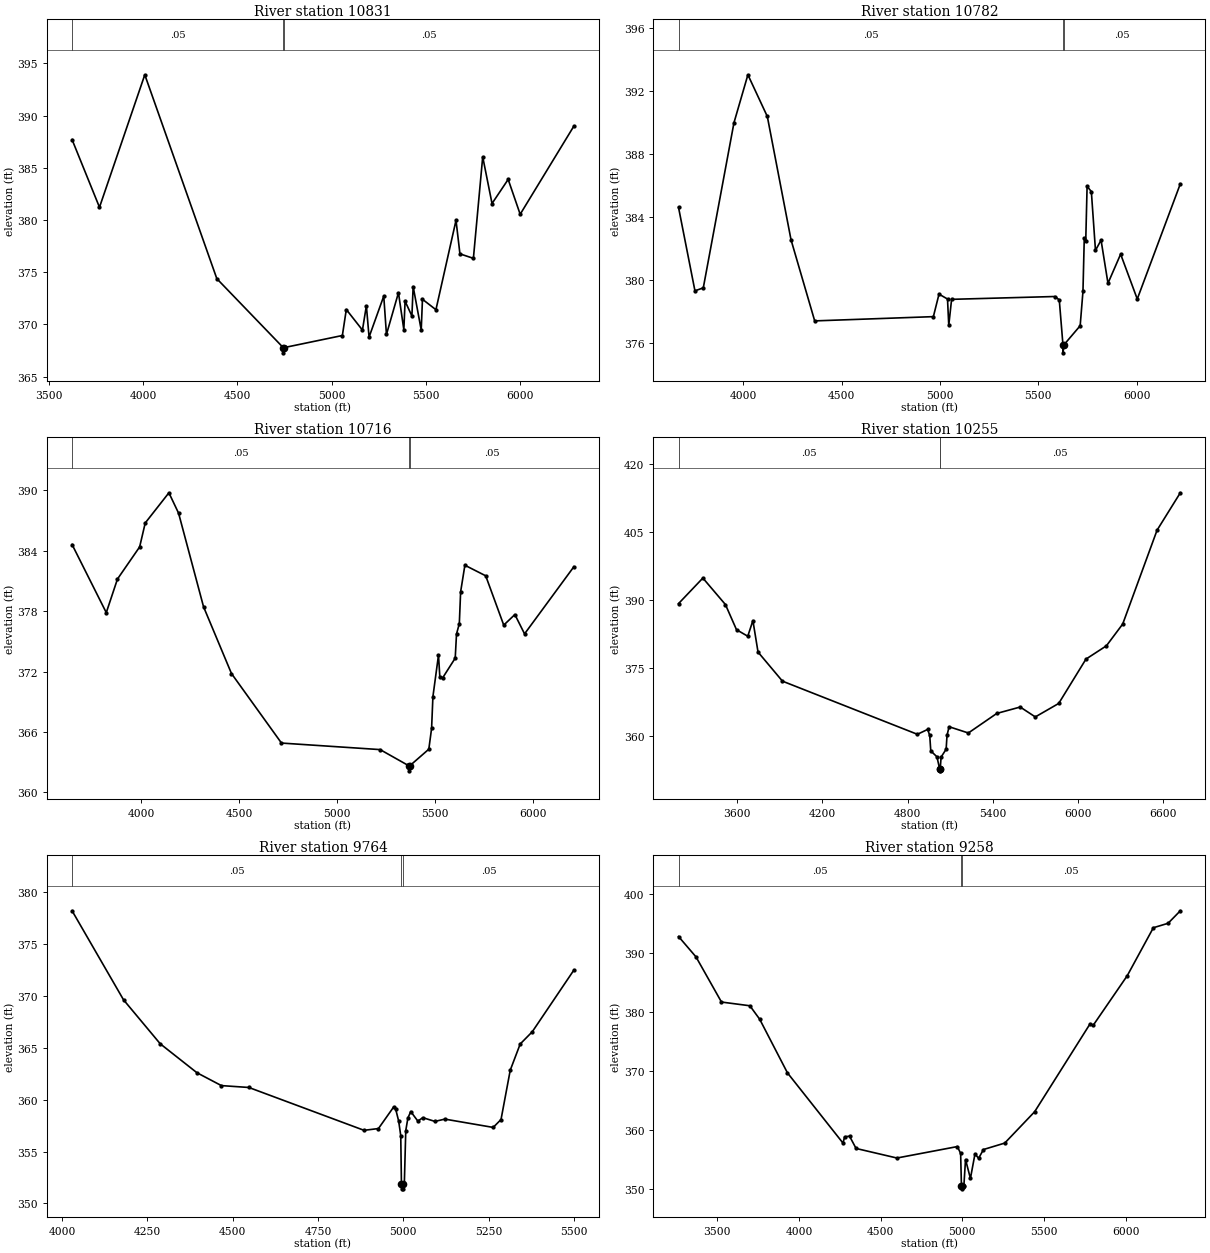
Type RM Length L Ch R = 1,10831,49,49,49
BEGIN DESCRIPTION:
Kings Creek 29 21.0
END DESCRIPTION:
XS GIS Cut Line= 3
      2648472.04      6846702.51      2649425.44      6845679.84
      2650246.31      6844719.91
#Sta/Elev= 30
  3623.5  387.70  3768.9  381.22  4009.2  393.91  4391.3  374.38  4743.4  367.78
  4743.7  367.28  4747.6  367.78  5057.0  368.94  5077.9  371.43  5163.5  369.46
  5184.3  371.79  5198.6  368.79  5276.5  372.71  5290.8  369.04  5354.5  373.04
  5383.0  369.50  5389.6  372.22  5425.8  370.81  5432.4  373.63  5475.2  369.47
  5481.8  372.41  5553.2  371.41  5659.7  379.97  5680.5  376.76  5751.9  376.33
  5801.3  386.05  5850.7  381.58  5936.3  383.89  6000.0  380.55  6284.7  388.99
#Mann=3,-1,0
  3623.5    0.05       0  4743.4    0.04       0  4747.6    0.05       0
Bank Sta=4743.4,4747.6
Exp/Cntr=0.3,0.1

Type RM Length L Ch R = 1,10782,66,66,66
BEGIN DESCRIPTION:
Kings Creek 29 13.0
END DESCRIPTION:
XS GIS Cut Line= 5
      2648565.79      6846698.74      2649080.82      6846153.53
      2649452.78      6845711.00      2649793.50      6845293.29
      2650249.18      6844785.39
#Sta/Elev= 30
  3671.9  384.59  3755.3  379.29  3797.7  379.48  3953.5  389.97  4024.3  393.02
  4123.0  390.37  4243.5  382.53  4363.7  377.38  4966.7  377.65  4995.3  379.08
  5038.5  378.77  5044.9  377.10  5059.3  378.75  5584.7  378.93  5606.4  378.71
  5625.1  375.85  5625.5  375.35  5629.4  375.85  5712.5  377.07  5726.7  379.25
  5733.4  382.65  5740.9  382.48  5747.7  385.93  5769.3  385.60  5790.3  381.86
  5818.7  382.51  5853.8  379.77  5918.1  381.62  6002.6  378.77  6221.4  386.09
#Mann=3,-1,0
  3671.9    0.05       0  5625.1    0.04       0  5629.4    0.05       0
Bank Sta=5625.1,5629.4
Exp/Cntr=0.3,0.1

Type RM Length L Ch R = 1,10716,461,461,461
BEGIN DESCRIPTION:
Kings Creek 29 16.0
END DESCRIPTION:
XS GIS Cut Line= 3
      2648628.26      6846769.38      2649500.15      6845748.18
      2650308.83      6844838.81
#Sta/Elev= 30
  3648.0  384.62  3822.5  377.85  3879.6  381.19  3992.7  384.38  4021.2  386.76
  4142.0  389.76  4191.4  387.73  4318.7  378.43  4461.1  371.80  4716.2  364.89
  5219.5  364.24  5366.2  362.63  5366.5  362.13  5370.5  362.63  5467.8  364.28
  5482.0  366.35  5488.7  369.50  5517.2  373.63  5523.9  371.49  5538.1  371.36
  5602.5  373.33  5609.1  375.73  5623.4  376.75  5630.1  379.92  5651.8  382.56
  5758.0  381.51  5850.0  376.61  5906.8  377.66  5956.2  375.74  6207.7  382.41
#Mann=3,-1,0
  3648.0    0.05       0  5366.2    0.04       0  5370.5    0.05       0
Bank Sta=5366.2,5370.5
Exp/Cntr=0.3,0.1

Type RM Length L Ch R = 1,10255,491,491,491
BEGIN DESCRIPTION:
Kings Creek 29 12.0
END DESCRIPTION:
XS GIS Cut Line= 3
      2648863.57      6847465.82      2649876.00      6845961.00
      2650899.57      6844575.73
#Sta/Elev= 30
  3186.3  389.25  3357.8  394.88  3516.8  389.04  3594.8  383.50  3674.2  382.06
  3710.4  385.51  3746.5  378.57  3918.7  372.16  4869.5  360.45  4941.5  361.52
  4956.5  360.21  4963.8  356.80  5007.3  355.49  5025.8  352.90  5026.3  352.40
  5030.5  352.90  5036.6  355.43  5072.1  357.17  5078.3  360.22  5092.9  362.12
  5228.6  360.74  5429.0  365.05  5594.0  366.46  5700.4  364.28  5865.4  367.25
  6057.4  377.02  6201.5  379.95  6316.4  384.75  6558.5  405.43  6722.4  413.67
#Mann=3,-1,0
  3186.3    0.05       0  5025.8    0.04       0  5030.5    0.05       0
Bank Sta=5025.8,5030.5
Exp/Cntr=0.3,0.1

Type RM Length L Ch R = 1,9764,506,506,506
BEGIN DESCRIPTION:
Kings Creek 29 11.0
END DESCRIPTION:
XS GIS Cut Line= 3
      2649776.01      6846860.98      2650326.00      6846061.00
      2650626.00      6845661.00
#Sta/Elev= 30
  4029.2  378.21  4180.0  369.63  4287.6  365.39  4395.2  362.60  4466.9  361.36
  4547.4  361.18  4885.0  357.05  4927.2  357.22  4971.6  359.29  4977.7  359.10
  4986.5  357.94  4992.6  356.54  4994.6  351.91  4995.1  351.41  4998.8  351.41
  4999.3  351.91  5003.1  351.91  5007.3  357.02  5013.5  358.23  5021.9  358.86
  5042.7  357.94  5057.3  358.27  5092.7  357.91  5121.9  358.13  5263.5  357.33
  5286.5  358.09  5313.5  362.84  5342.7  365.37  5378.1  366.55  5500.0  372.49
#Mann=3,-1,0
  4029.2    0.05       0  4994.6    0.04       0  4999.3    0.05       0
Bank Sta=4994.6,4999.3
Exp/Cntr=0.3,0.1

Type RM Length L Ch R = 1,9258,66,66,66
BEGIN DESCRIPTION:
Mapping XS 94100101
END DESCRIPTION:
XS GIS Cut Line= 4
      2650573.13      6847968.46      2650703.33      6847695.04
      2650748.76      6846261.00      2650785.80      6844926.01
#Sta/Elev= 30
  3262.4  392.72  3369.3  389.27  3525.4  381.62  3699.3  380.99  3759.4  378.71
  3929.5  369.62  4269.6  357.73  4279.6  358.79  4309.7  358.90  4349.7  356.82
  4599.8  355.20  4970.0  357.14  4990.0  355.98  4995.0  350.48  4995.6  349.98
  4999.9  350.48  5010.0  350.53  5020.0  354.94  5050.0  351.74  5077.9  355.90
  5100.0  355.15  5130.0  356.64  5260.1  357.73  5443.3  363.04  5780.3  377.82
  5803.6  377.75  6010.4  386.08  6170.4  394.21  6260.5  394.96  6335.5  397.08
#Mann=3,-1,0
  3262.4    0.05       0  4995.0    0.04       0  4999.9    0.05       0
Bank Sta=4995,4999.9
Exp/Cntr=0.3,0.1

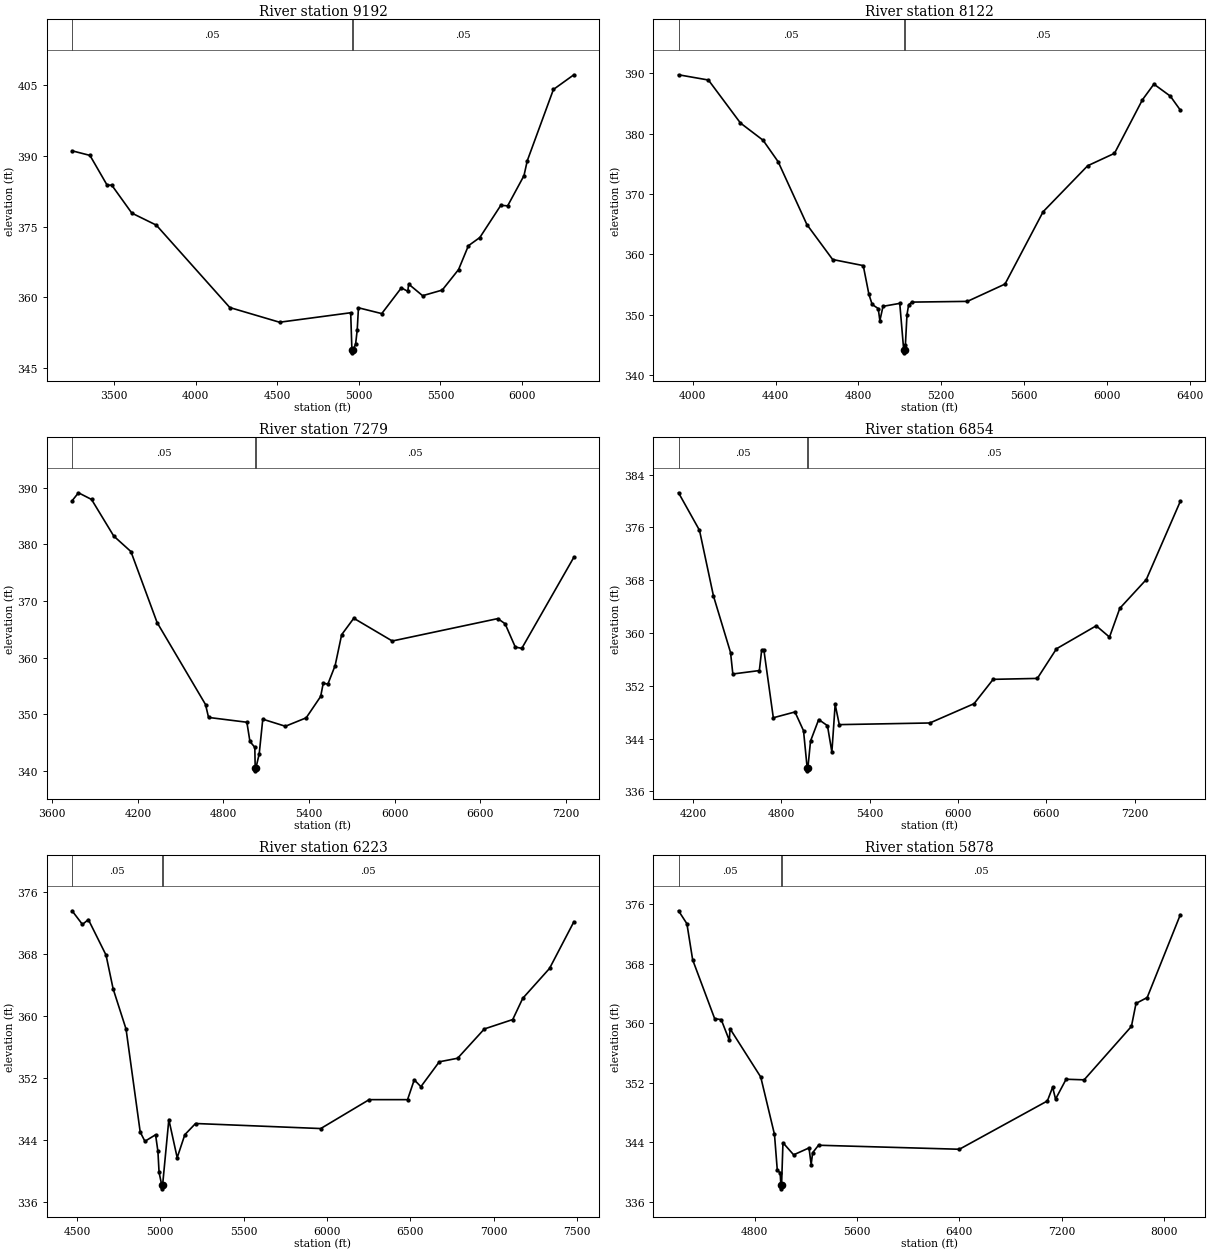
Type RM Length L Ch R = 1,9192,1070,1070,1070
BEGIN DESCRIPTION:
Mapping XS bb827ea5
END DESCRIPTION:
XS GIS Cut Line= 4
      2650642.59      6847985.80      2650772.78      6847729.76
      2650814.95      6846261.00      2650884.39      6844945.93
#Sta/Elev= 30
  3243.4  391.05  3352.8  390.08  3458.4  383.76  3486.3  383.79  3609.4  377.86
  3759.5  375.31  4209.7  357.86  4514.4  354.75  4950.0  356.76  4957.5  348.77
  4958.1  348.27  4962.4  348.77  4980.0  350.08  4990.0  353.13  4997.5  357.81
  5140.2  356.58  5260.4  362.03  5299.9  361.29  5304.9  362.83  5390.5  360.37
  5510.7  361.56  5610.8  365.91  5670.9  370.95  5741.0  372.69  5869.7  379.52
  5911.3  379.39  6011.4  385.79  6031.4  388.93  6191.7  404.04  6316.9  407.15
#Mann=3,-1,0
  3243.4    0.05       0  4957.5    0.04       0  4962.4    0.05       0
Bank Sta=4957.5,4962.4
Exp/Cntr=0.3,0.1

Type RM Length L Ch R = 1,8122,843,843,843
BEGIN DESCRIPTION:
Kings Creek 29 8.0
END DESCRIPTION:
XS GIS Cut Line= 3
      2650709.95      6847983.49      2651471.67      6846678.32
      2651745.29      6845809.26
#Sta/Elev= 30
  3931.9  389.77  4076.2  388.90  4230.8  381.77  4340.0  378.92  4412.7  375.36
  4551.6  364.94  4675.8  359.15  4823.6  358.14  4850.9  353.38  4866.6  351.70
  4895.8  351.02  4903.8  349.02  4919.0  351.39  4999.8  351.88  5018.8  344.18
  5019.4  343.68  5023.8  344.18  5027.0  344.98  5034.7  350.01  5042.7  351.63
  5057.9  352.09  5326.4  352.21  5507.9  355.08  5691.9  367.07  5906.9  374.69
  6036.4  376.75  6171.2  385.62  6226.6  388.22  6305.9  386.23  6354.2  383.91
#Mann=3,-1,0
  3931.9    0.05       0  5018.8    0.04       0  5023.8    0.05       0
Bank Sta=5018.8,5023.8
Exp/Cntr=0.3,0.1

Type RM Length L Ch R = 1,7279,425,425,425
BEGIN DESCRIPTION:
Kings Creek 29 7.0
END DESCRIPTION:
XS GIS Cut Line= 3
      2650968.75      6848087.08      2651876.00      6847211.00
      2652323.36      6844998.27
#Sta/Elev= 30
  3738.8  387.71  3783.6  389.13  3875.4  387.95  4031.1  381.48  4151.5  378.74
  4335.1  366.19  4674.7  351.70  4695.8  349.42  4964.6  348.57  4986.0  345.18
  5020.3  344.13  5022.9  340.48  5023.5  339.98  5027.9  340.48  5051.0  342.96
  5076.1  349.11  5234.7  347.86  5380.5  349.35  5482.0  353.13  5499.9  355.45
  5532.7  355.32  5583.5  358.59  5629.1  364.04  5714.2  366.95  5984.3  362.93
  6724.2  366.89  6775.2  365.98  6846.8  361.86  6892.4  361.63  7257.5  377.73
#Mann=3,-1,0
  3738.8    0.05       0  5022.9    0.04       0  5027.9    0.05       0
Bank Sta=5022.9,5027.9
Exp/Cntr=0.3,0.1

Type RM Length L Ch R = 1,6854,631,631,631
BEGIN DESCRIPTION:
Mapping XS a357cae3
END DESCRIPTION:
XS GIS Cut Line= 4
      2651388.61      6847959.56      2652156.82      6847490.82
      2652356.47      6847091.52      2652386.86      6845029.90
#Sta/Elev= 30
  4100.8  381.24  4243.1  375.56  4338.0  365.61  4454.1  357.04  4469.6  353.79
  4649.7  354.31  4665.2  357.35  4680.6  357.40  4744.6  347.16  4891.6  348.04
  4949.7  345.20  4974.2  339.62  4974.9  339.12  4979.6  339.62  4997.3  343.63
  5052.8  346.89  5112.3  345.96  5142.3  341.97  5164.6  349.19  5192.6  346.12
  5807.7  346.37  6107.8  349.29  6237.8  352.98  6537.8  353.12  6667.8  357.61
  6937.8  361.09  7027.9  359.38  7097.9  363.74  7277.9  368.10  7509.0  379.95
#Mann=3,-1,0
  4100.8    0.05       0  4974.2    0.03       0  4979.6    0.05       0
Bank Sta=4974.2,4979.6
Exp/Cntr=0.3,0.1

Type RM Length L Ch R = 1,6223,345,345,345
BEGIN DESCRIPTION:
Mapping XS 85acca20
END DESCRIPTION:
XS GIS Cut Line= 3
      2652230.57      6848063.78      2652599.53      6847677.46
      2652452.03      6845204.75
#Sta/Elev= 30
  4470.8  373.52  4533.1  371.76  4568.6  372.39  4674.6  367.82  4717.1  363.48
  4794.8  358.29  4879.7  345.04  4908.0  343.85  4971.9  344.69  4986.0  342.55
  4992.9  339.85  5008.8  338.23  5009.5  337.73  5014.2  338.23  5051.5  346.65
  5101.6  341.74  5147.5  344.70  5211.8  346.14  5963.2  345.49  6253.7  349.21
  6484.1  349.21  6524.2  351.76  6564.2  350.88  6674.4  354.08  6784.6  354.54
  6944.9  358.31  7115.2  359.52  7175.3  362.25  7336.1  366.10  7482.1  372.10
#Mann=3,-1,0
  4470.8    0.05       0  5008.8    0.03       0  5014.2    0.05       0
Bank Sta=5008.8,5014.2
Exp/Cntr=0.3,0.1

Type RM Length L Ch R = 1,5878,1234,1234,1234
BEGIN DESCRIPTION:
Kings Creek 29 6.0
END DESCRIPTION:
XS GIS Cut Line= 3
      2652055.91      6848285.48      2653151.64      6847776.44
      2652487.44      6845145.49
#Sta/Elev= 30
  4206.0  375.14  4271.4  373.40  4316.4  368.55  4488.4  360.64  4539.7  360.51
  4602.9  357.72  4608.4  359.29  4848.4  352.80  4955.9  345.08  4977.9  340.26
  5000.0  339.93  5005.9  338.27  5006.7  337.77  5011.3  338.27  5022.1  343.97
  5105.7  342.34  5225.7  343.27  5242.6  341.04  5254.1  342.62  5299.9  343.63
  6401.0  343.09  7088.6  349.58  7129.7  351.43  7152.5  349.83  7235.0  352.50
  7376.0  352.42  7745.5  359.60  7781.4  362.69  7868.7  363.48  8127.7  374.61
#Mann=3,-1,0
  4206.0    0.05       0  5005.9    0.03       0  5011.3    0.05       0
Bank Sta=5005.9,5011.3
Exp/Cntr=0.3,0.1

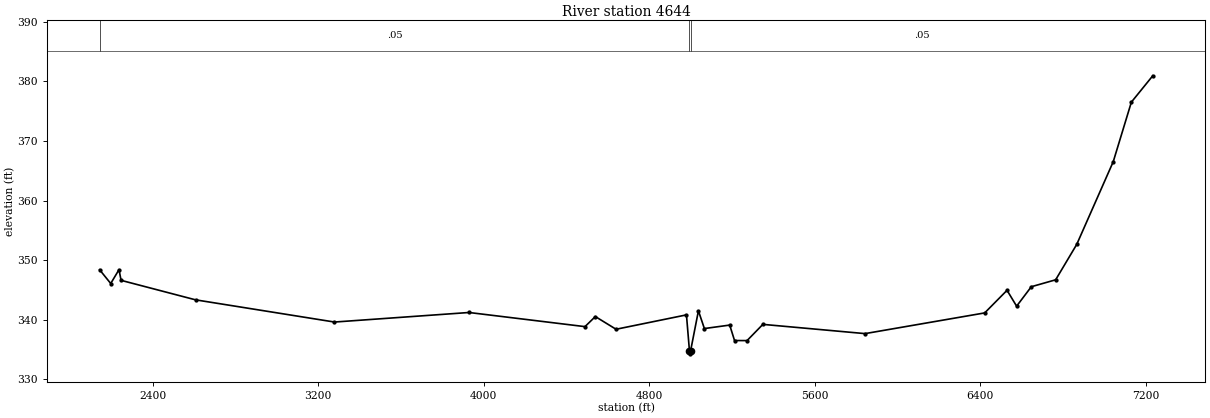
Type RM Length L Ch R = 1,4644,0,0,0
BEGIN DESCRIPTION:
Kings Creek 29 2.0
END DESCRIPTION:
XS GIS Cut Line= 4
      2653401.85      6845757.50      2653526.00      6848611.00
      2653237.92      6849269.08      2651926.51      6848509.84
#Sta/Elev= 30
  2143.8  348.39  2197.4  346.09  2237.4  348.41  2247.4  346.62  2607.7  343.35
  3278.9  339.63  3929.0  341.23  4489.5  338.86  4539.6  340.55  4639.7  338.42
  4980.0  340.83  4994.5  334.80  4995.3  334.30  5000.0  334.80  5037.8  341.51
  5066.6  338.54  5189.0  339.12  5212.4  336.53  5272.9  336.52  5349.3  339.24
  5843.1  337.69  6421.4  341.16  6529.4  344.95  6575.7  342.29  6646.7  345.55
  6764.3  346.71  6866.2  352.64  7042.7  366.51  7130.3  376.49  7233.7  380.91
#Mann=3,-1,0
  2143.8    0.05       0  4994.5    0.03       0  5000.0    0.05       0
Bank Sta=4994.5,5000
Exp/Cntr=0.3,0.1

Chan Stop Cuts=-1