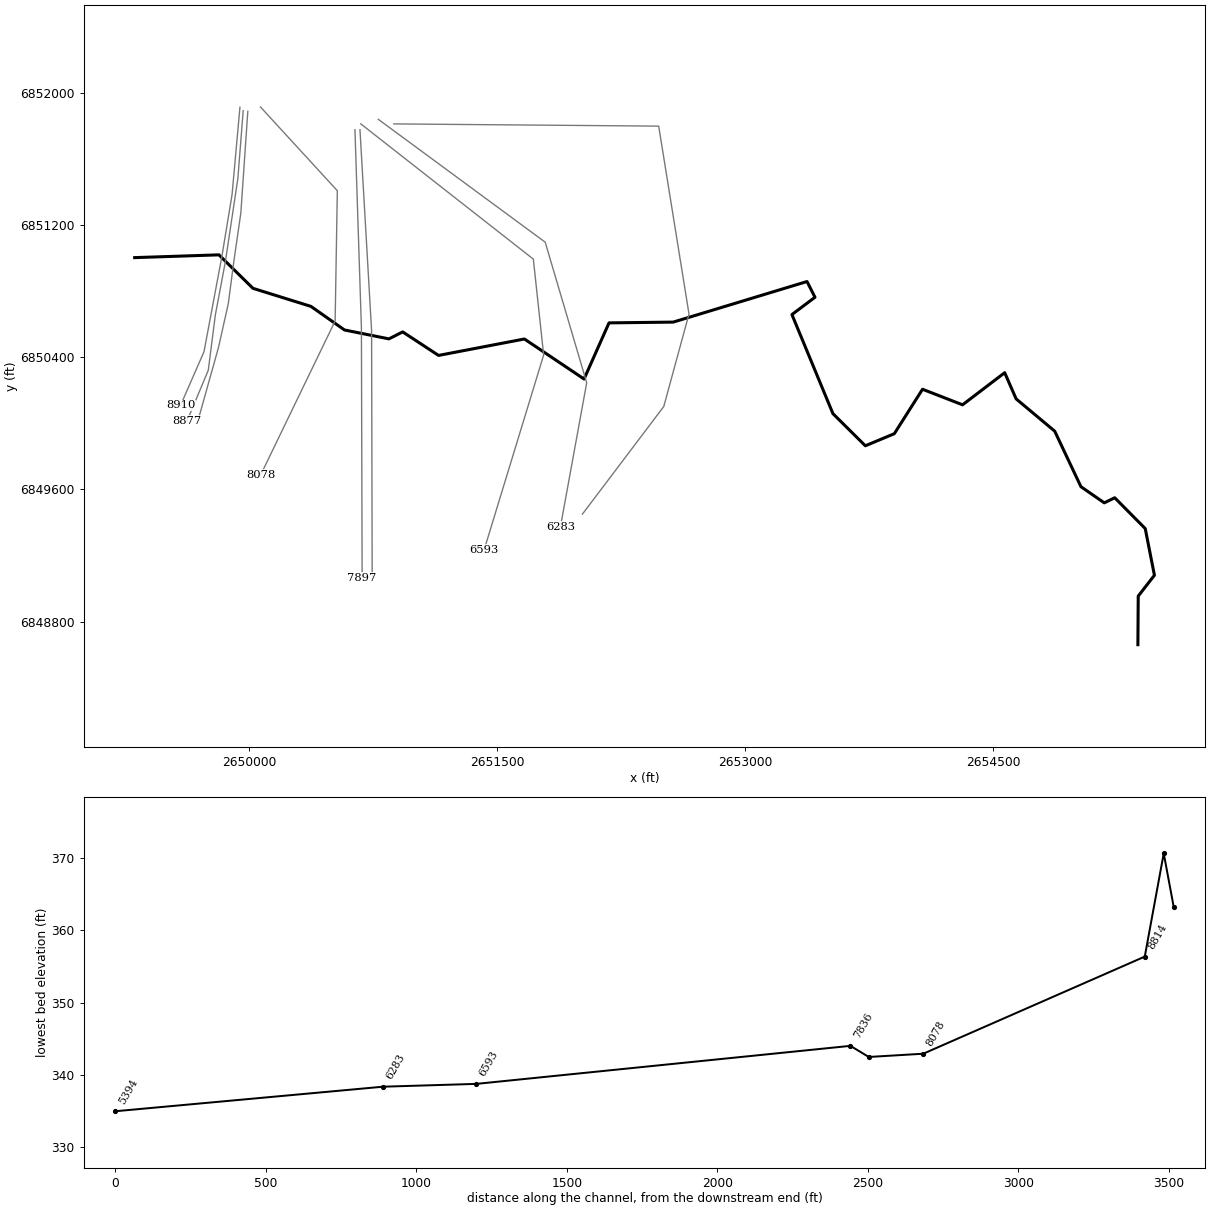
--- Kings Creek 29_1.prj (project) ---

Proj Title=Kings Creek 29_1 Base Level Engineering
Current Plan=p01
Default Exp/Contr=0.3,0.1
English Units
Geom File=g01
Flow File=f01
Plan File=p01
BEGIN DESCRIPTION:
Kings Creek 29_1
END DESCRIPTION:

--- Kings Creek 29_1.p01 (plan) ---

Plan Title=Multiple Run
Short Identifier=Multiple
Geom File=g01
Flow File=f01
Subcritical Flow
K Sum by GR= 0
Std Step Tol= 0.01
Critical Tol= 0.01
Num of Std Step Trials= 20
Max Error Tol= 0.3
Flow Tol Ratio= 0.001
Split Flow NTrial= 30
Split Flow Tol= 0.02
Split Flow Ratio= 0.02
Log Output Level= 0
Friction Slope Method= 1
Unsteady Friction Slope Method= 2
Unsteady Bridges Friction Slope Method= 1
Parabolic Critical Depth
Global Vel Dist=  1 , 1 , 1
Global Log Level= 0
CheckData=True
Encroach Param= -1, 0, 0, 0
BEGIN DESCRIPTION:
Multiple Run
END DESCRIPTION:

--- Kings Creek 29_1.f01 (steady flow) ---

Flow Title=Multiple
Number of Profiles=7
Profile Names=10-year,25-year,50-year,1pct_min,100-year,1pct_plu,500-year
River Rch & RM= Kings Creek 29_1,Reach-1,8910
     667     907    1103     665    1328    2649    1924
Boundary for River Rch & Prof#=Kings Creek 29_1,Reach-1,1
Up Type=0
Dn Type=3
Dn Slope=0.005
Boundary for River Rch & Prof#=Kings Creek 29_1,Reach-1,2
Up Type=0
Dn Type=3
Dn Slope=0.005
Boundary for River Rch & Prof#=Kings Creek 29_1,Reach-1,3
Up Type=0
Dn Type=3
Dn Slope=0.005
Boundary for River Rch & Prof#=Kings Creek 29_1,Reach-1,4
Up Type=0
Dn Type=3
Dn Slope=0.005
Boundary for River Rch & Prof#=Kings Creek 29_1,Reach-1,5
Up Type=0
Dn Type=3
Dn Slope=0.005
Boundary for River Rch & Prof#=Kings Creek 29_1,Reach-1,6
Up Type=0
Dn Type=3
Dn Slope=0.005
Boundary for River Rch & Prof#=Kings Creek 29_1,Reach-1,7
Up Type=0
Dn Type=3
Dn Slope=0.005

--- Kings Creek 29_1.g01 (geometry) ---

Geom Title=Existing Conditions

River Reach=Kings Creek 29_1,Reach-1
Reach XY= 30
      2649308.14      6851002.21      2649817.99      6851019.00
      2650023.57      6850816.52      2650374.44      6850707.24
      2650577.47      6850564.55      2650846.21      6850510.79
      2650929.31      6850552.93      2651146.16      6850410.68
      2651665.51      6850510.05      2652026.25      6850267.97
      2652177.25      6850607.55      2652565.50      6850612.22
      2653374.78      6850857.63      2653423.00      6850762.47
      2653283.53      6850657.85      2653531.52      6850058.57
      2653727.63      6849864.12      2653902.82      6849937.29
      2654073.43      6850206.05      2654315.52      6850111.93
      2654570.41      6850306.27      2654639.62      6850147.79
      2654872.84      6849952.66      2655031.62      6849616.62
      2655172.67      6849519.02      2655236.00      6849549.76
      2655420.46      6849363.37      2655476.04      6849080.99
      2655378.06      6848955.14      2655376.00      6848661.00

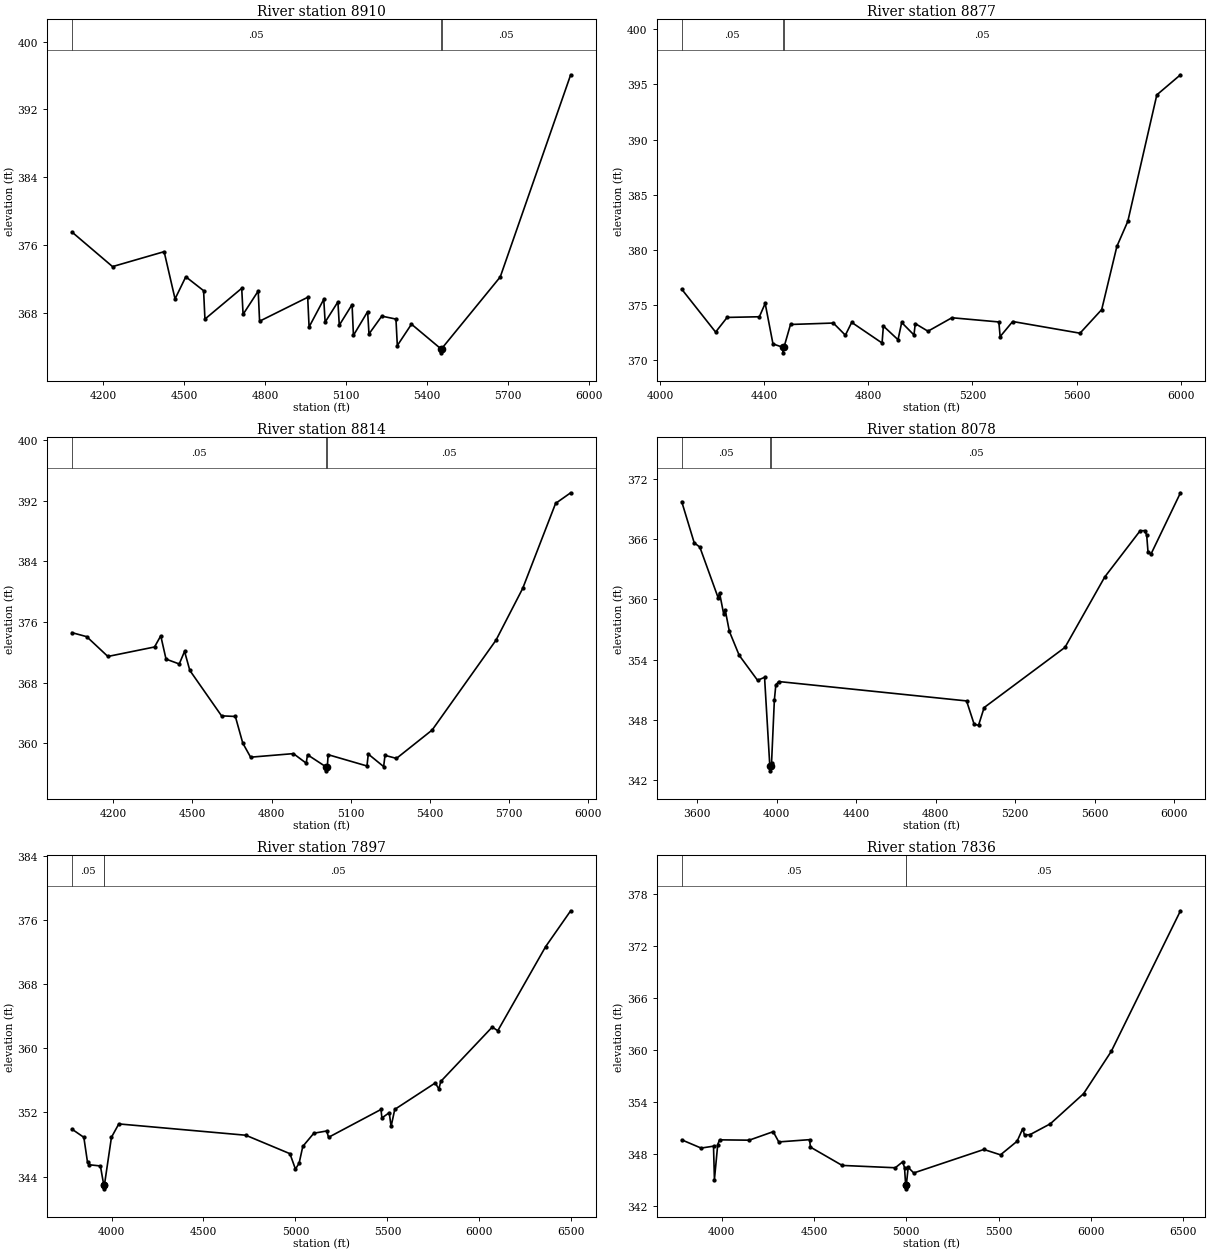
Type RM Length L Ch R = 1,8910,33,33,33
BEGIN DESCRIPTION:
Kings Creek 29_1 10.0
END DESCRIPTION:
XS GIS Cut Line= 5
      2649944.92      6851911.74      2649897.34      6851383.91
      2649835.55      6851008.40      2649727.64      6850433.39
      2649585.54      6850108.38
#Sta/Elev= 30
  4083.5  377.54  4234.2  373.46  4425.6  375.22  4466.1  369.65  4506.0  372.26
  4572.0  370.62  4577.0  367.27  4713.4  370.90  4718.5  367.83  4774.6  370.58
  4779.7  367.02  4958.2  369.84  4963.3  366.34  5017.8  369.60  5022.9  366.91
  5070.3  369.30  5075.4  366.55  5122.8  368.98  5127.9  365.35  5180.5  368.15
  5185.6  365.52  5233.0  367.62  5285.6  367.27  5290.7  364.15  5343.2  366.67
  5451.4  363.79  5451.6  363.29  5455.4  363.79  5672.5  372.24  5933.8  396.08
#Mann=3,-1,0
  4083.5    0.05       0  5451.4    0.03       0  5455.4    0.05       0
Bank Sta=5451.4,5455.4
Exp/Cntr=0.3,0.1

Type RM Length L Ch R = 1,8877,63,63,63
BEGIN DESCRIPTION:
Mapping XS b669a0ac
END DESCRIPTION:
XS GIS Cut Line= 6
      2649964.62      6851890.87      2649932.45      6851481.56
      2649857.22      6850979.76      2649796.13      6850655.37
      2649753.50      6850321.10      2649625.09      6850014.19
#Sta/Elev= 30
  4082.0  376.45  4212.3  372.56  4256.6  373.89  4380.6  373.95  4402.9  375.16
  4432.9  371.49  4471.1  371.18  4471.3  370.68  4475.1  371.18  4500.3  373.25
  4664.9  373.38  4711.3  372.28  4735.6  373.44  4852.4  371.57  4857.4  373.11
  4913.7  371.87  4927.8  373.43  4975.0  372.30  4980.1  373.33  5028.9  372.64
  5120.9  373.86  5301.4  373.48  5306.4  372.15  5354.6  373.52  5613.5  372.46
  5696.9  374.60  5755.3  380.33  5797.3  382.60  5908.9  394.06  5999.8  395.88
#Mann=3,-1,0
  4082.0    0.05       0  4471.1    0.03       0  4475.1    0.05       0
Bank Sta=4471.1,4475.1
Exp/Cntr=0.3,0.1

Type RM Length L Ch R = 1,8814,736,736,736
BEGIN DESCRIPTION:
Mapping XS af846c0b
END DESCRIPTION:
XS GIS Cut Line= 6
      2649992.54      6851886.96      2649950.33      6851271.67
      2649909.21      6850987.68      2649874.49      6850723.79
      2649815.46      6850459.90      2649693.95      6850025.96
#Sta/Elev= 30
  4042.9  374.60  4099.0  374.07  4179.2  371.46  4356.1  372.71  4379.7  374.18
  4399.7  371.11  4449.8  370.47  4469.9  372.13  4489.9  369.62  4610.2  363.63
  4662.5  363.55  4690.6  360.04  4720.3  358.18  4882.6  358.65  4931.1  357.39
  4936.1  358.50  5007.2  356.88  5007.4  356.38  5011.2  356.88  5014.2  358.51
  5161.5  357.02  5166.5  358.59  5224.7  356.94  5229.9  358.42  5273.3  358.02
  5408.6  361.76  5650.7  373.61  5752.0  380.44  5876.6  391.64  5933.8  393.04
#Mann=3,-1,0
  4042.9    0.05       0  5007.2    0.04       0  5011.2    0.05       0
Bank Sta=5007.2,5011.2
Exp/Cntr=0.3,0.1

Type RM Length L Ch R = 1,8078,181,181,181
BEGIN DESCRIPTION:
Mapping XS d72e2524
END DESCRIPTION:
XS GIS Cut Line= 4
      2650069.28      6851913.20      2650534.00      6851406.81
      2650520.70      6850619.21      2650070.43      6849687.97
#Sta/Elev= 30
  3522.9  369.72  3585.8  365.62  3614.1  365.19  3706.0  360.16  3713.4  360.62
  3734.4  358.49  3741.8  358.92  3762.7  356.80  3812.1  354.42  3904.6  351.93
  3939.7  352.23  3966.1  343.42  3966.3  342.92  3970.1  343.42  3974.9  343.72
  3989.0  349.95  3996.4  351.47  4010.6  351.81  4956.1  349.88  4994.5  347.54
  5016.4  347.46  5044.5  349.22  5451.2  355.21  5651.3  362.22  5829.4  366.82
  5852.0  366.83  5862.3  366.39  5869.0  364.69  5884.5  364.52  6032.3  370.60
#Mann=3,-1,0
  3522.9    0.05       0  3966.1    0.04       0  3970.1    0.05       0
Bank Sta=3966.1,3970.1
Exp/Cntr=0.3,0.1

Type RM Length L Ch R = 1,7897,61,61,61
BEGIN DESCRIPTION:
Mapping XS 7b633a79
END DESCRIPTION:
XS GIS Cut Line= 3
      2650640.56      6851775.78      2650679.62      6850577.85
      2650683.95      6849064.52
#Sta/Elev= 30
  3784.6  349.91  3849.4  348.89  3869.4  345.78  3879.4  345.47  3939.5  345.32
  3957.5  342.97  3957.7  342.47  3961.5  342.97  3999.5  348.89  4039.5  350.56
  4729.9  349.15  4970.0  346.85  5000.0  344.93  5020.0  345.67  5040.0  347.76
  5100.0  349.40  5170.0  349.68  5180.0  348.89  5465.1  352.36  5470.1  351.30
  5510.0  351.96  5520.0  350.24  5540.0  352.37  5760.0  355.66  5780.0  354.91
  5790.0  355.85  6070.0  362.63  6100.0  362.17  6360.0  372.64  6496.5  377.12
#Mann=3,-1,0
  3784.6    0.05       0  3957.5    0.04       0  3961.5    0.05       0
Bank Sta=3957.5,3961.5
Exp/Cntr=0.3,0.1

Type RM Length L Ch R = 1,7836,1243,1243,1243
BEGIN DESCRIPTION:
Mapping XS cd4843fe
END DESCRIPTION:
XS GIS Cut Line= 3
      2650670.94      6851775.79      2650741.18      6850561.42
      2650744.72      6849076.12
#Sta/Elev= 30
  3783.6  349.66  3888.6  348.71  3955.8  348.93  3960.8  345.08  3978.7  349.12
  3988.7  349.66  4149.0  349.62  4279.2  350.60  4309.3  349.42  4476.0  349.68
  4481.0  348.82  4652.7  346.71  4940.3  346.44  4980.4  347.12  4990.4  346.47
  4996.5  344.51  4996.7  344.01  5000.5  344.51  5010.4  346.49  5040.4  345.84
  5420.4  348.55  5510.4  347.93  5600.4  349.50  5630.4  350.93  5640.4  350.22
  5670.4  350.26  5780.4  351.51  5960.4  354.98  6110.4  359.86  6485.3  376.07
#Mann=3,-1,0
  3783.6    0.05       0  4996.5    0.04       0  5000.5    0.05       0
Bank Sta=4996.5,5000.5
Exp/Cntr=0.3,0.1

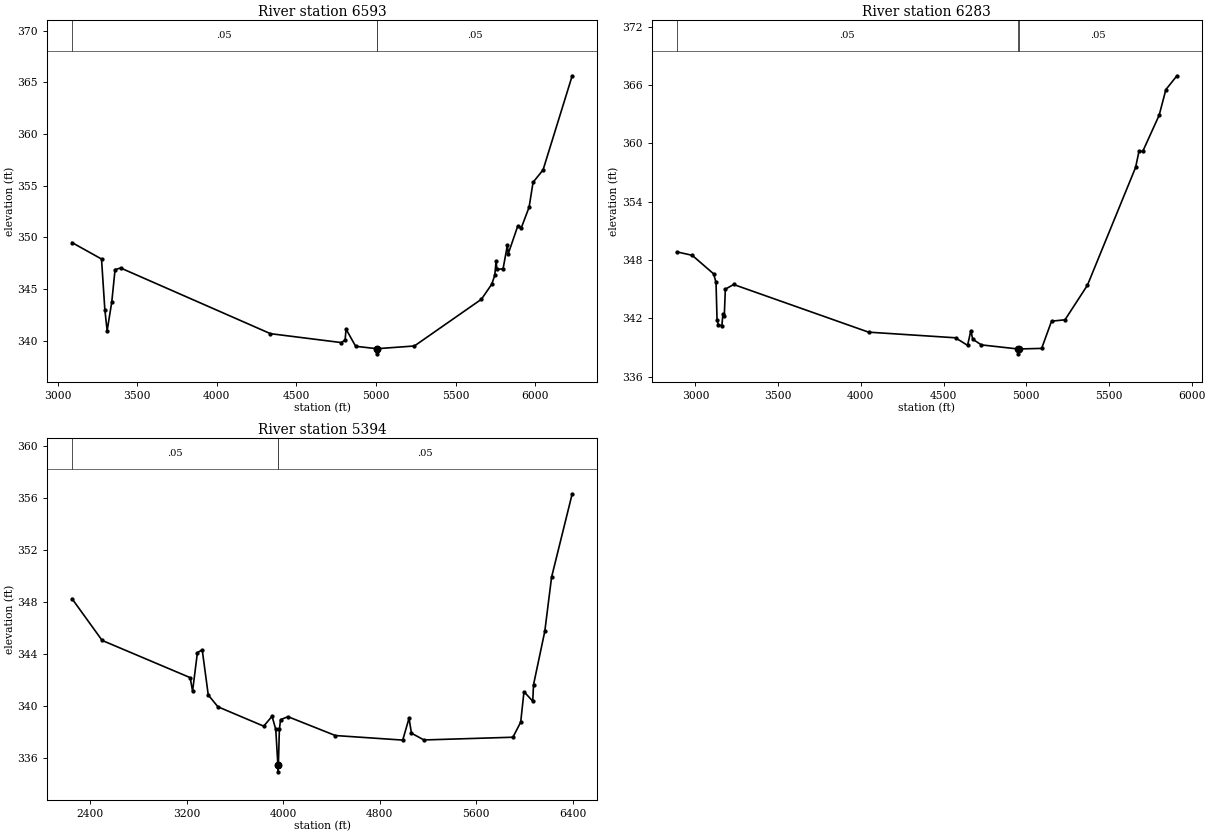
Type RM Length L Ch R = 1,6593,310,310,310
BEGIN DESCRIPTION:
Kings Creek 29_1 6.0
END DESCRIPTION:
XS GIS Cut Line= 4
      2650675.96      6851811.03      2651719.49      6850993.19
      2651781.90      6850413.16      2651422.37      6849236.04
#Sta/Elev= 30
  3090.8  349.50  3276.2  347.91  3297.0  343.02  3311.4  340.97  3340.4  343.74
  3361.2  346.89  3396.4  347.04  4336.7  340.69  4780.9  339.83  4805.3  340.07
  4811.1  341.13  4871.4  339.47  5003.3  339.24  5003.5  338.74  5007.3  339.24
  5240.1  339.50  5661.0  344.02  5725.5  345.47  5744.6  346.33  5753.0  347.69
  5758.3  346.90  5796.9  346.97  5823.9  349.24  5829.1  348.41  5889.5  351.12
  5911.9  350.95  5960.3  352.93  5985.1  355.33  6047.9  356.53  6230.8  365.63
#Mann=3,-1,0
  3090.8    0.05       0  5003.3    0.04       0  5007.3    0.05       0
Bank Sta=5003.3,5007.3
Exp/Cntr=0.3,0.1

Type RM Length L Ch R = 1,6283,889,889,889
BEGIN DESCRIPTION:
Mapping XS 584f47c4
END DESCRIPTION:
XS GIS Cut Line= 4
      2650781.96      6851838.51      2651791.22      6851095.65
      2652042.25      6850245.23      2651883.58      6849375.15
#Sta/Elev= 30
  2886.8  348.84  2980.2  348.48  3109.7  346.58  3124.4  345.70  3130.6  341.83
  3139.0  341.31  3159.9  341.26  3166.1  342.43  3174.5  342.29  3180.7  345.00
  3230.9  345.48  4046.6  340.58  4572.3  340.00  4645.3  339.22  4665.0  340.73
  4676.6  339.85  4728.7  339.27  4950.3  338.85  4950.5  338.35  4954.3  338.85
  5093.2  338.91  5153.0  341.71  5234.3  341.85  5369.8  345.40  5661.2  357.52
  5681.5  359.17  5704.7  359.18  5803.5  362.88  5844.2  365.52  5911.1  366.94
#Mann=3,-1,0
  2886.8    0.05       0  4950.3    0.04       0  4954.3    0.05       0
Bank Sta=4950.3,4954.3
Exp/Cntr=0.3,0.1

Type RM Length L Ch R = 1,5394,0,0,0
BEGIN DESCRIPTION:
Kings Creek 29_1 5.0
END DESCRIPTION:
XS GIS Cut Line= 5
      2650876.00      6851811.00      2652477.70      6851797.51
      2652660.94      6850661.15      2652508.44      6850101.78
      2652016.62      6849451.14
#Sta/Elev= 30
  2247.2  348.26  2497.2  345.05  3227.2  342.19  3247.2  341.15  3287.2  344.11
  3327.2  344.33  3377.2  340.86  3457.2  339.95  3837.3  338.46  3906.2  339.22
  3937.1  338.21  3954.8  335.45  3955.1  334.95  3958.8  335.45  3967.0  338.23
  3977.1  338.96  4037.9  339.19  4431.4  337.74  4990.0  337.39  5042.3  339.07
  5062.3  337.92  5166.0  337.40  5903.8  337.61  5968.3  338.77  5995.4  341.11
  6068.2  340.38  6074.5  341.64  6168.1  345.75  6224.3  349.91  6395.4  356.32
#Mann=3,-1,0
  2247.2    0.05       0  3954.8    0.03       0  3958.8    0.05       0
Bank Sta=3954.8,3958.8
Exp/Cntr=0.3,0.1

Chan Stop Cuts=-1