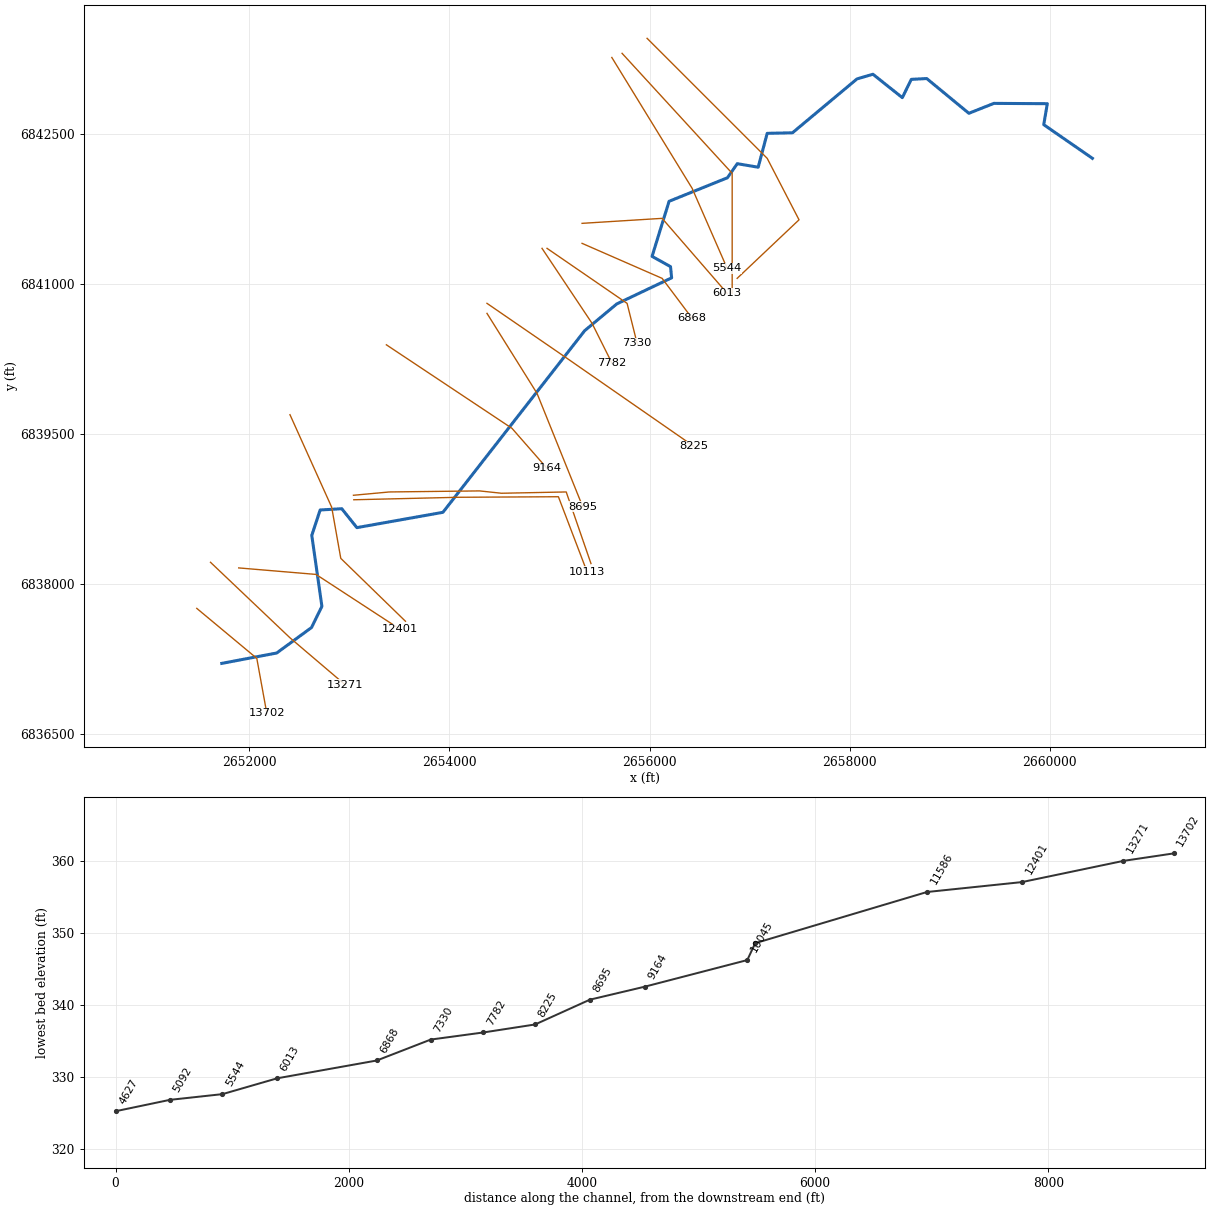
--- Kings Creek 30.prj (project) ---

Proj Title=Kings Creek 30 Base Level Engineering
Current Plan=p01
Default Exp/Contr=0.3,0.1
English Units
Geom File=g01
Flow File=f01
Plan File=p01
Y Axis Title=Elevation
X Axis Title(PF)=Main Channel Distance
X Axis Title(XS)=Station
BEGIN DESCRIPTION:
Kings Creek 30
END DESCRIPTION:
DSS Export Rating Curves= 0
DSS Export Rating Curve Sorted= 0
DSS Export Volume Flow Curves= 0
DXF OffsetX= 0
DXF OffsetY= 0
DXF ScaleX= 1
DXF ScaleY= 10

--- Kings Creek 30.p01 (plan) ---

Plan Title=Multiple Run
Short Identifier=Multiple
Geom File=g01
Flow File=f01
Subcritical Flow
K Sum by GR= 0
Std Step Tol= 0.01
Critical Tol= 0.01
Num of Std Step Trials= 20
Max Error Tol= 0.3
Flow Tol Ratio= 0.001
Split Flow NTrial= 30
Split Flow Tol= 0.02
Split Flow Ratio= 0.02
Log Output Level= 0
Friction Slope Method= 1
Unsteady Friction Slope Method= 2
Unsteady Bridges Friction Slope Method= 1
Parabolic Critical Depth
Global Vel Dist=  1 , 1 , 1
Global Log Level= 0
CheckData=True
Encroach Param= -1, 0, 0, 0
BEGIN DESCRIPTION:
Multiple Run
END DESCRIPTION:

--- Kings Creek 30.f01 (steady flow) ---

Flow Title=Multiple
Number of Profiles=7
Profile Names=10-year,25-year,50-year,1pct_min,100-year,1pct_plu,500-year
River Rch & RM= Kings Creek 30,Reach-1,13702
     789    1089    1338     815    1627    3246    2406
River Rch & RM= Kings Creek 30,Reach-1,11586
    1031    1431    1764    1078    2150    4290    3196
Boundary for River Rch & Prof#=Kings Creek 30,Reach-1,1
Up Type=0
Dn Type=3
Dn Slope=0.005
Boundary for River Rch & Prof#=Kings Creek 30,Reach-1,2
Up Type=0
Dn Type=3
Dn Slope=0.005
Boundary for River Rch & Prof#=Kings Creek 30,Reach-1,3
Up Type=0
Dn Type=3
Dn Slope=0.005
Boundary for River Rch & Prof#=Kings Creek 30,Reach-1,4
Up Type=0
Dn Type=3
Dn Slope=0.005
Boundary for River Rch & Prof#=Kings Creek 30,Reach-1,5
Up Type=0
Dn Type=3
Dn Slope=0.005
Boundary for River Rch & Prof#=Kings Creek 30,Reach-1,6
Up Type=0
Dn Type=3
Dn Slope=0.005
Boundary for River Rch & Prof#=Kings Creek 30,Reach-1,7
Up Type=0
Dn Type=3
Dn Slope=0.005

--- Kings Creek 30.g01 (geometry) ---

Geom Title=Existing Conditions
Program Version=4.10

River Reach=Kings Creek 30  ,Reach-1
Reach XY= 30
        2651726.        6837211.      2652274.51      6837314.61
      2652622.56      6837569.18       2652726.3      6837781.17
      2652625.41      6838490.95      2652708.78      6838744.76
      2652924.75      6838757.55       2653075.9      6838568.28
       2653935.8      6838721.48      2655352.26      6840537.89
       2655673.3      6840805.64      2656221.05      6841066.11
       2656209.8      6841178.18      2656025.55      6841281.02
      2656195.62      6841831.47      2656778.55      6842066.73
      2656877.25      6842207.56      2657086.09      6842172.09
        2657176.        6842511.      2657428.45      6842516.46
      2658073.58      6843055.47      2658232.74      6843101.87
      2658526.25      6842867.98      2658615.83      6843050.68
      2658770.14      6843058.95      2659191.22      6842711.49
      2659441.16      6842810.61      2659975.01      6842807.47
      2659939.52      6842597.62        2660426.        6842261.

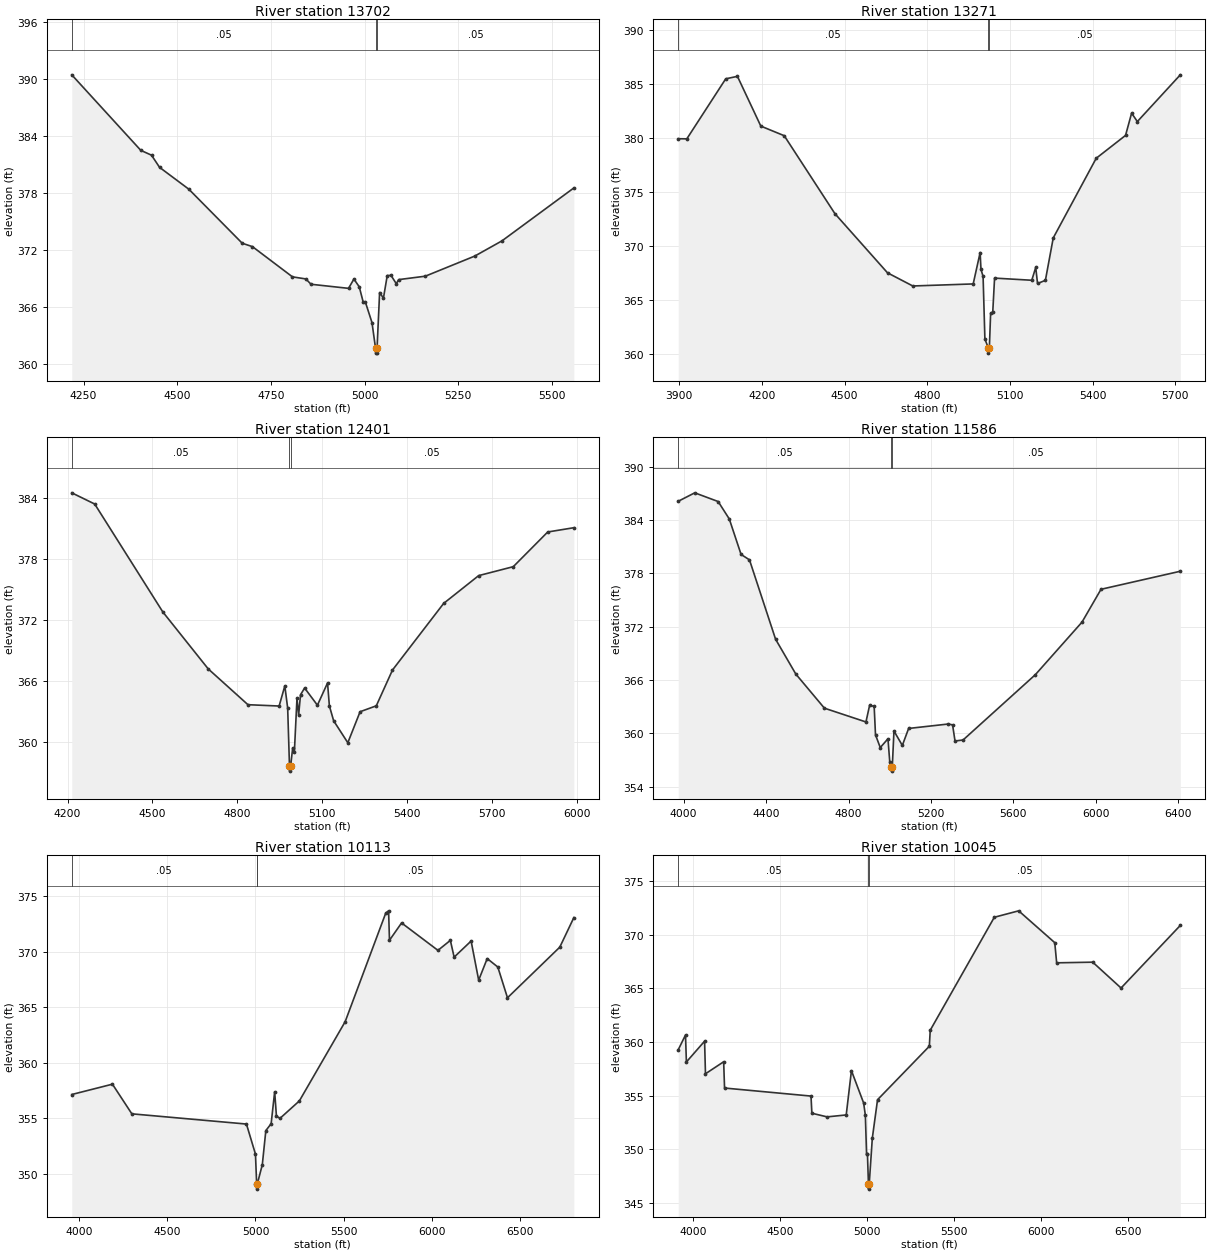
Type RM Length L Ch R = 1 ,13702   ,431,431,431
BEGIN DESCRIPTION:
Kings Creek 30 20.0
END DESCRIPTION:
XS GIS Cut Line= 3
      2651476.02      6837760.98        2652076.        6837261.
        2652176.      6836711.01
#Sta/Elev= 30
  4218.6  390.42  4402.8  382.47  4431.4  381.96  4452.9  380.68    4531  378.38
  4673.5  372.69  4700.9  372.33  4807.6  369.15  4843.4  368.93  4857.1  368.37
  4957.3  367.94  4971.6  368.92  4985.9   368.1  4996.3  366.51  5002.1  366.51
  5019.9  364.33  5029.4  361.62  5029.6  361.12  5033.1  361.12  5033.4  361.62
  5040.2   367.5  5050.4  366.91  5060.6  369.29  5070.7   369.3  5084.7  368.43
  5091.1  368.86  5162.2  369.22  5294.3  371.34  5366.8  372.94  5558.6  378.51
#Mann= 3 ,-1 , 0
  4218.6     .05       0  5029.4     .04       0  5033.4     .05       0
Bank Sta=5029.4,5033.4
XS Rating Curve= 0 ,0
Exp/Cntr=0.3,0.1

Type RM Length L Ch R = 1 ,13271   ,870,870,870
BEGIN DESCRIPTION:
Mapping XS 010cd837
END DESCRIPTION:
XS GIS Cut Line= 3
      2651613.06      6838221.97      2652407.32      6837466.77
      2652960.61      6836995.61
#Sta/Elev= 30
    3896  379.94  3927.2  379.93  4068.4  385.49  4110.9  385.72  4195.8  381.11
  4280.8  380.22  4464.8     373  4655.7  367.52  4747.5   366.3  4966.8  366.49
    4992   369.4    4995  367.85  5002.7  367.18  5009.3  361.38  5021.5  360.58
  5021.8  360.08  5025.5  360.58  5030.1  363.77  5037.8  363.88  5044.4  367.03
  5179.5  366.83  5193.8  368.02  5200.4  366.53  5228.9  366.82  5257.4  370.75
  5413.4  378.13  5519.9  380.25  5541.9  382.31  5562.7  381.53  5718.7  385.86
#Mann= 3 ,-1 , 0
    3896     .05       0  5021.5     .04       0  5025.5     .05       0
Bank Sta=5021.5,5025.5
XS Rating Curve= 0 ,0
Exp/Cntr=0.3,0.1

Type RM Length L Ch R = 1 ,12401   ,815,815,815
BEGIN DESCRIPTION:
Mapping XS 28dc40c0
END DESCRIPTION:
XS GIS Cut Line= 3
      2651895.14      6838165.56      2652667.73      6838100.45
      2653505.39      6837553.58
#Sta/Elev= 30
  4214.8  384.49  4295.9  383.39  4536.8  372.78  4697.4  367.18  4837.9  363.66
  4948.2  363.53  4968.3  365.51  4978.4  363.32  4984.8  357.63    4985  357.13
  4988.8  357.63  4996.2  359.42  5002.1  359.02  5011.3  364.29  5017.2  362.67
  5023.9  364.64  5038.3   365.3  5083.6  363.61  5119.4   365.8  5125.9  363.54
    5141  362.08  5191.1  359.92  5234.5  362.97  5291.8  363.55  5349.1  367.07
  5530.1  373.62  5653.8  376.35  5776.3  377.23  5898.1  380.64  5990.5  381.06
#Mann= 3 ,-1 , 0
  4214.8     .05       0  4984.8     .03       0  4988.8     .05       0
Bank Sta=4984.8,4988.8
XS Rating Curve= 0 ,0
Exp/Cntr=0.3,0.1

Type RM Length L Ch R = 1 ,11586   ,1473,1473,1473
BEGIN DESCRIPTION:
Mapping XS 6771141c
END DESCRIPTION:
XS GIS Cut Line= 4
      2652407.34      6839697.63      2652823.98      6838773.19
      2652915.13      6838261.04      2653561.42       6837632.1
#Sta/Elev= 30
  3973.8   386.1    4054  387.05  4167.5  386.07  4221.5  384.11  4278.7  380.12
  4319.5  379.51  4446.2  370.58  4544.2  366.67    4683  362.83  4884.6  361.28
  4902.2  363.14  4924.4  363.04  4930.9  359.83    4954   358.4  4991.4  359.39
  5000.2  356.75  5008.2  356.25  5008.6  355.75  5012.4  356.25  5020.5  360.26
  5061.1  358.64  5091.6  360.55  5284.6  361.05  5304.9  360.95  5316.7  359.14
  5355.7  359.25  5706.6   366.6  5932.9  372.51    6025   376.2  6409.8  378.23
#Mann= 3 ,-1 , 0
  3973.8     .05       0  5008.2     .03       0  5012.4     .05       0
Bank Sta=5008.2,5012.4
XS Rating Curve= 0 ,0
Exp/Cntr=0.3,0.1

Type RM Length L Ch R = 1 ,10113   ,68,68,68
BEGIN DESCRIPTION:
Mapping XS 3a8e025c
END DESCRIPTION:
XS GIS Cut Line= 4
      2653045.35      6838846.98      2654087.15      6838871.81
      2655089.61      6838877.36      2655376.06      6838126.52
#Sta/Elev= 30
  3957.9  357.15  4188.6  358.08  4298.7  355.41  4948.8  354.49    5000  351.78
  5006.6  349.13    5007  348.63    5011  349.13  5038.8  350.83  5058.8   353.9
  5088.9  354.52  5108.9   357.4  5118.9  355.21  5138.9     355  5248.9  356.57
  5508.9  363.71  5738.9  373.48  5755.2  373.69  5760.2  371.04  5828.9   372.6
  6035.2  370.13  6105.6  371.03    6127  369.52  6223.3  370.97  6266.2  367.45
  6314.6  369.39  6374.8  368.63  6429.6  365.86  6726.4  370.42  6806.1  373.08
#Mann= 3 ,-1 , 0
  3957.9     .05       0  5006.6     .03       0    5011     .05       0
Bank Sta=5006.6,5011
XS Rating Curve= 0 ,0
Exp/Cntr=0.3,0.1

Type RM Length L Ch R = 1 ,10045   ,881,881,881
BEGIN DESCRIPTION:
Mapping XS 465ce64a
END DESCRIPTION:
XS GIS Cut Line= 6
      2653041.62      6838891.95      2653401.24       6838925.1
      2654301.88      6838935.54      2654521.03      6838912.08
      2655167.73       6838925.1      2655415.11        6838209.
#Sta/Elev= 30
  3915.1  359.28  3956.9  360.66    3962  358.14  4066.6  360.08  4071.7  357.04
  4176.3  358.16  4181.4  355.71  4678.5  354.96  4683.5  353.36    4771  353.02
    4881   353.2    4911  357.33    4981  354.32    4991  353.18    4998  349.56
    5003  349.56  5008.8  346.78  5009.2  346.28  5013.3  346.78  5031.1  351.04
  5061.1  354.62    5359  359.61    5364   361.1  5732.6  371.64  5872.6  372.24
  6080.1  369.27    6091  367.39  6298.4  367.45  6461.3  365.04    6802  370.88
#Mann= 3 ,-1 , 0
  3915.1     .05       0  5008.8     .03       0  5013.3     .05       0
Bank Sta=5008.8,5013.3
XS Rating Curve= 0 ,0
Exp/Cntr=0.3,0.1

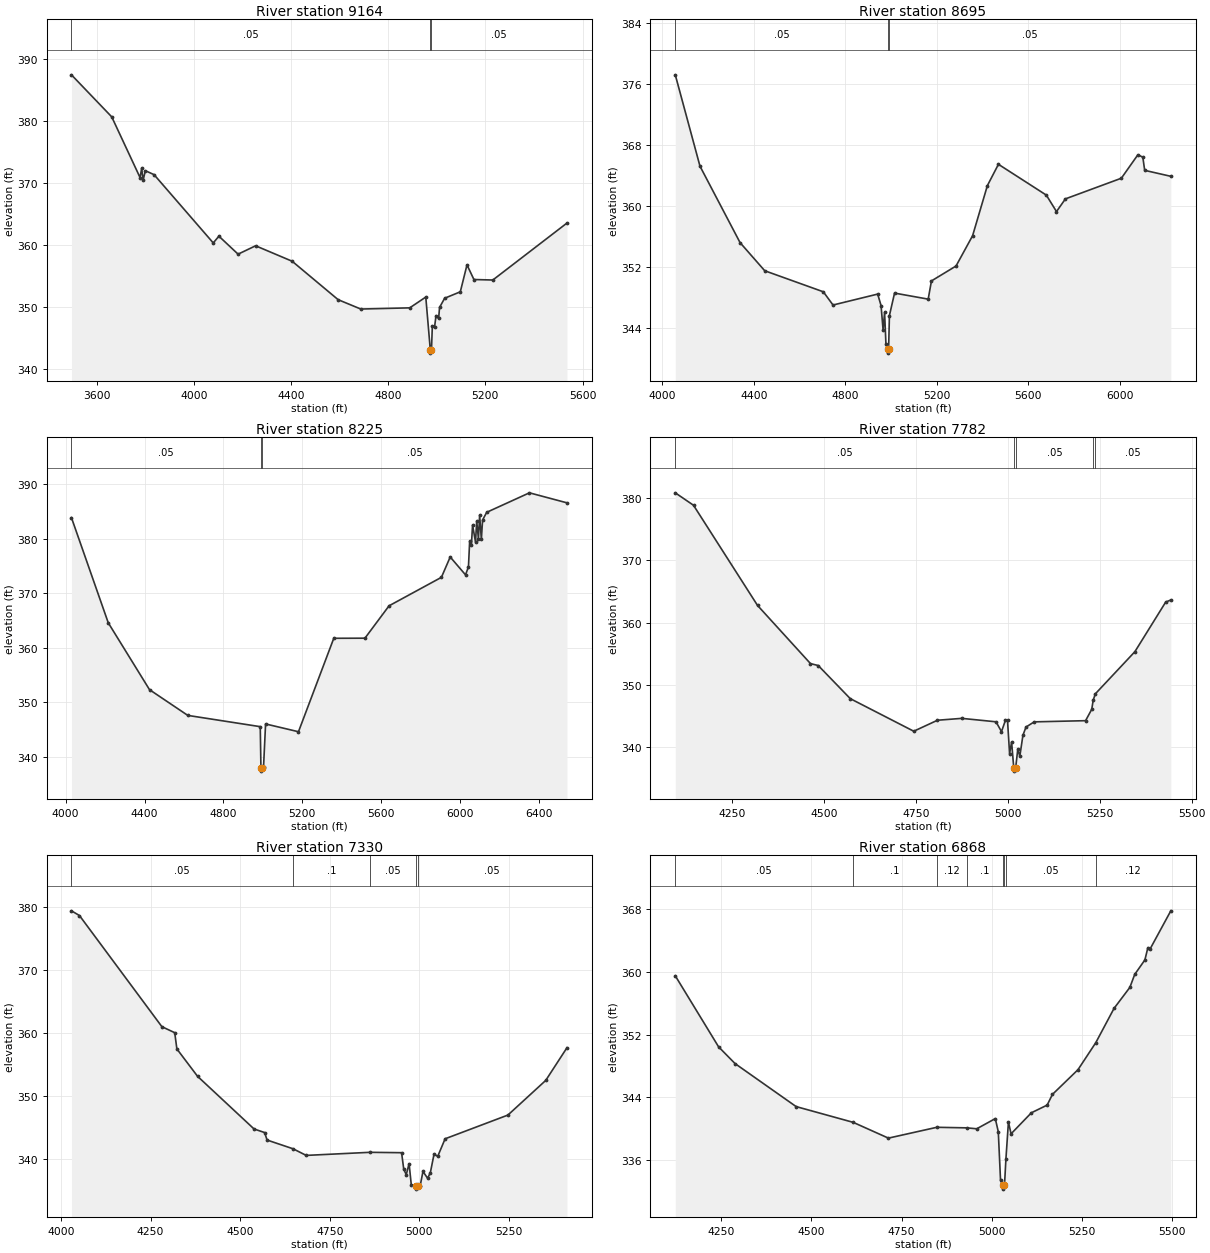
Type RM Length L Ch R = 1 ,9164    ,469,469,469
BEGIN DESCRIPTION:
Kings Creek 30 12.0
END DESCRIPTION:
XS GIS Cut Line= 3
      2653370.85      6840396.46        2654626.        6839561.
      2654976.01      6839160.99
#Sta/Elev= 30
  3496.7  387.45  3662.5  380.67  3779.2  370.87  3785.7  372.39  3791.7  370.45
  3800.8  371.99  3836.8  371.35  4080.3  360.34  4103.5  361.43  4182.5  358.53
  4254.6  359.88  4404.9  357.39  4594.2  351.19  4687.4  349.68  4888.8  349.87
  4954.9  351.61  4973.6  343.07  4974.1  342.57  4978.3  343.07  4981.9  346.92
    4991  346.75    4997  348.62  5007.8  348.16  5011.6  349.94  5032.5  351.42
    5097  352.46  5124.5   356.8    5153  354.44  5230.8  354.36    5536  363.55
#Mann= 3 ,-1 , 0
  3496.7     .05       0  4973.6     .04       0  4978.3     .05       0
Bank Sta=4973.6,4978.3
XS Rating Curve= 0 ,0
Exp/Cntr=0.3,0.1

Type RM Length L Ch R = 1 ,8695    ,470,470,470
BEGIN DESCRIPTION:
Kings Creek 30 11.0
END DESCRIPTION:
XS GIS Cut Line= 3
      2654375.97      6840711.04        2654876.        6839911.
      2655332.64      6838777.58
#Sta/Elev= 30
  4056.8  377.16  4164.8  365.21  4339.9  355.22  4447.8  351.54  4703.7  348.79
  4746.1  347.06  4941.3  348.49    4956  346.99  4964.9   343.8  4971.4  346.09
  4977.3  341.98  4984.3  341.27  4984.8  340.77    4989  341.27  4992.6  345.69
    5015  348.62    5162  347.83  5176.2  350.21  5283.6  352.16    5356  356.12
  5420.7  362.68  5468.9  365.46  5678.3  361.43  5722.6  359.28  5761.6  360.94
    6006  363.64  6078.4  366.71  6099.9  366.39    6108  364.67  6222.2  363.89
#Mann= 3 ,-1 , 0
  4056.8     .05       0  4984.3     .04       0    4989     .05       0
Bank Sta=4984.3,4989
XS Rating Curve= 0 ,0
Exp/Cntr=0.3,0.1

Type RM Length L Ch R = 1 ,8225    ,443,443,443
BEGIN DESCRIPTION:
Kings Creek 30 10.0
END DESCRIPTION:
XS GIS Cut Line= 3
      2654376.01      6840810.99        2655176.        6840261.
      2656442.41      6839381.78
#Sta/Elev= 30
  4029.4   383.9  4216.1  364.57  4425.2  352.29  4619.3  347.56  4986.7  345.49
  4990.2  337.82  4990.9  337.32  4995.3  337.82  5003.3  338.02  5013.7  345.99
  5180.5  344.56  5359.5  361.73  5517.5  361.75  5639.8   367.7  5905.2  372.93
  5949.8  376.67  6027.4  373.39  6042.3  374.84  6048.4  379.54  6057.2  378.81
  6063.2  382.54  6078.1  379.42  6084.2  383.26  6092.9  380.03    6099  384.34
  6107.8  379.89  6113.9  383.46  6134.8  384.88  6351.5  388.46  6541.9  386.62
#Mann= 3 ,-1 , 0
  4029.4     .05       0  4990.2     .06       0  4995.3     .05       0
Bank Sta=4990.2,4995.3
XS Rating Curve= 0 ,0
Exp/Cntr=0.3,0.1

Type RM Length L Ch R = 1 ,7782    ,452,452,452
BEGIN DESCRIPTION:
Kings Creek 30 9.0
END DESCRIPTION:
XS GIS Cut Line= 3
      2654926.01      6841360.98        2655426.        6840611.
      2655626.01      6840210.98
#Sta/Elev= 30
  4094.7  380.78  4144.3  378.79  4318.5  362.75  4462.7  353.43  4483.8  353.12
  4570.9  347.82  4743.7   342.6  4808.3  344.36  4874.4  344.66  4967.5  344.11
  4982.5  342.54  4993.1  344.33  4998.9  344.33  5004.5  338.99    5010  340.88
  5015.9  336.71  5016.5  336.21    5021  336.71  5026.8  339.71  5032.4   338.6
  5040.8  341.95  5049.2  343.27  5071.5   344.1  5211.3  344.29  5228.1  346.11
  5232.1  347.58  5237.9  348.59  5345.5  355.34  5429.3  363.28  5443.3  363.62
#Mann= 5 ,-1 , 0
  4094.7     .05       0  5015.9     .03       0    5021     .05       0
  5232.1      .1       0  5237.9     .05       0
Bank Sta=5015.9,5021
XS Rating Curve= 0 ,0
Exp/Cntr=0.3,0.1

Type RM Length L Ch R = 1 ,7330    ,462,462,462
BEGIN DESCRIPTION:
Kings Creek 30 8.0
END DESCRIPTION:
XS GIS Cut Line= 3
      2654975.97      6841361.02        2655776.        6840811.
      2655876.01      6840410.98
#Sta/Elev= 30
  4029.1  379.45  4051.5   378.7  4281.5  361.04  4317.4  360.08  4323.4   357.5
  4381.1  353.15  4538.8  344.78  4568.3  344.21  4575.2  343.02  4647.8  341.63
  4684.4  340.58    4862  341.07  4950.6  341.01  4956.7  338.37  4963.6  337.53
  4971.6  339.27  4977.6  335.94  4989.9  335.72  4990.6  335.22  4995.1  335.72
  5002.5  335.75  5010.3  338.03  5023.2  336.95  5030.9  337.83  5041.2  340.78
  5051.5  340.43  5072.1  343.22  5247.4  346.99    5353   352.5  5412.3   357.7
#Mann= 5 ,-1 , 0
  4029.1     .05       0  4647.8      .1       0    4862     .05       0
  4989.9     .03       0  4995.1     .05       0
Bank Sta=4989.9,4995.1
XS Rating Curve= 0 ,0
Exp/Cntr=0.3,0.1

Type RM Length L Ch R = 1 ,6868    ,855,855,855
BEGIN DESCRIPTION:
Kings Creek 30 7.0
END DESCRIPTION:
XS GIS Cut Line= 3
      2655325.99        6841411.        2656126.        6841061.
      2656425.99      6840661.02
#Sta/Elev= 30
  4122.6   359.5  4242.7  350.44  4288.3  348.31  4457.5  342.83  4615.7  340.82
  4713.2  338.81  4847.3  340.19  4930.4  340.12    4958     340  5009.4   341.3
  5017.7  339.63  5023.9  333.47  5029.7  332.81  5030.4  332.31  5034.9  332.81
  5038.9  336.18  5045.8  340.87  5053.1  339.36  5109.4  342.04  5153.1  343.02
  5167.7  344.38  5238.5  347.53  5287.8  350.97  5338.5  355.35  5382.3  358.02
  5395.8  359.68  5423.9  361.52  5432.3  363.09  5438.5  362.93  5495.8  367.78
#Mann= 8 ,-1 , 0
  4122.6     .05       0  4615.7      .1       0  4847.3     .12       0
  4930.4      .1       0  5029.7     .07       0  5034.9      .1       0
  5038.9     .05       0  5287.8     .12       0
Bank Sta=5029.7,5034.9
XS Rating Curve= 0 ,0
Exp/Cntr=0.3,0.1

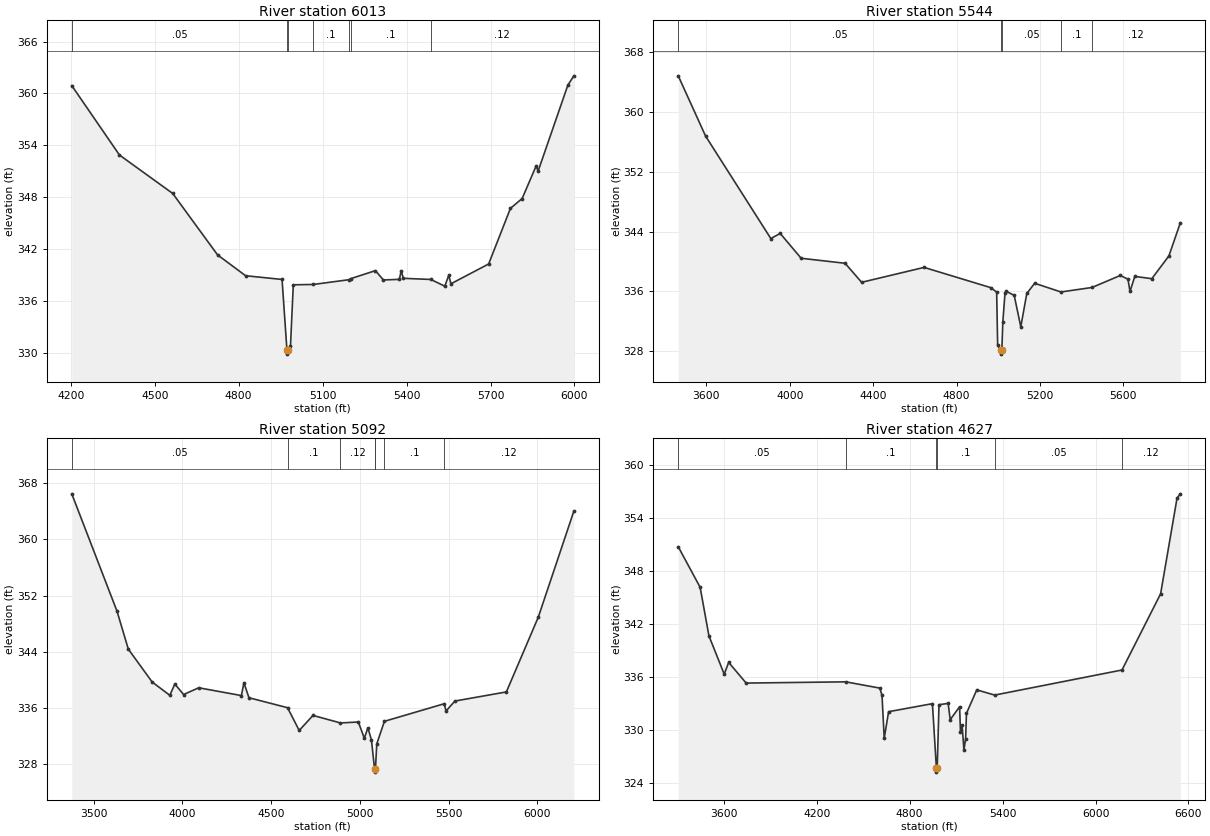
Type RM Length L Ch R = 1 ,6013    ,469,469,469
BEGIN DESCRIPTION:
Kings Creek 30 6.0
END DESCRIPTION:
XS GIS Cut Line= 3
      2655326.04        6841611.        2656126.        6841661.
      2656776.01      6840910.99
#Sta/Elev= 30
  4203.7   360.9    4374  352.87  4564.4  348.42  4724.7  341.31  4824.9   338.9
  4955.1  338.47  4972.5  330.33  4973.3  329.83  4977.8  330.33  4985.2  330.75
  4995.2  337.85    5067  337.89  5193.9  338.44  5200.2  338.56  5288.7  339.49
  5317.2  338.41  5374.2  338.48  5380.8  339.47  5388.5   338.6  5486.7  338.47
  5536.6  337.69  5550.8  338.96  5558.5  337.97  5693.3  340.26  5771.2   346.7
  5812.9  347.83  5863.3  351.63  5869.9  350.99  5976.3  360.95  5997.7  362.03
#Mann= 7 ,-1 , 0
  4203.7     .05       0  4972.5     .04       0  4977.8     .05       0
    5067      .1       0  5193.9     .12       0  5200.2      .1       0
  5486.7     .12       0
Bank Sta=4972.5,4977.8
XS Rating Curve= 0 ,0
Exp/Cntr=0.3,0.1

Type RM Length L Ch R = 1 ,5544    ,452,452,452
BEGIN DESCRIPTION:
Kings Creek 30 5.0
END DESCRIPTION:
XS GIS Cut Line= 3
      2655623.47      6843269.71        2656426.        6841961.
        2656776.      6841160.99
#Sta/Elev= 30
  3465.2  364.79  3596.5  356.74  3909.4  343.06  3954.2  343.75  4054.8  340.43
  4265.6  339.76  4344.9  337.22  4644.5  339.21  4965.2   336.5  4992.7  335.91
  4997.4  328.83  5012.1  328.13  5012.9  327.63  5017.5  328.13  5022.2  331.91
  5032.7  335.78  5038.2  336.02  5076.8  335.48  5108.4  331.28  5137.2  335.73
    5175  337.09  5301.1  335.93  5450.1  336.53  5585.5  338.13  5622.5  337.64
  5632.3     336  5655.3  338.01  5736.8   337.7    5819  340.75  5873.6  345.16
#Mann= 5 ,-1 , 0
  3465.2     .05       0  5012.1     .03       0  5017.5     .05       0
  5301.1      .1       0  5450.1     .12       0
Bank Sta=5012.1,5017.5
XS Rating Curve= 0 ,0
Exp/Cntr=0.3,0.1

Type RM Length L Ch R = 1 ,5092    ,465,465,465
BEGIN DESCRIPTION:
Kings Creek 30 4.0
END DESCRIPTION:
XS GIS Cut Line= 3
      2655725.99      6843311.01        2656826.        6842111.
        2656826.      6840910.99
#Sta/Elev= 30
  3376.9  366.49  3631.9  349.75  3695.4  344.36  3829.8  339.67  3929.1  337.78
  3957.5  339.38  4006.8  337.89  4091.9  338.85  4332.4  337.74  4346.5  339.57
  4374.9  337.43  4592.2  336.01  4657.9  332.77  4735.6  334.91  4890.3  333.84
  4990.9  333.97  5024.8  331.66  5044.8  333.15  5064.8  331.42  5082.1  327.33
  5082.8  326.83  5087.5  327.33  5094.8  330.85  5137.7  334.07  5475.2  336.58
  5484.8  335.53  5534.8  336.96  5824.8  338.26  6004.8  348.93  6204.8  364.02
#Mann= 7 ,-1 , 0
  3376.9     .05       0  4592.2      .1       0  4890.3     .12       0
  5082.1     .07       0  5087.5     .12       0  5137.7      .1       0
  5475.2     .12       0
Bank Sta=5082.1,5087.5
XS Rating Curve= 0 ,0
Exp/Cntr=0.3,0.1

Type RM Length L Ch R = 1 ,4627    ,0,0,0
BEGIN DESCRIPTION:
Kings Creek 30 3.0
END DESCRIPTION:
XS GIS Cut Line= 4
      2655975.98      6843461.02        2657176.        6842261.
      2657494.12      6841646.46      2656876.04      6841061.03
#Sta/Elev= 30
  3306.8  350.76  3448.2  346.17  3504.8  340.68  3603.8  336.33  3632.1  337.67
  3745.2  335.33  4387.7  335.47  4607.9  334.76    4622  333.94  4636.2  329.07
  4664.5  332.09  4947.3     333  4972.8  325.75  4973.6  325.25  4978.3  325.75
  4989.7  332.88  5048.9  333.03    5062  331.19  5122.8  332.65  5128.4  329.79
    5139  330.59  5150.6  327.74  5161.5  329.03  5167.1  331.91  5233.5  334.56
  5349.3  333.97  6170.9  336.81    6420  345.43    6526  356.25  6547.2  356.75
#Mann= 6 ,-1 , 0
  3306.8     .05       0  4387.7      .1       0  4972.8     .07       0
  4978.3      .1       0  5349.3     .05       0  6170.9     .12       0
Bank Sta=4972.8,4978.3
XS Rating Curve= 0 ,0
Exp/Cntr=0.3,0.1

Chan Stop Cuts=-1
Use User Specified Reach Order=0
Composite Channel Slope=5