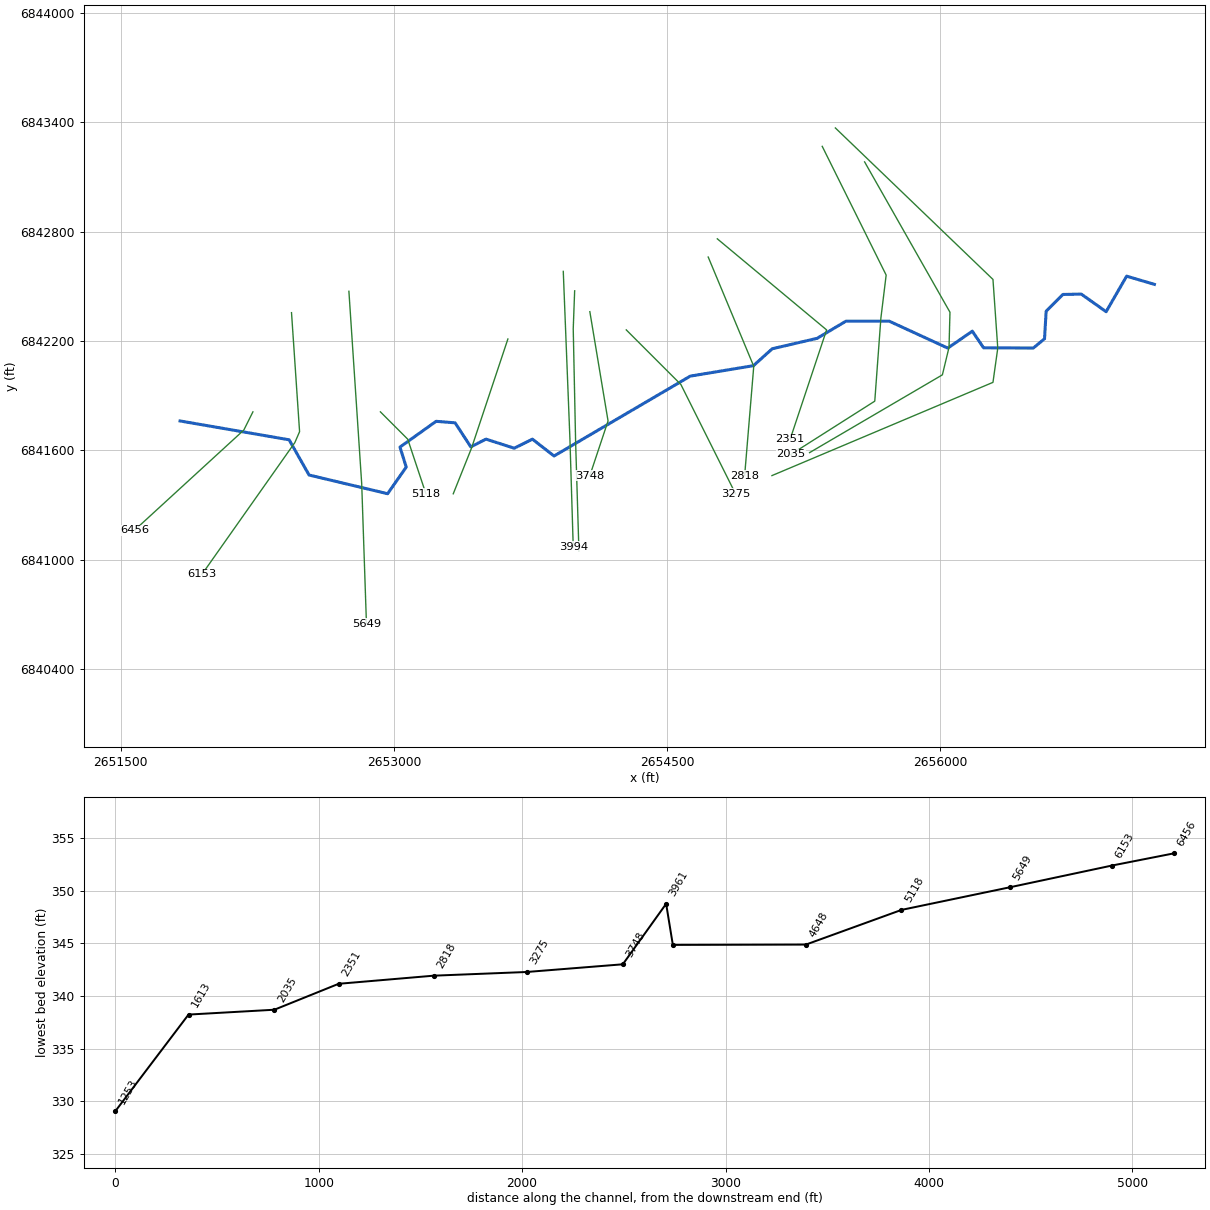
--- Kings Creek 30_1.prj (project) ---

Proj Title=Kings Creek 30_1 Base Level Engineering
Current Plan=p01
Default Exp/Contr=0.3,0.1
English Units
Geom File=g01
Flow File=f01
Plan File=p01
BEGIN DESCRIPTION:
Kings Creek 30_1
END DESCRIPTION:

--- Kings Creek 30_1.p01 (plan) ---

Plan Title=Multiple Run
Short Identifier=Multiple
Geom File=g01
Flow File=f01
Subcritical Flow
K Sum by GR= 0
Std Step Tol= 0.01
Critical Tol= 0.01
Num of Std Step Trials= 20
Max Error Tol= 0.3
Flow Tol Ratio= 0.001
Split Flow NTrial= 30
Split Flow Tol= 0.02
Split Flow Ratio= 0.02
Log Output Level= 0
Friction Slope Method= 1
Unsteady Friction Slope Method= 2
Unsteady Bridges Friction Slope Method= 1
Parabolic Critical Depth
Global Vel Dist=  1 , 1 , 1
Global Log Level= 0
CheckData=True
Encroach Param= -1, 0, 0, 0
BEGIN DESCRIPTION:
Multiple Run
END DESCRIPTION:

--- Kings Creek 30_1.f01 (steady flow) ---

Flow Title=Multiple
Number of Profiles=7
Profile Names=10-year,25-year,50-year,1pct_min,100-year,1pct_plu,500-year
River Rch & RM= Kings Creek 30_1,Reach-1,6456
     695     952    1165     707    1411    2816    2071
River Rch & RM= Kings Creek 30_1,Reach-1,3994
     747    1025    1255     762    1520    3033    2231
River Rch & RM= Kings Creek 30_1,Reach-1,2035
     786    1078    1319     800    1597    3186    2341
Boundary for River Rch & Prof#=Kings Creek 30_1,Reach-1,1
Up Type=0
Dn Type=3
Dn Slope=0.005
Boundary for River Rch & Prof#=Kings Creek 30_1,Reach-1,2
Up Type=0
Dn Type=3
Dn Slope=0.005
Boundary for River Rch & Prof#=Kings Creek 30_1,Reach-1,3
Up Type=0
Dn Type=3
Dn Slope=0.005
Boundary for River Rch & Prof#=Kings Creek 30_1,Reach-1,4
Up Type=0
Dn Type=3
Dn Slope=0.005
Boundary for River Rch & Prof#=Kings Creek 30_1,Reach-1,5
Up Type=0
Dn Type=3
Dn Slope=0.005
Boundary for River Rch & Prof#=Kings Creek 30_1,Reach-1,6
Up Type=0
Dn Type=3
Dn Slope=0.005
Boundary for River Rch & Prof#=Kings Creek 30_1,Reach-1,7
Up Type=0
Dn Type=3
Dn Slope=0.005

--- Kings Creek 30_1.g01 (geometry) ---

Geom Title=Existing Conditions

River Reach=Kings Creek 30_1,Reach-1
Reach XY= 30
      2651826.00      6841761.00      2652424.75      6841657.55
      2652534.32      6841464.15      2652965.53      6841361.53
      2653067.93      6841507.69      2653033.38      6841617.33
      2653231.90      6841759.03      2653336.10      6841750.69
      2653422.34      6841618.72      2653505.79      6841661.20
      2653660.73      6841611.40      2653760.66      6841661.04
      2653879.33      6841568.61      2654627.59      6842007.18
      2654974.50      6842064.62      2655077.50      6842157.38
      2655324.42      6842214.83      2655481.93      6842308.76
      2655720.07      6842308.76      2656041.42      6842161.03
      2656176.20      6842253.97      2656237.83      6842162.66
      2656510.98      6842161.32      2656572.56      6842212.22
      2656581.46      6842363.46      2656673.56      6842455.61
      2656774.50      6842457.53      2656910.78      6842360.83
      2657023.41      6842556.04      2657176.00      6842511.00

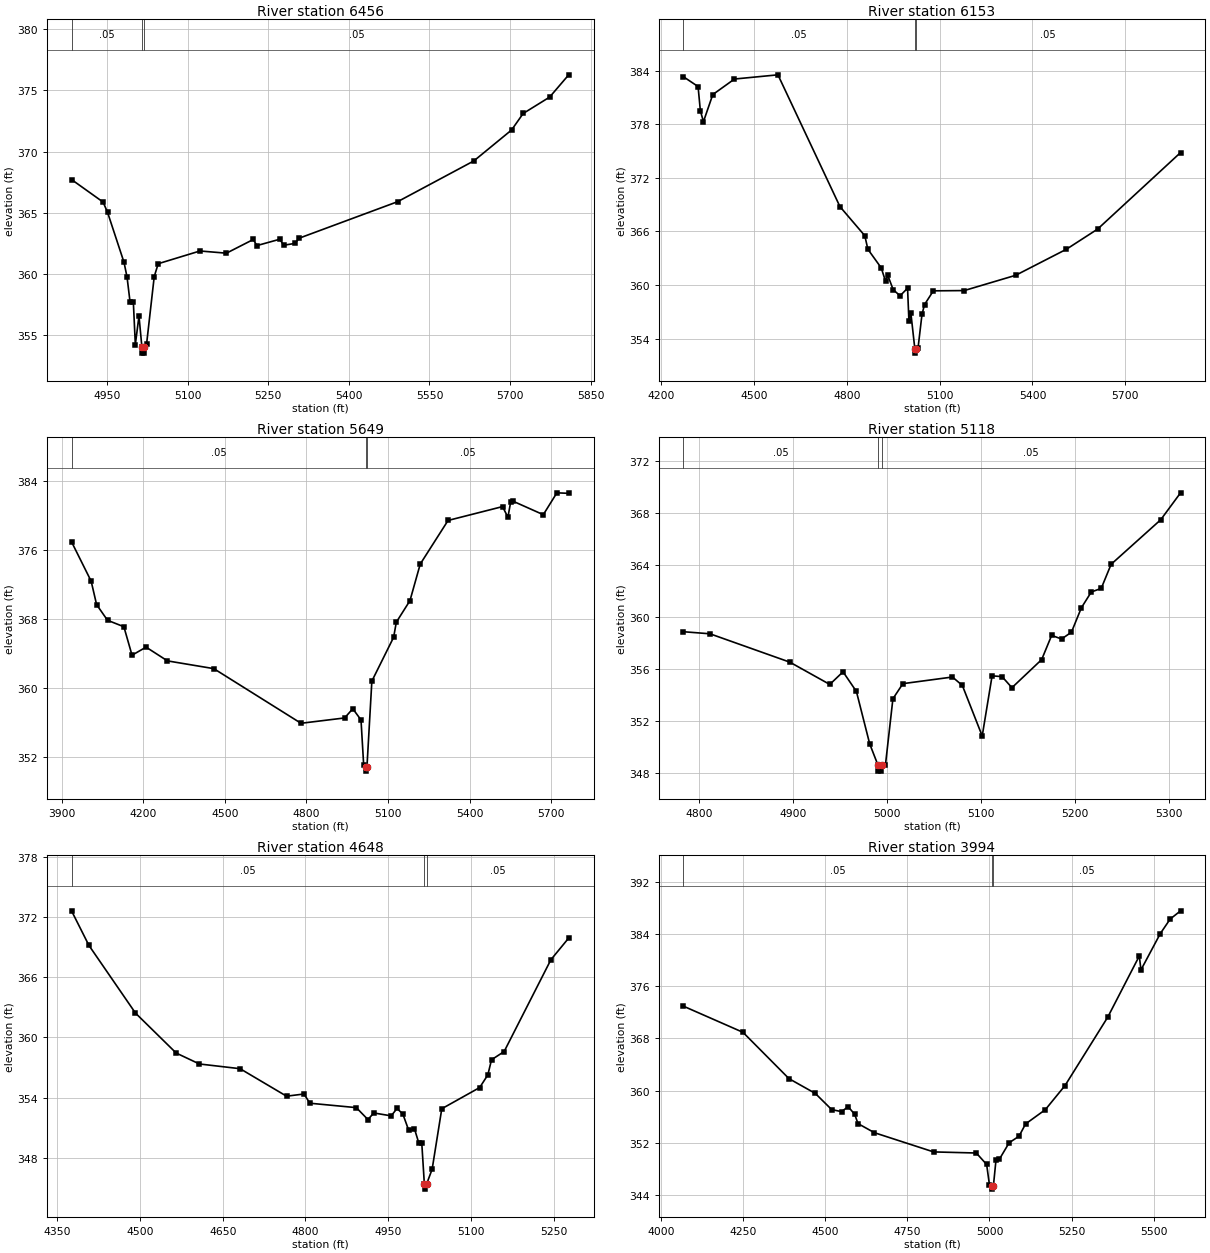
Type RM Length L Ch R = 1,6456,303,303,303
BEGIN DESCRIPTION:
Kings Creek 30_1 11.0
END DESCRIPTION:
XS GIS Cut Line= 3
      2652225.98      6841810.96      2652176.00      6841711.00
      2651576.00      6841161.00
#Sta/Elev= 30
  4883.6  367.72  4942.3  365.88  4950.6  365.05  4981.4  360.94  4987.0  359.74
  4992.6  357.70  4998.7  357.70  5002.4  354.23  5009.2  356.57  5014.6  354.03
  5014.9  353.53  5018.4  353.53  5018.6  354.03  5023.4  354.29  5037.6  359.79
  5045.0  360.84  5122.7  361.88  5172.0  361.70  5222.0  362.82  5228.7  362.32
  5271.3  362.84  5278.7  362.35  5299.7  362.50  5307.1  362.92  5490.8  365.91
  5632.6  369.24  5702.9  371.77  5724.5  373.12  5773.8  374.46  5809.3  376.28
#Mann=3,-1,0
  4883.6    0.05       0  5014.6    0.04       0  5018.6    0.05       0
Bank Sta=5014.6,5018.6
Exp/Cntr=0.3,0.1

Type RM Length L Ch R = 1,6153,504,504,504
BEGIN DESCRIPTION:
Mapping XS a8aac464
END DESCRIPTION:
XS GIS Cut Line= 4
      2652437.95      6842355.77      2652482.22      6841702.15
      2652456.17      6841642.26      2651945.77      6840918.32
#Sta/Elev= 30
  4272.2  383.31  4319.7  382.21  4327.1  379.50  4337.1  378.28  4367.2  381.31
  4437.3  383.05  4577.7  383.52  4778.1  368.77  4858.3  365.52  4868.3  364.00
  4911.4  361.92  4925.4  360.41  4932.2  361.11  4950.2  359.47  4972.2  358.80
  4996.5  359.64  5000.9  355.94  5007.1  356.88  5019.9  352.88  5020.1  352.38
  5023.9  352.88  5030.5  353.00  5043.1  356.72  5051.4  357.82  5079.8  359.35
  5179.5  359.38  5345.8  361.09  5509.5  364.00  5610.5  366.26  5878.4  374.82
#Mann=3,-1,0
  4272.2    0.05       0  5019.9    0.04       0  5023.9    0.05       0
Bank Sta=5019.9,5023.9
Exp/Cntr=0.3,0.1

Type RM Length L Ch R = 1,5649,531,531,531
BEGIN DESCRIPTION:
Mapping XS 37470b28
END DESCRIPTION:
XS GIS Cut Line= 3
      2652753.05      6842473.03      2652823.36      6841415.70
      2652849.40      6840647.51
#Sta/Elev= 30
  3936.0  376.96  4008.2  372.38  4028.2  369.66  4068.3  367.84  4128.5  367.09
  4158.5  363.78  4210.1  364.72  4288.8  363.12  4459.2  362.22  4779.9  355.87
  4940.2  356.49  4970.3  357.56  5000.5  356.26  5010.4  350.97  5018.4  350.81
  5018.6  350.31  5022.4  350.81  5040.4  360.77  5120.4  365.86  5130.4  367.62
  5180.5  370.12  5218.3  374.37  5320.6  379.44  5521.0  381.05  5540.7  379.81
  5550.7  381.55  5560.7  381.66  5670.8  380.11  5720.8  382.65  5764.3  382.59
#Mann=3,-1,0
  3936.0    0.05       0  5018.4    0.03       0  5022.4    0.05       0
Bank Sta=5018.4,5022.4
Exp/Cntr=0.3,0.1

Type RM Length L Ch R = 1,5118,470,470,470
BEGIN DESCRIPTION:
Kings Creek 30_1 8.0
END DESCRIPTION:
XS GIS Cut Line= 3
      2652925.97      6841811.03      2653076.00      6841661.00
      2653176.00      6841361.00
#Sta/Elev= 30
  4783.7  358.88  4812.0  358.72  4896.9  356.54  4939.3  354.83  4953.4  355.80
  4967.6  354.29  4981.7  350.27  4990.3  348.67  4990.6  348.17  4994.1  348.17
  4994.3  348.67  4998.5  348.67  5006.4  353.73  5017.0  354.89  5069.7  355.40
  5080.2  354.75  5101.3  350.87  5111.8  355.49  5122.4  355.43  5132.9  354.58
  5164.5  356.74  5175.1  358.60  5185.6  358.32  5196.1  358.84  5206.7  360.72
  5217.2  361.93  5227.8  362.21  5238.3  364.06  5291.0  367.48  5312.1  369.55
#Mann=3,-1,0
  4783.7    0.05       0  4990.3    0.03       0  4994.3    0.05       0
Bank Sta=4990.3,4994.3
Exp/Cntr=0.3,0.1

Type RM Length L Ch R = 1,4648,654,654,654
BEGIN DESCRIPTION:
Kings Creek 30_1 7.0
END DESCRIPTION:
XS GIS Cut Line= 3
      2653626.01      6842211.02      2653426.00      6841611.00
      2653326.01      6841361.03
#Sta/Elev= 30
  4375.7  372.61  4407.3  369.16  4491.7  362.42  4565.5  358.44  4607.6  357.35
  4681.4  356.88  4765.7  354.14  4797.4  354.36  4807.9  353.44  4892.2  353.00
  4913.3  351.81  4923.8  352.47  4955.5  352.18  4966.0  352.92  4976.6  352.36
  4987.1  350.76  4997.6  350.90  5005.5  349.48  5010.9  349.48  5015.6  345.38
  5015.9  344.88  5019.6  345.38  5029.7  346.86  5047.2  352.89  5115.9  355.00
  5130.7  356.26  5137.4  357.77  5160.3  358.59  5245.1  367.74  5277.4  369.90
#Mann=3,-1,0
  4375.7    0.05       0  5015.6    0.03       0  5019.6    0.05       0
Bank Sta=5015.6,5019.6
Exp/Cntr=0.3,0.1

Type RM Length L Ch R = 1,3994,33,33,33
BEGIN DESCRIPTION:
Mapping XS 79f7ae0b
END DESCRIPTION:
XS GIS Cut Line= 3
      2653930.13      6842582.36      2653966.59      6841663.09
      2653984.82      6841069.36
#Sta/Elev= 30
  4067.9  372.97  4249.4  368.95  4389.5  361.83  4469.6  359.56  4519.6  357.07
  4549.6  356.76  4569.7  357.53  4589.6  356.34  4599.7  354.92  4649.7  353.52
  4829.9  350.57  4960.0  350.40  4991.4  348.64  5000.0  345.49  5008.0  345.35
  5008.2  344.85  5012.0  345.35  5020.0  349.39  5030.0  349.43  5060.0  351.98
  5090.0  352.98  5110.0  354.87  5170.1  357.06  5230.1  360.77  5360.2  371.28
  5456.3  380.68  5461.3  378.54  5520.2  384.12  5550.2  386.35  5581.9  387.62
#Mann=3,-1,0
  4067.9    0.05       0  5008.0    0.03       0  5012.0    0.05       0
Bank Sta=5008,5012
Exp/Cntr=0.3,0.1

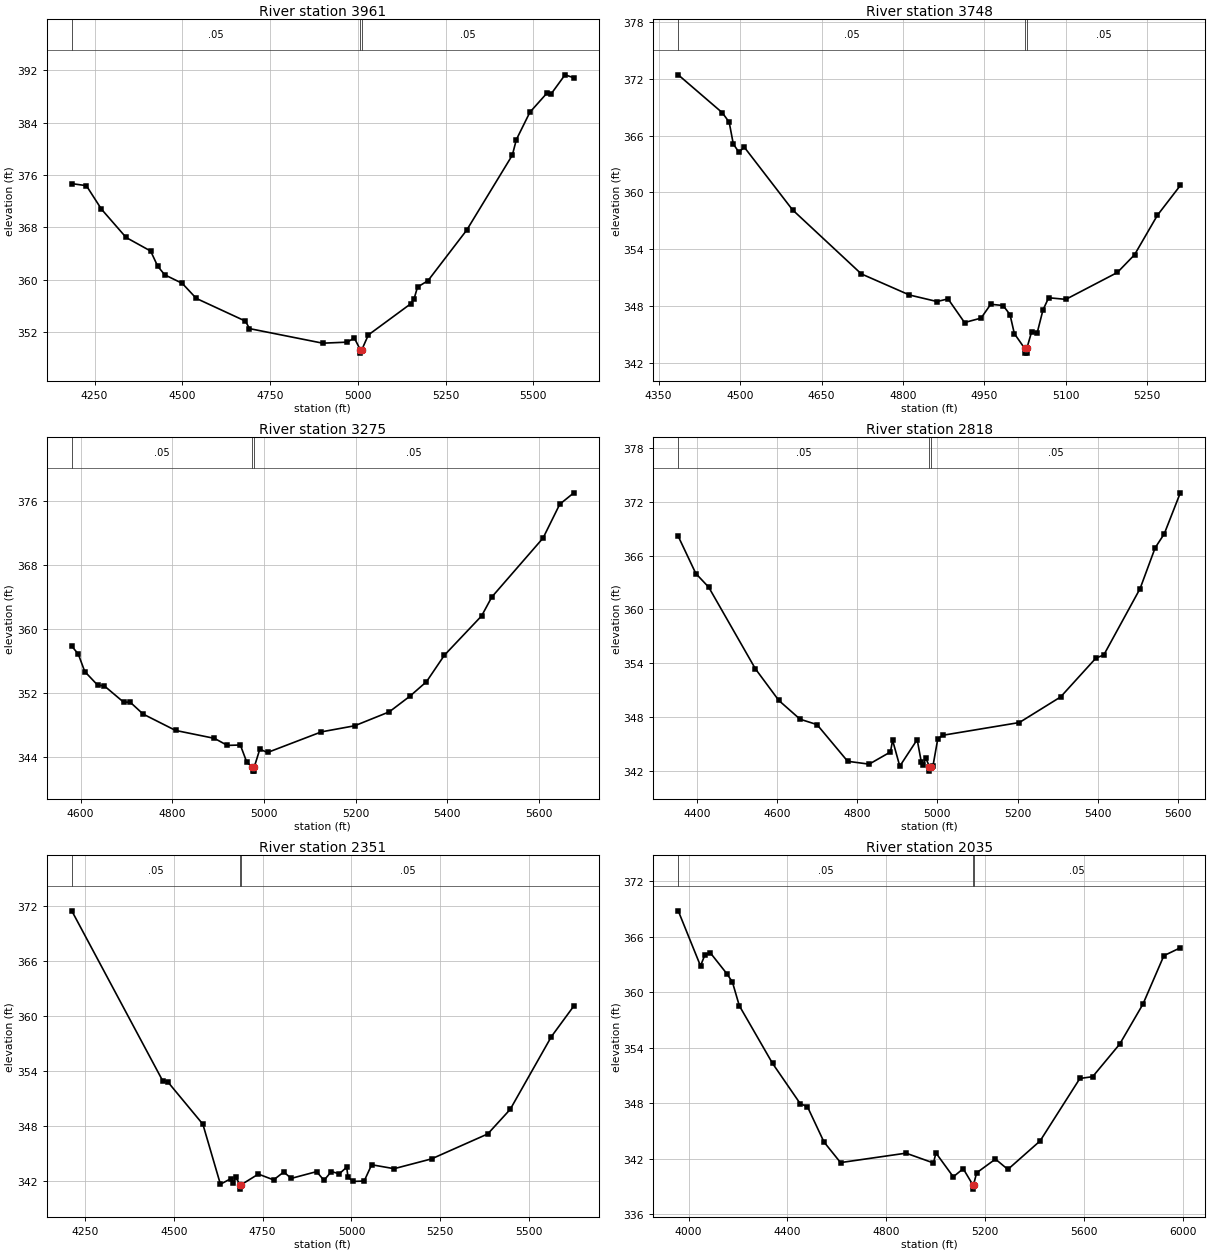
Type RM Length L Ch R = 1,3961,213,213,213
BEGIN DESCRIPTION:
Mapping XS e8829a62
END DESCRIPTION:
XS GIS Cut Line= 4
      2653992.63      6842475.54      2653984.82      6842267.26
      2653997.84      6841647.47      2654016.07      6841045.90
#Sta/Elev= 30
  4185.1  374.67  4226.7  374.36  4269.7  370.76  4339.8  366.44  4409.8  364.36
  4429.8  362.05  4449.8  360.73  4499.8  359.42  4539.8  357.12  4679.9  353.64
  4691.3  352.50  4899.9  350.27  4969.9  350.43  4989.9  351.07  5007.2  349.25
  5007.4  348.75  5011.2  349.25  5029.9  351.53  5150.0  356.27  5160.0  357.02
  5170.0  358.85  5200.0  359.84  5310.1  367.56  5440.1  379.03  5451.5  381.40
  5490.1  385.59  5540.2  388.60  5550.2  388.36  5590.2  391.31  5615.3  390.86
#Mann=3,-1,0
  4185.1    0.05       0  5007.2    0.03       0  5011.2    0.05       0
Bank Sta=5007.2,5011.2
Exp/Cntr=0.3,0.1

Type RM Length L Ch R = 1,3748,473,473,473
BEGIN DESCRIPTION:
Kings Creek 30_1 5.0
END DESCRIPTION:
XS GIS Cut Line= 3
      2654075.99      6842361.04      2654176.00      6841761.00
      2654076.01      6841461.04
#Sta/Elev= 30
  4386.2  372.41  4467.3  368.41  4480.0  367.41  4487.6  365.10  4497.8  364.25
  4507.9  364.76  4596.6  358.15  4723.3  351.38  4812.0  349.15  4862.7  348.46
  4883.0  348.74  4913.4  346.24  4943.8  346.71  4961.6  348.17  4984.4  348.04
  4997.1  347.08  5005.1  345.07  5024.1  343.51  5024.4  343.01  5027.9  343.01
  5028.1  343.51  5036.7  345.23  5047.2  345.16  5057.8  347.57  5068.3  348.86
  5099.9  348.69  5194.8  351.53  5226.4  353.40  5268.6  357.58  5310.7  360.72
#Mann=3,-1,0
  4386.2    0.05       0  5024.1    0.04       0  5028.1    0.05       0
Bank Sta=5024.1,5028.1
Exp/Cntr=0.3,0.1

Type RM Length L Ch R = 1,3275,457,457,457
BEGIN DESCRIPTION:
Kings Creek 30_1 4.0
END DESCRIPTION:
XS GIS Cut Line= 3
      2654275.99      6842261.01      2654576.00      6841961.00
      2654876.00      6841361.00
#Sta/Elev= 30
  4580.8  357.87  4595.0  356.89  4609.1  354.71  4637.4  353.00  4651.5  352.93
  4694.0  350.88  4708.1  350.89  4736.4  349.40  4807.1  347.36  4891.9  346.37
  4920.2  345.49  4948.5  345.54  4962.7  343.37  4974.8  342.78  4975.0  342.28
  4978.5  342.28  4978.8  342.78  4990.9  345.01  5007.9  344.61  5125.3  347.18
  5197.9  347.94  5273.4  349.68  5318.1  351.62  5354.5  353.44  5393.6  356.75
  5474.7  361.65  5497.0  364.01  5608.8  371.37  5645.2  375.59  5675.9  377.01
#Mann=3,-1,0
  4580.8    0.05       0  4974.8    0.04       0  4978.8    0.05       0
Bank Sta=4974.8,4978.8
Exp/Cntr=0.3,0.1

Type RM Length L Ch R = 1,2818,467,467,467
BEGIN DESCRIPTION:
Kings Creek 30_1 3.0
END DESCRIPTION:
XS GIS Cut Line= 3
      2654725.99      6842661.02      2654976.00      6842061.00
      2654926.00      6841461.00
#Sta/Elev= 30
  4353.9  368.17  4397.8  364.01  4429.8  362.49  4546.2  353.37  4604.7  349.83
  4657.8  347.73  4700.0  347.13  4776.4  343.03  4830.0  342.71  4883.1  344.07
  4888.5  345.38  4906.4  342.48  4949.8  345.45  4960.0  342.97  4965.5  342.67
  4971.4  343.38  4980.3  342.43  4980.5  341.93  4984.3  342.43  4989.3  342.54
  5001.2  345.55  5014.0  345.94  5204.6  347.36  5307.5  350.22  5395.3  354.55
  5415.3  354.92  5505.7  362.33  5543.3  366.89  5565.9  368.44  5606.0  373.03
#Mann=3,-1,0
  4353.9    0.05       0  4980.3    0.04       0  4984.3    0.05       0
Bank Sta=4980.3,4984.3
Exp/Cntr=0.3,0.1

Type RM Length L Ch R = 1,2351,316,316,316
BEGIN DESCRIPTION:
Kings Creek 30_1 2.0
END DESCRIPTION:
XS GIS Cut Line= 3
      2654775.98      6842761.01      2655376.00      6842261.00
      2655176.00      6841661.00
#Sta/Elev= 30
  4212.6  371.52  4468.4  352.99  4482.7  352.87  4581.7  348.24  4631.1  341.69
  4659.8  342.29  4667.6  341.82  4674.1  342.44  4686.4  341.66  4686.6  341.16
  4690.4  341.66  4737.9  342.80  4780.8  342.17  4809.5  343.03  4830.3  342.33
  4901.9  343.07  4922.7  342.12  4943.5  343.08  4965.7  342.83  4986.5  343.55
  4990.4  342.48  5004.2  342.00  5035.8  342.04  5056.9  343.82  5120.1  343.39
  5225.5  344.46  5383.7  347.18  5446.9  349.86  5562.9  357.80  5626.1  361.14
#Mann=3,-1,0
  4212.6    0.05       0  4686.4    0.03       0  4690.4    0.05       0
Bank Sta=4686.4,4690.4
Exp/Cntr=0.3,0.1

Type RM Length L Ch R = 1,2035,422,422,422
BEGIN DESCRIPTION:
Mapping XS 6c969e6b
END DESCRIPTION:
XS GIS Cut Line= 5
      2655352.02      6843268.81      2655703.00      6842562.04
      2655674.15      6842326.45      2655640.50      6841869.69
      2655179.98      6841577.07
#Sta/Elev= 30
  3958.4  368.80  4048.5  362.84  4065.3  363.98  4087.7  364.27  4154.9  362.00
  4177.3  361.11  4205.3  358.54  4339.7  352.30  4451.8  347.94  4480.7  347.62
  4547.7  343.80  4614.7  341.57  4879.5  342.59  4990.3  341.53  5000.4  342.61
  5070.6  340.03  5110.7  340.91  5148.7  339.20  5149.0  338.70  5152.9  339.20
  5164.8  340.46  5241.0  341.95  5291.2  340.83  5421.5  343.91  5582.4  350.67
  5634.0  350.86  5743.3  354.38  5837.3  358.70  5922.1  363.95  5988.5  364.80
#Mann=3,-1,0
  3958.4    0.05       0  5148.7    0.04       0  5152.9    0.05       0
Bank Sta=5148.7,5152.9
Exp/Cntr=0.3,0.1

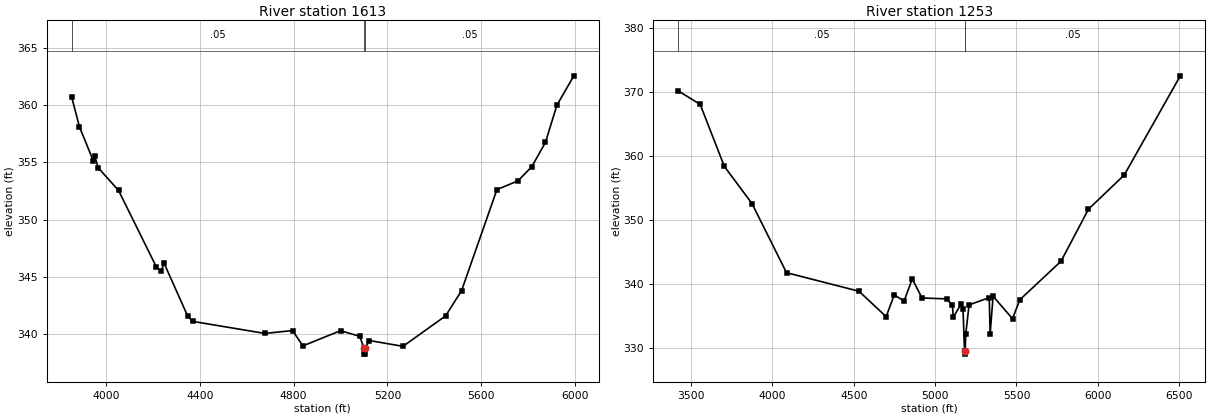
Type RM Length L Ch R = 1,1613,360,360,360
BEGIN DESCRIPTION:
Mapping XS 48f84ada
END DESCRIPTION:
XS GIS Cut Line= 5
      2655584.68      6843183.42      2656053.42      6842357.93
      2656048.21      6842165.22      2656011.75      6842014.18
      2655282.57      6841587.09
#Sta/Elev= 30
  3853.2  360.69  3885.5  358.14  3944.6  355.16  3950.4  355.60  3966.2  354.53
  4052.7  352.55  4214.3  345.86  4235.9  345.47  4246.0  346.24  4348.4  341.54
  4370.0  341.10  4677.1  340.05  4795.4  340.30  4839.4  338.96  5000.0  340.29
  5081.9  339.80  5100.4  338.74  5100.7  338.24  5104.2  338.24  5104.6  338.74
  5123.1  339.43  5266.6  338.92  5448.3  341.58  5516.6  343.79  5667.3  352.62
  5757.3  353.39  5815.9  354.62  5874.6  356.75  5923.3  360.00  5995.7  362.57
#Mann=3,-1,0
  3853.2    0.05       0  5100.4    0.04       0  5104.6    0.05       0
Bank Sta=5100.4,5104.6
Exp/Cntr=0.3,0.1

Type RM Length L Ch R = 1,1253,0,0,0
BEGIN DESCRIPTION:
Kings Creek 30_1 1.0
END DESCRIPTION:
XS GIS Cut Line= 5
      2655424.15      6843369.78      2656289.51      6842538.09
      2656315.84      6842160.84      2656289.51      6841972.99
      2655075.98      6841460.99
#Sta/Elev= 30
  3421.6  370.15  3556.4  368.04  3704.9  358.37  3874.7  352.57  4086.9  341.78
  4532.5  338.88  4699.1  334.92  4749.2  338.33  4809.4  337.34  4859.5  340.81
  4919.6  337.83  5070.5  337.69  5106.4  336.73  5111.4  334.82  5161.4  336.96
  5171.5  336.15  5180.7  329.57  5181.0  329.07  5184.9  329.57  5188.2  332.16
  5208.7  336.75  5332.7  337.89  5338.2  332.25  5356.3  338.10  5475.7  334.60
  5520.4  337.55  5773.9  343.57  5942.4  351.69  6162.2  357.02  6506.8  372.50
#Mann=3,-1,0
  3421.6    0.05       0  5180.7    0.04       0  5184.9    0.05       0
Bank Sta=5180.7,5184.9
Exp/Cntr=0.3,0.1

Chan Stop Cuts=-1