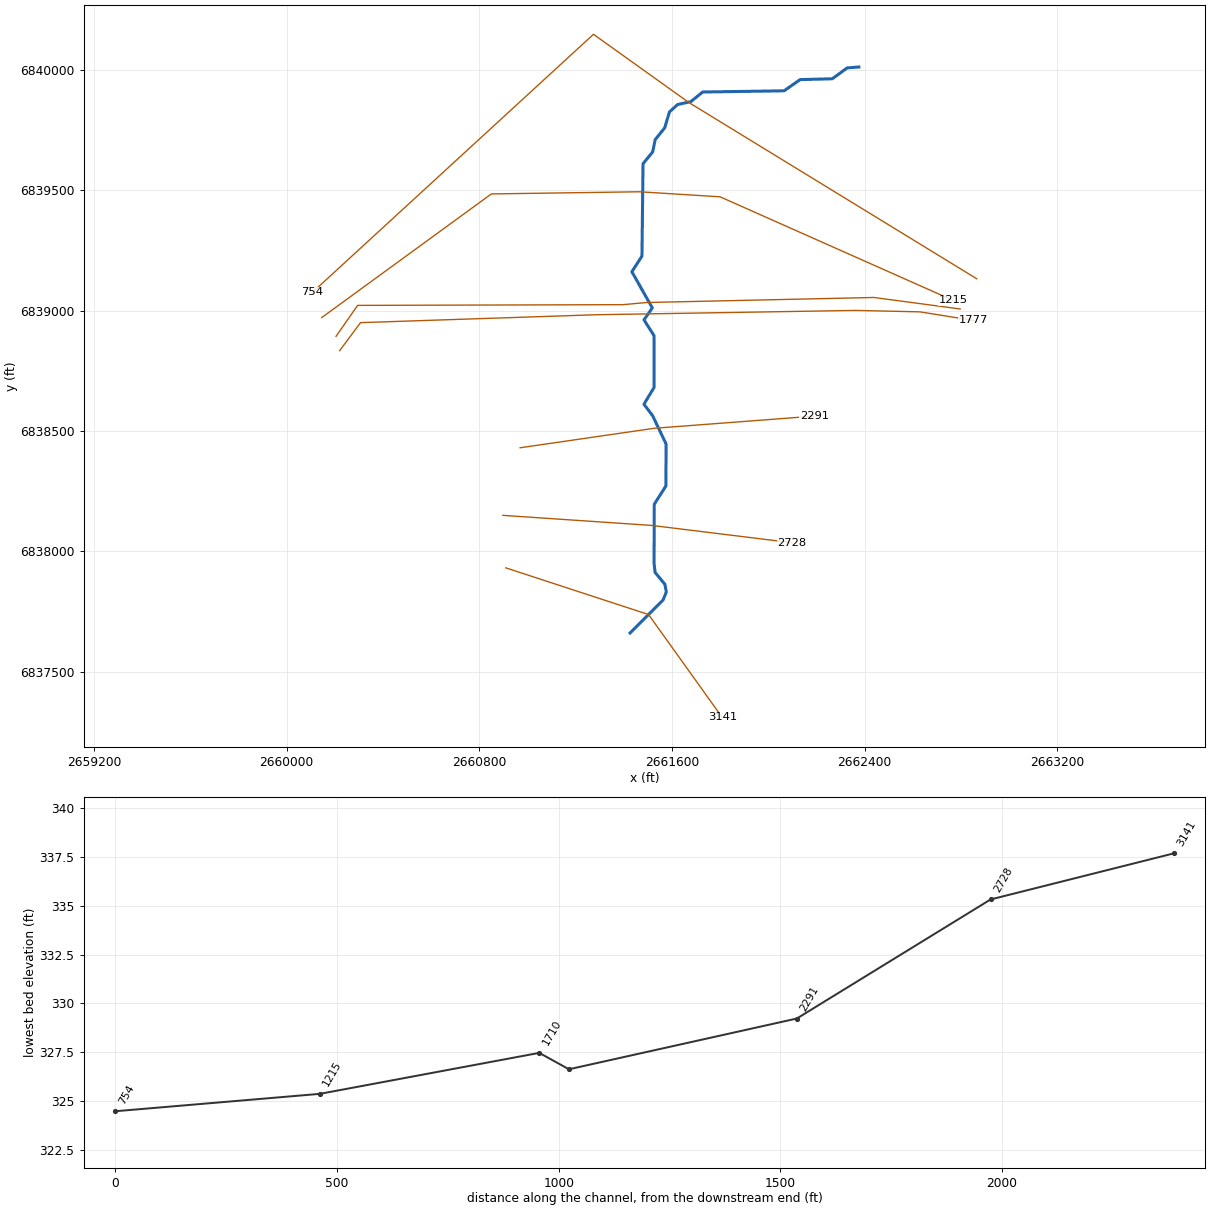
--- Kings Creek 31_1.prj (project) ---

Proj Title=Kings Creek 31_1 Base Level Engineering
Current Plan=p01
Default Exp/Contr=0.3,0.1
English Units
Geom File=g01
Flow File=f01
Plan File=p01
Y Axis Title=Elevation
X Axis Title(PF)=Main Channel Distance
X Axis Title(XS)=Station
BEGIN DESCRIPTION:
Kings Creek 31_1
END DESCRIPTION:
DSS Export Rating Curves= 0
DSS Export Rating Curve Sorted= 0
DSS Export Volume Flow Curves= 0
DXF OffsetX= 0
DXF OffsetY= 0
DXF ScaleX= 1
DXF ScaleY= 10

--- Kings Creek 31_1.p01 (plan) ---

Plan Title=Multiple Run
Short Identifier=Multiple
Geom File=g01
Flow File=f01
Subcritical Flow
K Sum by GR= 0
Std Step Tol= 0.01
Critical Tol= 0.01
Num of Std Step Trials= 20
Max Error Tol= 0.3
Flow Tol Ratio= 0.001
Split Flow NTrial= 30
Split Flow Tol= 0.02
Split Flow Ratio= 0.02
Log Output Level= 0
Friction Slope Method= 1
Unsteady Friction Slope Method= 2
Unsteady Bridges Friction Slope Method= 1
Parabolic Critical Depth
Global Vel Dist=  1 , 1 , 1
Global Log Level= 0
CheckData=True
Encroach Param= -1, 0, 0, 0
BEGIN DESCRIPTION:
Multiple Run
END DESCRIPTION:

--- Kings Creek 31_1.f01 (steady flow) ---

Flow Title=Multiple
Program Version=4.10
Number of Profiles= 7
Profile Names=10-year,25-year,50-year,1pct_min,100-year,1pct_plu,500-year
River Rch & RM=Kings Creek 31_1,Reach-1         ,3141
     439     577     686     406     809    1615    1124
Boundary for River Rch & Prof#=Kings Creek 31_1,Reach-1         , 1
Up Type= 0
Dn Type= 3
Dn Slope=0.00192
Boundary for River Rch & Prof#=Kings Creek 31_1,Reach-1         , 2
Up Type= 0
Dn Type= 3
Dn Slope=0.00192
Boundary for River Rch & Prof#=Kings Creek 31_1,Reach-1         , 3
Up Type= 0
Dn Type= 3
Dn Slope=0.00192
Boundary for River Rch & Prof#=Kings Creek 31_1,Reach-1         , 4
Up Type= 0
Dn Type= 3
Dn Slope=0.00192
Boundary for River Rch & Prof#=Kings Creek 31_1,Reach-1         , 5
Up Type= 0
Dn Type= 3
Dn Slope=0.00192
Boundary for River Rch & Prof#=Kings Creek 31_1,Reach-1         , 6
Up Type= 0
Dn Type= 3
Dn Slope=0.00192
Boundary for River Rch & Prof#=Kings Creek 31_1,Reach-1         , 7
Up Type= 0
Dn Type= 3
Dn Slope=0.00192
DSS Import GetInterval= 0
DSS Import GetPeak= 0
DSS Import FillOption= 0

--- Kings Creek 31_1.g01 (geometry) ---

Geom Title=Existing Conditions
Program Version=4.10

River Reach=Kings Creek 31_1,Reach-1
Reach XY= 30
        2661426.        6837661.      2661562.89      6837797.78
       2661576.4      6837831.13      2661570.65      6837863.17
      2661529.81      6837912.55      2661525.55      6837950.81
      2661526.52      6838195.78      2661574.78      6838271.51
      2661575.49      6838445.79      2661519.61      6838563.29
      2661483.53      6838610.99      2661525.82      6838680.98
      2661525.35      6838895.84       2661483.8       6838961.1
      2661518.23      6839010.92      2661433.53      6839160.99
      2661475.34      6839226.16      2661479.75      6839609.45
      2661519.88      6839658.82      2661530.16      6839709.28
      2661569.89      6839758.84      2661589.47      6839824.57
      2661623.45      6839855.27      2661678.15      6839867.15
      2661727.55      6839907.25       2662065.5      6839912.22
      2662131.94      6839958.73      2662265.53      6839962.13
      2662327.51      6840007.35        2662376.        6840011.

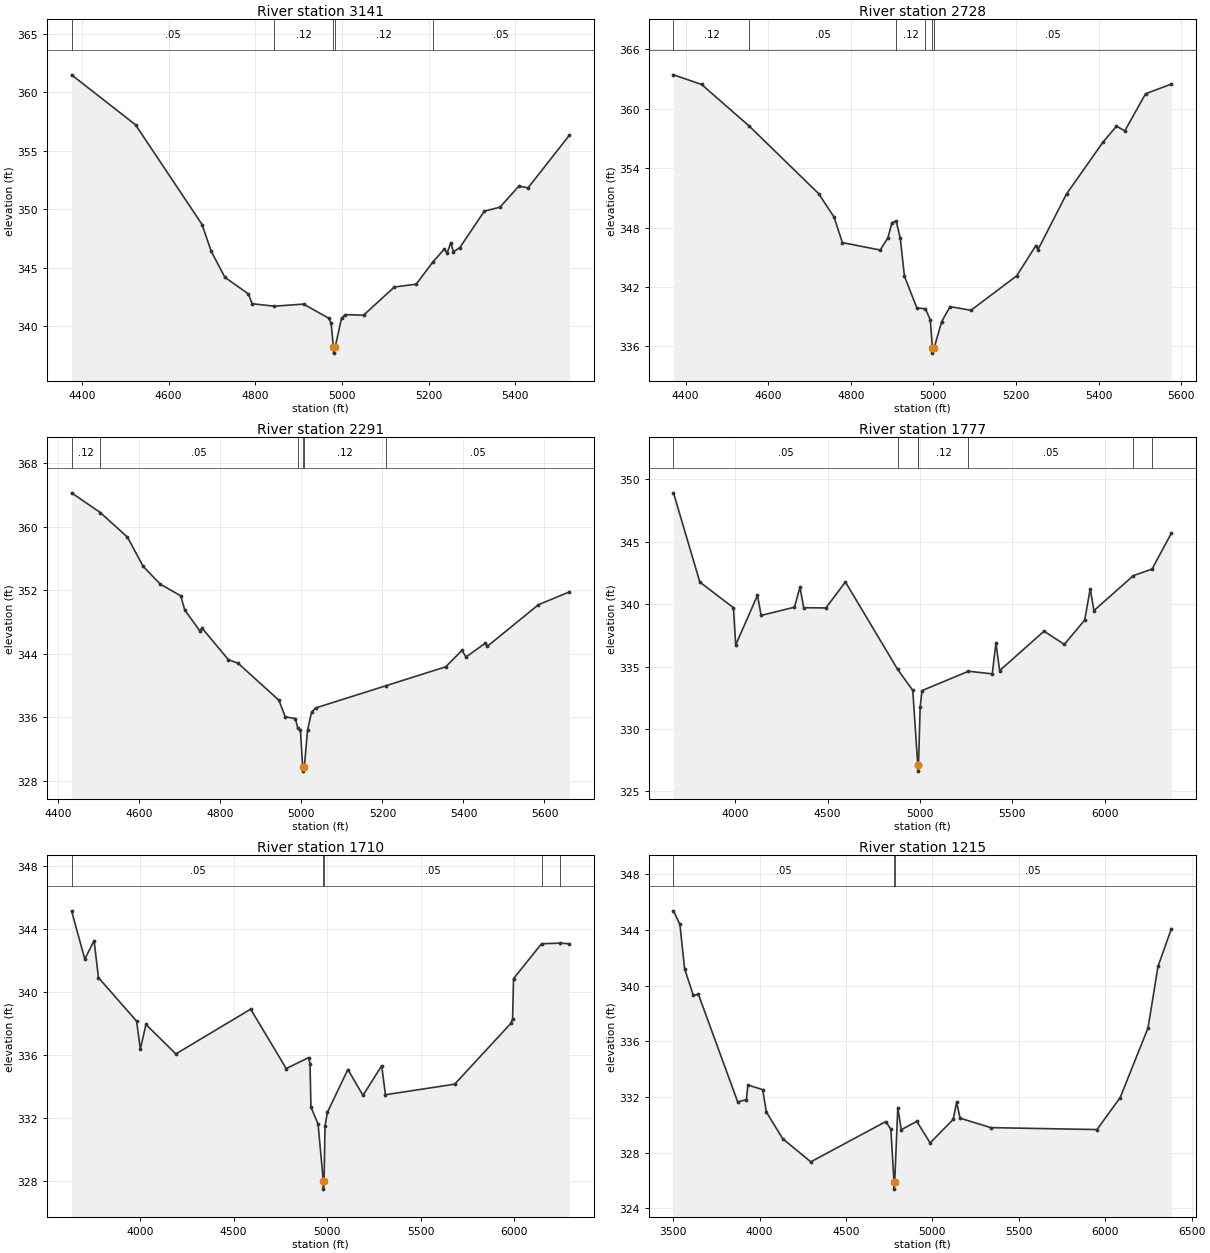
Type RM Length L Ch R = 1 ,3141    ,413,413,413
BEGIN DESCRIPTION:
Kings Creek 31_1 4.0
END DESCRIPTION:
XS GIS Cut Line= 3
      2660909.77      6837931.61      2661502.75      6837737.64
      2661808.47      6837310.59
#Sta/Elev= 30
  4376.1  361.47  4523.7   357.2  4677.3  348.68  4698.3   346.4  4729.9  344.17
  4783.9  342.76    4793  341.91  4844.4   341.7  4911.4  341.88  4969.8  340.67
  4975.1  340.23  4980.4  338.19  4980.6  337.69  4984.4  338.19  4999.1  340.68
  5008.1  340.98  5049.9  340.93  5121.1  343.34  5171.5  343.58  5209.5  345.46
  5236.6  346.59  5242.7  346.24  5251.3  347.12  5257.5  346.35  5272.2  346.71
  5328.7  349.82  5364.8  350.16  5408.6  351.97  5429.5  351.81  5525.2  356.32
#Mann= 5 ,-1 , 0
  4376.1     .05       0  4844.4     .12       0  4980.4     .07       0
  4984.4     .12       0  5209.5     .05       0
Bank Sta=4980.4,4984.4
XS Rating Curve= 0 ,0
Exp/Cntr=0.3,0.1

Type RM Length L Ch R = 1 ,2728    ,437,437,437
BEGIN DESCRIPTION:
Mapping XS 567fc7b1
END DESCRIPTION:
XS GIS Cut Line= 3
      2660897.91      6838149.53      2661515.87      6838107.74
        2662098.      6838036.09
#Sta/Elev= 30
  4370.5   363.4  4438.7  362.43  4554.5  358.21  4721.8  351.43  4759.5  349.05
  4779.5  346.48  4871.1  345.73  4889.8  346.95  4899.8   348.5  4909.9  348.65
  4919.8  346.93  4929.9  343.08  4959.9   339.9  4980.8   339.8  4992.5  338.69
  4997.6  335.83  4997.8  335.33  5001.6  335.83  5020.2  338.52  5040.4  340.02
  5090.9  339.65  5201.6  343.12  5248.3  346.18  5253.4  345.78  5322.5  351.39
  5410.8  356.61  5443.4  358.22  5463.6  357.75  5513.9  361.49  5576.4  362.47
#Mann= 6 ,-1 , 0
  4370.5     .12       0  4554.5     .05       0  4909.9     .12       0
  4980.8     .05       0  4997.6     .03       0  5001.6     .05       0
Bank Sta=4997.6,5001.6
XS Rating Curve= 0 ,0
Exp/Cntr=0.3,0.1

Type RM Length L Ch R = 1 ,2291    ,514,514,514
BEGIN DESCRIPTION:
Kings Creek 31_1 3.0
END DESCRIPTION:
XS GIS Cut Line= 3
      2660969.49      6838430.17        2661526.        6838511.
      2662190.63      6838561.54
#Sta/Elev= 30
  4432.8  364.29  4503.9   361.8  4570.7  358.71  4609.3  355.04  4651.6  352.79
  4702.1  351.32  4712.2  349.53  4749.6  346.88  4754.7  347.26  4819.8  343.27
  4843.6  342.83  4944.6  338.16  4960.1  336.08    4985  335.84  4991.3  334.65
  4997.7   334.4  5003.2  329.73  5003.4  329.23  5007.2  329.73  5015.2   334.4
  5025.2  336.67  5035.3  337.19  5209.4     340  5356.2  342.37  5396.3  344.44
  5406.3  343.61  5454.1  345.35  5459.1  344.96  5585.2   350.2  5661.7  351.81
#Mann= 6 ,-1 , 0
  4432.8     .12       0  4503.9     .05       0  4991.3     .12       0
  5003.2     .08       0  5007.2     .12       0  5209.4     .05       0
Bank Sta=5003.2,5007.2
XS Rating Curve= 0 ,0
Exp/Cntr=0.3,0.1

Type RM Length L Ch R = 1 ,1777    ,67,67,67
BEGIN DESCRIPTION:
Mapping XS ee77f800
END DESCRIPTION:
XS GIS Cut Line= 6
      2660220.17      6838833.23      2660306.74      6838949.65
      2661285.99      6838982.49      2662360.77      6839000.41
      2662629.46      6838994.44      2662852.23      6838958.79
#Sta/Elev= 30
  3666.1  348.92  3808.9  341.77  3990.5  339.72    4003  336.74  4120.6  340.71
  4140.6   339.1  4320.7  339.76  4350.7  341.37  4370.8  339.72  4490.8   339.7
  4596.6  341.78  4879.5  334.77    4961   333.1    4988  327.13  4988.3  326.63
    4992  327.13    5001  331.75    5011  333.08  5262.4  334.63  5391.1  334.42
  5411.1  336.91  5431.1  334.68  5671.2  337.84  5781.2  336.78  5891.3  338.73
  5921.3  341.24  5941.3  339.49    6155  342.29  6255.6  342.81  6360.4  345.69
#Mann= 7 ,-1 , 0
  3666.1     .05       0  4879.5     .12       0    4988     .07       0
    4992     .12       0  5262.4     .05       0    6155    .075       0
  6255.6     .05       0
Bank Sta=4988,4992
XS Rating Curve= 0 ,0
Exp/Cntr=0.3,0.1

Type RM Length L Ch R = 1 ,1710    ,495,495,495
BEGIN DESCRIPTION:
Mapping XS c7ae26f3
END DESCRIPTION:
XS GIS Cut Line= 6
      2660205.25      6838892.95       2660294.8      6839021.31
      2661396.45      6839024.29      2661494.97      6839033.25
      2662438.39      6839054.15      2662796.68      6839006.37
#Sta/Elev= 30
  3634.1  345.13  3704.9  342.07  3754.4  343.24    3778  340.89  3981.8  338.13
  4001.8  336.35  4031.8  337.92  4191.8  336.05  4591.8  338.89  4781.8  335.12
  4901.9  335.82    4909  335.41    4914  332.67  4952.1   331.6  4980.2  327.97
  4980.4  327.47  4984.2  327.97  4989.2  331.47  5002.2  332.35  5111.4  335.06
  5192.3  333.42  5292.3   335.3  5312.3  333.46  5682.4  334.13  5982.9  337.99
  5992.2  338.29  5997.2  340.83  6146.8  343.04    6247  343.08  6296.3  343.04
#Mann= 5 ,-1 , 0
  3634.1     .05       0  4980.2     .07       0  4984.2     .05       0
  6146.8    .075       0    6247     .05       0
Bank Sta=4980.2,4984.2
XS Rating Curve= 0 ,0
Exp/Cntr=0.3,0.1

Type RM Length L Ch R = 1 ,1215    ,461,461,461
BEGIN DESCRIPTION:
Mapping XS 1ea22d24
END DESCRIPTION:
XS GIS Cut Line= 5
      2660145.51      6838970.54       2660850.1      6839484.06
      2661465.12      6839493.02      2661799.49      6839472.12
      2662766.78      6839042.21
#Sta/Elev= 30
  3502.2  345.37  3539.6  344.39  3566.6  341.21  3616.9   339.3  3646.2  339.38
  3874.1  331.63  3924.3  331.81  3932.8  332.85  4018.6  332.52  4039.4  330.92
  4133.7     329  4296.7  327.33    4730  330.22    4760  329.68    4778  325.87
  4778.3  325.37    4782  325.87    4800  331.23    4820  329.64    4910  330.24
  4987.1  328.69  5120.3  330.38  5140.3  331.61  5160.4  330.47    5338  329.79
  5952.2  329.65  6086.4  331.95  6247.7  336.96  6305.2  341.37  6382.7  344.09
#Mann= 3 ,-1 , 0
  3502.2     .05       0    4778     .04       0    4782     .05       0
Bank Sta=4778,4782
XS Rating Curve= 0 ,0
Exp/Cntr=0.3,0.1

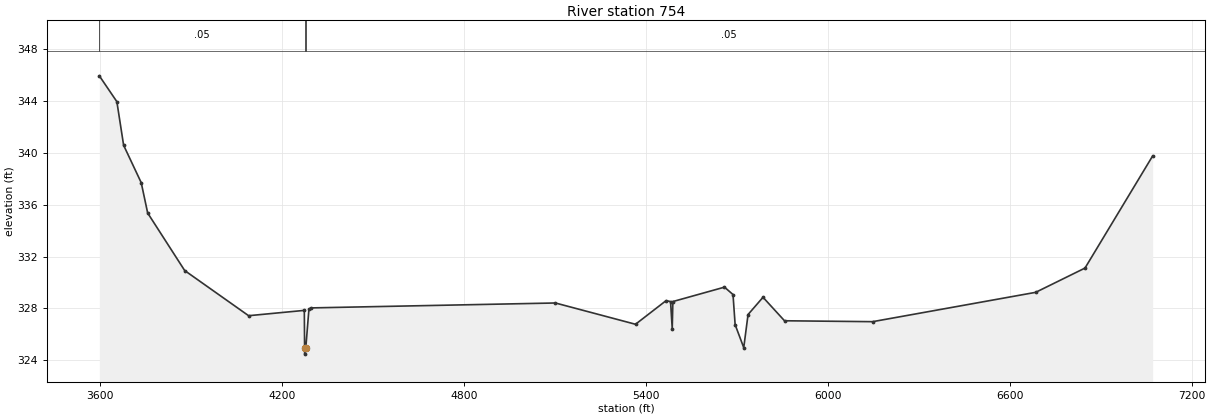
Type RM Length L Ch R = 1 ,754     ,0,0,0
BEGIN DESCRIPTION:
Kings Creek 31_1 1.0
END DESCRIPTION:
XS GIS Cut Line= 4
      2662865.33      6839131.76      2661669.83      6839863.76
      2661274.04      6840146.84      2660106.75      6839075.08
#Sta/Elev= 30
  3598.2  345.92    3656  343.93  3678.3  340.57  3736.3  337.69  3757.6  335.35
  3879.6  330.92  4090.4  327.44  4274.1  327.85    4275  324.98  4275.3  324.48
    4279  324.98  4289.2  327.92  4295.4  328.04    5102  328.42  5366.1  326.78
  5466.9   328.6  5481.6  328.53  5487.2  326.44  5489.3  328.53  5659.5  329.64
  5687.6  329.07  5694.6  326.75    5723  324.98  5737.2  327.53  5786.5  328.86
  5857.4  327.05  6147.8  326.98  6685.5  329.24  6848.2  331.11  7071.3  339.75
#Mann= 3 ,-1 , 0
  3598.2     .05       0    4275     .04       0    4279     .05       0
Bank Sta=4275,4279
XS Rating Curve= 0 ,0
Exp/Cntr=0.3,0.1

Chan Stop Cuts=-1
Use User Specified Reach Order=0
Composite Channel Slope=5