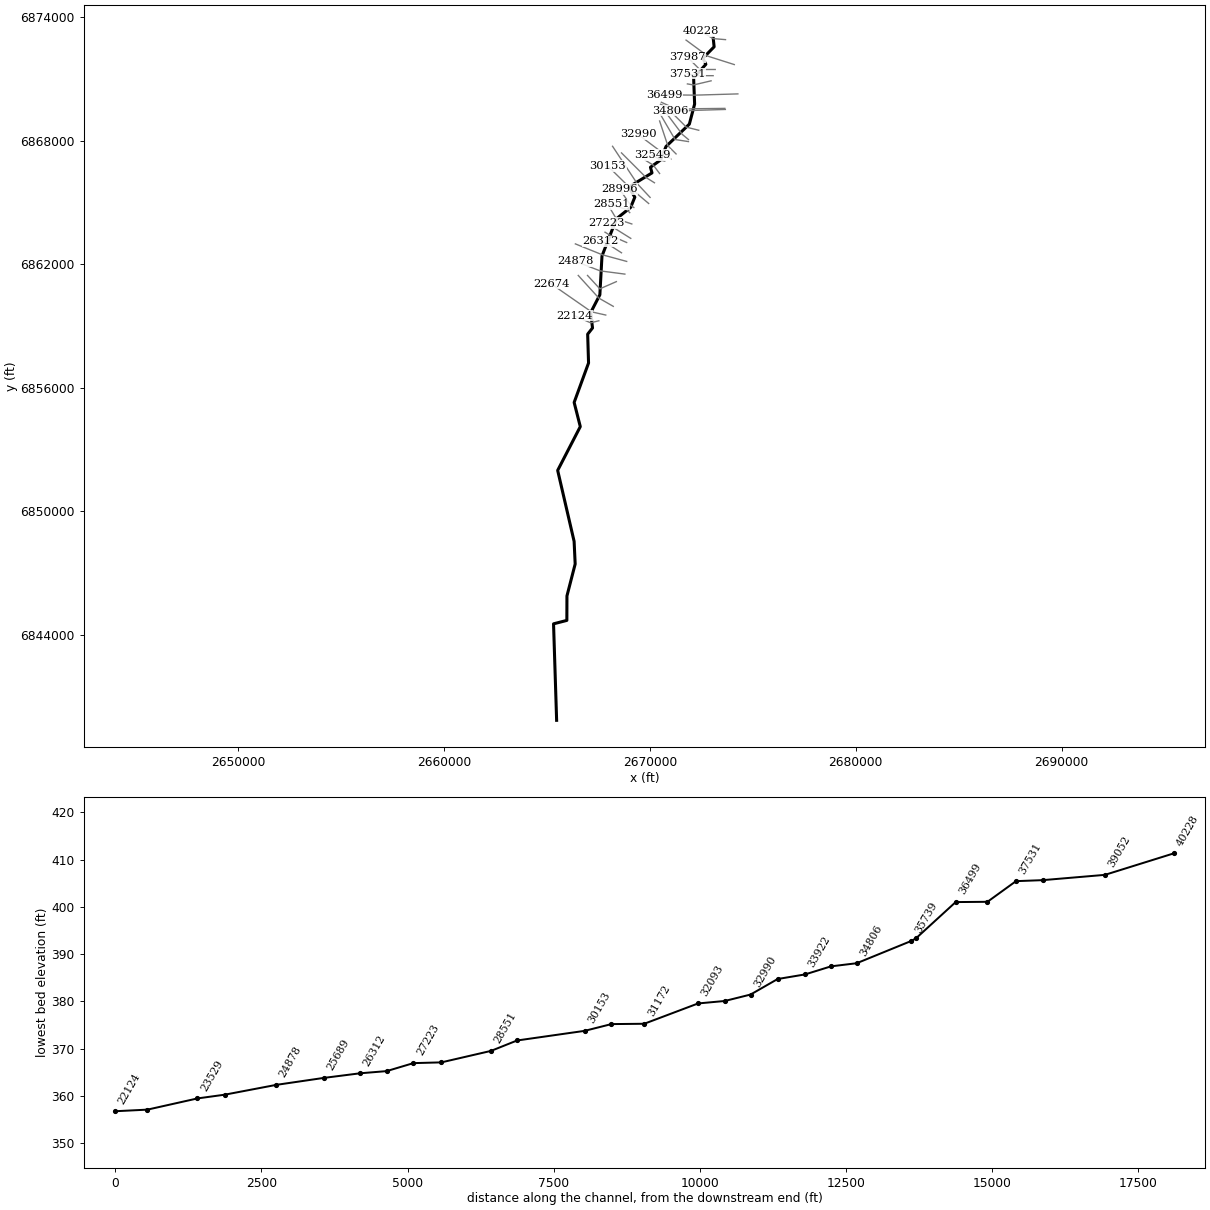
--- Kings Creek 32.prj (project) ---

Proj Title=Kings Creek 32 Base Level Engineering
Current Plan=p01
Default Exp/Contr=0.3,0.1
English Units
Geom File=g01
Flow File=f01
Plan File=p01
Y Axis Title=Elevation
X Axis Title(PF)=Main Channel Distance
X Axis Title(XS)=Station
BEGIN DESCRIPTION:
Kings Creek 32
END DESCRIPTION:
DSS Export Rating Curves= 0
DSS Export Rating Curve Sorted= 0
DSS Export Volume Flow Curves= 0
DXF OffsetX= 0
DXF OffsetY= 0
DXF ScaleX= 1
DXF ScaleY= 10

--- Kings Creek 32.p01 (plan) ---

Plan Title=Multiple Run
Short Identifier=Multiple
Geom File=g01
Flow File=f01
Subcritical Flow
K Sum by GR= 0
Std Step Tol= 0.01
Critical Tol= 0.01
Num of Std Step Trials= 20
Max Error Tol= 0.3
Flow Tol Ratio= 0.001
Split Flow NTrial= 30
Split Flow Tol= 0.02
Split Flow Ratio= 0.02
Log Output Level= 0
Friction Slope Method= 1
Unsteady Friction Slope Method= 2
Unsteady Bridges Friction Slope Method= 1
Parabolic Critical Depth
Global Vel Dist=  1 , 1 , 1
Global Log Level= 0
CheckData=True
Encroach Param= -1, 0, 0, 0
BEGIN DESCRIPTION:
Multiple Run
END DESCRIPTION:

--- Kings Creek 32.f01 (steady flow) ---

Flow Title=Multiple
Program Version=4.10
Number of Profiles= 7
Profile Names=10-year,25-year,50-year,1pct_min,100-year,1pct_plu,500-year
River Rch & RM=Kings Creek 32,Reach-1         ,40228
     431     567     674     398     794    1585    1102
River Rch & RM=Kings Creek 32,Reach-1         ,39052
     652     878    1062     637    1271    2536    1819
River Rch & RM=Kings Creek 32,Reach-1         ,34806
     748    1016    1234     743    1482    2957    2139
River Rch & RM=Kings Creek 32,Reach-1         ,33454
     915    1259    1544     938    1871    3733    2748
River Rch & RM=Kings Creek 32,Reach-1         ,31172
    1039    1434    1762    1071    2137    4264    3147
River Rch & RM=Kings Creek 32,Reach-1         ,28996
    1275    1770    2183    1331    2655    5297    3931
River Rch & RM=Kings Creek 32,Reach-1         ,21214
    1287    1787    2204    1343    2680    5347    3967
River Rch & RM=Kings Creek 32,Reach-1         ,20749
    1849    2611    3257    2006    4002    7984    6049
River Rch & RM=Kings Creek 32,Reach-1         ,17805
    1972    2786    3474    2138    4266    8513    6443
River Rch & RM=Kings Creek 32,Reach-1         ,11068
    1983    2801    3493    2150    4290    8559    6477
River Rch & RM=Kings Creek 32,Reach-1         ,10665
    1983    2799    3490    2147    4284    8548    6465
River Rch & RM=Kings Creek 32,Reach-1         ,9720
    2235    3171    3967    2449    4886    9749    7420
River Rch & RM=Kings Creek 32,Reach-1         ,7786
    2507    3576    4488    2779    5545   11064    8474
River Rch & RM=Kings Creek 32,Reach-1         ,6386
    2446    3477    4355    2690    5368   10710    8166
Boundary for River Rch & Prof#=Kings Creek 32,Reach-1         , 1
Up Type= 0
Dn Type= 3
Dn Slope=0.00047
Boundary for River Rch & Prof#=Kings Creek 32,Reach-1         , 2
Up Type= 0
Dn Type= 3
Dn Slope=0.00047
Boundary for River Rch & Prof#=Kings Creek 32,Reach-1         , 3
Up Type= 0
Dn Type= 3
Dn Slope=0.00047
Boundary for River Rch & Prof#=Kings Creek 32,Reach-1         , 4
Up Type= 0
Dn Type= 3
Dn Slope=0.00047
Boundary for River Rch & Prof#=Kings Creek 32,Reach-1         , 5
Up Type= 0
Dn Type= 3
Dn Slope=0.00047
Boundary for River Rch & Prof#=Kings Creek 32,Reach-1         , 6
Up Type= 0
Dn Type= 3
Dn Slope=0.00047
Boundary for River Rch & Prof#=Kings Creek 32,Reach-1         , 7
Up Type= 0
Dn Type= 3
Dn Slope=0.00047
DSS Import GetInterval= 0
DSS Import GetPeak= 0
DSS Import FillOption= 0

--- Kings Creek 32.g01 (geometry) ---

Geom Title=Existing Conditions

River Reach=Kings Creek 32,Reach-1
Reach XY= 30
      2673076.00      6873011.00      2673122.89      6872562.65
      2672577.57      6872004.96      2672722.54      6871712.50
      2672128.06      6871055.14      2672175.93      6869781.03
      2671920.48      6868808.57      2670786.65      6867721.00
      2670520.74      6867066.47      2670031.29      6866713.67
      2670106.79      6866440.42      2668978.89      6865753.08
      2669272.53      6865262.50      2669070.81      6864765.63
      2668381.73      6864213.55      2667678.26      6862405.06
      2667574.78      6860521.50      2667128.05      6859655.16
      2667218.67      6858911.10      2666983.19      6858611.33
      2667026.00      6857211.00      2666326.52      6855295.78
      2666624.96      6854121.43      2665526.52      6851995.78
      2666324.81      6848550.52      2666376.52      6847450.88
      2665977.04      6845900.56      2665972.47      6844712.45
      2665326.24      6844545.79      2665476.00      6839861.00

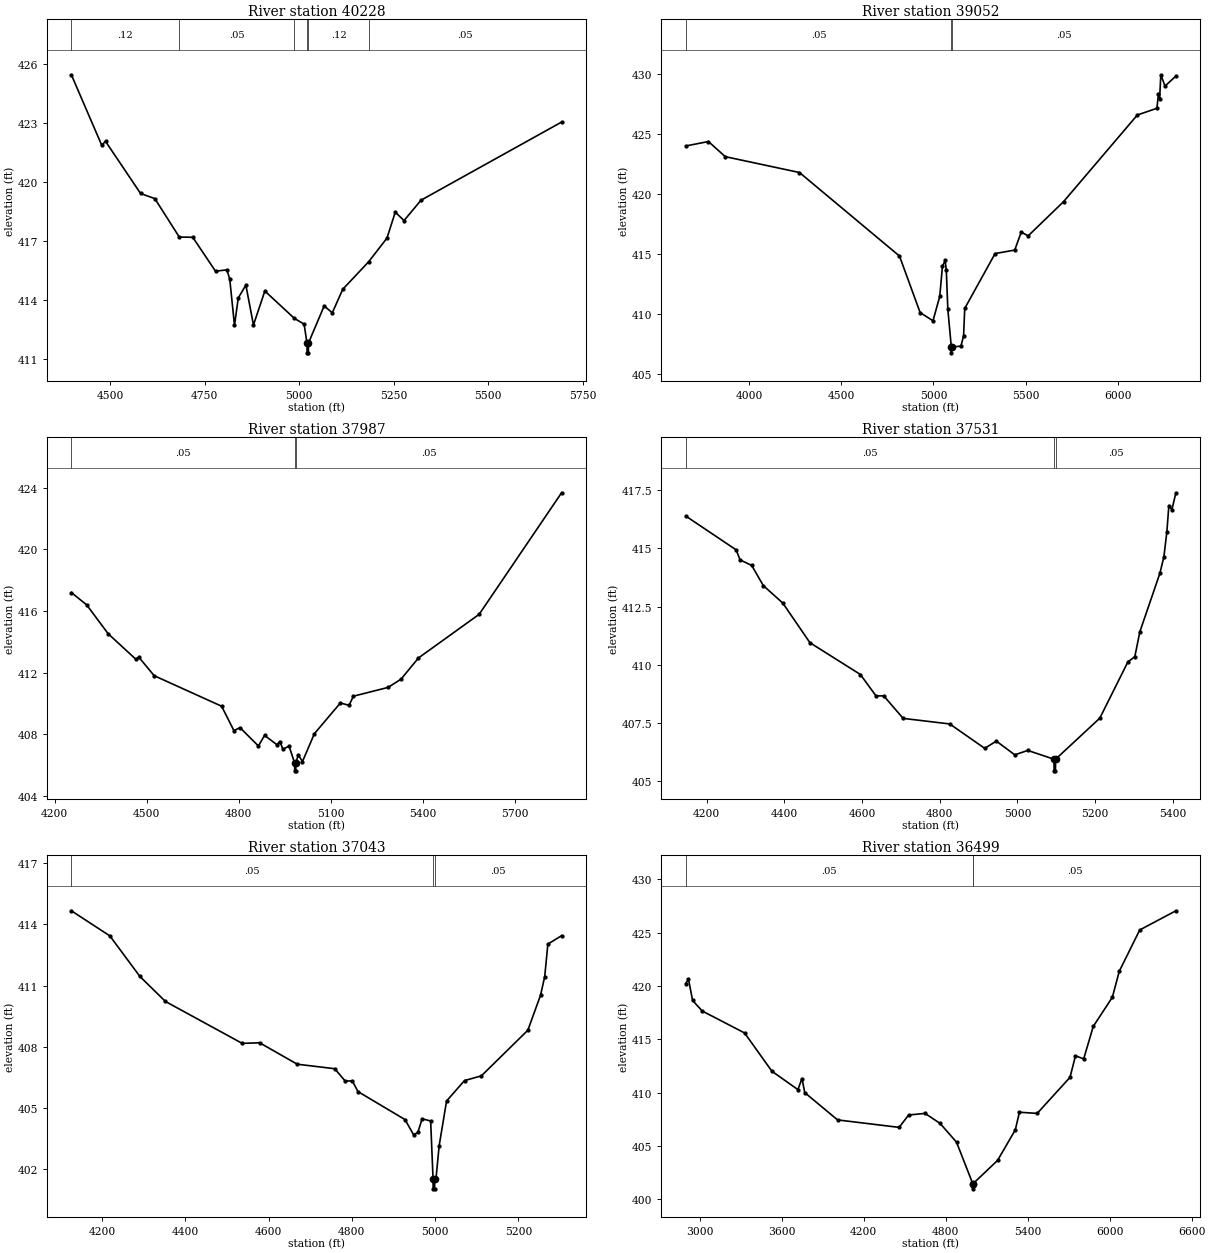
Type RM Length L Ch R = 1,40228,1176,1176,1176
BEGIN DESCRIPTION:
Kings Creek 32 82.0
END DESCRIPTION:
XS GIS Cut Line= 3
      2673676.01      6872911.00      2673076.00      6872961.00
      2672476.01      6873311.00
#Sta/Elev= 30
  4397.2  425.46  4477.5  421.87  4487.5  422.07  4580.3  419.41  4618.0  419.15
  4682.7  417.19  4718.3  417.18  4778.5  415.45  4808.6  415.52  4816.2  415.04
  4828.7  412.69  4838.7  414.09  4858.8  414.74  4878.9  412.71  4909.0  414.44
  4986.9  413.05  5012.9  412.75  5020.4  411.79  5020.7  411.29  5024.2  411.29
  5024.4  411.79  5065.9  413.68  5087.4  413.33  5115.1  414.53  5184.0  415.94
  5232.1  417.14  5254.0  418.46  5277.1  418.03  5322.2  419.07  5693.9  423.05
#Mann=6,-1,0
  4397.2    0.12       0  4682.7    0.05       0  4986.9    0.12       0
  5020.4    0.07       0  5024.4    0.12       0  5184.0    0.05       0
Bank Sta=5020.4,5024.4
Exp/Cntr=0.3,0.1

Type RM Length L Ch R = 1,39052,1065,1065,1065
BEGIN DESCRIPTION:
Mapping XS fe9c8175
END DESCRIPTION:
XS GIS Cut Line= 3
      2674103.01      6871699.87      2672818.26      6872107.86
      2671760.11      6872888.47
#Sta/Elev= 30
  3654.0  423.98  3777.7  424.35  3869.2  423.09  4272.1  421.77  4815.5  414.81
  4927.7  410.10  4997.5  409.42  5034.2  411.45  5048.8  413.96  5063.5  414.45
  5069.7  413.65  5078.1  410.37  5096.9  407.25  5097.2  406.75  5100.9  407.25
  5149.1  407.30  5163.7  408.17  5169.9  410.45  5334.9  415.02  5441.4  415.31
  5477.0  416.81  5514.3  416.49  5706.6  419.34  6107.6  426.56  6214.0  427.12
  6222.4  428.35  6228.7  427.93  6235.0  429.91  6257.9  428.97  6316.9  429.80
#Mann=3,-1,0
  3654.0    0.05       0  5096.9    0.03       0  5100.9    0.05       0
Bank Sta=5096.9,5100.9
Exp/Cntr=0.3,0.1

Type RM Length L Ch R = 1,37987,456,456,456
BEGIN DESCRIPTION:
Kings Creek 32 78.0
END DESCRIPTION:
XS GIS Cut Line= 3
      2673176.03      6871461.00      2672426.00      6871461.00
      2671825.97      6872061.03
#Sta/Elev= 30
  4254.3  417.19  4304.3  416.39  4374.3  414.52  4464.3  412.87  4474.3  413.00
  4524.3  411.80  4744.3  409.82  4784.3  408.24  4804.3  408.43  4864.3  407.24
  4884.3  407.93  4924.3  407.33  4934.3  407.53  4944.3  407.03  4964.3  407.24
  4982.3  406.13  4982.6  405.63  4986.1  405.63  4986.3  406.13  4994.3  406.67
  5007.9  406.23  5046.8  408.04  5131.6  410.03  5159.9  409.88  5174.0  410.47
  5287.2  411.04  5329.6  411.58  5386.2  412.95  5584.2  415.78  5852.9  423.66
#Mann=3,-1,0
  4254.3    0.05       0  4982.3    0.03       0  4986.3    0.05       0
Bank Sta=4982.3,4986.3
Exp/Cntr=0.3,0.1

Type RM Length L Ch R = 1,37531,488,488,488
BEGIN DESCRIPTION:
Kings Creek 32 77.0
END DESCRIPTION:
XS GIS Cut Line= 3
      2673075.97      6871161.00      2672226.00      6871161.00
      2671825.99      6871261.00
#Sta/Elev= 30
  4145.6  416.40  4275.6  414.94  4285.6  414.51  4315.6  414.27  4345.6  413.40
  4395.6  412.65  4465.6  410.94  4595.6  409.57  4635.6  408.65  4655.6  408.65
  4705.6  407.68  4825.6  407.44  4915.6  406.39  4945.6  406.70  4993.1  406.11
  5026.5  406.30  5094.1  405.92  5094.3  405.42  5097.8  405.42  5098.1  405.92
  5212.0  407.69  5284.2  410.11  5302.2  410.34  5315.1  411.41  5366.7  413.93
  5377.0  414.64  5384.7  415.72  5389.8  416.85  5397.6  416.67  5407.9  417.40
#Mann=3,-1,0
  4145.6    0.05       0  5094.1    0.04       0  5098.1    0.05       0
Bank Sta=5094.1,5098.1
Exp/Cntr=0.3,0.1

Type RM Length L Ch R = 1,37043,544,544,544
BEGIN DESCRIPTION:
Kings Creek 32 76.0
END DESCRIPTION:
XS GIS Cut Line= 3
      2672975.99      6870911.00      2672126.00      6870711.00
      2671826.04      6870760.99
#Sta/Elev= 30
  4126.4  414.66  4218.9  413.43  4290.8  411.45  4352.4  410.22  4536.7  408.17
  4578.4  408.20  4668.9  407.15  4758.8  406.93  4783.9  406.33  4801.2  406.33
  4814.7  405.81  4927.7  404.44  4948.2  403.70  4958.5  403.81  4968.8  404.48
  4989.3  404.37  4995.0  401.55  4995.3  401.05  4998.8  401.05  4999.0  401.55
  5002.1  401.55  5009.7  403.16  5027.5  405.35  5070.6  406.35  5111.1  406.58
  5222.6  408.81  5253.1  410.52  5263.2  411.44  5270.8  413.03  5303.7  413.44
#Mann=3,-1,0
  4126.4    0.05       0  4995.0    0.04       0  4999.0    0.05       0
Bank Sta=4995,4999
Exp/Cntr=0.3,0.1

Type RM Length L Ch R = 1,36499,677,677,677
BEGIN DESCRIPTION:
Mapping XS 14246204
END DESCRIPTION:
XS GIS Cut Line= 3
      2674276.62      6870276.27      2672193.26      6870215.50
      2670691.51      6870232.86
#Sta/Elev= 30
  2898.6  420.23  2919.2  420.63  2949.2  418.65  3019.3  417.66  3329.4  415.60
  3529.5  412.01  3719.6  410.29  3749.6  411.33  3769.6  410.01  4009.7  407.45
  4459.9  406.75  4529.9  407.91  4650.0  408.06  4760.0  407.12  4880.1  405.36
  4998.1  401.49  4998.4  400.99  5002.1  401.49  5180.1  403.65  5310.1  406.52
  5340.1  408.17  5470.1  408.06  5710.2  411.44  5750.2  413.46  5810.2  413.17
  5880.2  416.21  6020.2  418.95  6070.2  421.37  6220.2  425.25  6484.7  427.05
#Mann=3,-1,0
  2898.6    0.05       0  4998.1    0.04       0  5002.1    0.05       0
Bank Sta=4998.1,5002.1
Exp/Cntr=0.3,0.1

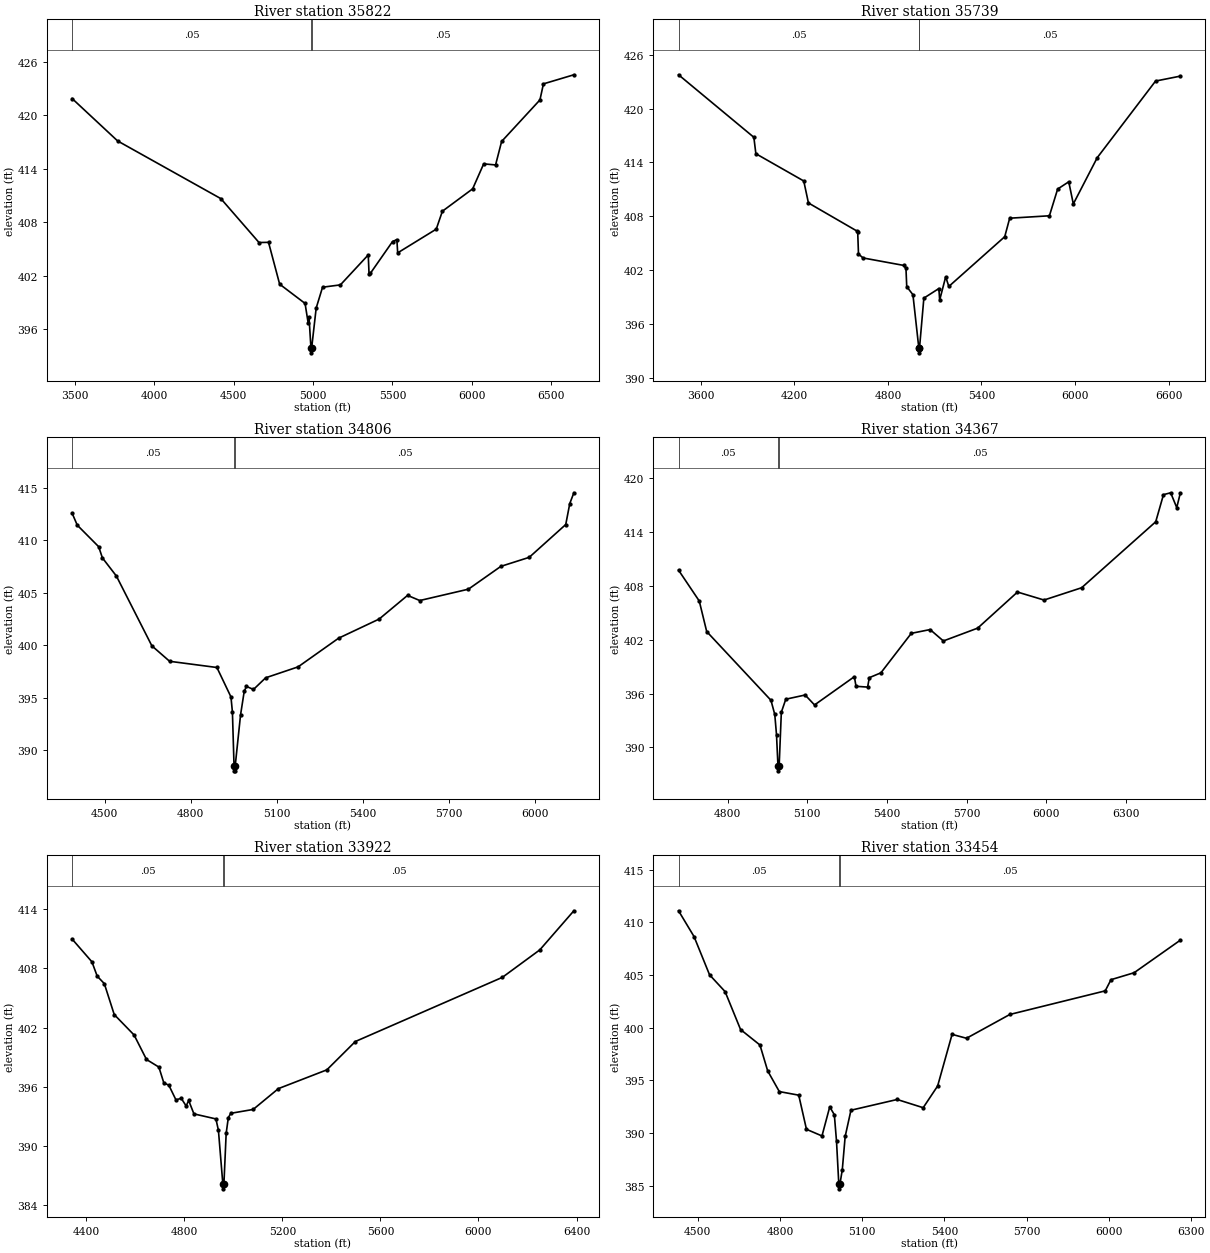
Type RM Length L Ch R = 1,35822,83,83,83
BEGIN DESCRIPTION:
Mapping XS 3e661520
END DESCRIPTION:
XS GIS Cut Line= 4
      2673642.89      6869573.14      2672132.50      6869555.78
      2671351.25      6869512.38      2670561.28      6869868.30
#Sta/Elev= 30
  3483.0  421.86  3769.9  417.10  4420.0  410.63  4660.0  405.71  4720.0  405.73
  4790.0  401.04  4950.0  398.88  4969.7  396.67  4974.7  397.39  4987.2  393.84
  4987.5  393.34  4991.2  393.84  5020.0  398.36  5060.1  400.70  5172.5  400.96
  5347.8  404.32  5352.8  402.21  5360.6  402.24  5500.8  405.82  5528.1  406.04
  5533.1  404.55  5776.0  407.21  5814.6  409.22  6005.2  411.73  6074.6  414.53
  6149.5  414.41  6187.5  417.04  6428.8  421.70  6450.8  423.50  6642.4  424.52
#Mann=3,-1,0
  3483.0    0.05       0  4987.2    0.04       0  4991.2    0.05       0
Bank Sta=4987.2,4991.2
Exp/Cntr=0.3,0.1

Type RM Length L Ch R = 1,35739,933,933,933
BEGIN DESCRIPTION:
Mapping XS 4ef3df3e
END DESCRIPTION:
XS GIS Cut Line= 4
      2673668.94      6869521.06      2672245.34      6869477.65
      2671325.21      6869434.25      2670519.50      6869772.13
#Sta/Elev= 30
  3456.6  423.76  3939.8  416.79  3952.7  414.96  4259.9  411.92  4289.9  409.47
  4600.1  406.35  4606.0  406.22  4611.0  403.78  4640.1  403.34  4900.2  402.51
  4915.6  402.17  4920.6  400.14  4960.3  399.24  4998.3  393.26  4998.6  392.76
  5002.3  393.26  5030.4  398.86  5126.8  399.93  5131.8  398.64  5170.5  401.24
  5190.5  400.16  5549.3  405.71  5581.0  407.77  5835.8  408.04  5888.7  411.02
  5960.0  411.83  5989.2  409.36  6142.7  414.52  6516.8  423.06  6675.7  423.61
#Mann=3,-1,0
  3456.6    0.05       0  4998.3    0.03       0  5002.3    0.05       0
Bank Sta=4998.3,5002.3
Exp/Cntr=0.3,0.1

Type RM Length L Ch R = 1,34806,439,439,439
BEGIN DESCRIPTION:
Kings Creek 32 71.0
END DESCRIPTION:
XS GIS Cut Line= 3
      2672376.02      6868511.00      2671776.00      6868661.00
      2670975.97      6869461.03
#Sta/Elev= 30
  4385.9  412.57  4404.0  411.42  4478.7  409.37  4491.6  408.31  4540.5  406.58
  4664.2  399.94  4726.1  398.47  4891.0  397.88  4940.0  395.08  4945.1  393.64
  4950.7  388.55  4951.0  388.05  4954.6  388.05  4954.9  388.55  4973.5  393.38
  4986.3  395.62  4994.1  396.08  5018.5  395.79  5061.0  396.90  5174.1  397.94
  5315.5  400.67  5456.9  402.49  5555.9  404.74  5598.4  404.25  5768.1  405.33
  5881.2  407.50  5980.2  408.36  6107.5  411.48  6121.6  413.48  6135.8  414.50
#Mann=3,-1,0
  4385.9    0.05       0  4950.7    0.03       0  4954.9    0.05       0
Bank Sta=4950.7,4954.9
Exp/Cntr=0.3,0.1

Type RM Length L Ch R = 1,34367,445,445,445
BEGIN DESCRIPTION:
Kings Creek 32 70.0
END DESCRIPTION:
XS GIS Cut Line= 3
      2671876.02      6868060.98      2671576.00      6868311.00
      2670676.02      6869510.97
#Sta/Elev= 30
  4614.9  409.75  4693.0  406.31  4721.0  402.91  4963.1  395.25  4977.5  393.67
  4984.0  391.41  4989.6  387.89  4990.0  387.39  4993.9  387.89  5002.2  393.92
  5019.0  395.37  5091.9  395.84  5127.3  394.73  5277.3  397.88  5283.6  396.81
  5327.3  396.72  5333.6  397.77  5377.3  398.31  5491.9  402.71  5562.7  403.13
  5612.7  401.86  5741.9  403.29  5891.9  407.31  5991.9  406.42  6133.6  407.79
  6412.7  415.14  6441.9  418.16  6469.0  418.37  6491.9  416.72  6505.4  418.34
#Mann=3,-1,0
  4614.9    0.05       0  4989.6    0.03       0  4993.9    0.05       0
Bank Sta=4989.6,4993.9
Exp/Cntr=0.3,0.1

Type RM Length L Ch R = 1,33922,468,468,468
BEGIN DESCRIPTION:
Kings Creek 32 69.0
END DESCRIPTION:
XS GIS Cut Line= 3
      2671876.02      6867961.00      2671226.00      6868061.00
      2670526.01      6869260.99
#Sta/Elev= 30
  4342.1  410.98  4423.1  408.67  4444.6  407.22  4473.7  406.46  4514.1  403.33
  4595.1  401.26  4645.7  398.78  4696.2  398.01  4716.5  396.40  4736.7  396.18
  4765.8  394.69  4787.3  394.85  4807.5  394.07  4817.7  394.63  4839.2  393.27
  4928.9  392.76  4939.1  391.61  4957.1  386.18  4957.5  385.68  4961.5  386.18
  4970.7  391.30  4979.5  392.89  4989.7  393.33  5080.8  393.72  5183.8  395.83
  5381.4  397.73  5497.6  400.60  6097.5  407.10  6250.1  409.88  6389.0  413.84
#Mann=3,-1,0
  4342.1    0.05       0  4957.1    0.04       0  4961.5    0.05       0
Bank Sta=4957.1,4961.5
Exp/Cntr=0.3,0.1

Type RM Length L Ch R = 1,33454,464,464,464
BEGIN DESCRIPTION:
Kings Creek 32 68.0
END DESCRIPTION:
XS GIS Cut Line= 3
      2671276.03      6867360.97      2670876.00      6867761.00
      2670476.01      6868960.96
#Sta/Elev= 30
  4429.9  411.10  4486.5  408.65  4543.1  405.02  4599.7  403.43  4656.2  399.83
  4726.9  398.36  4755.2  395.90  4797.6  393.94  4868.4  393.60  4896.6  390.36
  4953.2  389.73  4981.5  392.49  4998.3  391.74  5006.2  389.24  5014.5  385.21
  5014.9  384.71  5019.0  385.21  5027.3  386.52  5037.8  389.68  5058.9  392.17
  5227.5  393.19  5322.4  392.41  5375.1  394.47  5427.8  399.37  5480.5  399.00
  5638.6  401.26  5986.5  403.50  6007.6  404.56  6091.9  405.22  6260.5  408.31
#Mann=3,-1,0
  4429.9    0.05       0  5014.5    0.03       0  5019.0    0.05       0
Bank Sta=5014.5,5019
Exp/Cntr=0.3,0.1

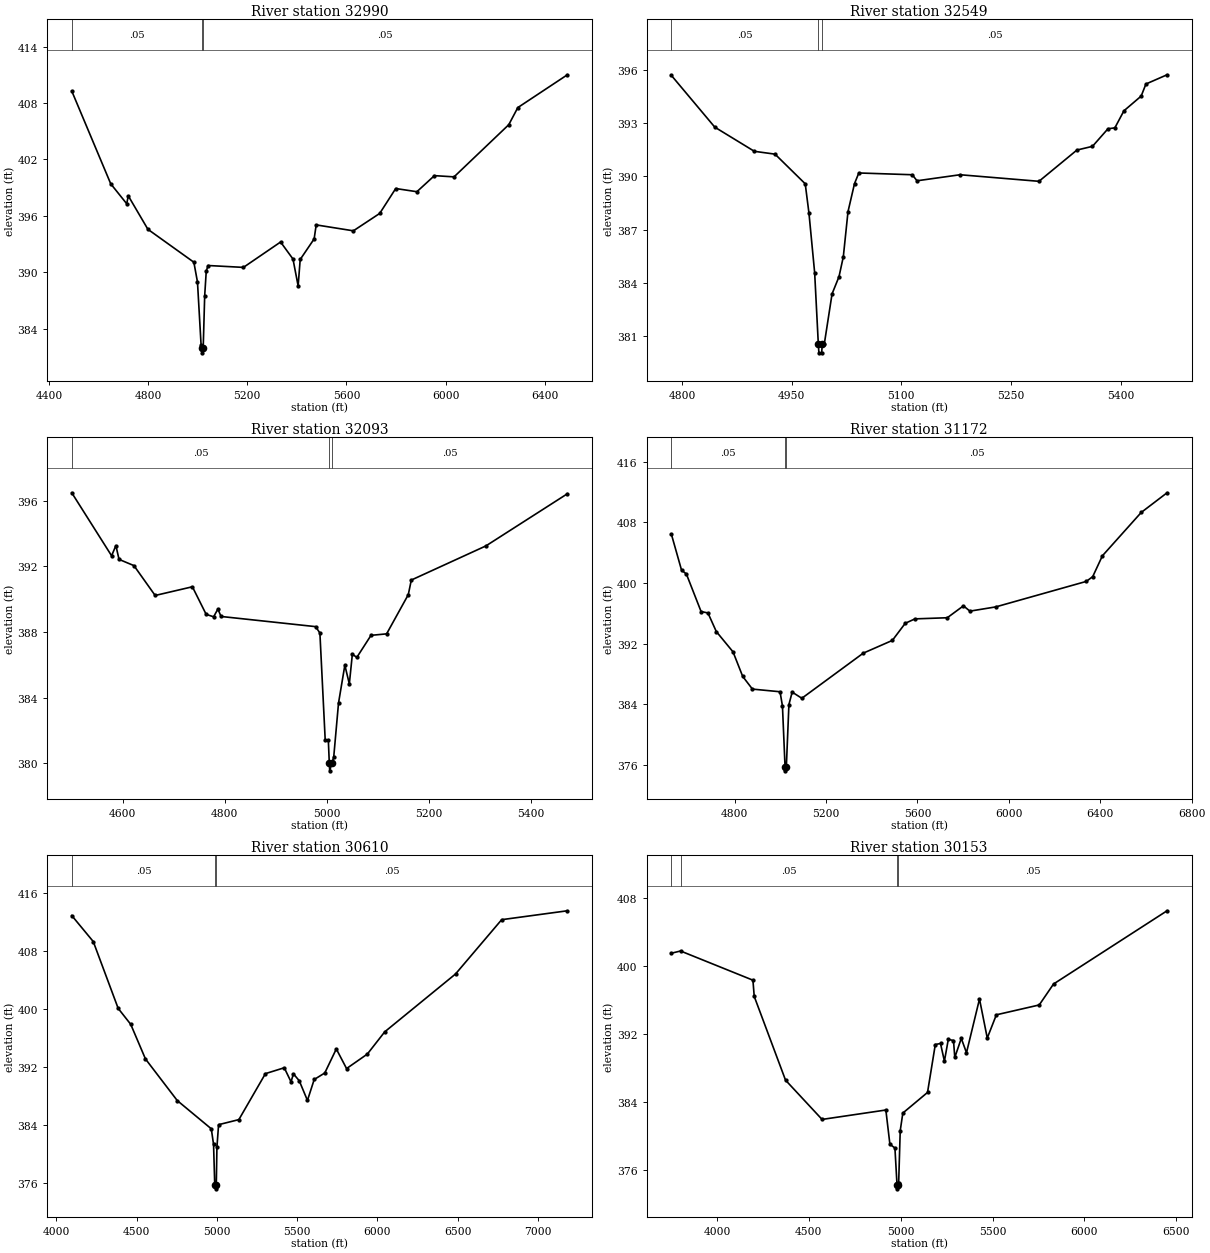
Type RM Length L Ch R = 1,32990,441,441,441
BEGIN DESCRIPTION:
Kings Creek 32 67.0
END DESCRIPTION:
XS GIS Cut Line= 3
      2671025.98      6867111.02      2670626.00      6867411.00
      2669425.98      6868311.02
#Sta/Elev= 30
  4491.8  409.27  4649.1  399.40  4713.6  397.28  4719.9  398.12  4799.1  394.56
  4984.5  391.06  4999.1  388.96  5013.6  382.29  5017.6  381.92  5018.1  381.42
  5022.2  381.92  5028.2  387.49  5034.5  390.10  5041.8  390.71  5184.5  390.51
  5334.5  393.21  5384.5  391.40  5405.3  388.54  5413.6  391.35  5469.9  393.54
  5478.2  395.03  5628.2  394.40  5734.5  396.25  5799.1  398.90  5884.5  398.56
  5955.3  400.27  6034.5  400.14  6255.3  405.69  6291.8  407.51  6491.8  411.00
#Mann=3,-1,0
  4491.8    0.05       0  5017.6    0.03       0  5022.2    0.05       0
Bank Sta=5017.6,5022.2
Exp/Cntr=0.3,0.1

Type RM Length L Ch R = 1,32549,456,456,456
BEGIN DESCRIPTION:
Kings Creek 32 66.0
END DESCRIPTION:
XS GIS Cut Line= 3
      2670726.01      6867011.00      2670526.00      6867061.00
      2670125.97      6867311.02
#Sta/Elev= 30
  4785.7  395.68  4845.0  392.77  4899.1  391.41  4927.4  391.25  4968.7  389.58
  4973.8  387.93  4981.6  384.57  4986.6  380.56  4987.4  380.06  4991.2  380.06
  4992.0  380.56  4994.8  380.56  5005.4  383.38  5014.9  384.35  5020.8  385.47
  5027.2  388.01  5036.1  389.59  5042.0  390.19  5115.1  390.09  5121.6  389.75
  5180.5  390.09  5288.4  389.72  5340.3  391.48  5361.6  391.69  5382.8  392.68
  5392.2  392.73  5404.6  393.69  5428.2  394.52  5434.7  395.20  5463.6  395.72
#Mann=3,-1,0
  4785.7    0.05       0  4986.6    0.03       0  4992.0    0.05       0
Bank Sta=4986.6,4992
Exp/Cntr=0.3,0.1

Type RM Length L Ch R = 1,32093,921,921,921
BEGIN DESCRIPTION:
Kings Creek 32 65.0
END DESCRIPTION:
XS GIS Cut Line= 3
      2670476.00      6866410.99      2670176.00      6866811.00
      2669776.01      6867061.00
#Sta/Elev= 30
  4500.0  396.49  4578.1  392.65  4586.5  393.27  4592.7  392.43  4621.9  392.05
  4663.5  390.23  4736.5  390.76  4763.5  389.08  4778.1  388.93  4786.5  389.40
  4792.7  388.95  4978.1  388.33  4986.5  387.94  4996.9  381.42  5003.0  381.42
  5004.9  380.04  5005.7  379.54  5010.4  380.04  5013.6  380.38  5023.0  383.67
  5035.4  385.98  5044.2  384.84  5050.1  386.64  5059.0  386.46  5086.7  387.80
  5117.3  387.89  5159.8  390.28  5165.7  391.17  5311.9  393.25  5471.7  396.43
#Mann=3,-1,0
  4500.0    0.05       0  5004.9    0.03       0  5010.4    0.05       0
Bank Sta=5004.9,5010.4
Exp/Cntr=0.3,0.1

Type RM Length L Ch R = 1,31172,562,562,562
BEGIN DESCRIPTION:
Kings Creek 32 63.0
END DESCRIPTION:
XS GIS Cut Line= 3
      2670226.00      6865961.00      2669826.00      6866211.00
      2668625.97      6867411.03
#Sta/Elev= 30
  4523.5  406.42  4567.7  401.71  4588.9  401.20  4653.2  396.25  4683.3  396.06
  4719.8  393.61  4793.0  390.93  4835.4  387.69  4877.9  386.02  4998.7  385.67
  5009.3  383.80  5020.7  375.74  5021.5  375.24  5026.3  375.74  5037.6  383.98
  5051.8  385.62  5094.2  384.81  5362.9  390.76  5490.2  392.44  5546.7  394.70
  5589.2  395.28  5730.6  395.43  5801.3  397.00  5829.6  396.30  5942.7  396.86
  6338.7  400.22  6367.0  400.85  6409.4  403.60  6579.1  409.31  6692.3  411.91
#Mann=3,-1,0
  4523.5    0.05       0  5020.7    0.03       0  5026.3    0.05       0
Bank Sta=5020.7,5026.3
Exp/Cntr=0.3,0.1

Type RM Length L Ch R = 1,30610,457,457,457
BEGIN DESCRIPTION:
Mapping XS 3333fe25
END DESCRIPTION:
XS GIS Cut Line= 3
      2670014.44      6865250.22      2669389.44      6865918.63
      2668191.54      6867732.83
#Sta/Elev= 30
  4095.5  412.91  4229.5  409.32  4384.8  400.09  4463.0  397.89  4554.8  393.11
  4753.1  387.36  4965.2  383.46  4979.3  381.30  4986.5  375.88  4990.6  375.67
  4991.5  375.17  4996.3  375.67  5000.3  380.92  5010.6  384.03  5137.0  384.73
  5302.6  391.08  5420.0  391.89  5462.1  389.95  5477.2  391.05  5513.3  390.10
  5564.5  387.38  5606.6  390.27  5672.5  391.17  5744.4  394.49  5808.3  391.78
  5937.7  393.78  6046.1  396.85  6487.4  404.84  6775.0  412.34  7184.6  413.57
#Mann=3,-1,0
  4095.5    0.05       0  4990.6    0.05       0  4996.3    0.05       0
Bank Sta=4990.6,4996.3
Exp/Cntr=0.3,0.1

Type RM Length L Ch R = 1,30153,1157,1157,1157
BEGIN DESCRIPTION:
Mapping XS 5b5839c8
END DESCRIPTION:
XS GIS Cut Line= 3
      2669945.02      6864955.06      2668998.82      6865753.70
      2667958.15      6866777.02
#Sta/Elev= 30
  3752.1  401.51  3801.7  401.77  4195.7  398.33  4202.7  396.42  4373.1  386.55
  4572.0  381.92  4919.2  383.03  4941.2  379.00  4968.6  378.55  4979.9  374.24
  4980.9  373.74  4985.9  374.24  4988.9  374.44  4997.4  380.59  5011.6  382.67
  5146.0  385.10  5188.4  390.75  5216.7  390.87  5237.9  388.79  5259.1  391.35
  5287.4  391.22  5294.4  389.22  5329.8  391.47  5358.1  389.78  5428.9  396.11
  5471.2  391.51  5520.7  394.25  5754.0  395.41  5831.9  397.88  6449.8  406.51
#Mann=4,-1,0
  3752.1    0.12       0  3801.7    0.05       0  4979.9    0.05       0
  4985.9    0.05       0
Bank Sta=4979.9,4985.9
Exp/Cntr=0.3,0.1

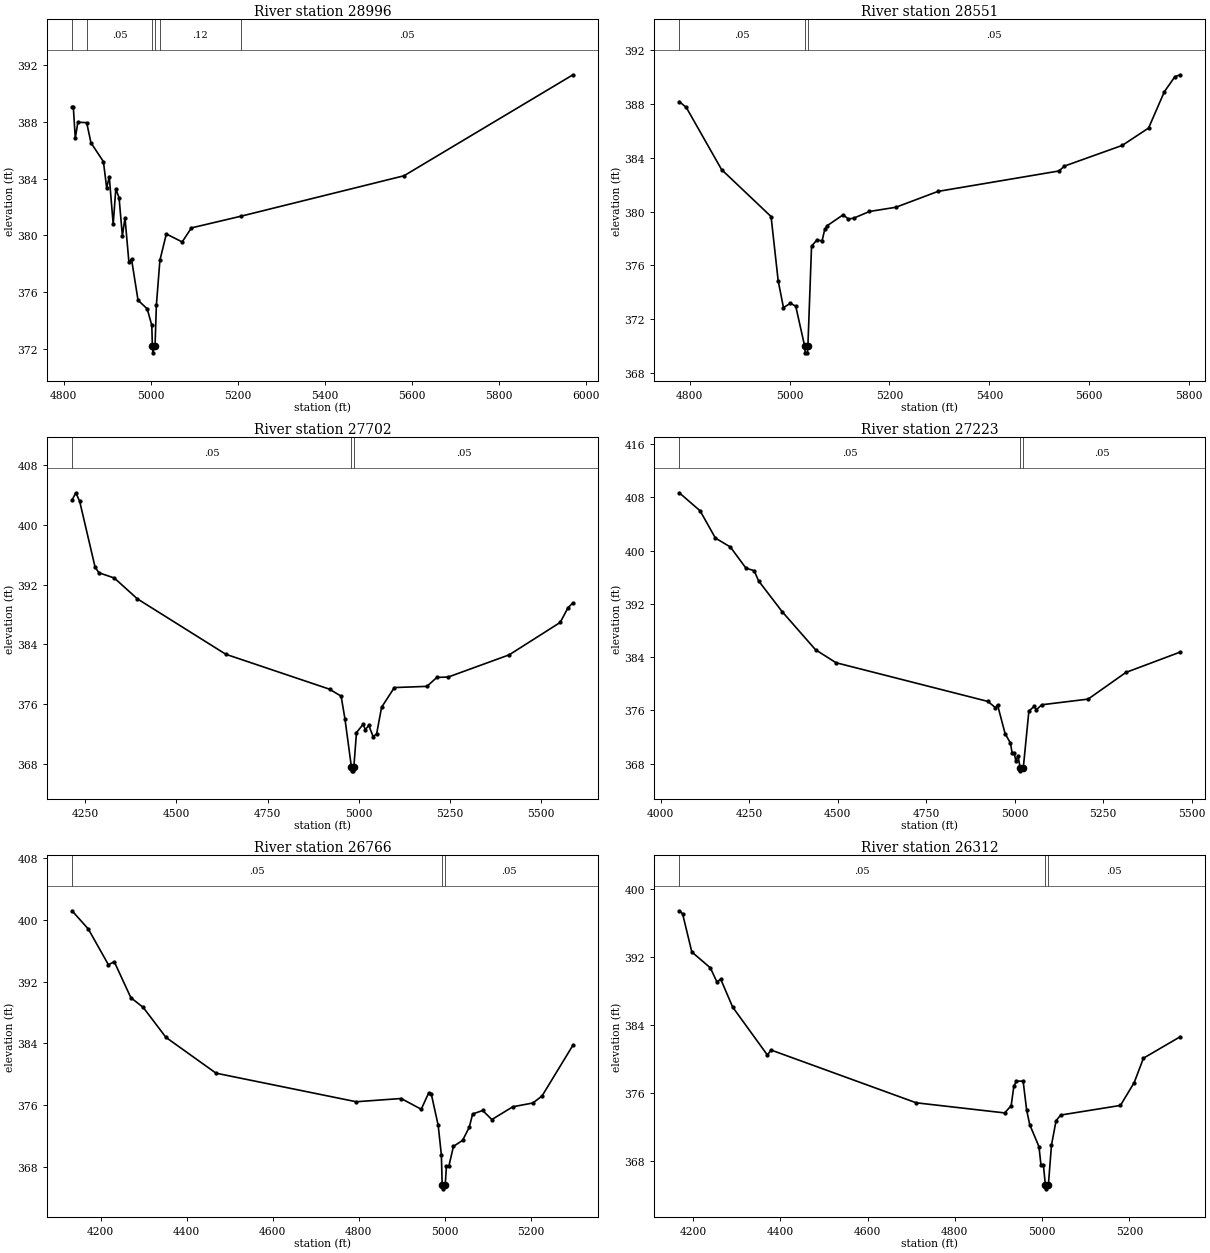
Type RM Length L Ch R = 1,28996,445,445,445
BEGIN DESCRIPTION:
Kings Creek 32 59.0
END DESCRIPTION:
XS GIS Cut Line= 3
      2669225.99      6864761.01      2669076.00      6864861.00
      2668525.99      6865661.01
#Sta/Elev= 30
  4819.2  389.04  4822.2  389.04  4826.7  386.86  4832.7  387.98  4852.9  387.95
  4862.7  386.53  4891.3  385.20  4898.8  383.35  4904.8  384.12  4913.8  380.78
  4919.8  383.27  4927.3  382.65  4934.9  379.95  4940.9  381.24  4949.9  378.10
  4955.9  378.32  4970.9  375.41  4991.9  374.81  5002.5  373.64  5003.8  372.20
  5004.9  371.70  5010.0  372.20  5013.0  375.05  5021.1  378.23  5035.9  380.09
  5072.3  379.53  5093.5  380.52  5206.6  381.34  5582.0  384.20  5970.3  391.33
#Mann=6,-1,0
  4819.2    0.12       0  4852.9    0.05       0  5003.8    0.03       0
  5010.0    0.05       0  5021.1    0.12       0  5206.6    0.05       0
Bank Sta=5003.8,5010
Exp/Cntr=0.3,0.1

Type RM Length L Ch R = 1,28551,849,849,849
BEGIN DESCRIPTION:
Kings Creek 32 58.0
END DESCRIPTION:
XS GIS Cut Line= 3
      2669025.98      6864511.02      2668876.00      6864661.00
      2668125.97      6864911.01
#Sta/Elev= 30
  4779.2  388.18  4793.3  387.74  4864.0  383.12  4963.0  379.63  4977.2  374.86
  4987.8  372.86  5001.8  373.19  5012.4  372.96  5030.2  370.00  5031.3  369.50
  5035.7  369.50  5036.7  370.00  5044.0  377.43  5054.5  377.88  5065.1  377.83
  5070.4  378.67  5075.6  378.96  5107.2  379.76  5117.8  379.45  5128.3  379.51
  5160.0  380.01  5212.7  380.32  5297.0  381.50  5539.4  383.02  5550.0  383.38
  5665.9  384.92  5718.6  386.21  5750.2  388.91  5771.3  390.03  5781.9  390.17
#Mann=3,-1,0
  4779.2    0.05       0  5030.2    0.03       0  5036.7    0.05       0
Bank Sta=5030.2,5036.7
Exp/Cntr=0.3,0.1

Type RM Length L Ch R = 1,27702,479,479,479
BEGIN DESCRIPTION:
Kings Creek 32 56.0
END DESCRIPTION:
XS GIS Cut Line= 3
      2669125.96      6863961.01      2668376.00      6864211.00
      2668076.01      6864710.98
#Sta/Elev= 30
  4213.6  403.33  4224.1  404.30  4234.6  403.15  4276.8  394.35  4287.3  393.59
  4329.5  392.89  4392.7  390.10  4635.2  382.68  4919.8  378.00  4951.4  377.07
  4962.0  374.02  4979.7  367.57  4980.8  367.07  4985.2  367.07  4986.3  367.57
  4993.6  372.20  5011.9  373.30  5017.7  372.58  5027.4  373.16  5039.1  371.66
  5048.8  372.02  5062.4  375.58  5097.4  378.22  5186.8  378.38  5214.0  379.58
  5245.1  379.63  5412.3  382.60  5552.2  386.94  5573.6  388.91  5587.2  389.56
#Mann=3,-1,0
  4213.6    0.05       0  4979.7    0.03       0  4986.3    0.05       0
Bank Sta=4979.7,4986.3
Exp/Cntr=0.3,0.1

Type RM Length L Ch R = 1,27223,457,457,457
BEGIN DESCRIPTION:
Kings Creek 32 55.0
END DESCRIPTION:
XS GIS Cut Line= 3
      2669075.96      6863261.02      2668276.00      6863761.00
      2667875.96      6864011.03
#Sta/Elev= 30
  4052.7  408.70  4111.6  405.99  4154.7  401.90  4197.1  400.55  4241.3  397.36
  4264.3  397.00  4276.7  395.47  4343.3  390.84  4437.7  385.11  4495.5  383.16
  4924.7  377.34  4945.9  376.40  4951.8  376.82  4973.1  372.52  4988.4  371.06
  4993.1  369.55  4999.0  369.55  5003.7  368.38  5009.6  369.20  5015.5  367.41
  5016.6  366.91  5022.5  367.41  5024.9  367.54  5040.3  375.88  5055.0  376.59
  5061.5  376.09  5076.8  376.84  5207.7  377.69  5314.5  381.70  5467.8  384.76
#Mann=3,-1,0
  4052.7    0.05       0  5015.5    0.04       0  5022.5    0.05       0
Bank Sta=5015.5,5022.5
Exp/Cntr=0.3,0.1

Type RM Length L Ch R = 1,26766,454,454,454
BEGIN DESCRIPTION:
Kings Creek 32 54.0
END DESCRIPTION:
XS GIS Cut Line= 3
      2668875.99      6863061.00      2668076.00      6863411.00
      2667825.96      6863561.02
#Sta/Elev= 30
  4133.5  401.14  4171.3  398.79  4218.1  394.17  4231.7  394.56  4270.3  389.91
  4299.2  388.65  4351.8  384.79  4468.4  380.16  4794.3  376.47  4898.7  376.89
  4945.5  375.50  4963.0  377.64  4968.9  377.46  4984.9  373.42  4992.3  369.60
  4994.2  365.72  4995.3  365.22  5001.3  365.72  5004.0  368.12  5009.6  368.12
  5020.3  370.70  5041.7  371.49  5057.2  373.18  5065.0  374.89  5088.3  375.34
  5109.7  374.17  5158.3  375.82  5205.0  376.31  5226.3  377.21  5298.3  383.78
#Mann=3,-1,0
  4133.5    0.05       0  4994.2    0.04       0  5001.3    0.05       0
Bank Sta=4994.2,5001.3
Exp/Cntr=0.3,0.1

Type RM Length L Ch R = 1,26312,623,623,623
BEGIN DESCRIPTION:
Kings Creek 32 53.0
END DESCRIPTION:
XS GIS Cut Line= 3
      2668626.02      6862560.98      2667926.00      6863011.00
      2667626.02      6863110.99
#Sta/Elev= 30
  4168.2  397.43  4175.8  397.09  4197.0  392.59  4239.6  390.72  4254.4  389.08
  4263.3  389.39  4290.7  386.11  4370.3  380.48  4378.6  381.07  4711.4  374.87
  4914.2  373.68  4929.1  374.53  4935.3  376.84  4941.3  377.41  4956.5  377.42
  4964.7  373.98  4971.7  372.30  4992.8  369.72  4997.4  367.58  5003.0  367.58
  5007.4  365.26  5008.5  364.76  5014.5  365.26  5021.5  369.89  5032.0  372.76
  5042.6  373.43  5179.6  374.56  5211.2  377.25  5232.3  380.11  5316.6  382.63
#Mann=3,-1,0
  4168.2    0.05       0  5007.4    0.04       0  5014.5    0.05       0
Bank Sta=5007.4,5014.5
Exp/Cntr=0.3,0.1

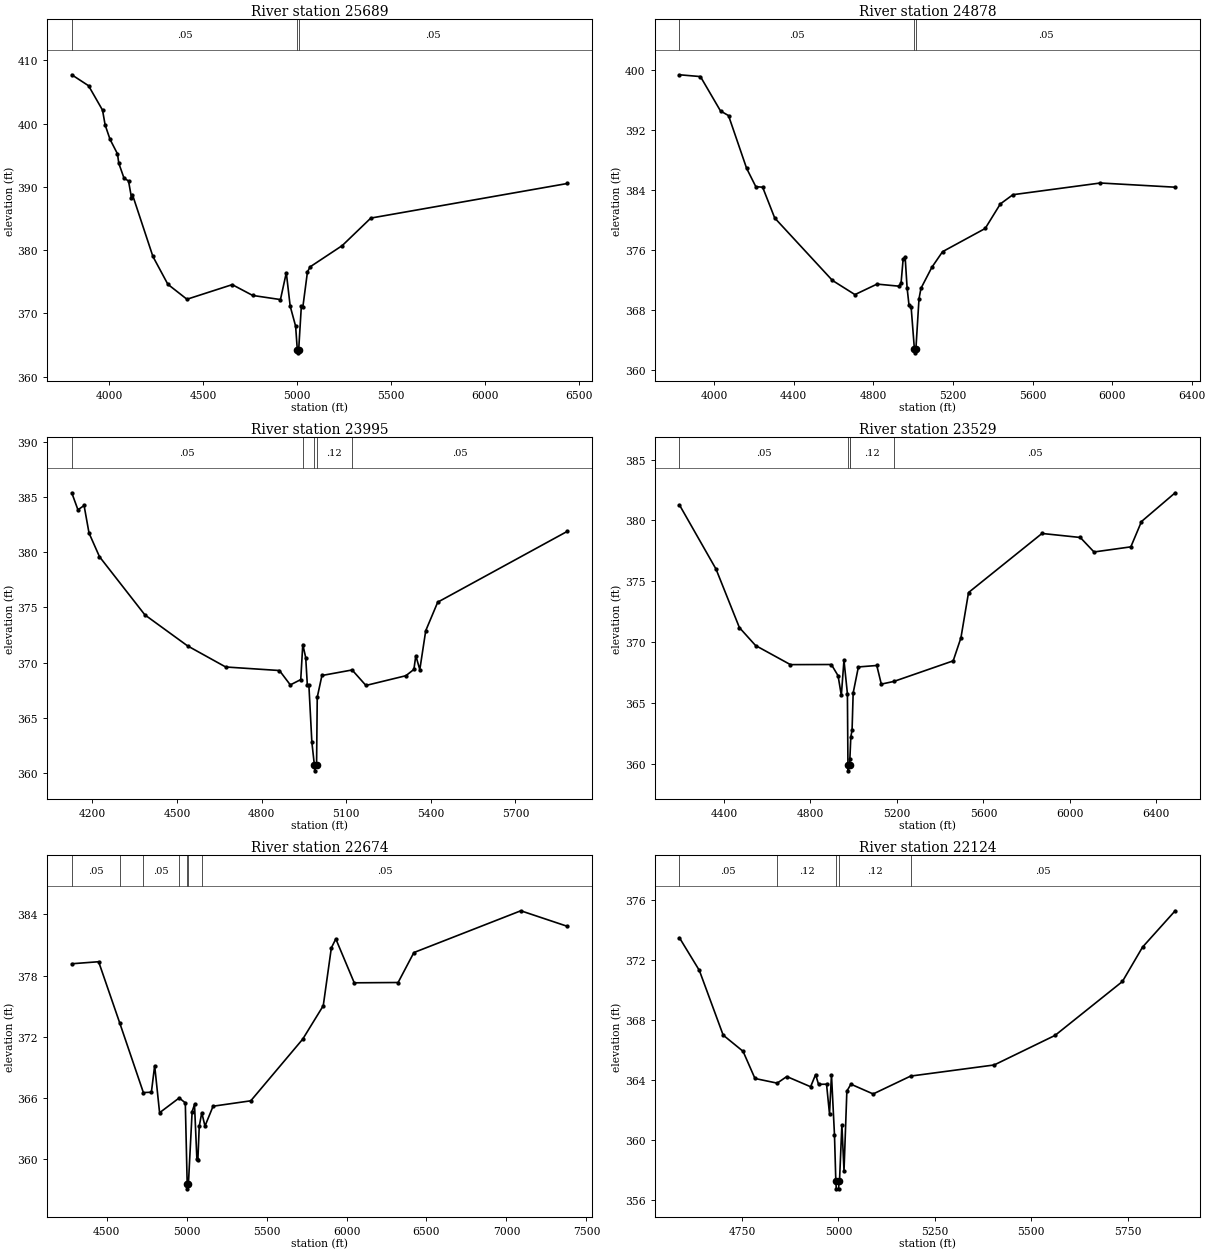
Type RM Length L Ch R = 1,25689,811,811,811
BEGIN DESCRIPTION:
Mapping XS b6904f4c
END DESCRIPTION:
XS GIS Cut Line= 3
      2668877.29      6862142.58      2667696.73      6862463.77
      2666386.01      6862993.26
#Sta/Elev= 30
  3800.1  407.73  3889.4  406.00  3963.8  402.14  3977.6  399.80  4003.6  397.53
  4043.3  395.23  4050.2  393.75  4077.9  391.40  4102.0  390.95  4117.7  388.33
  4122.9  388.79  4231.8  379.01  4311.4  374.61  4412.9  372.25  4653.8  374.56
  4762.7  372.85  4910.3  372.20  4941.4  376.44  4962.1  371.16  4991.0  367.99
  4999.9  364.28  5001.1  363.78  5007.3  364.28  5021.4  371.13  5029.6  371.05
  5053.8  376.54  5067.5  377.36  5238.9  380.73  5391.1  385.08  6437.2  390.55
#Mann=3,-1,0
  3800.1    0.05       0  4999.9    0.04       0  5007.3    0.05       0
Bank Sta=4999.9,5007.3
Exp/Cntr=0.3,0.1

Type RM Length L Ch R = 1,24878,883,883,883
BEGIN DESCRIPTION:
Mapping XS dc499241
END DESCRIPTION:
XS GIS Cut Line= 3
      2668790.53      6861526.26      2667592.57      6861682.52
      2666394.69      6862142.57
#Sta/Elev= 30
  3825.6  399.36  3931.0  399.12  4031.9  394.54  4072.2  393.92  4163.0  386.90
  4209.3  384.45  4243.6  384.38  4304.2  380.28  4594.2  371.96  4707.5  370.07
  4818.5  371.47  4929.4  371.19  4939.5  371.67  4949.6  374.75  4959.7  375.12
  4969.7  370.95  4979.1  368.69  4989.9  368.41  5006.3  362.81  5007.5  362.31
  5013.8  362.81  5029.5  369.52  5039.4  370.91  5094.1  373.71  5147.9  375.79
  5362.1  378.88  5438.2  382.15  5501.4  383.38  5940.9  384.94  6316.9  384.38
#Mann=3,-1,0
  3825.6    0.05       0  5006.3    0.04       0  5013.8    0.05       0
Bank Sta=5006.3,5013.8
Exp/Cntr=0.3,0.1

Type RM Length L Ch R = 1,23995,466,466,466
BEGIN DESCRIPTION:
Kings Creek 32 48.0
END DESCRIPTION:
XS GIS Cut Line= 3
      2668376.03      6861161.01      2667576.00      6860811.00
      2666976.03      6861460.97
#Sta/Elev= 30
  4126.7  385.37  4148.6  383.83  4170.4  384.22  4187.9  381.73  4225.0  379.59
  4386.0  374.33  4537.2  371.53  4672.5  369.62  4863.1  369.30  4901.7  368.00
  4938.7  368.48  4945.9  371.65  4956.3  370.47  4962.1  367.97  4967.6  367.95
  4978.1  362.83  4987.1  360.73  4988.3  360.23  4994.8  360.73  4997.2  366.88
  5013.8  368.85  5120.9  369.35  5169.8  367.95  5311.5  368.83  5339.9  369.40
  5346.7  370.64  5360.9  369.38  5381.9  372.90  5424.4  375.48  5884.5  381.89
#Mann=5,-1,0
  4126.7    0.05       0  4945.9    0.12       0  4987.1    0.07       0
  4994.8    0.12       0  5120.9    0.05       0
Bank Sta=4987.1,4994.8
Exp/Cntr=0.3,0.1

Type RM Length L Ch R = 1,23529,855,855,855
BEGIN DESCRIPTION:
Kings Creek 32 47.0
END DESCRIPTION:
XS GIS Cut Line= 3
      2668226.04      6859960.98      2667526.00      6860361.00
      2666525.98      6861461.02
#Sta/Elev= 30
  4194.1  381.27  4363.3  376.00  4471.3  371.20  4546.1  369.73  4707.4  368.16
  4896.7  368.17  4927.7  367.25  4942.8  365.64  4955.0  368.52  4970.9  365.78
  4973.4  359.94  4974.6  359.44  4981.2  359.94  4982.4  360.44  4986.7  362.23
  4992.5  362.78  4997.5  365.83  5021.7  367.97  5106.8  368.09  5127.7  366.56
  5185.7  366.78  5460.2  368.47  5496.0  370.36  5531.2  374.08  5871.0  378.93
  6048.1  378.60  6111.6  377.41  6281.9  377.83  6331.2  379.91  6487.0  382.27
#Mann=5,-1,0
  4194.1    0.05       0  4973.4    0.07       0  4981.2    0.05       0
  4982.4    0.12       0  5185.7    0.05       0
Bank Sta=4973.4,4981.2
Exp/Cntr=0.3,0.1

Type RM Length L Ch R = 1,22674,550,550,550
BEGIN DESCRIPTION:
Mapping XS 3064be09
END DESCRIPTION:
XS GIS Cut Line= 3
      2667861.71      6859538.41      2667167.22      6859694.67
      2665206.46      6861056.79
#Sta/Elev= 30
  4282.2  379.16  4450.2  379.36  4581.9  373.36  4729.9  366.52  4780.0  366.55
  4800.5  369.16  4831.3  364.54  4953.9  365.99  4992.1  365.51  5003.8  357.57
  5005.0  357.07  5011.6  357.57  5034.8  364.66  5049.6  365.35  5064.5  359.99
  5070.6  359.90  5079.3  363.22  5095.1  364.54  5115.1  363.23  5165.8  365.18
  5401.5  365.71  5726.1  371.76  5854.6  375.04  5905.2  380.72  5933.1  381.60
  6048.4  377.29  6322.6  377.32  6421.2  380.26  7089.8  384.36  7381.5  382.83
#Mann=7,-1,0
  4282.2    0.05       0  4581.9    0.12       0  4729.9    0.05       0
  4953.9    0.12       0  5003.8    0.07       0  5011.6    0.12       0
  5095.1    0.05       0
Bank Sta=5003.8,5011.6
Exp/Cntr=0.3,0.1

Type RM Length L Ch R = 1,22124,449,449,449
BEGIN DESCRIPTION:
Kings Creek 32 44.0
END DESCRIPTION:
XS GIS Cut Line= 3
      2667525.96      6859260.99      2667126.00      6859161.00
      2666325.99      6859511.01
#Sta/Elev= 30
  4587.7  373.45  4639.2  371.28  4701.0  366.97  4752.6  365.89  4783.5  364.08
  4841.1  363.77  4866.0  364.21  4927.8  363.53  4940.7  364.34  4948.4  363.69
  4969.1  363.70  4976.8  361.72  4981.9  364.33  4989.7  360.32  4993.2  357.23
  4994.4  356.73  5000.3  356.73  5001.6  357.23  5002.7  357.23  5008.9  360.99
  5014.4  357.93  5021.8  363.24  5032.3  363.70  5090.0  363.05  5187.2  364.24
  5403.8  364.98  5561.7  366.95  5736.4  370.54  5788.6  372.83  5873.2  375.25
#Mann=5,-1,0
  4587.7    0.05       0  4841.1    0.12       0  4993.2    0.07       0
  5001.6    0.12       0  5187.2    0.05       0
Bank Sta=4993.2,5001.6
Exp/Cntr=0.3,0.1