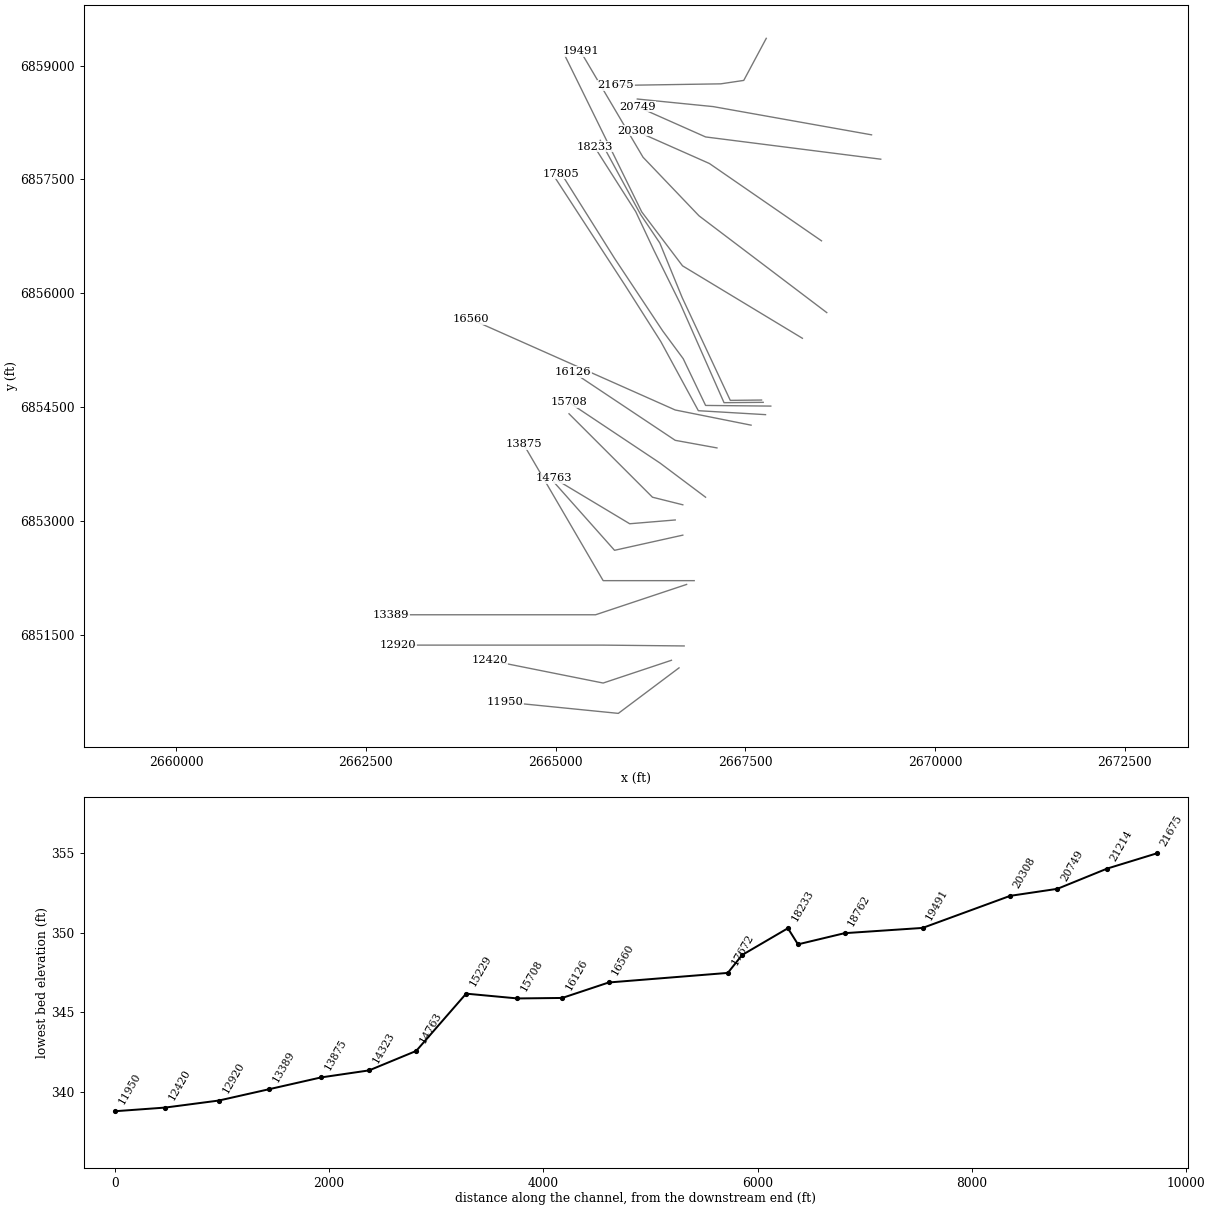
HEC-RAS study Kings Creek 32.prj: Kings Creek 32 Base Level Engineering

--- Kings Creek 32.g01 (geometry) --- (continued)

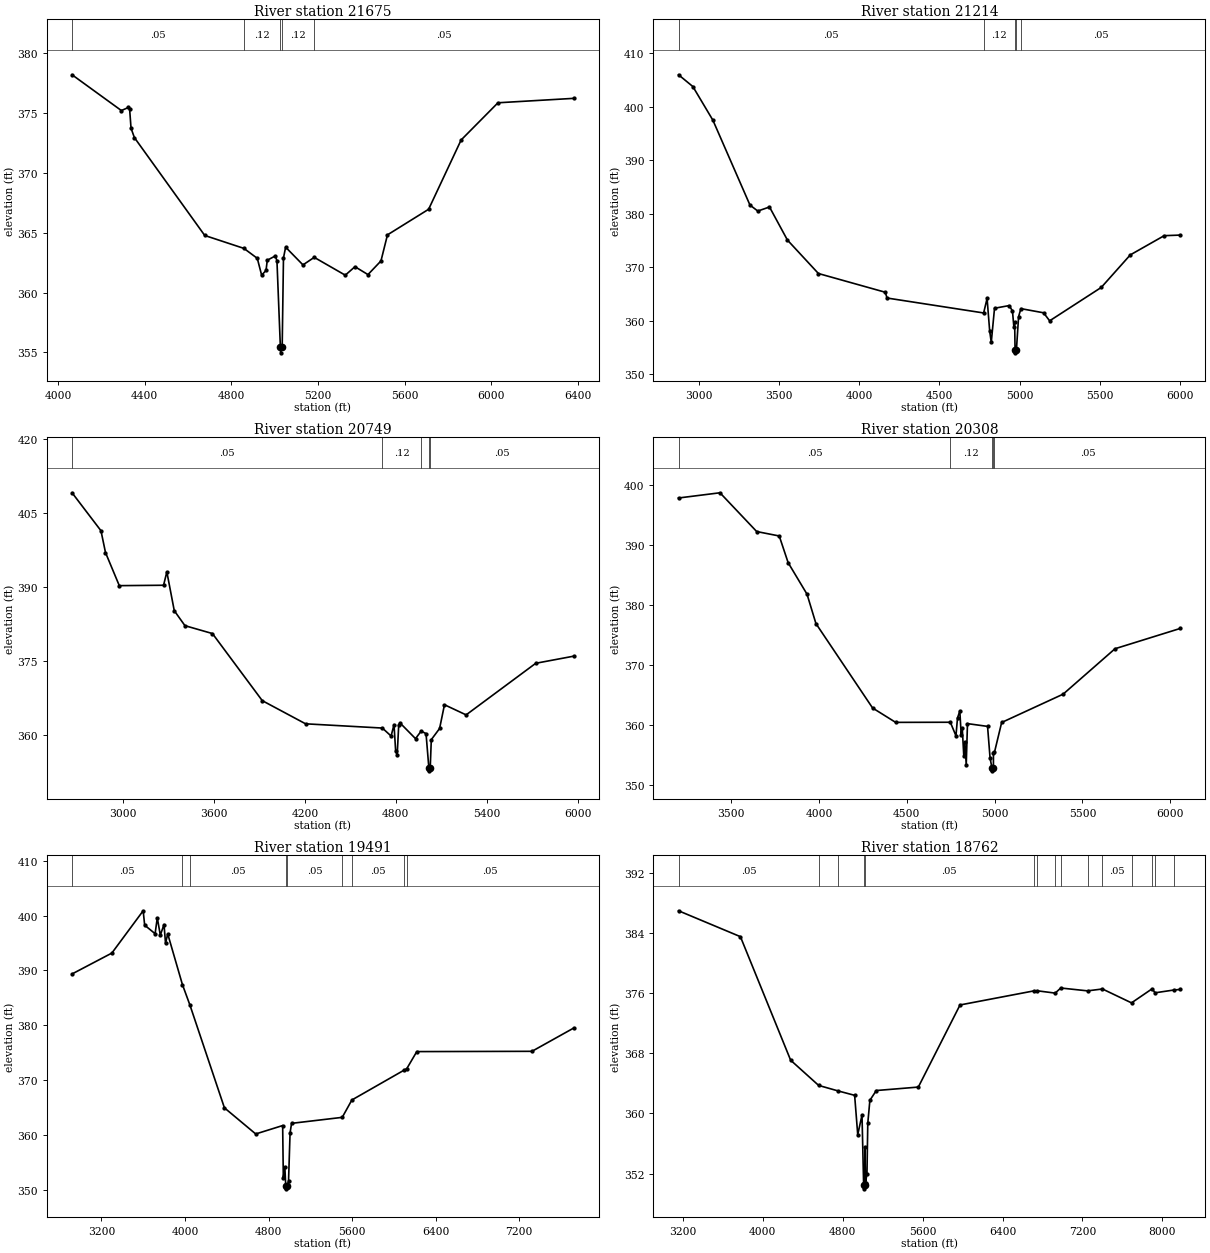
Type RM Length L Ch R = 1,21675,461,461,461
BEGIN DESCRIPTION:
Kings Creek 32 43.0
END DESCRIPTION:
XS GIS Cut Line= 4
      2667776.01      6859361.02      2667479.34      6858806.33
      2667176.00      6858761.00      2665795.71      6858739.81
#Sta/Elev= 30
  4064.6  378.20  4292.2  375.21  4324.7  375.47  4330.4  375.30  4336.8  373.73
  4352.3  372.95  4677.0  364.77  4857.8  363.69  4919.5  362.86  4939.7  361.45
  4959.9  361.85  4965.7  362.70  5002.8  363.06  5010.3  362.65  5026.1  355.46
  5027.4  354.96  5034.5  355.46  5040.4  362.89  5050.4  363.79  5130.4  362.31
  5182.4  362.94  5325.7  361.45  5370.4  362.16  5430.4  361.50  5490.4  362.64
  5520.4  364.82  5710.4  366.96  5860.4  372.75  6030.5  375.86  6380.8  376.23
#Mann=5,-1,0
  4064.6    0.05       0  4857.8    0.12       0  5026.1    0.07       0
  5034.5    0.12       0  5182.4    0.05       0
Bank Sta=5026.1,5034.5
Exp/Cntr=0.3,0.1

Type RM Length L Ch R = 1,21214,465,465,465
BEGIN DESCRIPTION:
Kings Creek 32 42.0
END DESCRIPTION:
XS GIS Cut Line= 3
      2669163.77      6858088.76      2667076.00      6858461.00
      2666075.98      6858561.00
#Sta/Elev= 30
  2874.8  405.96  2964.0  403.76  3088.9  397.47  3319.7  381.62  3368.5  380.50
  3441.4  381.26  3553.1  375.08  3746.1  368.83  4162.6  365.33  4173.6  364.25
  4775.4  361.46  4796.8  364.18  4812.7  358.17  4822.8  355.96  4843.1  362.34
  4934.5  362.84  4954.9  361.83  4963.5  358.89  4968.6  359.78  4971.0  354.51
  4972.2  354.01  4979.4  354.51  4993.0  360.78  5007.5  362.27  5148.8  361.49
  5186.4  359.99  5508.0  366.23  5688.9  372.31  5900.0  375.90  6000.5  376.01
#Mann=5,-1,0
  2874.8    0.05       0  4775.4    0.12       0  4971.0    0.07       0
  4979.4    0.12       0  5007.5    0.05       0
Bank Sta=4971,4979.4
Exp/Cntr=0.3,0.1

Type RM Length L Ch R = 1,20749,441,441,441
BEGIN DESCRIPTION:
Kings Creek 32 41.0
END DESCRIPTION:
XS GIS Cut Line= 3
      2669285.29      6857767.58      2666976.00      6858061.00
      2666076.04      6858460.98
#Sta/Elev= 30
  2662.9  409.15  2853.7  401.45  2883.6  397.02  2974.7  390.31  3267.0  390.39
  3288.6  393.10  3337.6  385.23  3408.1  382.19  3589.6  380.59  3918.5  366.98
  4204.5  362.28  4711.4  361.42  4769.0  359.80  4788.3  362.11  4799.2  356.70
  4809.3  356.00  4819.4  362.05  4829.5  362.41  4930.3  359.27  4967.5  360.80
  4999.7  360.29  5018.6  353.24  5019.9  352.74  5027.2  353.24  5034.5  359.07
  5089.2  361.33  5121.4  366.15  5264.3  364.09  5724.0  374.56  5975.6  376.01
#Mann=5,-1,0
  2662.9    0.05       0  4711.4    0.12       0  4967.5    0.05       0
  5018.6    0.03       0  5027.2    0.05       0
Bank Sta=5018.6,5027.2
Exp/Cntr=0.3,0.1

Type RM Length L Ch R = 1,20308,817,817,817
BEGIN DESCRIPTION:
Kings Creek 32 40.0
END DESCRIPTION:
XS GIS Cut Line= 3
      2668504.02      6856691.20      2667026.00      6857711.00
      2666056.08      6858140.86
#Sta/Elev= 30
  3200.5  397.84  3436.4  398.71  3645.4  392.24  3773.8  391.50  3824.5  387.04
  3932.0  381.78  3982.7  376.88  4305.2  362.79  4436.4  360.39  4747.8  360.41
  4779.8  358.15  4788.6  361.12  4801.8  362.30  4809.6  358.30  4815.7  359.41
  4824.5  354.76  4830.5  357.11  4838.3  353.31  4845.4  360.18  4959.7  359.72
  4973.9  354.48  4984.5  352.80  4985.7  352.30  4993.1  352.80  4993.2  355.35
  4999.2  355.41  5039.9  360.37  5390.0  365.10  5685.3  372.68  6057.1  376.07
#Mann=5,-1,0
  3200.5    0.05       0  4747.8    0.12       0  4984.5    0.03       0
  4993.1    0.12       0  4999.2    0.05       0
Bank Sta=4984.5,4993.1
Exp/Cntr=0.3,0.1

Type RM Length L Ch R = 1,19491,729,729,729
BEGIN DESCRIPTION:
Mapping XS 5ec70878
END DESCRIPTION:
XS GIS Cut Line= 4
      2668573.48      6855745.01      2666889.44      6857021.06
      2666151.59      6857793.63      2665326.96      6859191.17
#Sta/Elev= 30
  2919.2  389.37  3300.2  393.17  3599.8  400.86  3614.3  398.24  3714.2  396.69
  3735.0  399.58  3764.1  396.44  3799.5  398.36  3814.0  394.93  3834.9  396.66
  3975.5  387.45  4047.9  383.69  4377.8  365.02  4677.4  360.27  4935.3  361.80
  4941.6  352.31  4956.2  354.25  4964.9  350.79  4966.5  350.29  4976.6  350.79
  4991.5  351.63  5006.1  360.45  5020.7  362.20  5505.6  363.29  5598.0  366.45
  6093.7  371.83  6123.3  372.14  6219.4  375.25  7322.0  375.30  7723.1  379.55
#Mann=9,-1,0
  2919.2    0.05       0  3975.5   0.075       0  4047.9    0.05       0
  4964.9    0.03       0  4976.6    0.05       0  5505.6   0.075       0
  5598.0    0.05       0  6093.7   0.075       0  6123.3    0.05       0
Bank Sta=4964.9,4976.6
Exp/Cntr=0.3,0.1

Type RM Length L Ch R = 1,18762,435,435,435
BEGIN DESCRIPTION:
Mapping XS a71f2e18
END DESCRIPTION:
XS GIS Cut Line= 4
      2668252.25      6855406.50      2666672.43      6856361.34
      2666134.23      6857073.14      2665127.30      6859121.73
#Sta/Elev= 30
  3158.2  387.01  3777.4  383.56  4280.0  367.10  4560.2  363.74  4753.9  363.01
  4920.3  362.42  4951.3  357.17  4994.0  359.79  5010.4  350.46  5012.0  349.96
  5022.1  350.46  5022.8  355.48  5029.1  350.80  5043.6  351.94  5051.9  358.70
  5072.8  361.76  5137.3  363.06  5557.6  363.52  5974.8  374.46  6711.5  376.33
  6746.8  376.35  6927.2  376.04  6982.8  376.72  7250.6  376.34  7399.8  376.59
  7690.7  374.74  7897.5  376.62  7926.6  376.08  8113.2  376.45  8179.2  376.53
#Mann=15,-1,0
  3158.2    0.05       0  4560.2   0.075       0  4753.9    0.05       0
  5010.4    0.03       0  5022.1    0.05       0  6711.5   0.075       0
  6746.8    0.05       0  6927.2   0.075       0  6982.8    0.05       0
  7250.6   0.075       0  7399.8    0.05       0  7690.7   0.075       0
  7897.5    0.05       0  7926.6   0.075       0  8113.2    0.05       0
Bank Sta=5010.4,5022.1
Exp/Cntr=0.3,0.1

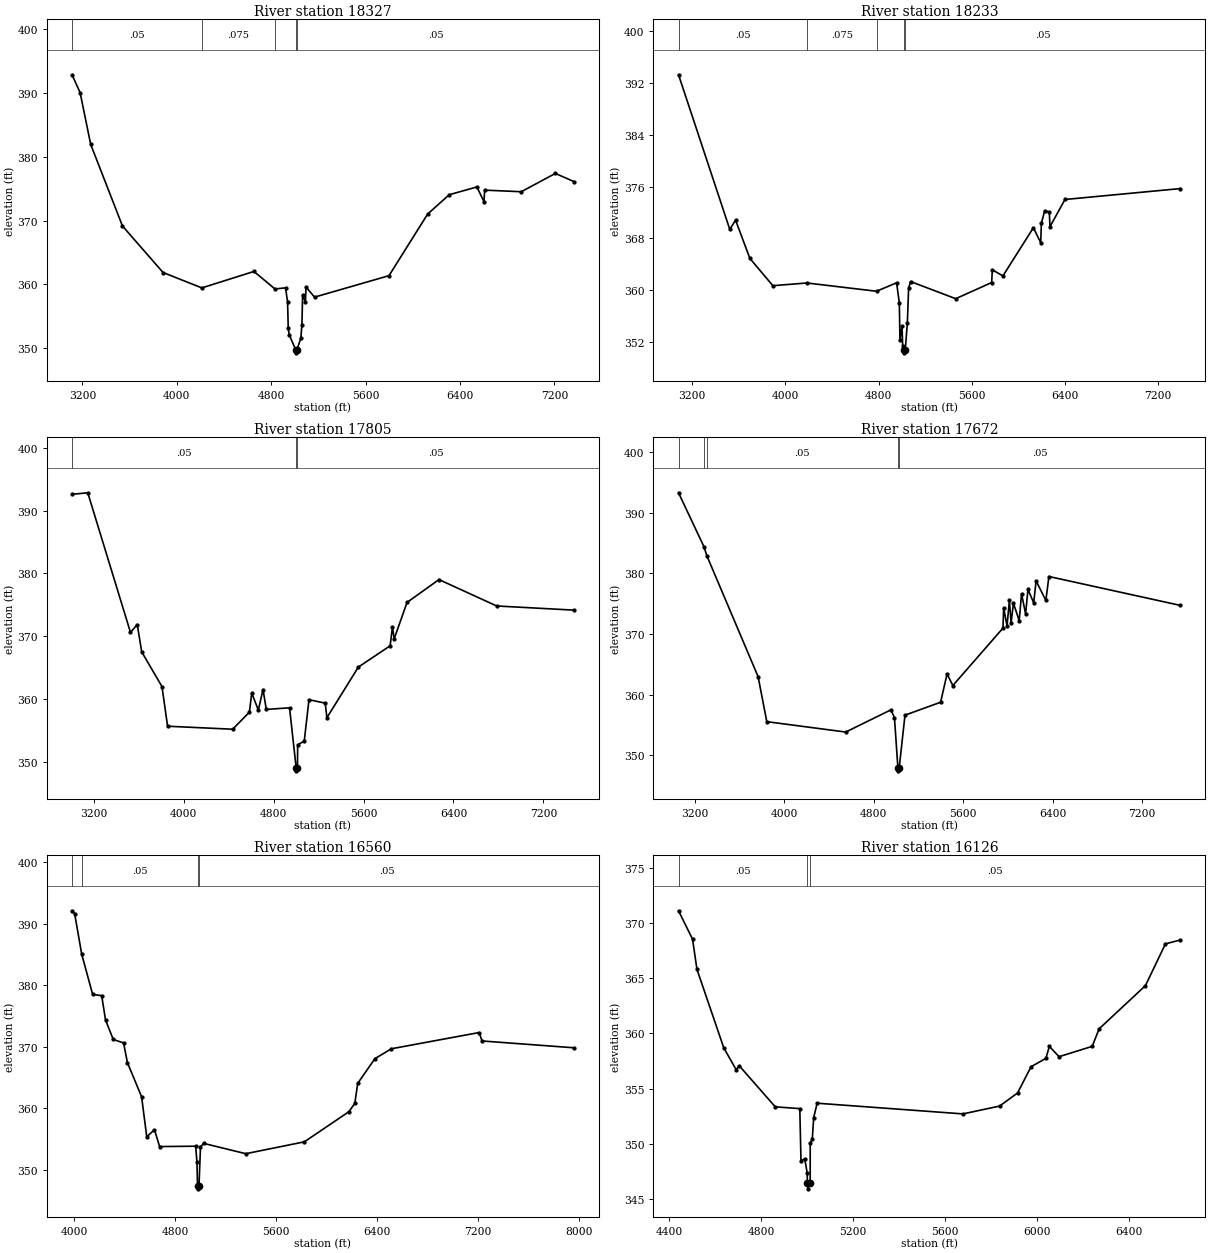
Type RM Length L Ch R = 1,18327,94,94,94
BEGIN DESCRIPTION:
Mapping XS 9f1623a4
END DESCRIPTION:
XS GIS Cut Line= 6
      2667713.99      6854592.17      2667301.67      6854587.83
      2666667.99      6855941.99      2666372.85      6856662.48
      2666121.12      6857035.74      2665587.41      6858016.36
#Sta/Elev= 30
  3112.2  392.89  3180.2  390.10  3270.2  381.96  3539.1  369.17  3883.5  361.86
  4212.3  359.45  4653.7  362.03  4831.8  359.28  4921.4  359.46  4938.7  357.24
  4944.3  353.15  4952.3  352.11  5006.9  349.76  5008.5  349.26  5018.6  349.76
  5051.0  351.58  5060.4  353.69  5065.8  358.30  5089.8  357.26  5095.2  359.58
  5167.2  358.00  5798.2  361.37  6125.8  371.04  6308.6  374.07  6543.2  375.29
  6603.0  372.98  6608.7  374.79  6919.3  374.54  7208.0  377.41  7364.9  376.14
#Mann=5,-1,0
  3112.2    0.05       0  4212.3   0.075       0  4831.8    0.05       0
  5006.9    0.05       0  5018.6    0.05       0
Bank Sta=5006.9,5018.6
Exp/Cntr=0.3,0.1

Type RM Length L Ch R = 1,18233,428,428,428
BEGIN DESCRIPTION:
Mapping XS f19fcd78
END DESCRIPTION:
XS GIS Cut Line= 6
      2667735.66      6854561.78      2667219.21      6854557.44
      2666641.95      6855863.87      2666294.73      6856566.99
      2666056.01      6857074.81      2665510.09      6857932.68
#Sta/Elev= 30
  3083.3  393.30  3523.0  369.39  3573.0  370.80  3695.4  364.89  3892.8  360.66
  4184.4  361.08  4782.6  359.80  4955.0  361.11  4978.3  358.00  4983.8  352.21
  5001.6  354.41  5007.1  351.32  5017.9  350.77  5019.5  350.27  5029.6  350.77
  5047.2  354.88  5058.3  360.33  5075.2  361.30  5462.3  358.65  5771.0  361.15
  5776.6  363.13  5867.2  362.17  6129.1  369.63  6192.0  367.30  6197.5  370.30
  6225.8  372.27  6265.9  372.03  6271.4  369.79  6399.9  374.00  7390.2  375.69
#Mann=5,-1,0
  3083.3    0.05       0  4184.4   0.075       0  4782.6    0.05       0
  5017.9    0.05       0  5029.6    0.05       0
Bank Sta=5017.9,5029.6
Exp/Cntr=0.3,0.1

Type RM Length L Ch R = 1,17805,133,133,133
BEGIN DESCRIPTION:
Mapping XS a84611e0
END DESCRIPTION:
XS GIS Cut Line= 6
      2667835.66      6854512.38      2666976.25      6854521.06
      2666681.11      6855137.38      2666412.01      6855501.96
      2665778.33      6856456.82      2665075.40      6857576.30
#Sta/Elev= 30
  3007.2  392.59  3146.9  392.83  3526.9  370.61  3586.9  371.87  3626.9  367.51
  3806.9  362.00  3856.9  355.69  4436.0  355.21  4584.7  357.93  4605.6  360.98
  4664.1  358.25  4705.8  361.53  4735.1  358.36  4941.7  358.62  5000.6  349.09
  5002.2  348.59  5012.4  349.09  5014.0  352.73  5072.6  353.32  5114.7  359.91
  5259.1  359.36  5274.1  357.04  5554.1  365.10  5836.5  368.48  5857.5  371.47
  5872.6  369.59  5986.8  375.38  6271.0  379.02  6784.6  374.82  7471.0  374.16
#Mann=3,-1,0
  3007.2    0.05       0  5000.6    0.03       0  5012.4    0.05       0
Bank Sta=5000.6,5012.4
Exp/Cntr=0.3,0.1

Type RM Length L Ch R = 1,17672,1112,1112,1112
BEGIN DESCRIPTION:
Mapping XS 82155533
END DESCRIPTION:
XS GIS Cut Line= 5
      2667766.20      6854399.53      2666880.76      6854451.61
      2666385.97      6855363.07      2665917.22      6856100.92
      2664997.09      6857515.83
#Sta/Elev= 30
  3056.6  393.27  3284.4  384.36  3309.3  382.92  3768.0  362.98  3845.6  355.57
  4551.3  353.86  4955.6  357.52  4987.0  356.23  5017.6  347.97  5019.2  347.47
  5029.4  347.97  5081.0  356.64  5399.5  358.77  5457.1  363.43  5508.8  361.52
  5957.1  370.98  5963.1  374.30  5993.4  371.33  6014.5  375.56  6029.6  371.81
  6050.7  375.08  6102.1  372.20  6123.2  376.61  6159.4  373.33  6180.5  377.34
  6231.9  375.14  6253.0  378.76  6340.6  375.54  6367.8  379.48  7542.6  374.72
#Mann=5,-1,0
  3056.6    0.05       0  3284.4     0.1       0  3309.3    0.05       0
  5017.6    0.03       0  5029.4    0.05       0
Bank Sta=5017.6,5029.4
Exp/Cntr=0.3,0.1

Type RM Length L Ch R = 1,16560,434,434,434
BEGIN DESCRIPTION:
Kings Creek 32 32.0
END DESCRIPTION:
XS GIS Cut Line= 3
      2667575.98      6854261.00      2666576.00      6854461.00
      2663876.04      6855660.98
#Sta/Elev= 30
  3984.4  392.13  4004.8  391.67  4060.6  385.07  4147.5  378.51  4218.9  378.32
  4249.5  374.35  4310.7  371.18  4392.3  370.62  4422.9  367.41  4535.1  361.86
  4575.9  355.34  4637.1  356.49  4677.8  353.75  4963.4  353.81  4973.6  351.25
  4977.9  347.37  4979.5  346.87  4989.7  347.37  5001.6  353.68  5026.1  354.27
  5360.5  352.59  5824.2  354.52  6177.2  359.43  6223.7  360.78  6246.9  364.04
  6383.0  368.06  6513.7  369.67  7208.5  372.31  7231.8  370.94  7958.8  369.83
#Mann=4,-1,0
  3984.4     0.1       0  4060.6    0.05       0  4977.9    0.04       0
  4989.7    0.05       0
Bank Sta=4977.9,4989.7
Exp/Cntr=0.3,0.1

Type RM Length L Ch R = 1,16126,418,418,418
BEGIN DESCRIPTION:
Kings Creek 32 31.0
END DESCRIPTION:
XS GIS Cut Line= 3
      2667125.99      6853961.00      2666576.00      6854061.00
      2665226.00      6854961.00
#Sta/Elev= 30
  4441.6  371.13  4502.6  368.55  4521.6  365.82  4638.5  358.68  4691.9  356.72
  4705.9  357.06  4862.1  353.34  4968.8  353.18  4973.9  348.46  4990.4  348.61
  5000.6  347.37  5002.2  346.40  5003.8  345.90  5014.0  346.40  5014.1  350.06
  5023.1  350.40  5029.1  352.36  5044.2  353.67  5678.1  352.70  5837.4  353.41
  5915.5  354.60  5974.1  356.98  6038.7  357.74  6053.7  358.83  6095.8  357.89
  6240.0  358.83  6270.1  360.42  6471.4  364.34  6558.5  368.13  6623.1  368.48
#Mann=3,-1,0
  4441.6    0.05       0  5002.2    0.04       0  5014.0    0.05       0
Bank Sta=5002.2,5014
Exp/Cntr=0.3,0.1

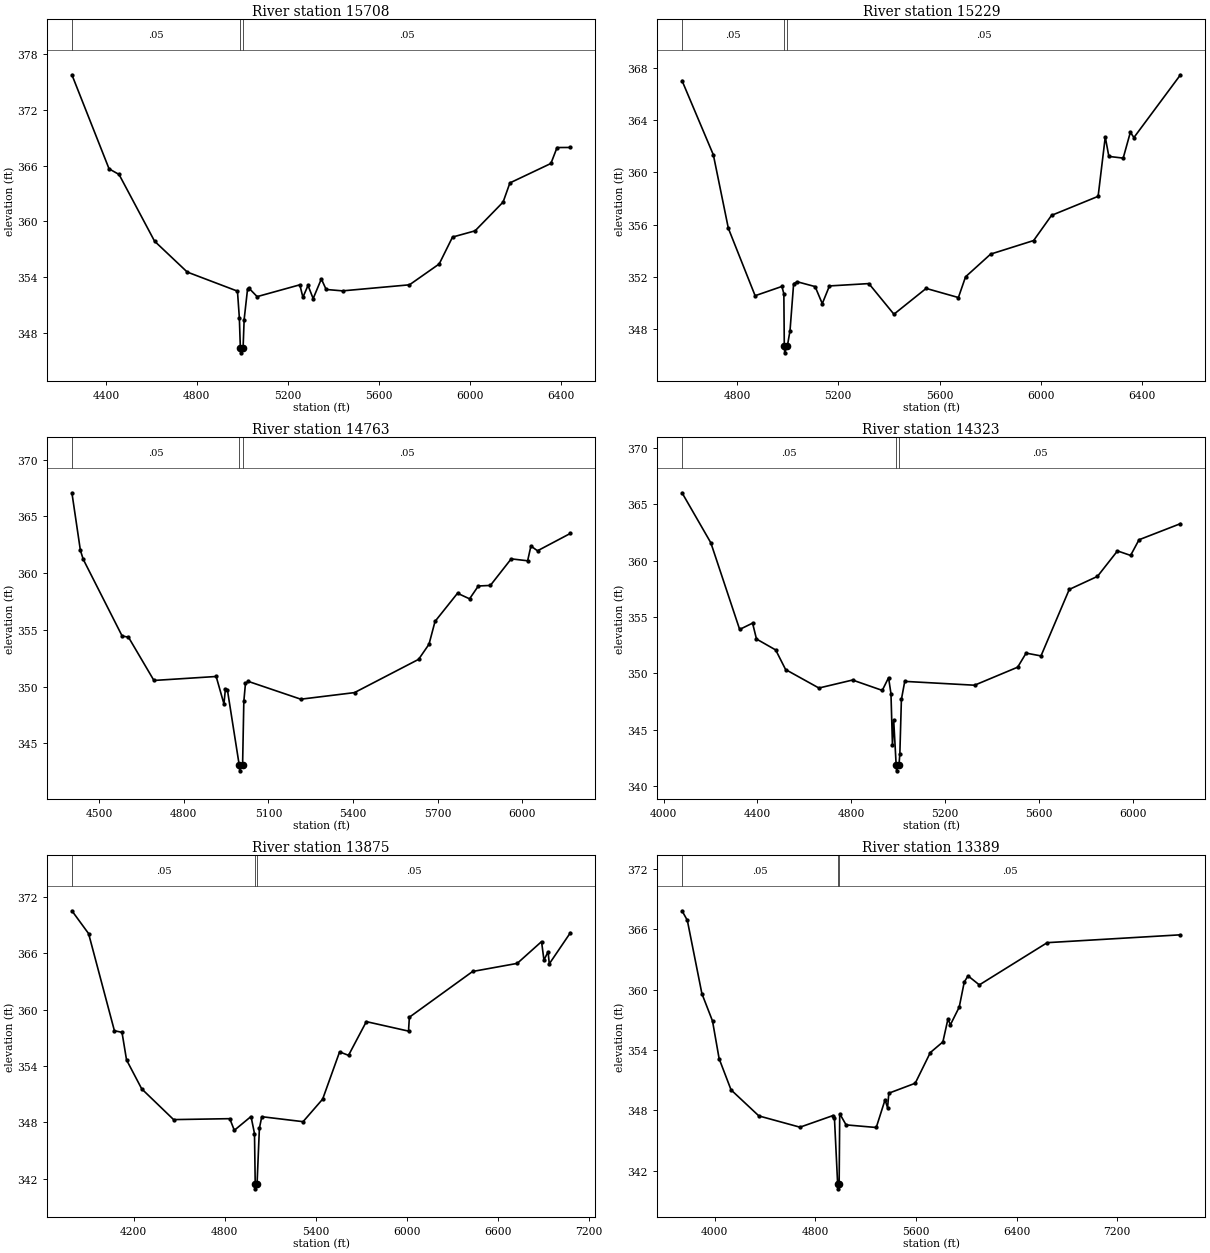
Type RM Length L Ch R = 1,15708,479,479,479
BEGIN DESCRIPTION:
Kings Creek 32 30.0
END DESCRIPTION:
XS GIS Cut Line= 3
      2666975.99      6853311.01      2666376.00      6853761.00
      2665176.01      6854561.00
#Sta/Elev= 30
  4250.4  375.75  4413.9  365.64  4457.7  365.04  4613.9  357.87  4757.7  354.55
  4978.5  352.50  4986.8  349.64  4991.3  346.37  4993.0  345.87  5003.2  346.37
  5007.9  349.45  5022.9  352.73  5028.9  352.82  5065.0  351.91  5252.8  353.18
  5266.3  351.84  5288.8  353.11  5311.4  351.70  5347.4  353.81  5368.5  352.68
  5440.6  352.53  5735.0  353.18  5865.7  355.42  5924.3  358.31  6023.5  358.98
  6146.7  362.07  6176.7  364.13  6357.0  366.22  6384.0  367.93  6442.6  367.94
#Mann=3,-1,0
  4250.4    0.05       0  4991.3    0.04       0  5003.2    0.05       0
Bank Sta=4991.3,5003.2
Exp/Cntr=0.3,0.1

Type RM Length L Ch R = 1,15229,466,466,466
BEGIN DESCRIPTION:
Kings Creek 32 29.0
END DESCRIPTION:
XS GIS Cut Line= 3
      2666675.99      6853211.00      2666276.00      6853311.00
      2665176.02      6854410.98
#Sta/Elev= 30
  4583.1  367.04  4706.8  361.35  4766.0  355.72  4871.7  350.55  4977.4  351.26
  4985.1  350.70  4986.9  346.67  4988.5  346.17  4998.8  346.67  5009.5  347.88
  5023.7  351.47  5037.8  351.62  5108.5  351.25  5136.8  349.94  5165.1  351.30
  5320.7  351.48  5419.7  349.13  5546.9  351.11  5674.2  350.41  5702.5  352.00
  5801.5  353.74  5971.2  354.78  6041.9  356.71  6225.8  358.17  6254.0  362.72
  6268.2  361.23  6324.8  361.10  6353.0  363.08  6367.2  362.68  6551.0  367.49
#Mann=3,-1,0
  4583.1    0.05       0  4986.9    0.04       0  4998.8    0.05       0
Bank Sta=4986.9,4998.8
Exp/Cntr=0.3,0.1

Type RM Length L Ch R = 1,14763,440,440,440
BEGIN DESCRIPTION:
Kings Creek 32 28.0
END DESCRIPTION:
XS GIS Cut Line= 3
      2666576.02      6853011.00      2665976.00      6852961.00
      2664975.99      6853561.01
#Sta/Elev= 30
  4402.9  367.07  4433.0  362.00  4443.1  361.21  4581.0  354.46  4603.6  354.35
  4693.9  350.54  4914.7  350.89  4942.3  348.47  4947.3  349.76  4954.8  349.67
  4996.5  343.08  4998.2  342.58  5008.4  343.08  5012.8  348.69  5018.6  350.28
  5028.3  350.46  5214.9  348.89  5405.4  349.47  5632.8  352.40  5669.7  353.73
  5691.1  355.74  5770.8  358.22  5813.6  357.73  5844.7  358.86  5887.4  358.91
  5961.3  361.25  6019.6  361.08  6031.2  362.38  6054.6  361.96  6171.2  363.49
#Mann=3,-1,0
  4402.9    0.05       0  4996.5    0.04       0  5008.4    0.05       0
Bank Sta=4996.5,5008.4
Exp/Cntr=0.3,0.1

Type RM Length L Ch R = 1,14323,448,448,448
BEGIN DESCRIPTION:
Kings Creek 32 27.0
END DESCRIPTION:
XS GIS Cut Line= 3
      2666675.99      6852811.00      2665776.00      6852611.00
      2664976.01      6853510.99
#Sta/Elev= 30
  4078.1  366.04  4201.0  361.60  4323.9  353.91  4379.0  354.47  4395.7  353.06
  4477.6  352.09  4519.9  350.35  4662.0  348.71  4805.4  349.42  4932.2  348.50
  4959.1  349.63  4969.3  348.21  4975.7  343.61  4980.8  345.89  4991.5  341.86
  4993.2  341.36  5003.4  341.86  5007.2  342.88  5013.8  347.70  5028.1  349.30
  5325.8  348.96  5509.7  350.56  5545.7  351.81  5609.2  351.56  5729.7  357.46
  5850.1  358.62  5935.4  360.88  5991.4  360.48  6027.3  361.87  6204.2  363.30
#Mann=3,-1,0
  4078.1    0.05       0  4991.5    0.04       0  5003.4    0.05       0
Bank Sta=4991.5,5003.4
Exp/Cntr=0.3,0.1

Type RM Length L Ch R = 1,13875,486,486,486
BEGIN DESCRIPTION:
Kings Creek 32 26.0
END DESCRIPTION:
XS GIS Cut Line= 3
      2666826.01      6852211.00      2665626.00      6852211.00
      2664575.99      6854011.02
#Sta/Elev= 30
  3794.0  370.52  3904.0  368.09  4074.0  357.75  4124.0  357.58  4154.0  354.64
  4254.0  351.56  4464.0  348.29  4834.0  348.39  4864.0  347.15  4974.0  348.62
  4996.9  346.81  5001.7  341.42  5003.3  340.92  5013.7  341.42  5029.2  347.37
  5044.9  348.60  5316.9  348.07  5445.9  350.47  5557.6  355.50  5616.3  355.13
  5733.7  358.72  6011.5  357.71  6017.3  359.19  6434.1  364.06  6727.7  364.92
  6888.1  367.24  6903.8  365.27  6931.1  366.16  6939.0  364.87  7077.9  368.18
#Mann=3,-1,0
  3794.0    0.05       0  5001.7    0.04       0  5013.7    0.05       0
Bank Sta=5001.7,5013.7
Exp/Cntr=0.3,0.1

Type RM Length L Ch R = 1,13389,469,469,469
BEGIN DESCRIPTION:
Kings Creek 32 25.0
END DESCRIPTION:
XS GIS Cut Line= 3
      2666726.01      6852161.00      2665526.00      6851761.00
      2662826.02      6851761.00
#Sta/Elev= 30
  3739.2  367.83  3781.4  366.88  3897.3  359.59  3981.7  356.87  4034.4  353.12
  4129.2  350.02  4350.6  347.43  4677.4  346.31  4940.9  347.47  4951.4  347.27
  4977.0  340.68  4978.7  340.18  4989.0  340.68  4993.6  347.65  5044.1  346.54
  5284.1  346.28  5354.1  349.03  5374.1  348.25  5384.1  349.69  5594.1  350.68
  5714.1  353.73  5814.1  354.79  5854.1  357.05  5874.1  356.50  5944.1  358.25
  5984.1  360.74  6014.1  361.36  6104.1  360.46  6644.1  364.66  7704.1  365.44
#Mann=3,-1,0
  3739.2    0.05       0  4977.0    0.04       0  4989.0    0.05       0
Bank Sta=4977,4989
Exp/Cntr=0.3,0.1

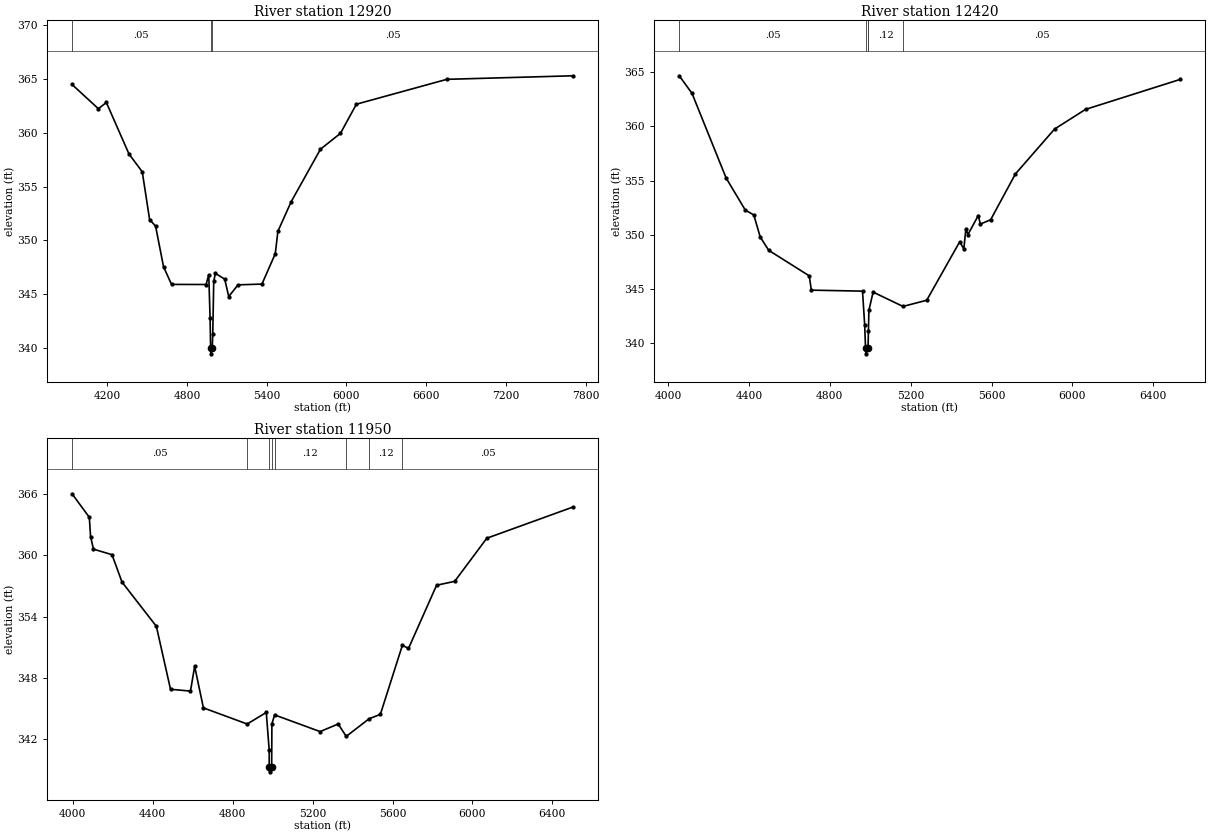
Type RM Length L Ch R = 1,12920,500,500,500
BEGIN DESCRIPTION:
Kings Creek 32 24.0
END DESCRIPTION:
XS GIS Cut Line= 3
      2666693.99      6851349.98      2665626.00      6851361.00
      2662926.05      6851361.00
#Sta/Elev= 30
  3936.5  364.49  4134.5  362.24  4194.5  362.82  4364.5  358.04  4464.5  356.38
  4519.8  351.94  4564.5  351.34  4624.5  347.56  4684.5  345.92  4944.5  345.91
  4964.5  346.82  4974.5  342.76  4978.5  339.97  4980.2  339.47  4990.5  339.97
  4994.5  341.28  5002.0  346.22  5014.5  346.94  5084.5  346.41  5114.5  344.79
  5184.5  345.88  5364.5  345.95  5464.5  348.77  5484.5  350.86  5584.5  353.61
  5804.5  358.48  5954.5  359.95  6074.5  362.66  6754.5  364.97  7704.5  365.30
#Mann=3,-1,0
  3936.5    0.05       0  4978.5    0.04       0  4990.5    0.05       0
Bank Sta=4978.5,4990.5
Exp/Cntr=0.3,0.1

Type RM Length L Ch R = 1,12420,470,470,470
BEGIN DESCRIPTION:
Kings Creek 32 23.0
END DESCRIPTION:
XS GIS Cut Line= 3
      2666526.01      6851161.00      2665626.00      6850861.00
      2664126.00      6851161.00
#Sta/Elev= 30
  4055.4  364.66  4118.7  363.04  4287.3  355.24  4382.2  352.28  4424.3  351.83
  4456.0  349.80  4498.1  348.57  4698.4  346.22  4708.9  344.90  4961.9  344.81
  4972.5  341.73  4976.9  339.53  4978.6  339.03  4989.2  339.53  4991.2  341.16
  4993.5  343.04  5014.3  344.72  5162.1  343.40  5279.4  343.97  5442.6  349.36
  5463.0  348.70  5473.2  350.57  5483.4  350.03  5534.4  351.78  5544.6  350.99
  5595.6  351.39  5718.0  355.61  5911.7  359.75  6064.7  361.56  6533.8  364.33
#Mann=5,-1,0
  4055.4    0.05       0  4976.9    0.07       0  4989.2    0.05       0
  4991.2    0.12       0  5162.1    0.05       0
Bank Sta=4976.9,4989.2
Exp/Cntr=0.3,0.1

Type RM Length L Ch R = 1,11950,439,439,439
BEGIN DESCRIPTION:
Kings Creek 32 22.0
END DESCRIPTION:
XS GIS Cut Line= 3
      2666626.00      6851061.00      2665826.00      6850461.00
      2664325.99      6850611.00
#Sta/Elev= 30
  3996.4  366.01  4082.9  363.71  4089.1  361.82  4103.7  360.59  4196.4  360.05
  4246.4  357.37  4418.3  353.04  4489.1  346.88  4589.1  346.70  4609.9  349.13
  4653.7  345.06  4872.7  343.48  4968.3  344.61  4982.9  340.92  4983.0  339.30
  4984.7  338.80  4995.3  339.30  4996.4  343.49  5010.0  344.37  5237.6  342.74
  5328.0  343.48  5368.4  342.27  5483.2  344.00  5539.1  344.42  5649.4  351.19
  5679.8  350.87  5820.5  357.06  5910.9  357.44  6071.7  361.66  6503.9  364.72
#Mann=8,-1,0
  3996.4    0.05       0  4872.7    0.12       0  4983.0    0.07       0
  4995.3    0.12       0  5010.0    0.12       0  5368.4    0.05       0
  5483.2    0.12       0  5649.4    0.05       0
Bank Sta=4983,4995.3
Exp/Cntr=0.3,0.1