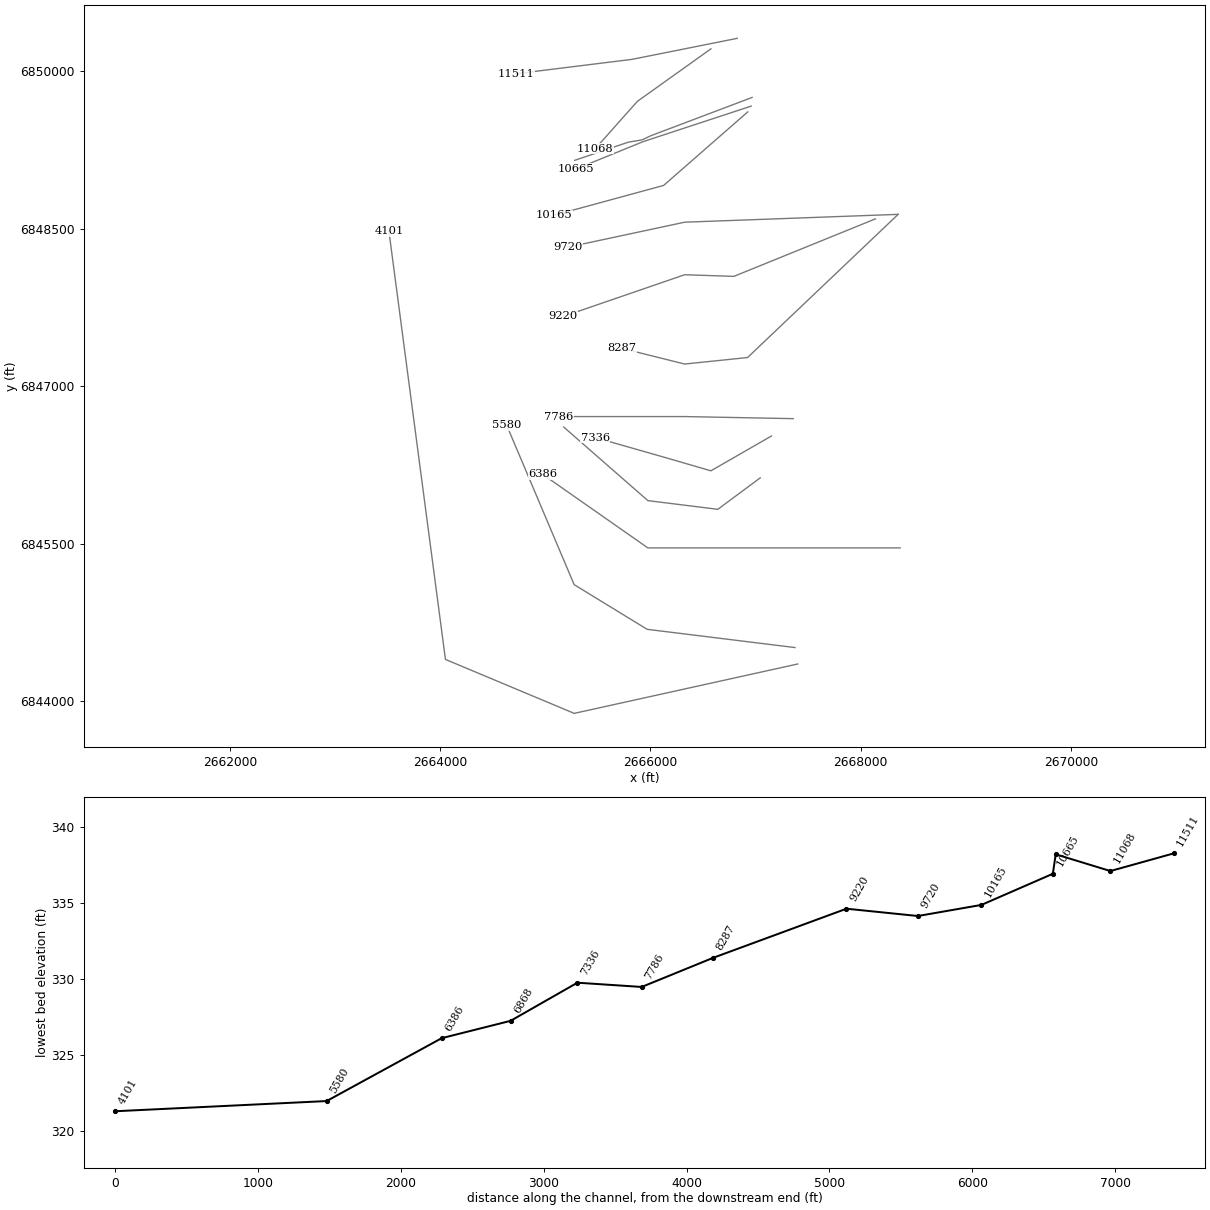
HEC-RAS study Kings Creek 32.prj: Kings Creek 32 Base Level Engineering

--- Kings Creek 32.g01 (geometry) --- (continued)

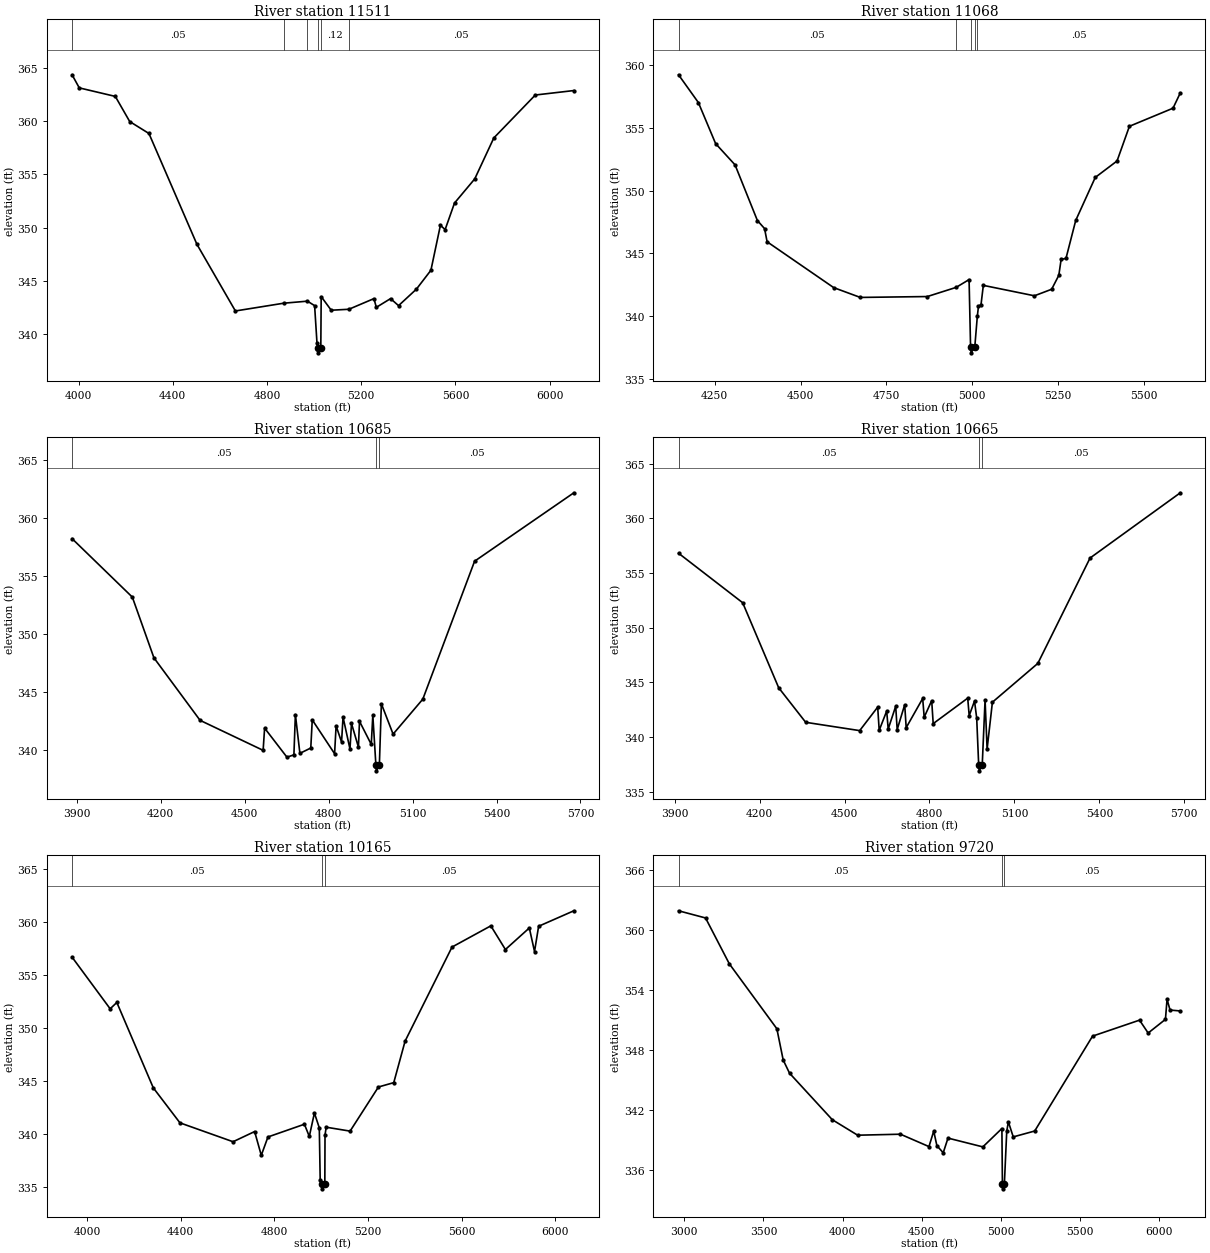
Type RM Length L Ch R = 1,11511,443,443,443
BEGIN DESCRIPTION:
Kings Creek 32 21.0
END DESCRIPTION:
XS GIS Cut Line= 3
      2666826.02      6850311.00      2665826.00      6850111.00
      2664723.59      6849974.12
#Sta/Elev= 30
  3972.4  364.34  4003.0  363.11  4156.0  362.31  4217.2  359.95  4298.8  358.83
  4502.7  348.42  4665.9  342.17  4871.4  342.90  4971.8  343.09  5002.3  342.67
  5012.4  339.15  5016.3  338.74  5018.0  338.24  5028.6  338.74  5030.2  343.52
  5072.8  342.24  5147.8  342.33  5254.2  343.33  5264.3  342.51  5324.8  343.33
  5358.7  342.67  5434.6  344.22  5496.1  345.99  5536.4  350.21  5556.5  349.81
  5596.3  352.30  5682.3  354.57  5763.2  358.41  5939.4  362.44  6103.1  362.86
#Mann=6,-1,0
  3972.4    0.05       0  4871.4     0.1       0  4971.8    0.12       0
  5016.3    0.07       0  5028.6    0.12       0  5147.8    0.05       0
Bank Sta=5016.3,5028.6
Exp/Cntr=0.3,0.1

Type RM Length L Ch R = 1,11068,383,383,383
BEGIN DESCRIPTION:
Kings Creek 32 20.0
END DESCRIPTION:
XS GIS Cut Line= 3
      2666575.99      6850211.00      2665876.00      6849711.00
      2665476.00      6849261.00
#Sta/Elev= 30
  4144.5  359.21  4202.3  357.00  4252.6  353.73  4309.2  352.04  4374.3  347.61
  4395.2  346.97  4402.6  345.92  4596.7  342.27  4674.2  341.49  4869.5  341.56
  4953.5  342.29  4991.2  342.91  4995.5  337.58  4997.2  337.08  5007.9  337.58
  5015.3  340.01  5018.5  340.77  5026.0  340.92  5032.7  342.45  5181.6  341.62
  5231.8  342.14  5252.7  343.25  5259.4  344.51  5273.6  344.60  5302.0  347.62
  5358.9  351.04  5422.4  352.35  5458.4  355.11  5585.5  356.55  5606.8  357.77
#Mann=5,-1,0
  4144.5    0.05       0  4953.5    0.12       0  4995.5    0.07       0
  5007.9    0.12       0  5015.3    0.05       0
Bank Sta=4995.5,5007.9
Exp/Cntr=0.3,0.1

Type RM Length L Ch R = 1,10685,20,20,20
BEGIN DESCRIPTION:
Mapping XS 1615b68d
END DESCRIPTION:
XS GIS Cut Line= 5
      2666967.49      6849748.42      2666003.93      6849383.83
      2665921.46      6849344.77      2665791.25      6849323.07
      2665280.01      6849149.77
#Sta/Elev= 30
  3883.0  358.23  4098.4  353.18  4175.5  347.94  4340.5  342.54  4565.8  339.95
  4571.1  341.87  4650.9  339.36  4675.8  339.56  4681.1  343.04  4697.2  339.69
  4736.1  340.15  4741.4  342.58  4821.2  339.66  4826.6  342.06  4846.1  340.67
  4851.4  342.82  4876.2  340.06  4881.6  342.27  4906.4  340.23  4910.2  342.46
  4952.3  340.46  4957.8  342.98  4968.8  338.68  4970.6  338.18  4981.2  338.68
  4988.4  343.97  5030.3  341.35  5136.5  344.37  5321.5  356.28  5676.3  362.19
#Mann=3,-1,0
  3883.0    0.05       0  4968.8    0.05       0  4981.2    0.05       0
Bank Sta=4968.8,4981.2
Exp/Cntr=0.3,0.1

Type RM Length L Ch R = 1,10665,500,500,500
BEGIN DESCRIPTION:
Mapping XS 63787206
END DESCRIPTION:
XS GIS Cut Line= 3
      2666958.79      6849665.95      2665930.14      6849327.41
      2665292.16      6849067.01
#Sta/Elev= 30
  3913.8  356.81  4140.3  352.28  4267.5  344.50  4362.8  341.34  4553.5  340.58
  4617.1  342.73  4622.4  340.61  4648.9  342.37  4654.2  340.73  4680.7  342.81
  4685.9  340.68  4712.5  342.95  4717.7  340.85  4776.0  343.52  4781.3  341.81
  4807.8  343.32  4813.1  341.22  4935.0  343.55  4940.2  341.95  4959.0  343.29
  4966.7  341.73  4973.8  337.40  4975.6  336.90  4986.2  337.40  4996.3  343.38
  5003.5  338.90  5022.2  343.18  5182.6  346.73  5367.0  356.37  5685.8  362.34
#Mann=3,-1,0
  3913.8    0.05       0  4973.8    0.05       0  4986.2    0.05       0
Bank Sta=4973.8,4986.2
Exp/Cntr=0.3,0.1

Type RM Length L Ch R = 1,10165,445,445,445
BEGIN DESCRIPTION:
Kings Creek 32 18.0
END DESCRIPTION:
XS GIS Cut Line= 3
      2666925.97      6849610.98      2666126.00      6848911.00
      2665083.89      6848626.96
#Sta/Elev= 30
  3936.6  356.69  4099.3  351.82  4127.8  352.42  4283.5  344.37  4397.4  341.07
  4624.2  339.29  4716.3  340.25  4744.7  338.01  4773.2  339.74  4928.9  340.94
  4949.8  339.79  4971.6  342.00  4992.5  340.60  4996.3  335.71  5003.7  335.35
  5005.5  334.85  5016.1  335.35  5016.9  339.93  5022.0  340.66  5124.0  340.29
  5245.0  344.45  5310.5  344.86  5359.0  348.78  5559.3  357.64  5725.1  359.64
  5787.3  357.41  5889.5  359.44  5911.7  357.22  5929.2  359.60  6079.7  361.06
#Mann=3,-1,0
  3936.6    0.05       0  5003.7    0.03       0  5016.1    0.05       0
Bank Sta=5003.7,5016.1
Exp/Cntr=0.3,0.1

Type RM Length L Ch R = 1,9720,500,500,500
BEGIN DESCRIPTION:
Kings Creek 32 17.0
END DESCRIPTION:
XS GIS Cut Line= 3
      2668356.47      6848635.64      2666326.00      6848561.00
      2665214.10      6848323.14
#Sta/Elev= 30
  2964.0  361.96  3134.6  361.24  3284.7  356.65  3584.9  350.15  3624.9  347.02
  3664.9  345.70  3935.1  341.04  4095.2  339.49  4365.4  339.59  4545.5  338.35
  4575.6  339.90  4595.6  338.44  4635.6  337.73  4665.6  339.20  4885.8  338.32
  5006.1  340.16  5009.3  334.62  5011.0  334.12  5021.7  334.62  5036.7  339.89
  5047.0  340.83  5077.7  339.32  5213.3  339.91  5578.7  349.41  5875.2  351.01
  5929.8  349.72  6038.9  351.09  6049.1  353.10  6068.0  352.02  6132.9  351.93
#Mann=3,-1,0
  2964.0    0.05       0  5009.3    0.03       0  5021.7    0.05       0
Bank Sta=5009.3,5021.7
Exp/Cntr=0.3,0.1

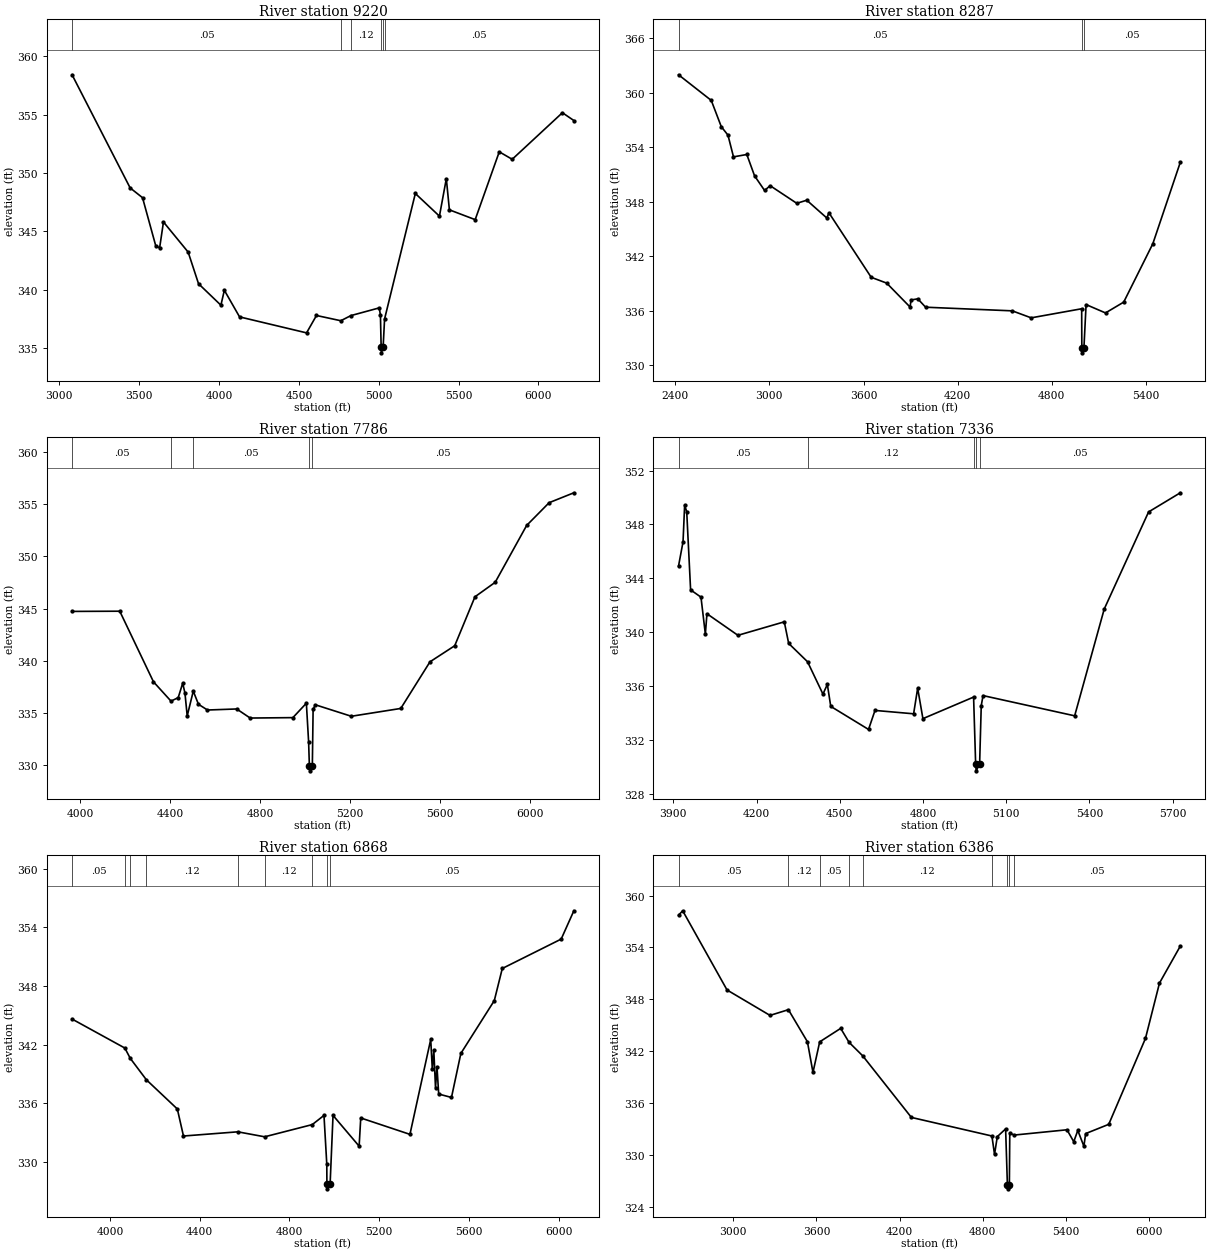
Type RM Length L Ch R = 1,9220,933,933,933
BEGIN DESCRIPTION:
Kings Creek 32 16.0
END DESCRIPTION:
XS GIS Cut Line= 4
      2668139.44      6848592.24      2666793.96      6848045.36
      2666326.00      6848061.00      2665170.88      6847663.48
#Sta/Elev= 30
  3079.5  358.42  3443.1  348.73  3520.7  347.89  3603.7  343.76  3627.8  343.59
  3651.8  345.81  3806.4  343.23  3871.4  340.52  4011.5  338.68  4033.1  339.96
  4128.3  337.68  4547.9  336.31  4609.9  337.80  4762.3  337.35  4825.4  337.79
  5002.7  338.45  5010.4  337.85  5015.0  335.10  5016.7  334.60  5027.4  335.10
  5036.4  337.50  5229.0  348.25  5379.9  346.31  5423.1  349.52  5442.3  346.85
  5603.8  346.01  5754.6  351.82  5835.6  351.18  6150.0  355.17  6221.7  354.50
#Mann=6,-1,0
  3079.5    0.05       0  4762.3     0.1       0  4825.4    0.12       0
  5015.0    0.07       0  5027.4    0.12       0  5036.4    0.05       0
Bank Sta=5015,5027.4
Exp/Cntr=0.3,0.1

Type RM Length L Ch R = 1,8287,501,501,501
BEGIN DESCRIPTION:
Kings Creek 32 14.0
END DESCRIPTION:
XS GIS Cut Line= 4
      2668356.43      6848635.62      2666924.16      6847272.79
      2666326.00      6847211.00      2665726.05      6847360.99
#Sta/Elev= 30
  2421.6  361.96  2630.1  359.14  2694.0  356.25  2736.5  355.32  2771.7  352.93
  2856.6  353.19  2906.0  350.84  2969.9  349.23  3005.1  349.76  3174.9  347.82
  3238.5  348.16  3365.9  346.21  3380.0  346.77  3649.0  339.68  3747.7  339.04
  3896.5  336.41  3903.4  337.19  3945.9  337.31  3995.6  336.39  4547.6  335.99
  4668.2  335.22  4989.9  336.22  4990.9  331.87  4992.8  331.37  5004.1  331.87
  5018.0  336.68  5141.7  335.76  5257.7  336.95  5443.2  343.37  5618.4  352.34
#Mann=3,-1,0
  2421.6    0.05       0  4990.9    0.04       0  5004.1    0.05       0
Bank Sta=4990.9,5004.1
Exp/Cntr=0.3,0.1

Type RM Length L Ch R = 1,7786,450,450,450
BEGIN DESCRIPTION:
Kings Creek 32 13.0
END DESCRIPTION:
XS GIS Cut Line= 3
      2667358.15      6846691.20      2666326.00      6846711.00
      2665126.04      6846711.00
#Sta/Elev= 30
  3963.1  344.73  4175.3  344.75  4325.3  337.98  4403.3  336.13  4435.3  336.47
  4455.3  337.85  4465.3  336.90  4475.3  334.71  4502.3  337.09  4525.3  335.83
  4565.4  335.28  4695.4  335.38  4755.4  334.51  4945.4  334.55  5005.4  335.93
  5015.4  332.23  5018.8  329.95  5020.7  329.45  5032.0  329.95  5035.4  335.33
  5045.4  335.78  5205.4  334.68  5425.4  335.43  5555.4  339.90  5665.4  341.44
  5755.4  346.13  5845.4  347.52  5985.4  352.97  6085.4  355.15  6195.4  356.10
#Mann=5,-1,0
  3963.1    0.05       0  4403.3    0.12       0  4502.3    0.05       0
  5018.8    0.03       0  5032.0    0.05       0
Bank Sta=5018.8,5032
Exp/Cntr=0.3,0.1

Type RM Length L Ch R = 1,7336,468,468,468
BEGIN DESCRIPTION:
Kings Creek 32 12.0
END DESCRIPTION:
XS GIS Cut Line= 4
      2667151.58      6846526.06      2666575.49      6846194.59
      2666176.00      6846311.00      2665475.96      6846511.01
#Sta/Elev= 30
  3918.9  344.92  3935.1  346.71  3940.9  349.43  3948.4  348.95  3962.4  343.15
  3999.8  342.61  4015.6  339.87  4021.3  341.38  4133.0  339.78  4300.1  340.78
  4315.9  339.18  4383.9  337.82  4439.5  335.42  4455.3  336.14  4467.6  334.51
  4603.8  332.80  4627.1  334.21  4766.3  333.96  4780.9  335.86  4799.8  333.60
  4982.5  335.20  4989.9  330.23  4991.9  329.73  5004.2  330.23  5010.1  334.57
  5016.6  335.31  5346.8  333.81  5453.4  341.73  5613.3  348.93  5727.7  350.35
#Mann=5,-1,0
  3918.9    0.05       0  4383.9    0.12       0  4982.5    0.05       0
  4989.9    0.03       0  5004.2    0.05       0
Bank Sta=4989.9,5004.2
Exp/Cntr=0.3,0.1

Type RM Length L Ch R = 1,6868,482,482,482
BEGIN DESCRIPTION:
Kings Creek 32 11.0
END DESCRIPTION:
XS GIS Cut Line= 4
      2667044.75      6846127.58      2666641.14      6845828.13
      2665976.00      6845911.00      2665175.97      6846611.02
#Sta/Elev= 30
  3831.2  344.61  4066.4  341.64  4090.4  340.59  4162.3  338.39  4300.2  335.40
  4327.6  332.63  4569.7  333.06  4689.4  332.55  4901.4  333.80  4953.7  334.74
  4966.2  329.74  4966.7  327.72  4968.7  327.22  4981.0  327.72  4994.0  334.74
  5110.3  331.59  5117.5  334.48  5336.7  332.80  5429.3  342.52  5436.4  339.48
  5443.0  341.44  5450.6  337.58  5457.3  339.69  5464.8  336.93  5521.8  336.58
  5563.6  341.09  5712.6  346.50  5748.2  349.79  6010.6  352.80  6067.1  355.70
#Mann=9,-1,0
  3831.2    0.05       0  4066.4    0.12       0  4090.4     0.1       0
  4162.3    0.12       0  4569.7     0.1       0  4689.4    0.12       0
  4901.4    0.05       0  4966.7    0.03       0  4981.0    0.05       0
Bank Sta=4966.7,4981
Exp/Cntr=0.3,0.1

Type RM Length L Ch R = 1,6386,806,806,806
BEGIN DESCRIPTION:
Kings Creek 32 10.0
END DESCRIPTION:
XS GIS Cut Line= 3
      2668375.96      6845461.00      2665976.00      6845461.00
      2664976.01      6846160.99
#Sta/Elev= 30
  2604.7  357.73  2634.7  358.24  2954.7  349.08  3264.7  346.14  3397.5  346.80
  3534.7  343.09  3574.7  339.55  3623.2  343.08  3774.7  344.64  3834.8  343.03
  3933.8  341.46  4284.7  334.34  4865.8  332.19  4884.7  330.06  4904.7  332.12
  4964.7  333.01  4977.5  326.58  4979.5  326.08  4991.8  326.58  4994.7  332.52
  5027.0  332.30  5407.5  332.91  5456.3  331.53  5485.5  332.83  5529.5  331.01
  5542.2  332.47  5708.7  333.54  5973.8  343.48  6074.9  349.88  6225.3  354.16
#Mann=9,-1,0
  2604.7    0.05       0  3397.5    0.12       0  3623.2    0.05       0
  3834.8     0.1       0  3933.8    0.12       0  4865.8     0.1       0
  4977.5    0.07       0  4991.8     0.1       0  5027.0    0.05       0
Bank Sta=4977.5,4991.8
Exp/Cntr=0.3,0.1

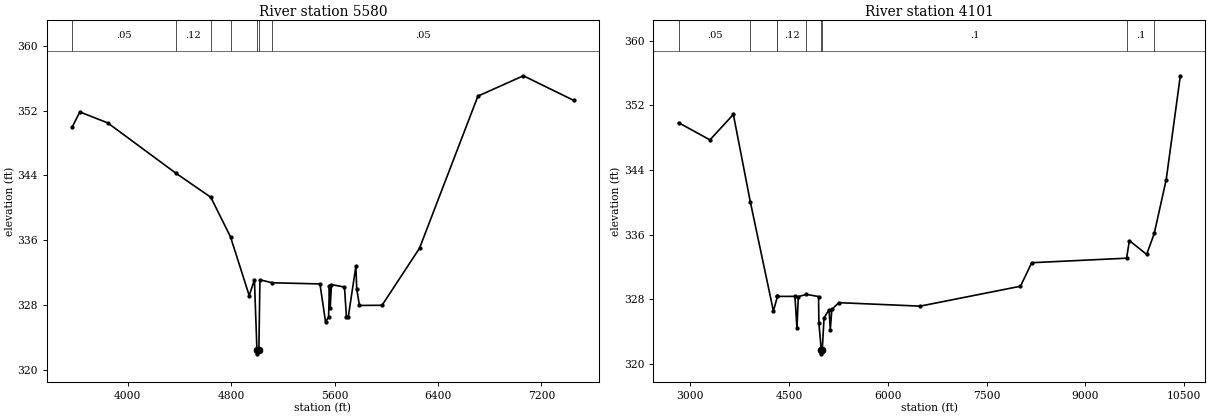
Type RM Length L Ch R = 1,5580,1479,1479,1479
BEGIN DESCRIPTION:
Mapping XS d1b8e3ff
END DESCRIPTION:
XS GIS Cut Line= 4
      2667375.56      6844512.38      2665969.30      6844685.99
      2665274.86      6845111.34      2664632.50      6846630.42
#Sta/Elev= 30
  3570.1  349.93  3630.1  351.83  3845.6  350.48  4372.3  344.27  4642.9  341.29
  4795.5  336.39  4940.0  329.14  4980.3  331.08  4999.8  322.44  5001.8  321.94
  5014.9  322.44  5022.8  331.09  5118.8  330.72  5487.1  330.58  5530.3  325.89
  5553.8  326.48  5560.5  330.28  5566.4  327.63  5576.0  330.50  5676.6  330.19
  5692.0  326.50  5706.2  326.50  5764.9  332.76  5771.4  329.96  5792.7  327.92
  5967.3  327.94  6257.0  334.99  6708.8  353.79  7060.5  356.30  7450.7  353.25
#Mann=7,-1,0
  3570.1    0.05       0  4372.3    0.12       0  4642.9    0.05       0
  4795.5     0.1       0  4999.8    0.07       0  5014.9     0.1       0
  5118.8    0.05       0
Bank Sta=4999.8,5014.9
Exp/Cntr=0.3,0.1

Type RM Length L Ch R = 1,4101,0,0,0
BEGIN DESCRIPTION:
Kings Creek 32 7.0
END DESCRIPTION:
XS GIS Cut Line= 4
      2667401.63      6844356.13      2665275.59      6843886.00
      2664050.90      6844399.53      2663512.93      6848477.70
#Sta/Elev= 30
  2822.6  349.86  3299.5  347.73  3654.9  350.88  3914.4  339.99  4263.1  326.57
  4324.4  328.37  4324.8  328.37  4589.9  328.38  4620.6  324.42  4641.1  328.35
  4764.9  328.62  4948.4  328.36  4953.6  325.08  4989.7  321.77  4991.7  321.27
  5004.8  321.77  5032.1  325.73  5108.4  326.73  5126.8  324.27  5150.5  326.77
  5256.5  327.60  6490.9  327.17  8014.2  329.63  8185.4  332.54  9625.0  333.10
  9668.2  335.27  9930.4  333.57 10045.7  336.16 10227.4  342.83 10441.5  355.66
#Mann=9,-1,0
  2822.6    0.05       0  3914.4    0.12       0  4324.4     0.1       0
  4324.8    0.12       0  4764.9     0.1       0  4989.7   0.035       0
  5004.8     0.1       0  9625.0     0.1       0 10045.7    0.05       0
Bank Sta=4989.7,5004.8
Exp/Cntr=0.3,0.1

Chan Stop Cuts=-1