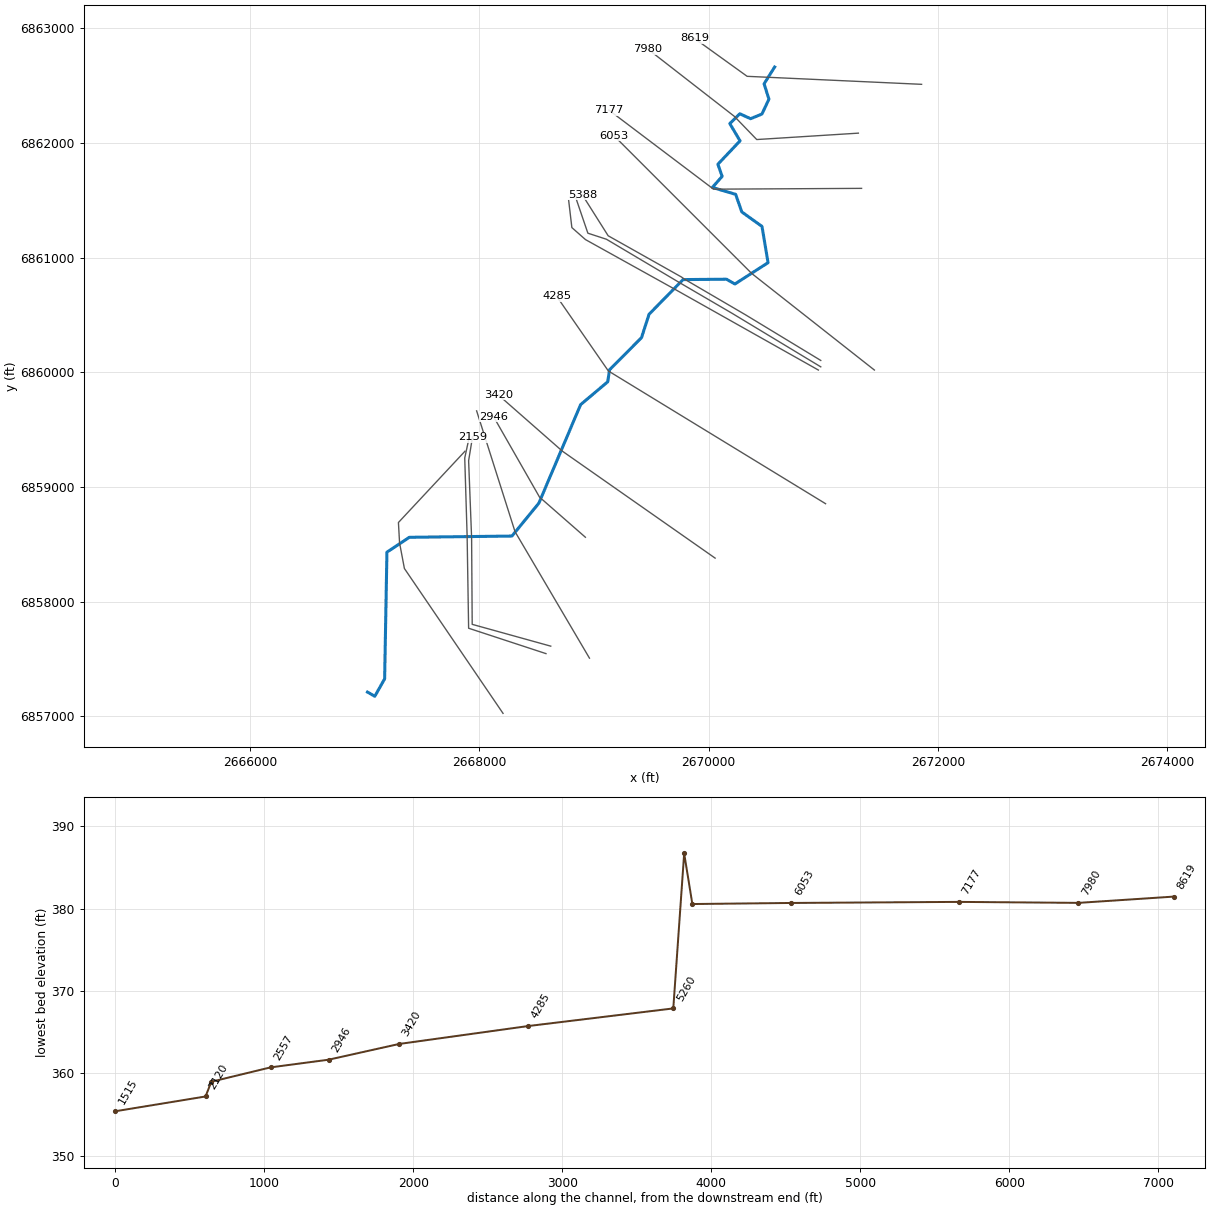
--- Kings Creek 32_1.prj (project) ---

Proj Title=Kings Creek 32_1 Base Level Engineering
Current Plan=p01
Default Exp/Contr=0.3,0.1
English Units
Geom File=g01
Flow File=f01
Plan File=p01
Y Axis Title=Elevation
X Axis Title(PF)=Main Channel Distance
X Axis Title(XS)=Station
BEGIN DESCRIPTION:
Kings Creek 32_1
END DESCRIPTION:
DSS Export Rating Curves= 0
DSS Export Rating Curve Sorted= 0
DSS Export Volume Flow Curves= 0
DXF OffsetX= 0
DXF OffsetY= 0
DXF ScaleX= 1
DXF ScaleY= 10

--- Kings Creek 32_1.p01 (plan) ---

Plan Title=Multiple Run
Short Identifier=Multiple
Geom File=g01
Flow File=f01
Subcritical Flow
K Sum by GR= 0
Std Step Tol= 0.01
Critical Tol= 0.01
Num of Std Step Trials= 20
Max Error Tol= 0.3
Flow Tol Ratio= 0.001
Split Flow NTrial= 30
Split Flow Tol= 0.02
Split Flow Ratio= 0.02
Log Output Level= 0
Friction Slope Method= 1
Unsteady Friction Slope Method= 2
Unsteady Bridges Friction Slope Method= 1
Parabolic Critical Depth
Global Vel Dist=  1 , 1 , 1
Global Log Level= 0
CheckData=True
Encroach Param= -1, 0, 0, 0
BEGIN DESCRIPTION:
Multiple Run
END DESCRIPTION:

--- Kings Creek 32_1.f01 (steady flow) ---

Flow Title=Multiple
Number of Profiles=7
Profile Names=10-year,25-year,50-year,1pct_min,100-year,1pct_plu,500-year
River Rch & RM= Kings Creek 32_1,Reach-1,8619
     449     589     700     413     823    1643    1138
River Rch & RM= Kings Creek 32_1,Reach-1,7980
     659     885    1067     638    1273    2539    1810
River Rch & RM= Kings Creek 32_1,Reach-1,6053
     670     901    1087     650    1297    2587    1846
River Rch & RM= Kings Creek 32_1,Reach-1,5333
     853    1161    1413     851    1699    3390    2456
Boundary for River Rch & Prof#=Kings Creek 32_1,Reach-1,1
Up Type=0
Dn Type=3
Dn Slope=0.005
Boundary for River Rch & Prof#=Kings Creek 32_1,Reach-1,2
Up Type=0
Dn Type=3
Dn Slope=0.005
Boundary for River Rch & Prof#=Kings Creek 32_1,Reach-1,3
Up Type=0
Dn Type=3
Dn Slope=0.005
Boundary for River Rch & Prof#=Kings Creek 32_1,Reach-1,4
Up Type=0
Dn Type=3
Dn Slope=0.005
Boundary for River Rch & Prof#=Kings Creek 32_1,Reach-1,5
Up Type=0
Dn Type=3
Dn Slope=0.005
Boundary for River Rch & Prof#=Kings Creek 32_1,Reach-1,6
Up Type=0
Dn Type=3
Dn Slope=0.005
Boundary for River Rch & Prof#=Kings Creek 32_1,Reach-1,7
Up Type=0
Dn Type=3
Dn Slope=0.005

--- Kings Creek 32_1.g01 (geometry) ---

Geom Title=Existing Conditions
Program Version=4.10

River Reach=Kings Creek 32_1,Reach-1
Reach XY= 30
        2670576.        6862661.      2670484.02      6862514.32
       2670526.1       6862381.1      2670465.39      6862250.93
      2670365.95      6862210.25      2670272.55       6862253.2
      2670184.96      6862167.71      2670274.42      6862017.05
      2670081.12      6861813.29      2670118.15      6861707.59
      2670032.99      6861610.75      2670236.17      6861550.67
      2670289.39      6861397.67      2670465.66      6861271.12
      2670518.53      6860954.93      2670229.32      6860769.04
      2670156.01      6860810.84       2669777.5      6860807.54
      2669481.26      6860505.53      2669415.24       6860301.3
      2669136.54      6860020.75      2669120.74      6859916.47
      2668884.14      6859717.06      2668520.48      6858858.57
      2668285.82      6858571.47      2667391.21      6858560.49
      2667195.59       6858431.2      2667175.49      6857326.21
      2667089.78      6857174.25        2667026.        6857211.

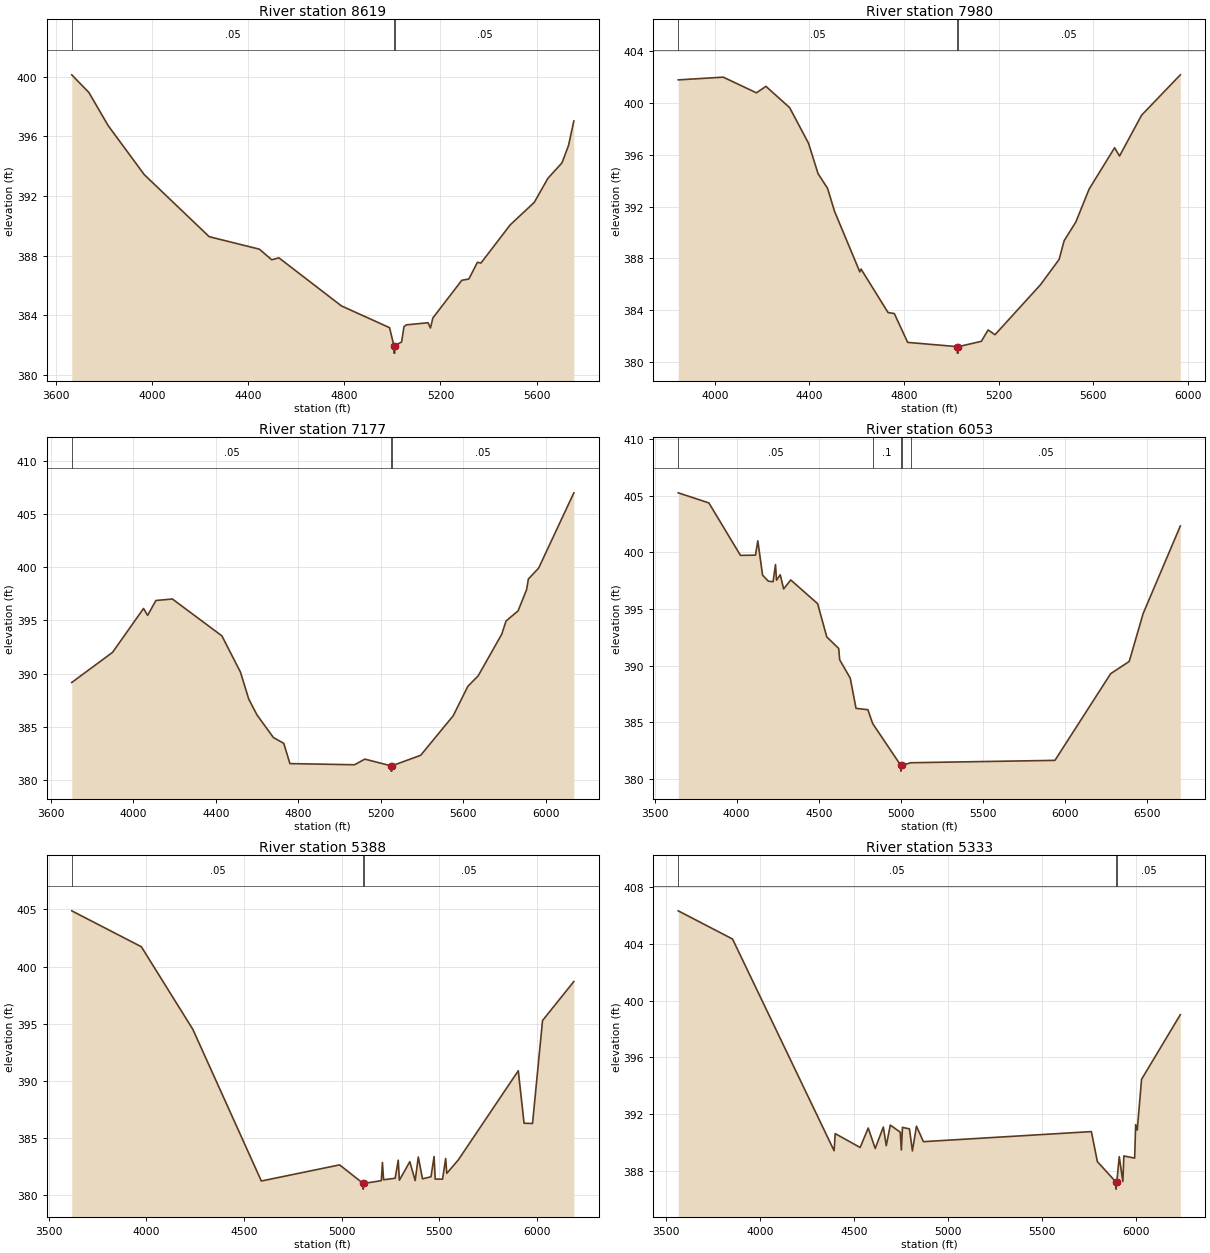
Type RM Length L Ch R = 1 ,8619    ,639,639,639
BEGIN DESCRIPTION:
Kings Creek 32_1 12.0
END DESCRIPTION:
XS GIS Cut Line= 3
      2671857.31      6862510.02      2670336.15       6862579.8
      2669876.01        6862911.
#Sta/Elev= 30
  3665.5  400.14  3736.9  398.95    3817  396.73  3967.1  393.44  4237.4  389.27
  4446.6  388.43  4497.7  387.72  4527.7  387.85    4788  384.62  4988.2  383.16
  5006.2  381.95  5006.5  381.45    5010  381.45  5010.2  381.95  5038.3   382.2
  5048.3  383.23  5058.3  383.35  5148.4  383.49  5158.4  383.14  5168.4  383.81
  5288.8  386.34  5318.3  386.43  5353.9  387.55  5368.6   387.5  5490.1  390.06
  5590.7  391.58  5647.2  393.19  5705.9  394.23  5733.1   395.4  5755.2  397.04
#Mann= 3 ,-1 , 0
  3665.5     .05       0  5006.2     .03       0  5010.2     .05       0
Bank Sta=5006.2,5010.2
XS Rating Curve= 0 ,0
Exp/Cntr=0.3,0.1

Type RM Length L Ch R = 1 ,7980    ,803,803,803
BEGIN DESCRIPTION:
Mapping XS 8aaacb70
END DESCRIPTION:
XS GIS Cut Line= 4
      2671306.05      6862084.37      2670419.88      6862028.54
       2670224.5       6862230.9      2669471.63      6862816.47
#Sta/Elev= 30
  3845.2  401.79  4035.6     402  4175.9  400.79    4216  401.29  4316.2  399.65
  4396.3  396.89  4436.4  394.55  4476.5  393.42  4506.6  391.62  4613.1  386.96
  4618.2  387.18  4732.6  383.82  4758.8  383.75  4815.4  381.52  5025.1  381.19
  5025.4  380.69  5028.9  380.69  5029.1  381.19  5126.7   381.6  5155.6  382.48
  5184.6  382.11  5377.3  385.98  5455.9  387.93  5476.9  389.37  5526.6  390.82
  5582.7  393.36  5690.4  396.55  5711.2  395.91  5804.4  399.06  5968.2  402.18
#Mann= 3 ,-1 , 0
  3845.2     .05       0  5025.1     .03       0  5029.1     .05       0
Bank Sta=5025.1,5029.1
XS Rating Curve= 0 ,0
Exp/Cntr=0.3,0.1

Type RM Length L Ch R = 1 ,7177    ,1124,1124,1124
BEGIN DESCRIPTION:
Mapping XS 8538b807
END DESCRIPTION:
XS GIS Cut Line= 3
      2671333.97      6861602.89      2670043.07      6861595.91
      2669130.48      6862285.58
#Sta/Elev= 30
  3701.2  389.16  3899.2     392  4049.2  396.13  4069.2  395.48  4109.2  396.88
  4189.2  397.02  4429.2  393.55  4519.2  390.14  4559.2  387.61  4599.2  386.11
  4679.2  383.97  4729.2  383.43  4759.2  381.52  5072.6  381.41  5122.5  381.94
  5249.5  381.31  5249.8  380.81  5253.3  380.81  5253.5  381.31  5393.1   382.3
  5551.2  386.03    5622   388.8  5671.9  389.78  5786.4  393.71  5807.2  394.95
  5865.5   395.9  5907.1  397.91  5915.4   398.9  5965.3  399.93    6136  407.02
#Mann= 3 ,-1 , 0
  3701.2     .05       0  5249.5     .03       0  5253.5     .05       0
Bank Sta=5249.5,5253.5
XS Rating Curve= 0 ,0
Exp/Cntr=0.3,0.1

Type RM Length L Ch R = 1 ,6053    ,665,665,665
BEGIN DESCRIPTION:
Kings Creek 32_1 9.0
END DESCRIPTION:
XS GIS Cut Line= 3
      2671445.61      6860018.92        2670376.        6860861.
      2669175.98      6862061.02
#Sta/Elev= 30
  3644.1  405.24  3830.8  404.35  4023.2  399.72  4114.5  399.74    4129     401
  4157.9  397.97  4193.1  397.44    4222   397.4  4236.5  398.91  4242.8  397.53
  4265.4  398.01  4286.2  396.76  4329.5  397.55  4493.1  395.46  4549.1  392.52
  4621.4  391.51  4627.7   390.5  4691.9  388.89  4727.1  386.22  4799.4   386.1
  4828.5  384.88  5000.1  381.18  5000.4  380.68  5004.4  381.18  5059.8  381.42
  5938.8  381.63  6278.2  389.28  6391.3  390.36  6476.2  394.59  6702.5  402.31
#Mann= 5 ,-1 , 0
  3644.1     .05       0  4828.5      .1       0  5000.1     .07       0
  5004.4      .1       0  5059.8     .05       0
Bank Sta=5000.1,5004.4
XS Rating Curve= 0 ,0
Exp/Cntr=0.3,0.1

Type RM Length L Ch R = 1 ,5388    ,55,55,55
BEGIN DESCRIPTION:
Mapping XS 15e95235
END DESCRIPTION:
XS GIS Cut Line= 6
      2670978.09      6860102.65      2670322.19      6860500.37
      2669791.22      6860810.76      2669762.44      6860830.54
      2669124.42       6861189.7      2668899.05       6861546.5
#Sta/Elev= 30
  3617.9  404.88  3974.3  401.74  4237.9  394.52  4588.8  381.26  4989.6  382.67
  5109.9  381.05  5110.3  380.55  5114.3  381.05    5203  381.29  5208.9  382.88
  5214.7  381.37  5273.9   381.5  5289.9  383.08  5295.6  381.33  5349.1  382.95
  5376.5   381.3  5392.5  383.36  5414.1  381.45  5457.5  381.63  5473.4   383.4
  5479.1  381.43  5516.7  381.42  5532.7  383.23  5538.4  381.93  5597.7  383.11
  5904.6   390.9  5934.2  386.31  5977.5  386.29  6028.8  395.29  6189.1   398.7
#Mann= 3 ,-1 , 0
  3617.9     .05       0  5109.9     .03       0  5114.3     .05       0
Bank Sta=5109.9,5114.3
XS Rating Curve= 0 ,0
Exp/Cntr=0.3,0.1

Type RM Length L Ch R = 1 ,5333    ,73,73,73
BEGIN DESCRIPTION:
Mapping XS 84870e04
END DESCRIPTION:
XS GIS Cut Line= 6
      2670978.08      6860046.83      2670203.57      6860514.33
       2669745.8      6860781.51      2669109.23      6861159.32
      2668947.54      6861212.12       2668843.4      6861517.58
#Sta/Elev= 30
  3565.3  406.33  3853.9  404.34  4393.5   389.4  4399.3  390.61  4531.8  389.63
  4574.8     391    4612  389.56    4655  391.07  4670.7  389.76  4692.2  391.21
    4745  390.71  4750.9  389.45  4756.7  391.05  4793.9  390.94  4809.6  389.39
  4831.1  391.13  4868.3  390.04  5760.6  390.75  5792.5  388.63  5891.2  387.19
  5891.6  386.69  5895.6  387.19  5908.6  388.98  5927.8  387.23  5933.1  389.03
  5990.5  388.88  5995.8  391.24  6004.3  390.86  6027.2  394.44  6233.1     399
#Mann= 3 ,-1 , 0
  3565.3     .05       0  5891.2     .03       0  5895.6     .05       0
Bank Sta=5891.2,5895.6
XS Rating Curve= 0 ,0
Exp/Cntr=0.3,0.1

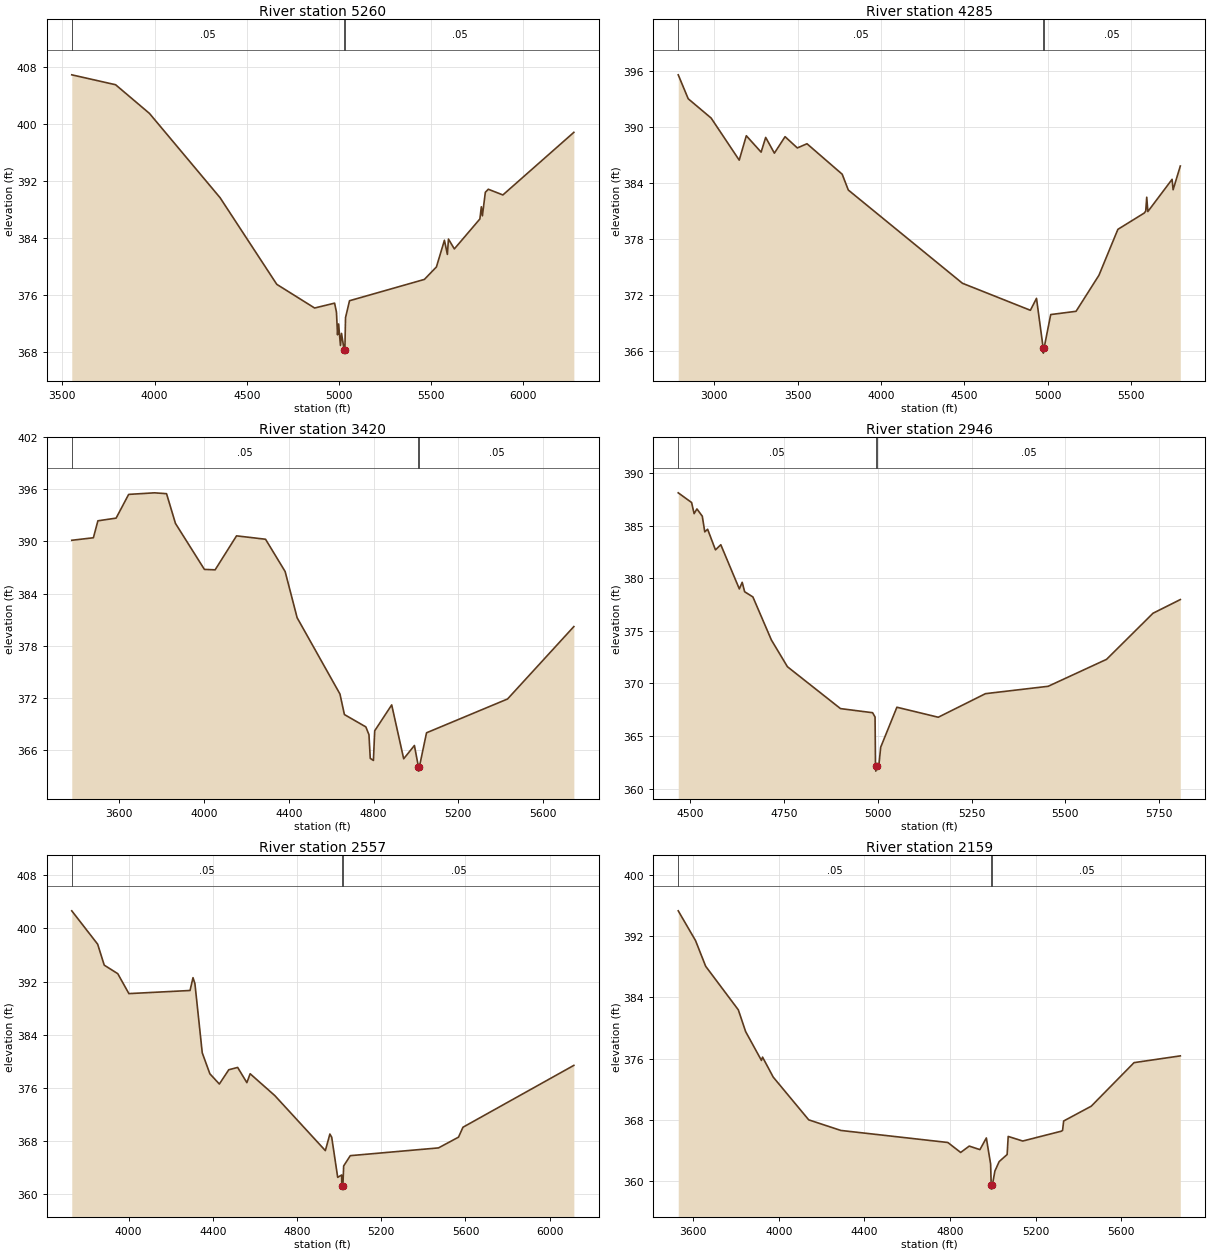
Type RM Length L Ch R = 1 ,5260    ,975,975,975
BEGIN DESCRIPTION:
Mapping XS 346f280a
END DESCRIPTION:
XS GIS Cut Line= 5
      2670957.23      6860018.87      2669680.22      6860737.62
       2668926.6       6861156.3      2668807.98      6861260.97
      2668780.19      6861497.15
#Sta/Elev= 30
  3550.9  406.93  3788.6  405.54  3972.2  401.52  4355.2   389.7    4663  377.54
  4868.2  374.22  4976.6   374.9  4986.7  373.64  4992.5  370.46  4998.3  371.98
  5008.4  368.96  5014.2  370.66    5028  368.39  5028.4  367.89  5032.4  368.39
  5035.9  372.87  5057.6  375.24  5463.7  378.23  5528.9  379.98  5572.4  383.72
  5588.4  381.74  5594.2  383.89  5626.2  382.51  5764.7  386.71  5772.6  388.42
  5778.3  387.15  5794.3  390.45  5810.4  390.88  5889.5  390.08  6274.4  398.86
#Mann= 3 ,-1 , 0
  3550.9     .05       0    5028     .04       0  5032.4     .05       0
Bank Sta=5028,5032.4
XS Rating Curve= 0 ,0
Exp/Cntr=0.3,0.1

Type RM Length L Ch R = 1 ,4285    ,865,865,865
BEGIN DESCRIPTION:
Kings Creek 32_1 5.0
END DESCRIPTION:
XS GIS Cut Line= 3
        2671020.      6858853.57        2669126.        6860011.
      2668676.02      6860660.98
#Sta/Elev= 30
  2784.4  395.63  2844.2  393.06  2981.6  390.99    3150  386.47  3192.6  389.09
  3281.3  387.33  3308.7  388.91  3360.9  387.22  3424.9  388.99  3498.4  387.78
  3556.4  388.23  3767.4  384.96  3804.1  383.26  4488.4  373.25  4895.7  370.35
  4932.4  371.63  4972.8  366.25  4973.2  365.75  4977.3  366.25  5017.6  369.89
  5169.6  370.24  5306.8  374.11  5420.3  379.04  5578.4  380.79  5587.2     381
  5593.3  382.49    5600  380.95  5745.3  384.41  5751.4  383.29  5794.6  385.84
#Mann= 3 ,-1 , 0
  2784.4     .05       0  4972.8     .05       0  4977.3     .05       0
Bank Sta=4972.8,4977.3
XS Rating Curve= 0 ,0
Exp/Cntr=0.3,0.1

Type RM Length L Ch R = 1 ,3420    ,474,474,474
BEGIN DESCRIPTION:
Kings Creek 32_1 3.0
END DESCRIPTION:
XS GIS Cut Line= 3
      2670057.01      6858379.09        2668726.        6859311.
      2668165.98       6859802.6
#Sta/Elev= 30
  3375.2  390.14  3477.3  390.43  3498.5  392.38  3584.5  392.69  3643.8  395.42
  3765.9   395.6  3822.6   395.5  3864.7  392.08  4001.3  386.79  4051.9  386.74
    4153  390.65  4289.9  390.26  4382.3  386.55    4439  381.23  4641.2  372.45
  4662.2  370.09  4763.3  368.67  4778.1  367.77  4784.2  365.05  4799.1  364.81
  4805.2  368.22  4885.4   371.2    4942     365  4992.6  366.53  5011.5  364.08
  5011.9  363.58  5016.1  364.08  5049.8  367.99  5432.3  371.88  5745.2  380.21
#Mann= 3 ,-1 , 0
  3375.2     .05       0  5011.5     .04       0  5016.1     .05       0
Bank Sta=5011.5,5016.1
XS Rating Curve= 0 ,0
Exp/Cntr=0.3,0.1

Type RM Length L Ch R = 1 ,2946    ,389,389,389
BEGIN DESCRIPTION:
Kings Creek 32_1 2.0
END DESCRIPTION:
XS GIS Cut Line= 3
      2668926.01      6858560.99        2668526.        6858911.
      2668126.02      6859610.96
#Sta/Elev= 30
  4468.5  388.11  4504.1  387.19  4510.8  386.13  4518.3  386.58  4532.6  385.89
  4539.2   384.4  4546.8  384.65  4567.7  382.69  4581.9  383.18  4631.3  378.98
  4638.9  379.61  4645.5  378.71  4667.4  378.22  4716.7  374.13  4759.4  371.59
  4900.8  367.61  4986.3  367.22  4992.9  366.81  4994.1  362.17  4994.8  361.67
  4999.3  362.17  5002.9  362.17  5007.9  363.94  5051.1  367.74  5161.3  366.79
  5287.2  369.03  5454.2  369.73  5609.7  372.29  5733.5  376.67  5806.2  377.97
#Mann= 3 ,-1 , 0
  4468.5     .05       0  4994.1     .04       0  4999.3     .05       0
Bank Sta=4994.1,4999.3
XS Rating Curve= 0 ,0
Exp/Cntr=0.3,0.1

Type RM Length L Ch R = 1 ,2557    ,398,398,398
BEGIN DESCRIPTION:
Mapping XS 604ffa9c
END DESCRIPTION:
XS GIS Cut Line= 3
      2668961.47      6857506.88      2668312.54      6858609.35
       2667977.6      6859663.02
#Sta/Elev= 30
  3729.9  402.66  3852.8  397.64  3884.1  394.48  3948.5  393.19  4001.3  390.19
  4291.7  390.66  4305.8  392.59  4314.9  391.69  4349.7  381.27  4385.8  378.12
  4430.9  376.57  4475.7  378.72  4517.9  379.07  4561.6  376.78  4577.2  378.12
  4694.4  374.83  4934.5  366.54    4956  369.04  4964.7  368.55  4993.1  362.51
  5011.7  362.87  5012.6  361.24  5013.3  360.74  5017.8  361.24  5021.4  364.23
  5052.9  365.78  5471.9  366.95    5567  368.57    5588  370.06  6114.8  379.38
#Mann= 3 ,-1 , 0
  3729.9     .05       0  5012.6     .04       0  5017.8     .05       0
Bank Sta=5012.6,5017.8
XS Rating Curve= 0 ,0
Exp/Cntr=0.3,0.1

Type RM Length L Ch R = 1 ,2159    ,39,39,39
BEGIN DESCRIPTION:
Mapping XS ae694ddf
END DESCRIPTION:
XS GIS Cut Line= 5
      2668623.94      6857611.49      2667939.06      6857801.59
      2667933.85       6858556.8      2667907.81      6859228.68
      2667941.67      6859434.43
#Sta/Elev= 30
  3529.8  395.28  3610.7   391.4  3658.1  388.05  3810.7  382.37    3845  379.53
  3918.7  375.78  3923.9  376.21  3973.9   373.6  4139.8  368.03    4290  366.65
    4790  365.08    4850  363.78    4890  364.61    4940  364.15    4970  365.67
    4990  362.27  4992.8   359.5  4993.5     359    4998   359.5    5010  361.36
    5030  362.59  5067.2  363.51  5072.2  365.87  5140.1  365.27  5320.2  366.55
  5326.4  366.66  5331.4  367.88  5460.3  369.81  5660.5  375.49  5876.7  376.37
#Mann= 3 ,-1 , 0
  3529.8     .05       0  4992.8     .03       0    4998     .05       0
Bank Sta=4992.8,4998
XS Rating Curve= 0 ,0
Exp/Cntr=0.3,0.1

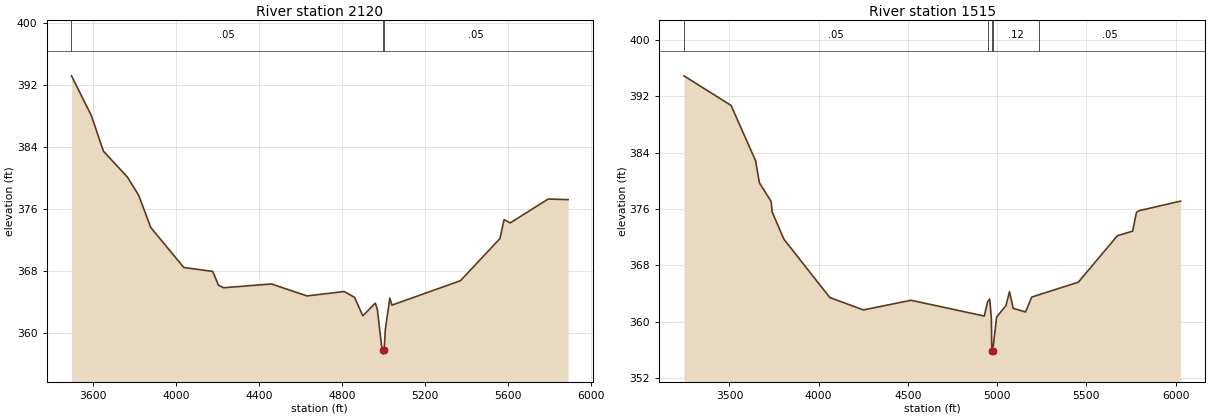
Type RM Length L Ch R = 1 ,2120    ,605,605,605
BEGIN DESCRIPTION:
Mapping XS 5a4286a5
END DESCRIPTION:
XS GIS Cut Line= 5
      2668582.25       6857546.4      2667907.81      6857767.74
      2667894.79      6858572.43      2667873.95      6859252.11
      2667915.62      6859444.83
#Sta/Elev= 30
  3496.8  393.22  3592.3  388.08  3650.7  383.47  3766.5  380.11  3820.3  377.77
  3878.7  373.59  4037.8  368.42    4177  367.91    4205  366.11  4229.9   365.8
  4459.9  366.29  4631.2  364.74    4810  365.31    4860  364.56    4900  362.16
    4960  363.81    4970  362.99    4990  358.31  4997.4  357.71  4998.1  357.21
  5002.6  357.71  5008.2  360.37    5030  364.46    5040  363.55  5370.2  366.71
  5560.3  372.16  5580.3  374.61  5610.3  374.19  5792.6  377.28  5888.6   377.2
#Mann= 3 ,-1 , 0
  3496.8     .05       0  4997.4     .03       0  5002.6     .05       0
Bank Sta=4997.4,5002.6
XS Rating Curve= 0 ,0
Exp/Cntr=0.3,0.1

Type RM Length L Ch R = 1 ,1515    ,0,0,0
BEGIN DESCRIPTION:
Kings Creek 32_1 1.0
END DESCRIPTION:
XS GIS Cut Line= 5
      2668207.86      6857025.38      2667347.91      6858288.57
      2667305.79      6858511.51      2667295.83      6858689.61
      2667875.99      6859310.99
#Sta/Elev= 30
    3245  394.89  3508.9  390.69  3646.5  382.84  3667.5  379.73  3733.3  377.08
  3739.4  375.57  3805.1  371.72  4062.6  363.44  4251.1  361.69  4517.4  363.06
  4928.2  360.82  4946.8  362.85  4958.8  363.23  4967.9  360.46  4970.3  355.92
  4971.1  355.42  4975.6  355.92  4997.2  360.67  5049.6   362.3  5069.6  364.27
  5090.2  361.91  5159.7   361.4  5193.9  363.51  5234.8  363.84  5455.2  365.62
  5674.6  372.22  5759.6  372.86  5781.1  375.52  5795.2  375.76  6028.5  377.12
#Mann= 5 ,-1 , 0
    3245     .05       0  4946.8     .12       0  4970.3     .07       0
  4975.6     .12       0  5234.8     .05       0
Bank Sta=4970.3,4975.6
XS Rating Curve= 0 ,0
Exp/Cntr=0.3,0.1

Chan Stop Cuts=-1
Use User Specified Reach Order=0
Composite Channel Slope=5