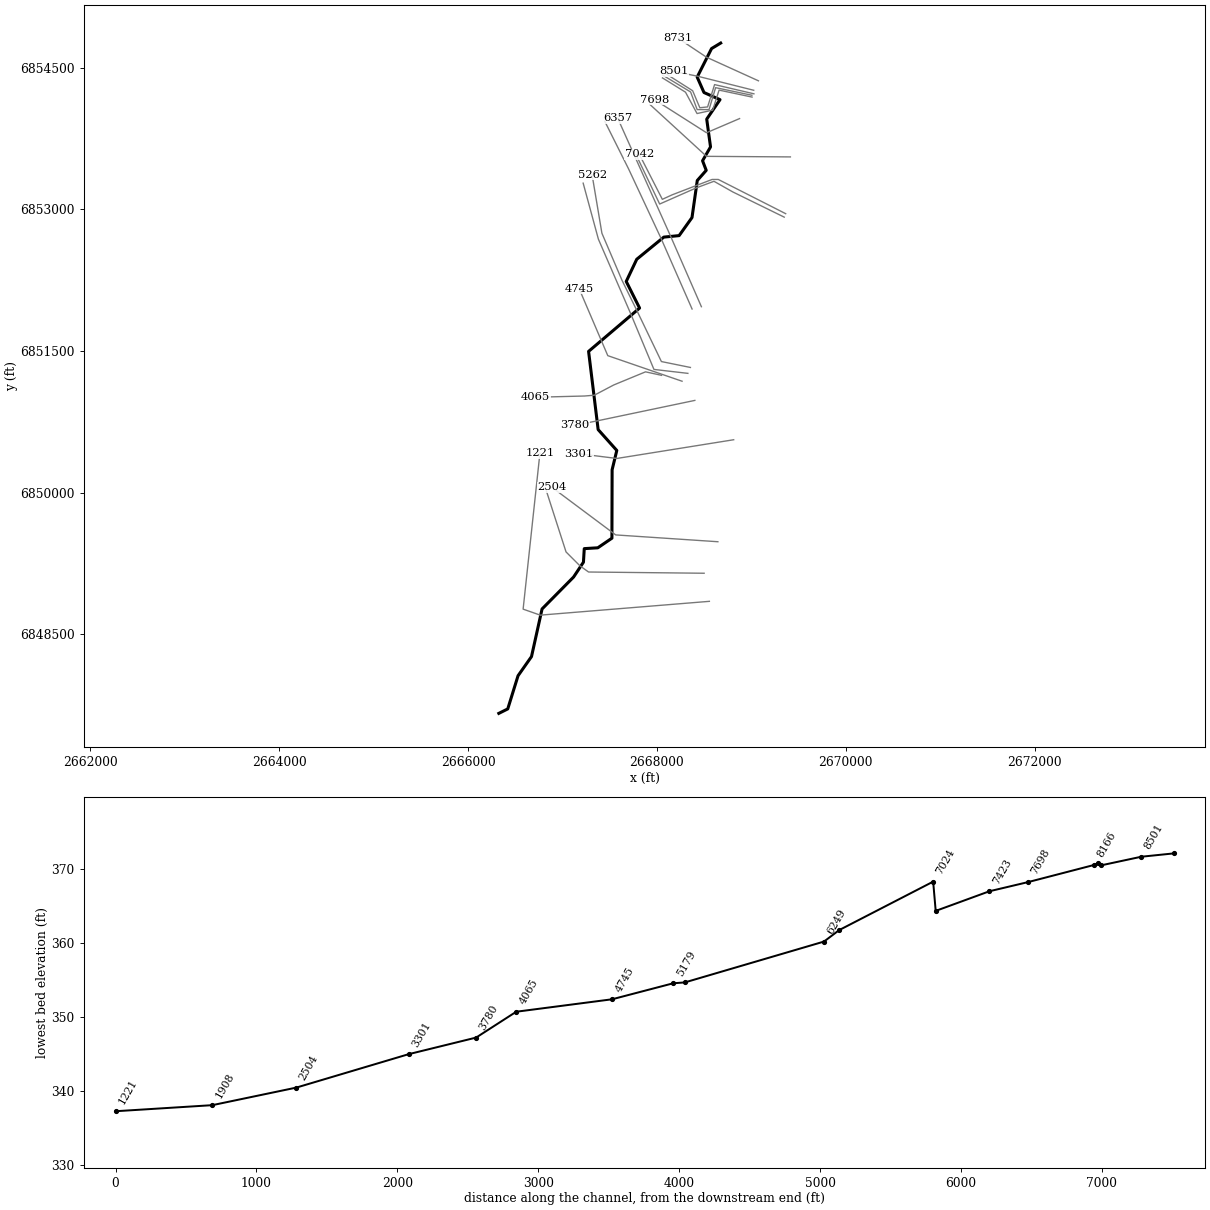
--- Kings Creek 32_2.prj (project) ---

Proj Title=Kings Creek 32_2 Base Level Engineering
Current Plan=p01
Default Exp/Contr=0.3,0.1
English Units
Geom File=g01
Flow File=f01
Plan File=p01
Y Axis Title=Elevation
X Axis Title(PF)=Main Channel Distance
X Axis Title(XS)=Station
BEGIN DESCRIPTION:
Kings Creek 32_2
END DESCRIPTION:
DSS Export Rating Curves= 0
DSS Export Rating Curve Sorted= 0
DSS Export Volume Flow Curves= 0
DXF OffsetX= 0
DXF OffsetY= 0
DXF ScaleX= 1
DXF ScaleY= 10

--- Kings Creek 32_2.p01 (plan) ---

Plan Title=Multiple Run
Short Identifier=Multiple
Geom File=g01
Flow File=f01
Subcritical Flow
K Sum by GR= 0
Std Step Tol= 0.01
Critical Tol= 0.01
Num of Std Step Trials= 20
Max Error Tol= 0.3
Flow Tol Ratio= 0.001
Split Flow NTrial= 30
Split Flow Tol= 0.02
Split Flow Ratio= 0.02
Log Output Level= 0
Friction Slope Method= 1
Unsteady Friction Slope Method= 2
Unsteady Bridges Friction Slope Method= 1
Parabolic Critical Depth
Global Vel Dist=  1 , 1 , 1
Global Log Level= 0
CheckData=True
Encroach Param= -1, 0, 0, 0
BEGIN DESCRIPTION:
Multiple Run
END DESCRIPTION:

--- Kings Creek 32_2.f01 (steady flow) ---

Flow Title=Multiple
Number of Profiles=7
Profile Names=10-year,25-year,50-year,1pct_min,100-year,1pct_plu,500-year
River Rch & RM= Kings Creek 32_2,Reach-1,8731
     586     783     941     561    1120    2235    1585
Boundary for River Rch & Prof#=Kings Creek 32_2,Reach-1,1
Up Type=0
Dn Type=3
Dn Slope=0.005
Boundary for River Rch & Prof#=Kings Creek 32_2,Reach-1,2
Up Type=0
Dn Type=3
Dn Slope=0.005
Boundary for River Rch & Prof#=Kings Creek 32_2,Reach-1,3
Up Type=0
Dn Type=3
Dn Slope=0.005
Boundary for River Rch & Prof#=Kings Creek 32_2,Reach-1,4
Up Type=0
Dn Type=3
Dn Slope=0.005
Boundary for River Rch & Prof#=Kings Creek 32_2,Reach-1,5
Up Type=0
Dn Type=3
Dn Slope=0.005
Boundary for River Rch & Prof#=Kings Creek 32_2,Reach-1,6
Up Type=0
Dn Type=3
Dn Slope=0.005
Boundary for River Rch & Prof#=Kings Creek 32_2,Reach-1,7
Up Type=0
Dn Type=3
Dn Slope=0.005

--- Kings Creek 32_2.g01 (geometry) ---

Geom Title=Existing Conditions
Program Version=4.10

River Reach=Kings Creek 32_2,Reach-1
Reach XY= 30
        2668676.        6854761.      2668579.43      6854702.66
      2668427.08      6854400.45      2668499.06      6854237.15
      2668668.82      6854161.33      2668528.06      6853955.14
      2668568.47      6853660.99      2668484.07      6853514.31
      2668522.83      6853412.65      2668428.07      6853305.14
      2668372.18      6852912.58      2668235.82      6852721.47
      2668073.55      6852705.53      2667786.77       6852470.7
      2667675.58        6852236.      2667816.96        6851954.
      2667276.91      6851495.06      2667378.07      6850666.86
      2667575.64      6850445.84      2667526.07      6850240.97
      2667524.02      6849516.67      2667374.44      6849414.76
      2667231.01      6849405.99      2667222.44      6849262.48
      2667117.84      6849104.95      2666784.14      6848767.06
      2666672.24      6848262.56      2666529.62       6848059.5
      2666420.67      6847708.34        2666326.        6847661.

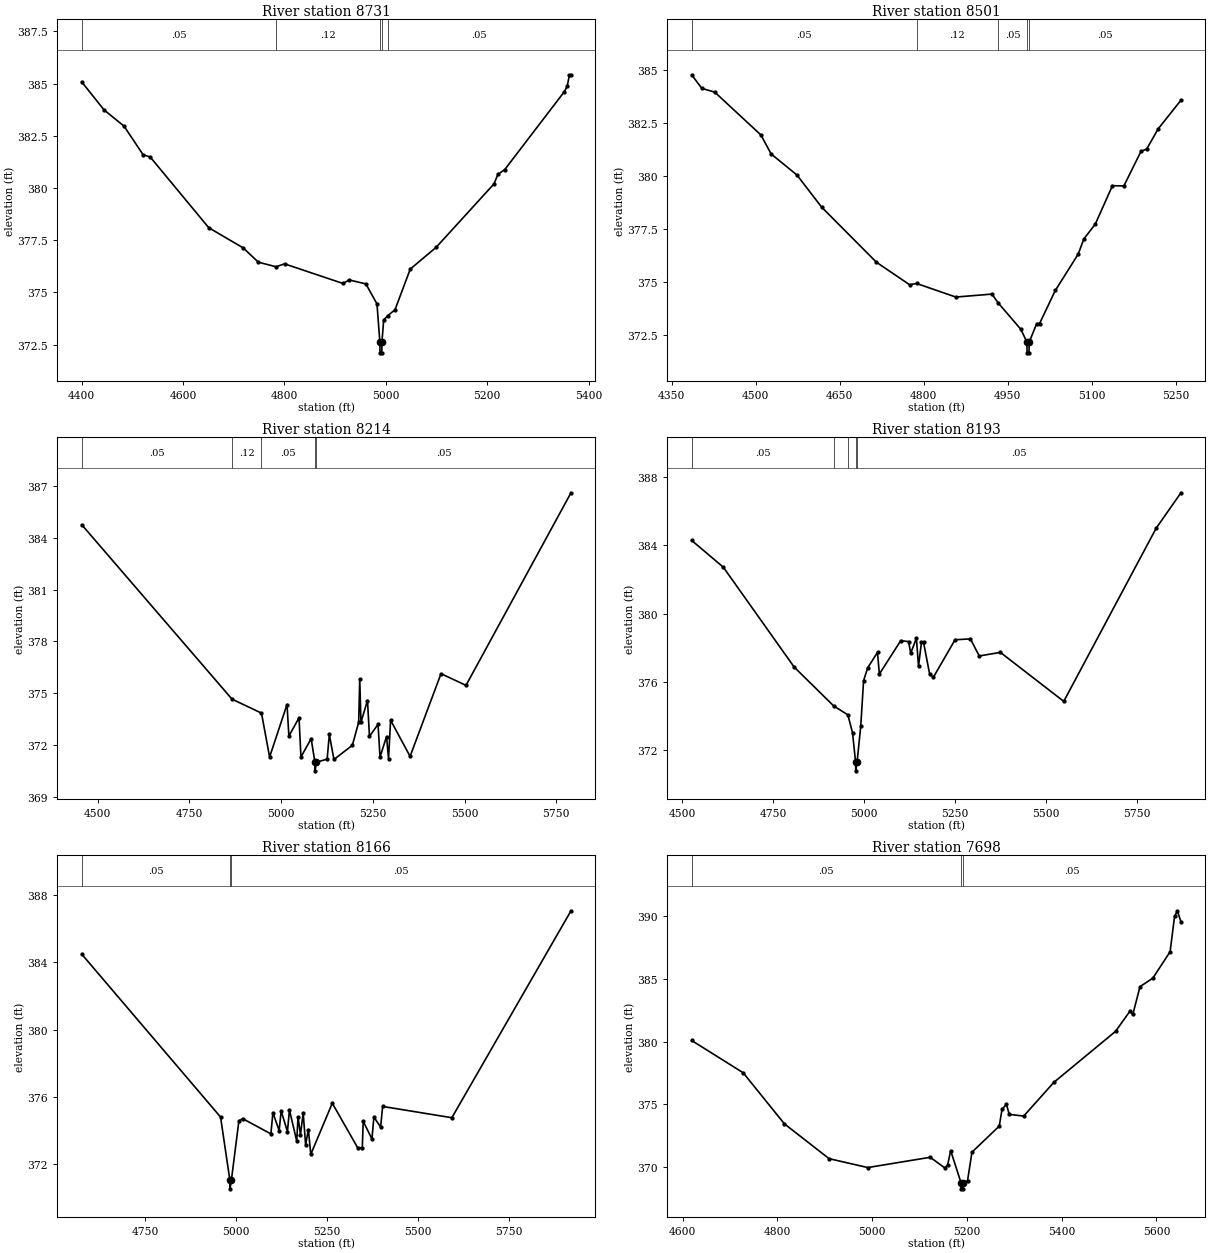
Type RM Length L Ch R = 1 ,8731    ,230,230,230
BEGIN DESCRIPTION:
Kings Creek 32_2 16.0
END DESCRIPTION:
XS GIS Cut Line= 3
      2669076.04      6854360.98        2668526.        6854611.
      2668226.04      6854810.97
#Sta/Elev= 30
  4400.3  385.08  4444.3  383.74  4483.8  382.96  4521.2   381.6  4535.5  381.48
  4650.8   378.1  4718.9  377.13  4748.6  376.45  4783.5  376.23  4800.2  376.37
  4915.5  375.43  4927.6   375.6  4960.6  375.41  4982.5  374.45  4988.2  372.61
  4988.5  372.11    4992  372.11  4992.2  372.61  4995.7  373.68  5003.7  373.89
    5018  374.17  5048.1  376.12  5099.1  377.16  5213.3   380.2  5220.8  380.65
  5234.3  380.88  5351.5   384.6  5357.5  384.87    5362  385.42    5365  385.42
#Mann= 5 ,-1 , 0
  4400.3     .05       0  4783.5     .12       0  4988.2     .07       0
  4992.2     .12       0  5003.7     .05       0
Bank Sta=4988.2,4992.2
XS Rating Curve= 0 ,0
Exp/Cntr=0.3,0.1

Type RM Length L Ch R = 1 ,8501    ,287,287,287
BEGIN DESCRIPTION:
Kings Creek 32_2 15.0
END DESCRIPTION:
XS GIS Cut Line= 3
      2669026.03      6854260.99        2668426.        6854411.
      2668176.04      6854460.99
#Sta/Elev= 30
  4385.6  384.77  4403.7  384.13  4426.9  383.95  4509.3  381.93  4527.4  381.04
  4573.7  380.04  4617.6  378.53  4715.5  375.93  4774.7  374.87  4787.1  374.93
  4857.2  374.29  4921.6  374.43  4932.9  374.01  4973.2  372.77  4984.1  372.16
  4984.3  371.66  4987.8  371.66  4988.1  372.16  5001.5  373.04  5006.6  373.04
  5034.7   374.6  5075.5  376.31  5085.7  377.03  5106.1  377.73  5136.7  379.54
  5157.1  379.53  5187.7  381.16  5197.9  381.27  5218.3  382.22    5259  383.57
#Mann= 5 ,-1 , 0
  4385.6     .05       0  4787.1     .12       0  4932.9     .05       0
  4984.1     .03       0  4988.1     .05       0
Bank Sta=4984.1,4988.1
XS Rating Curve= 0 ,0
Exp/Cntr=0.3,0.1

Type RM Length L Ch R = 1 ,8214    ,21,21,21
BEGIN DESCRIPTION:
Mapping XS 9bd93435
END DESCRIPTION:
XS GIS Cut Line= 6
      2669028.08      6854223.39      2668611.38      6854321.06
      2668537.59      6854084.51      2668455.13      6854075.83
      2668379.17      6854255.95      2668089.72      6854439.56
#Sta/Elev= 30
  4456.3  384.78  4866.1  374.65  4946.4  373.84  4968.5  371.29  5015.9  374.34
  5021.1  372.51  5048.7  373.57  5053.9  371.29  5081.7  372.36    5092  370.99
  5092.3  370.49    5096  370.99  5125.3  371.17  5131.3   372.6  5143.8  371.15
    5194  371.97  5211.3  373.31  5214.2  375.82  5217.5  373.31  5235.3  374.57
  5240.7  372.49    5264  373.19  5269.5  371.29  5287.2  372.48  5292.7  371.19
  5298.3  373.43  5351.4  371.33  5435.7  376.13  5503.8  375.45    5790  386.63
#Mann= 5 ,-1 , 0
  4456.3     .05       0  4866.1     .12       0  4946.4     .05       0
    5092     .03       0    5096     .05       0
Bank Sta=5092,5096
XS Rating Curve= 0 ,0
Exp/Cntr=0.3,0.1

Type RM Length L Ch R = 1 ,8193    ,27,27,27
BEGIN DESCRIPTION:
Mapping XS 8718f840
END DESCRIPTION:
XS GIS Cut Line= 6
      2669006.38       6854208.2      2668622.23      6854288.51
      2668552.78       6854056.3      2668426.92       6854056.3
      2668357.47      6854242.93      2668062.37      6854420.86
#Sta/Elev= 30
  4526.2  384.29  4613.3  382.72  4808.1  376.87    4917  374.59  4955.8  374.07
  4968.6  373.02  4977.1  371.29  4977.4  370.79  4981.1  371.29  4991.2   373.4
    4999  376.07  5010.4  376.83  5037.3  377.73  5042.4  376.46  5101.3  378.42
  5122.8  378.36  5128.6  377.68  5144.3  378.56  5150.1  376.92  5158.2  378.33
  5163.8  378.33  5180.6  376.47  5190.6  376.26  5250.6  378.47  5292.8  378.52
  5317.1  377.52  5375.2  377.73  5549.5  374.86  5803.8  385.01  5871.8  387.08
#Mann= 5 ,-1 , 0
  4526.2     .05       0    4917     .12       0  4955.8     .05       0
  4977.1     .03       0  4981.1     .05       0
Bank Sta=4977.1,4981.1
XS Rating Curve= 0 ,0
Exp/Cntr=0.3,0.1

Type RM Length L Ch R = 1 ,8166    ,468,468,468
BEGIN DESCRIPTION:
Mapping XS 276d777f
END DESCRIPTION:
XS GIS Cut Line= 6
      2669008.47      6854188.69      2668659.12      6854262.46
      2668591.11      6854050.58      2668425.66      6854014.42
      2668303.22      6854240.76      2668059.47      6854391.76
#Sta/Elev= 30
  4574.9  384.48  4956.7  374.81  4982.4  371.05  4982.6  370.55  4986.4  371.05
    5007  374.57  5017.1  374.72  5095.1  373.81  5100.6  375.07  5117.8  374.01
  5123.3  375.17  5140.6  373.95  5146.1  375.23  5166.2  373.38  5169.7  374.83
  5176.4  373.76  5183.9  375.05  5190.6  373.16  5198.1  374.07  5204.8   372.6
  5263.9  375.63  5333.9  372.98  5346.4  372.99  5348.9  374.56  5372.9  373.51
  5378.3  374.81  5396.8  374.21  5402.3  375.44  5592.6  374.77  5920.2  387.05
#Mann= 3 ,-1 , 0
  4574.9     .05       0  4982.4     .03       0  4986.4     .05       0
Bank Sta=4982.4,4986.4
XS Rating Curve= 0 ,0
Exp/Cntr=0.3,0.1

Type RM Length L Ch R = 1 ,7698    ,275,275,275
BEGIN DESCRIPTION:
Kings Creek 32_2 12.0
END DESCRIPTION:
XS GIS Cut Line= 3
      2668875.99        6853961.        2668526.        6853811.
        2667976.        6854161.
#Sta/Elev= 30
  4619.1  380.09  4727.9  377.51  4814.9  373.43  4909.2  370.65  4990.8  369.94
  5122.6  370.76  5153.1  369.92  5159.1  370.11  5165.8  371.29  5187.5  368.74
  5187.8  368.24  5191.3  368.24  5191.5  368.74  5201.4  368.89  5210.7  371.17
  5268.3  373.25  5274.2  374.59  5283.5  374.99  5289.4  374.19  5319.9  374.05
  5383.4  376.74  5513.8  380.82  5544.3  382.44  5550.2  382.17  5565.4  384.39
  5592.5  385.07  5628.9  387.18  5638.3     390  5644.2  390.45  5651.8  389.58
#Mann= 3 ,-1 , 0
  4619.1     .05       0  5187.5     .04       0  5191.5     .05       0
Bank Sta=5187.5,5191.5
XS Rating Curve= 0 ,0
Exp/Cntr=0.3,0.1

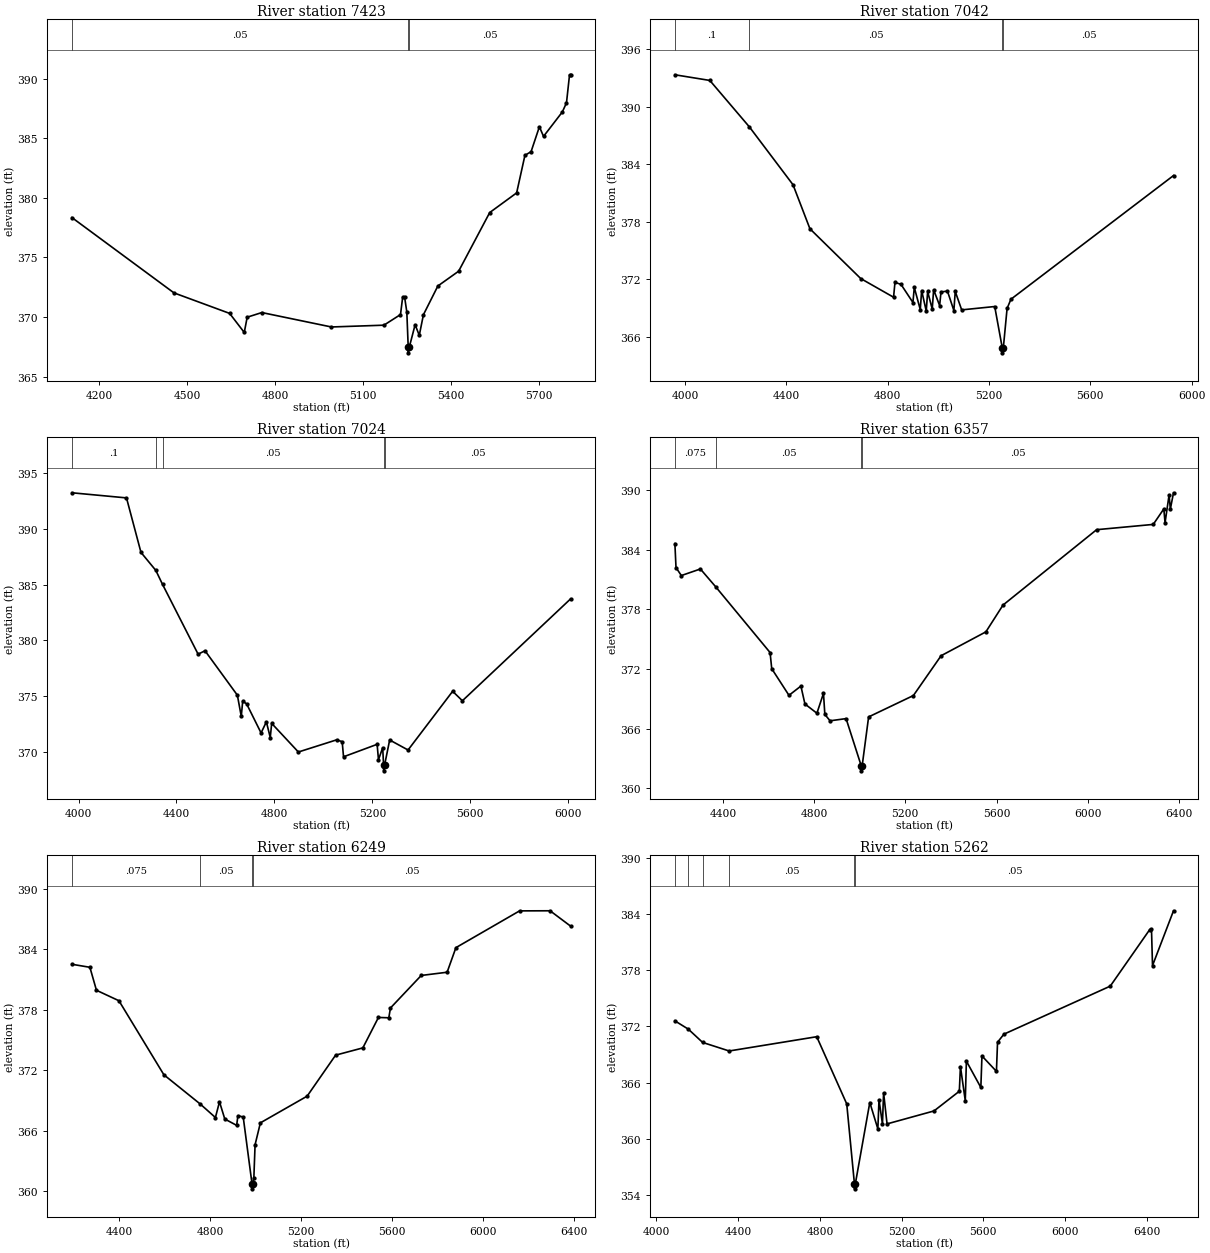
Type RM Length L Ch R = 1 ,7423    ,381,381,381
BEGIN DESCRIPTION:
Kings Creek 32_2 11.0
END DESCRIPTION:
XS GIS Cut Line= 3
      2669414.37        6853555.        2668526.        6853561.
      2667926.03      6854110.98
#Sta/Elev= 30
  4106.5  378.35  4454.9  372.03  4644.9  370.31  4694.9  368.71  4704.9  369.99
  4754.9  370.38  4992.4  369.17  5171.6  369.32  5228.3  370.21  5235.7  371.67
  5242.5  371.65  5249.9  370.42  5254.6   367.5  5254.9     367  5258.6   367.5
  5278.2  369.36  5292.4  368.47  5306.6   370.2  5355.9  372.61  5426.8  373.85
  5532.9  378.77  5624.8  380.42  5653.1  383.57  5674.1  383.88  5702.5  385.97
  5716.6  385.16  5780.8  387.21    5795  387.98  5805.4  390.33  5808.8  390.33
#Mann= 3 ,-1 , 0
  4106.5     .05       0  5254.6     .04       0  5258.6     .05       0
Bank Sta=5254.6,5258.6
XS Rating Curve= 0 ,0
Exp/Cntr=0.3,0.1

Type RM Length L Ch R = 1 ,7042    ,18,18,18
BEGIN DESCRIPTION:
Mapping XS cec43cef
END DESCRIPTION:
XS GIS Cut Line= 6
      2669364.43      6852953.86      2668650.44      6853316.28
      2668585.34      6853316.28      2668162.16      6853153.52
      2668057.99      6853105.78      2667814.93      6853581.05
#Sta/Elev= 30
  3960.6  393.35  4098.4  392.76  4254.7  387.91  4426.8  381.88  4493.5  377.29
  4693.9   372.1  4823.6  370.15  4829.1  371.69  4852.7   371.5    4900   369.6
  4905.4  371.17    4929  368.86  4934.4  370.84  4952.6  368.71  4958.1  370.75
  4976.2  368.91  4981.7  370.93  5005.4  369.28  5010.8   370.7  5036.2  370.79
  5061.6  368.76    5067  370.75  5092.4  368.83  5222.8  369.18  5252.7  364.85
  5252.9  364.35  5256.7  364.85  5271.6  368.98  5286.8  369.94  5928.4  382.84
#Mann= 4 ,-1 , 0
  3960.6      .1       0  4254.7     .05       0  5252.7     .05       0
  5256.7     .05       0
Bank Sta=5252.7,5256.7
XS Rating Curve= 0 ,0
Exp/Cntr=0.3,0.1

Type RM Length L Ch R = 1 ,7024    ,667,667,667
BEGIN DESCRIPTION:
Mapping XS 115e60f6
END DESCRIPTION:
XS GIS Cut Line= 6
      2669349.25      6852916.97      2668804.52       6853183.9
      2668604.87      6853296.75      2668418.24      6853227.31
      2668029.78      6853055.87      2667780.79       6853575.5
#Sta/Elev= 30
    3973  393.26  4195.9   392.8    4255  387.91  4315.7  386.29    4343  385.04
  4488.4  378.77  4516.5  379.08  4648.7  375.09  4664.6  373.19  4670.4  374.54
  4686.3  374.32  4745.5   371.7  4767.1   372.7    4783  371.29  4788.8  372.56
  4897.8  369.99  5053.8  371.08  5076.7  370.92  5082.2  369.56  5219.4  370.68
  5224.9   369.3  5242.2  370.38  5245.7   368.8    5246   368.3  5249.7   368.8
  5270.6  371.07  5345.7  370.17  5527.8  375.44  5567.6  374.59  6009.2  383.73
#Mann= 5 ,-1 , 0
    3973      .1       0  4315.7    .075       0    4343     .05       0
  5245.7     .05       0  5249.7     .05       0
Bank Sta=5245.7,5249.7
XS Rating Curve= 0 ,0
Exp/Cntr=0.3,0.1

Type RM Length L Ch R = 1 ,6357    ,108,108,108
BEGIN DESCRIPTION:
Mapping XS df8bc079
END DESCRIPTION:
XS GIS Cut Line= 3
      2668471.64      6851968.51      2668142.34      6852722.29
      2667584.43      6853966.67
#Sta/Elev= 30
  4189.7   384.6  4194.6  382.19    4218  381.39  4301.5  382.05  4368.6  380.26
  4607.1  373.65  4614.3  372.03  4689.9  369.35  4742.2  370.28  4759.9  368.48
  4812.4  367.55  4841.2  369.55  4847.2  367.43  4870.1  366.79  4940.3  367.01
  5006.8  362.26  5007.1  361.76  5010.8  362.26  5039.1  367.18  5235.5  369.33
  5356.9  373.33  5553.3  375.73  5628.3  378.42  6038.9     386  6287.1  386.53
  6333.5  388.09  6338.9   386.7  6356.6  389.49  6362.1  388.07    6376  389.71
#Mann= 4 ,-1 , 0
  4189.7    .075       0  4368.6     .05       0  5006.8     .04       0
  5010.8     .05       0
Bank Sta=5006.8,5010.8
XS Rating Curve= 0 ,0
Exp/Cntr=0.3,0.1

Type RM Length L Ch R = 1 ,6249    ,987,987,987
BEGIN DESCRIPTION:
Mapping XS 526e1ebb
END DESCRIPTION:
XS GIS Cut Line= 4
        2668373.      6851944.07      2668043.14      6852694.94
      2667700.25      6853428.44      2667448.53       6853931.9
#Sta/Elev= 30
  4192.1   382.5  4271.2   382.2    4300  379.92  4398.9  378.88  4596.6  371.53
  4756.3  368.63  4823.2  367.29  4841.1  368.85  4864.4  367.14  4916.6  366.51
  4922.1  367.47  4945.4  367.34  4984.1  360.71  4984.3  360.21  4988.1  360.71
  4992.1  361.25  4997.6  364.59  5020.9  366.76  5226.5  369.41  5351.7  373.48
  5471.5   374.2    5540  377.22  5585.7  377.19  5592.9  378.16  5728.3  381.39
  5842.1  381.71  5880.7  384.15  6160.7   387.8  6294.9  387.81  6384.8  386.29
#Mann= 4 ,-1 , 0
  4192.1    .075       0  4756.3     .05       0  4984.1     .05       0
  4988.1     .05       0
Bank Sta=4984.1,4988.1
XS Rating Curve= 0 ,0
Exp/Cntr=0.3,0.1

Type RM Length L Ch R = 1 ,5262    ,83,83,83
BEGIN DESCRIPTION:
Mapping XS 5a8091d7
END DESCRIPTION:
XS GIS Cut Line= 6
      2668355.37      6851324.94      2668048.13      6851387.43
      2667787.71      6851929.09      2667631.46       6852246.8
      2667417.92       6852746.8       2667313.8      6853366.32
#Sta/Elev= 30
  4090.3   372.6  4155.8  371.72  4226.1   370.3  4355.9  369.39  4784.5  370.91
  4931.4  363.75  4969.2   355.2  4969.4   354.7  4973.2   355.2  5044.3   363.9
  5083.7  361.09  5089.3  364.18  5106.2  361.62  5111.8  364.94  5128.7  361.62
  5358.5     363  5482.5   365.1  5487.9  367.73  5511.6  364.09    5517  368.31
  5587.8   365.5  5593.2  368.86  5664.1  367.22  5669.5  370.32  5700.6  371.18
  6221.2   376.3  6413.9  382.31    6423  382.38    6428  378.49  6530.8  384.33
#Mann= 6 ,-1 , 0
  4090.3    .075       0  4155.8     .05       0  4226.1    .075       0
  4355.9     .05       0  4969.2     .03       0  4973.2     .05       0
Bank Sta=4969.2,4973.2
XS Rating Curve= 0 ,0
Exp/Cntr=0.3,0.1

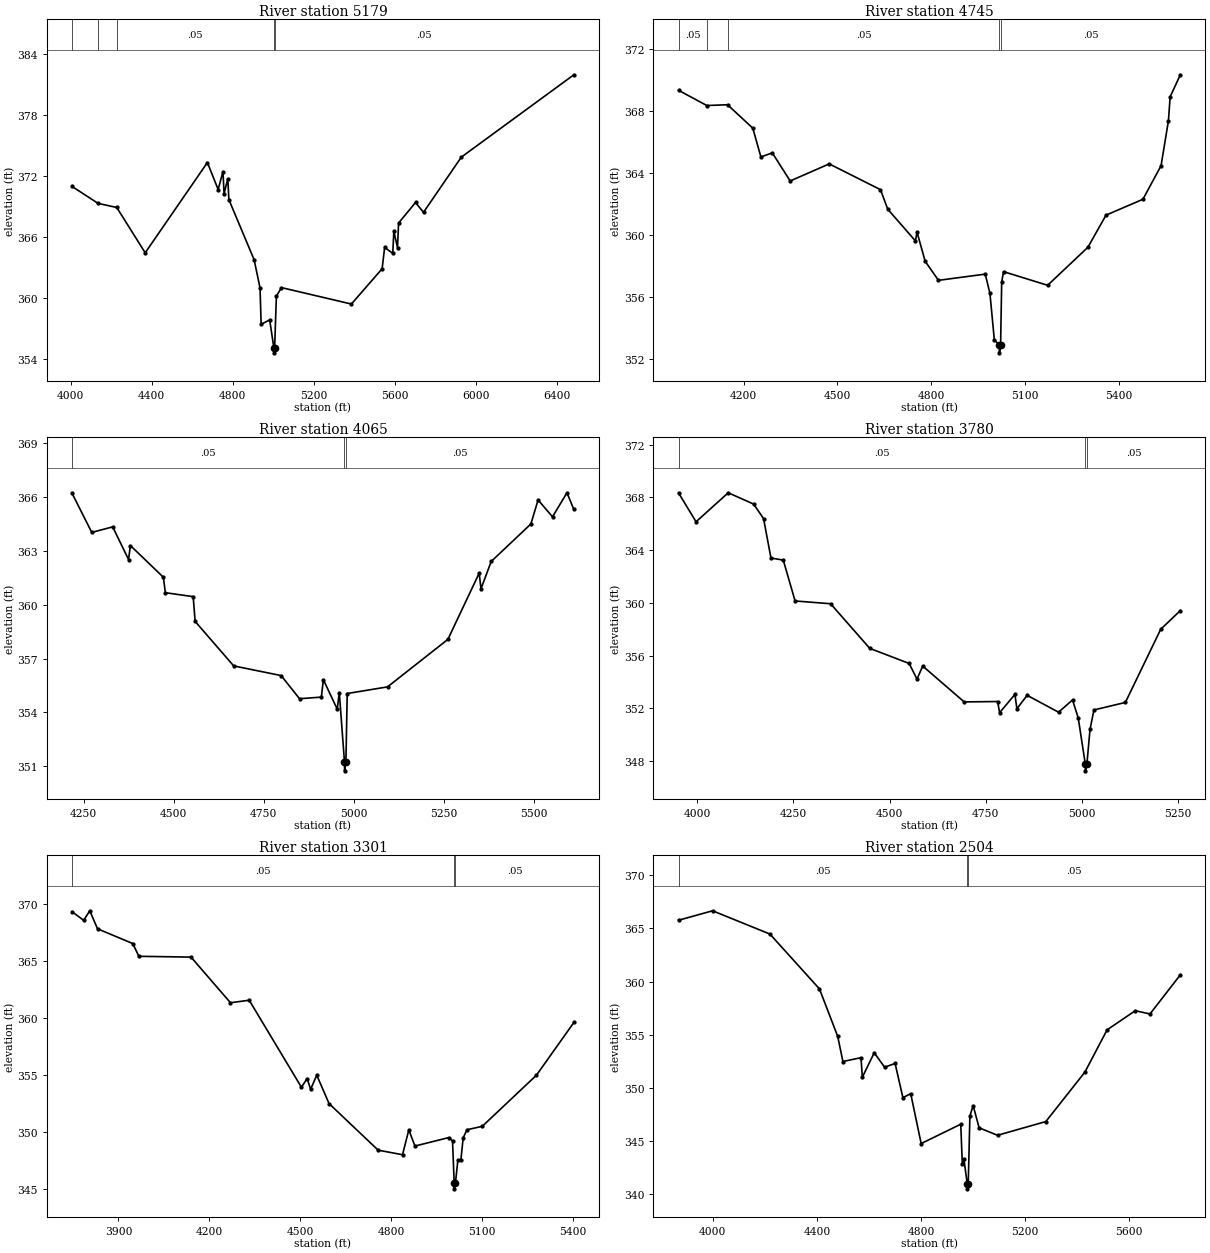
Type RM Length L Ch R = 1 ,5179    ,434,434,434
BEGIN DESCRIPTION:
Mapping XS 2850b67b
END DESCRIPTION:
XS GIS Cut Line= 5
      2668328.55      6851262.42      2667969.13      6851304.09
      2667719.13      6851903.05      2667380.59       6852684.3
       2667219.4      6853277.07
#Sta/Elev= 30
  4007.1  370.98  4135.6  369.31  4227.7  368.91    4368  364.44    4675  373.34
  4728.1  370.68  4751.9  372.45  4757.3  370.28  4775.7  371.74  4781.1  369.68
  4905.6  363.76  4934.8  360.98  4940.3  357.39  4982.5  357.83  5002.9  355.08
  5003.2  354.58  5006.9  355.08  5015.5  360.17  5040.7  361.01  5385.7  359.39
  5537.4  362.87  5549.8  364.97  5589.8  364.39  5595.3  366.55  5613.3  364.96
  5618.7  367.38  5702.3   369.4  5741.6  368.43  5928.2  373.87  6483.7  381.99
#Mann= 5 ,-1 , 0
  4007.1     .05       0  4135.6    .075       0  4227.7     .05       0
  5002.9     .07       0  5006.9     .05       0
Bank Sta=5002.9,5006.9
XS Rating Curve= 0 ,0
Exp/Cntr=0.3,0.1

Type RM Length L Ch R = 1 ,4745    ,680,680,680
BEGIN DESCRIPTION:
Kings Creek 32_2 5.0
END DESCRIPTION:
XS GIS Cut Line= 3
      2668266.91      6851179.08       2667480.2      6851449.99
        2667176.        6852161.
#Sta/Elev= 30
  3991.8  369.33  4082.3  368.35  4148.6   368.4  4229.4  366.89  4255.3  365.04
  4291.8   365.3    4349  363.49  4473.9  364.59  4637.9  362.93  4661.2  361.67
  4749.6  359.63  4754.9  360.19  4780.8  358.32  4823.4  357.09  4973.1  357.49
  4988.1  356.25  5002.1  353.26  5018.2  352.92  5018.5  352.42  5022.2  352.92
  5025.7  356.99  5031.6  357.65  5172.6  356.77  5301.5  359.22  5359.5  361.29
  5477.5  362.31  5535.5  364.47  5559.1  367.36  5564.6  368.91  5597.2  370.33
#Mann= 5 ,-1 , 0
  3991.8     .05       0  4082.3    .075       0  4148.6     .05       0
  5018.2     .03       0  5022.2     .05       0
Bank Sta=5018.2,5022.2
XS Rating Curve= 0 ,0
Exp/Cntr=0.3,0.1

Type RM Length L Ch R = 1 ,4065    ,285,285,285
BEGIN DESCRIPTION:
Mapping XS d4f5142c
END DESCRIPTION:
XS GIS Cut Line= 6
      2668049.31      6851241.63      2667880.04      6851278.52
      2667543.67      6851139.63      2667337.51      6851031.13
      2667233.34      6851022.45      2666716.86      6851009.43
#Sta/Elev= 30
  4218.3  366.21  4272.9  364.03  4330.9  364.34  4374.9  362.52    4380   363.3
  4471.5  361.53  4476.9  360.67  4554.1  360.45  4559.5  359.07  4666.4  356.59
    4798  356.05    4849  354.76  4909.5  354.85  4915.1  355.82  4953.5  354.18
  4959.2   355.1  4973.6  351.24  4973.8  350.74  4977.6  351.24  4981.2  355.05
    5093  355.42  5260.4  358.07  5347.1  361.76  5352.1  360.89  5380.4  362.41
  5490.4   364.5  5510.4  365.84  5550.4   364.9  5590.5  366.24  5609.6  365.31
#Mann= 3 ,-1 , 0
  4218.3     .05       0  4973.6     .05       0  4977.6     .05       0
Bank Sta=4973.6,4977.6
XS Rating Curve= 0 ,0
Exp/Cntr=0.3,0.1

Type RM Length L Ch R = 1 ,3780    ,479,479,479
BEGIN DESCRIPTION:
Kings Creek 32_2 3.0
END DESCRIPTION:
XS GIS Cut Line= 3
      2668402.34      6850975.98        2667376.        6850761.
      2667125.97      6850710.99
#Sta/Elev= 30
  3951.7  368.34  3997.2  366.15  4080.8  368.35    4147  367.49  4172.7  366.38
  4191.8   363.4  4223.8  363.24  4254.5  360.14  4346.7  359.93  4448.6  356.54
  4550.8   355.4  4571.2  354.21  4586.1   355.2  4693.8  352.48  4780.7  352.51
  4785.8  351.66  4825.6  353.05  4830.7  351.96  4857.3  352.98    4939   351.7
  4975.3  352.63  4990.1  351.26  5008.5  347.75  5008.8  347.25  5012.5  347.75
  5020.7   350.4  5030.9  351.87  5112.5  352.44  5204.3  357.99  5255.3  359.41
#Mann= 3 ,-1 , 0
  3951.7     .05       0  5008.5     .03       0  5012.5     .05       0
Bank Sta=5008.5,5012.5
XS Rating Curve= 0 ,0
Exp/Cntr=0.3,0.1

Type RM Length L Ch R = 1 ,3301    ,797,797,797
BEGIN DESCRIPTION:
Kings Creek 32_2 2.0
END DESCRIPTION:
XS GIS Cut Line= 3
      2668813.77       6850559.3        2667576.        6850361.
      2667175.97        6850411.
#Sta/Elev= 30
  3746.9   369.3  3785.2  368.54  3805.4  369.38  3830.9   367.8  3947.2  366.51
  3967.4  365.39  4139.6  365.32  4269.9  361.32  4331.8  361.54  4504.2  353.91
  4522.9  354.68  4534.6  353.74  4554.8  354.97  4595.4  352.48  4757.4   348.4
  4837.9     348  4858.7  350.18  4878.9  348.76  4990.3   349.5    5003  349.22
  5008.5  345.51  5008.8  345.01  5012.5  345.51  5020.6   347.5  5030.7  347.57
  5038.2  349.48  5050.8  350.19  5101.2  350.49  5280.1  354.97  5403.6  359.59
#Mann= 3 ,-1 , 0
  3746.9     .05       0  5008.5     .03       0  5012.5     .05       0
Bank Sta=5008.5,5012.5
XS Rating Curve= 0 ,0
Exp/Cntr=0.3,0.1

Type RM Length L Ch R = 1 ,2504    ,596,596,596
BEGIN DESCRIPTION:
Mapping XS fd4cc14b
END DESCRIPTION:
XS GIS Cut Line= 3
      2668646.41      6849479.05      2667564.13      6849551.21
      2666887.92      6850056.11
#Sta/Elev= 30
  3868.1  365.77  3998.8  366.66  4219.3  364.47  4409.7  359.31  4479.9  354.84
  4499.9  352.48  4569.4  352.84  4574.5     351  4620.2   353.3  4660.3  351.94
  4700.4   352.3  4730.4  349.08  4760.5  349.45  4800.6  344.76  4952.8  346.58
  4958.7  342.86    4965  343.27  4977.6     341  4977.8   340.5  4981.6     341
  4987.9  347.35  5000.4  348.34  5023.4  346.24  5094.2  345.54  5279.8  346.83
  5429.9  351.48  5515.3  355.46  5623.7  357.26    5680  356.95  5796.7  360.63
#Mann= 3 ,-1 , 0
  3868.1     .05       0  4977.6     .03       0  4981.6     .05       0
Bank Sta=4977.6,4981.6
XS Rating Curve= 0 ,0
Exp/Cntr=0.3,0.1

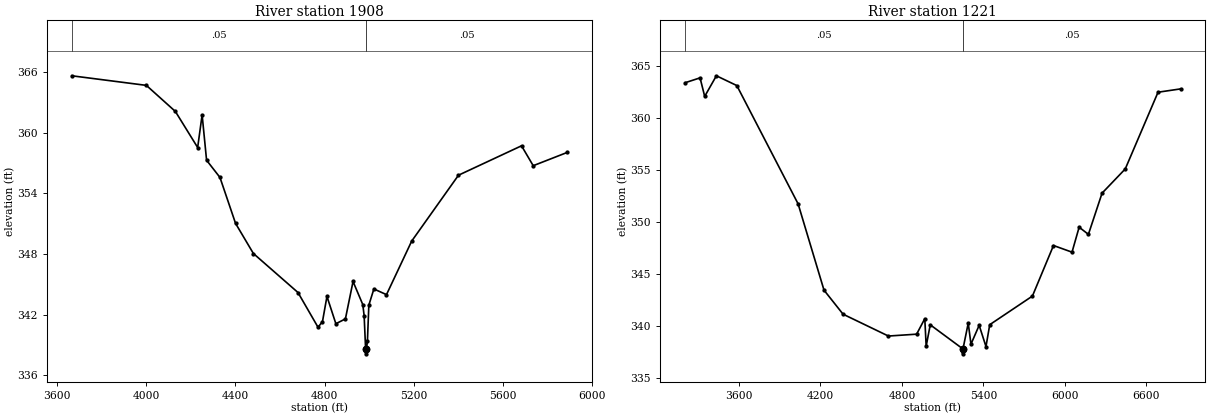
Type RM Length L Ch R = 1 ,1908    ,687,687,687
BEGIN DESCRIPTION:
Mapping XS 5efadb90
END DESCRIPTION:
XS GIS Cut Line= 5
      2668500.72      6849145.28      2667276.74       6849158.3
       2667185.6       6849223.4      2667038.03      6849370.97
      2666829.97      6850016.83
#Sta/Elev= 30
  3666.2  365.65  4000.9   364.7    4131  362.12    4231  358.55    4251  361.78
    4271  357.29    4331  355.59    4401  351.04    4481  348.06    4681   344.2
    4771  340.76    4791  341.33    4811  343.81    4851  341.11  4893.8  341.59
    4928  345.29  4971.7  343.01  4977.8  341.92  4984.4  338.63  4984.7  338.13
  4988.4  338.63  4992.6  339.41  4998.9  342.95  5021.5  344.55  5078.1  343.99
  5191.2  349.29  5401.1  355.81  5683.8  358.72  5736.3  356.75  5889.5  358.07
#Mann= 3 ,-1 , 0
  3666.2     .05       0  4984.4     .03       0  4988.4     .05       0
Bank Sta=4984.4,4988.4
XS Rating Curve= 0 ,0
Exp/Cntr=0.3,0.1

Type RM Length L Ch R = 1 ,1221    ,0,0,0
BEGIN DESCRIPTION:
Kings Creek 32_2 1.0
END DESCRIPTION:
XS GIS Cut Line= 4
      2668556.28      6848847.72      2666764.84      6848701.48
      2666583.46      6848765.07      2666761.37       6850416.5
#Sta/Elev= 30
  3202.6  363.36  3313.3  363.83  3347.5  362.05  3433.6  364.03  3584.1  363.09
  4035.6  351.72  4226.3  343.43  4366.7  341.12  4700.7  339.02  4908.5   339.2
  4968.7  340.69  4978.8  338.05  5008.9   340.1  5246.5  337.81  5246.7  337.31
  5250.5  337.81  5288.7  340.26  5308.8  338.24  5369.2  340.05  5419.4  338.01
    5447  340.11  5761.4  342.86  5916.7  347.72  6053.1  347.08  6105.6  349.48
  6173.8  348.79  6274.4  352.75  6445.4  355.08  6686.7  362.45  6853.2  362.77
#Mann= 3 ,-1 , 0
  3202.6     .05       0  5246.5     .03       0  5250.5     .05       0
Bank Sta=5246.5,5250.5
XS Rating Curve= 0 ,0
Exp/Cntr=0.3,0.1

Chan Stop Cuts=-1
Use User Specified Reach Order=0
Composite Channel Slope=5