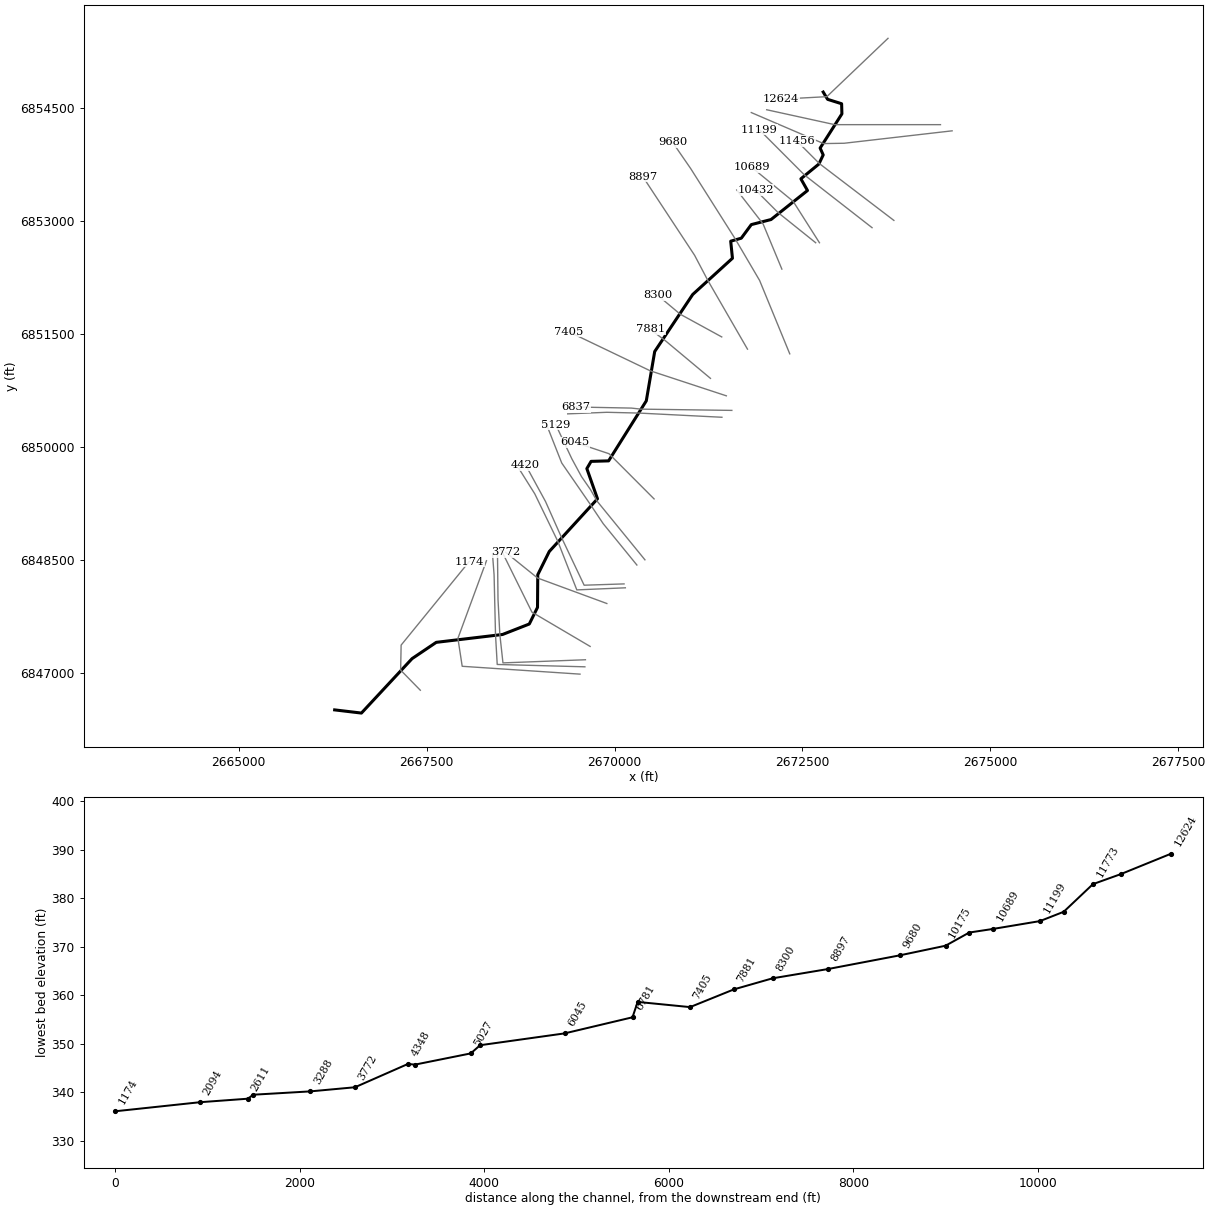
--- Kings Creek 32_3.prj (project) ---

Proj Title=Kings Creek 32_3 Base Level Engineering
Current Plan=p01
Default Exp/Contr=0.3,0.1
English Units
Geom File=g01
Flow File=f01
Plan File=p01
Y Axis Title=Elevation
X Axis Title(PF)=Main Channel Distance
X Axis Title(XS)=Station
BEGIN DESCRIPTION:
Kings Creek 32_3
END DESCRIPTION:
DSS Export Rating Curves= 0
DSS Export Rating Curve Sorted= 0
DSS Export Volume Flow Curves= 0
DXF OffsetX= 0
DXF OffsetY= 0
DXF ScaleX= 1
DXF ScaleY= 10

--- Kings Creek 32_3.p01 (plan) ---

Plan Title=Multiple Run
Short Identifier=Multiple
Geom File=g01
Flow File=f01
Subcritical Flow
K Sum by GR= 0
Std Step Tol= 0.01
Critical Tol= 0.01
Num of Std Step Trials= 20
Max Error Tol= 0.3
Flow Tol Ratio= 0.001
Split Flow NTrial= 30
Split Flow Tol= 0.02
Split Flow Ratio= 0.02
Log Output Level= 0
Friction Slope Method= 1
Unsteady Friction Slope Method= 2
Unsteady Bridges Friction Slope Method= 1
Parabolic Critical Depth
Global Vel Dist=  1 , 1 , 1
Global Log Level= 0
CheckData=True
Encroach Param= -1, 0, 0, 0
BEGIN DESCRIPTION:
Multiple Run
END DESCRIPTION:

--- Kings Creek 32_3.f01 (steady flow) ---

Flow Title=Multiple
Number of Profiles=7
Profile Names=10-year,25-year,50-year,1pct_min,100-year,1pct_plu,500-year
River Rch & RM= Kings Creek 32_3,Reach-1,12624
     177     219     249     141     282     563     360
River Rch & RM= Kings Creek 32_3,Reach-1,10689
     554     739     887     528    1054    2104    1489
River Rch & RM= Kings Creek 32_3,Reach-1,6045
     580     776     933     556    1110    2214    1571
River Rch & RM= Kings Creek 32_3,Reach-1,5027
     650     873    1052     629    1255    2503    1784
Boundary for River Rch & Prof#=Kings Creek 32_3,Reach-1,1
Up Type=0
Dn Type=3
Dn Slope=0.005
Boundary for River Rch & Prof#=Kings Creek 32_3,Reach-1,2
Up Type=0
Dn Type=3
Dn Slope=0.005
Boundary for River Rch & Prof#=Kings Creek 32_3,Reach-1,3
Up Type=0
Dn Type=3
Dn Slope=0.005
Boundary for River Rch & Prof#=Kings Creek 32_3,Reach-1,4
Up Type=0
Dn Type=3
Dn Slope=0.005
Boundary for River Rch & Prof#=Kings Creek 32_3,Reach-1,5
Up Type=0
Dn Type=3
Dn Slope=0.005
Boundary for River Rch & Prof#=Kings Creek 32_3,Reach-1,6
Up Type=0
Dn Type=3
Dn Slope=0.005
Boundary for River Rch & Prof#=Kings Creek 32_3,Reach-1,7
Up Type=0
Dn Type=3
Dn Slope=0.005

--- Kings Creek 32_3.g01 (geometry) ---

Geom Title=Existing Conditions
Program Version=4.10

River Reach=Kings Creek 32_3,Reach-1
Reach XY= 30
        2672776.        6854711.      2672834.34      6854614.43
      2673020.98      6854555.92      2673024.82      6854421.52
      2672735.15      6853967.73      2672775.86      6853876.41
      2672717.86      6853754.94      2672479.01      6853559.57
      2672567.04      6853404.31      2672082.06      6853019.14
      2671819.31      6852951.71       2671686.1      6852771.39
      2671545.38      6852731.64      2671568.52      6852504.93
      2671039.63      6852024.21      2670534.14      6851267.06
      2670422.26      6850612.53      2669920.92      6849816.03
       2669687.8      6849809.38      2669631.32      6849713.23
      2669772.87      6849312.63      2669131.52      6848613.43
      2668978.24      6848305.07      2668974.94      6847871.44
      2668865.64      6847650.84      2668510.06      6847511.92
      2667627.47      6847407.45      2667305.91      6847191.21
      2666632.21       6846468.8        2666276.        6846511.

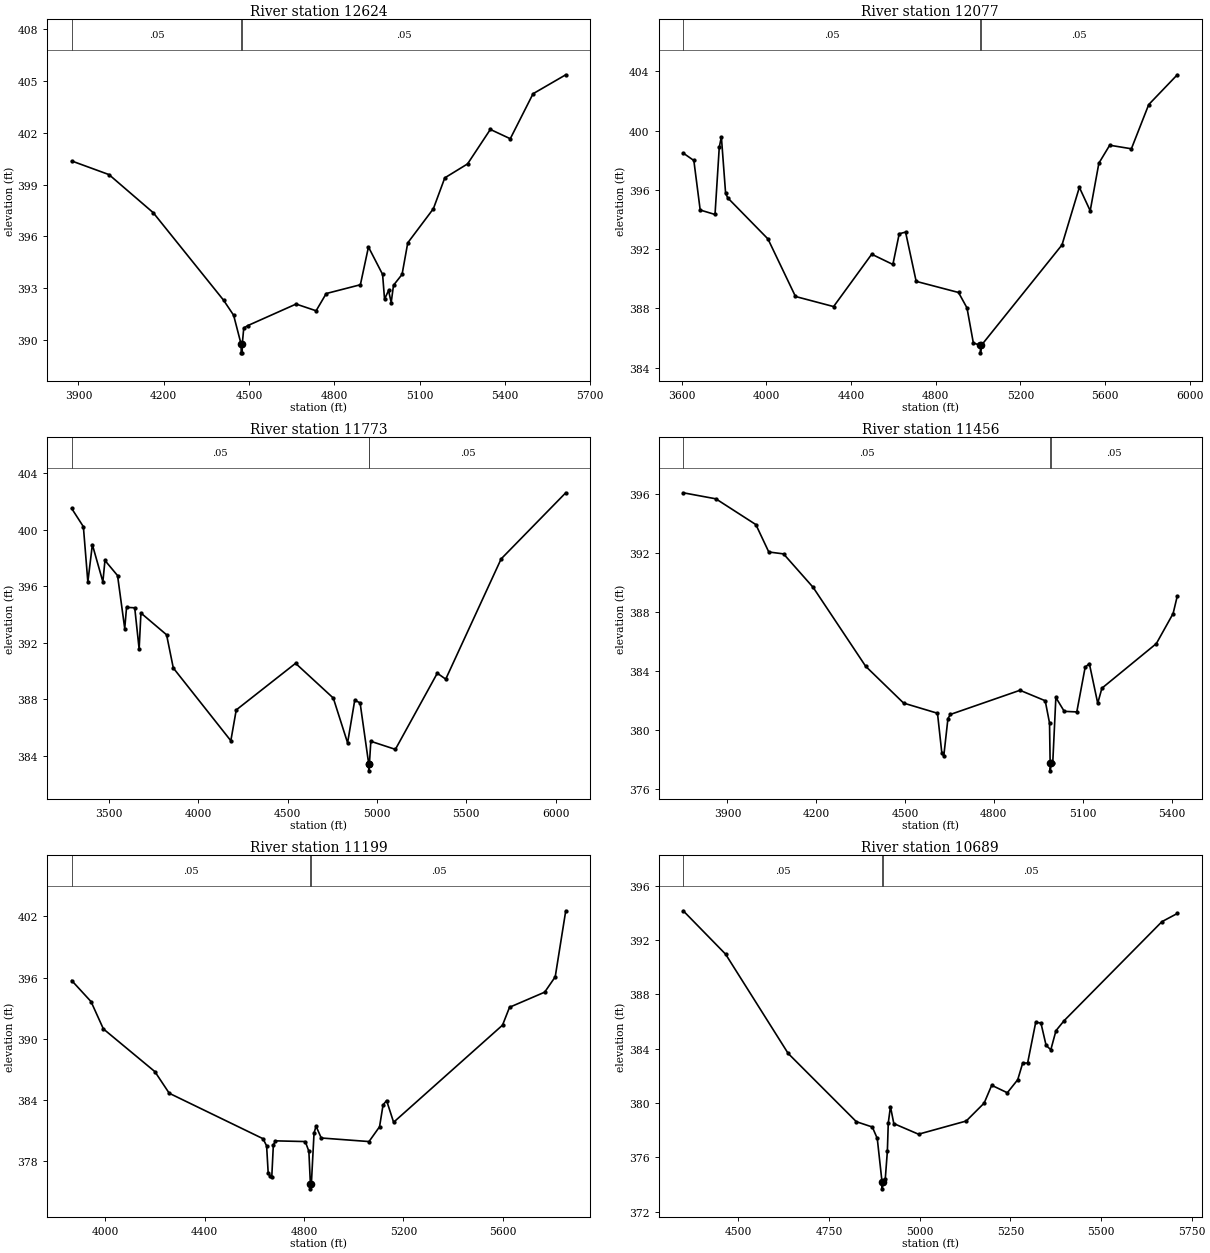
Type RM Length L Ch R = 1 ,12624   ,547,547,547
BEGIN DESCRIPTION:
Kings Creek 32_3 26.0
END DESCRIPTION:
XS GIS Cut Line= 3
      2673638.28      6855424.12      2672824.12      6854649.77
       2672211.2      6854616.82
#Sta/Elev= 30
  3876.4  400.37  4007.5  399.58  4163.2  397.37  4410.7  392.29  4445.9  391.42
  4472.2  389.74  4472.5  389.24    4476  389.24  4476.2  389.74  4481.5  390.68
  4495.6  390.82  4665.5  392.07  4735.9  391.68  4771.5  392.68  4891.6  393.19
    4920  395.38  4969.7  393.79  4976.6  392.35  4990.7  392.86    5000  392.16
  5008.1  393.16  5038.2  393.79  5058.2  395.62  5148.3   397.6  5188.4  399.39
  5268.5   400.2  5348.6   402.2  5418.7  401.66  5498.8  404.27  5613.8  405.37
#Mann= 3 ,-1 , 0
  3876.4     .05       0  4472.2     .04       0  4476.2     .05       0
Bank Sta=4472.2,4476.2
XS Rating Curve= 0 ,0
Exp/Cntr=0.3,0.1

Type RM Length L Ch R = 1 ,12077   ,304,304,304
BEGIN DESCRIPTION:
Mapping XS c826c034
END DESCRIPTION:
XS GIS Cut Line= 3
      2674336.22      6854278.27      2672929.94      6854278.27
      2672024.16      6854476.09
#Sta/Elev= 30
  3607.5  398.48  3657.7  397.98  3687.7  394.64  3757.7  394.34  3777.7  398.86
  3787.7  399.58  3807.7  395.77  3817.7  395.46  4007.7  392.69  4137.7  388.81
  4317.7  388.13  4497.7  391.66  4597.7  390.97  4627.7  393.04  4657.7  393.15
  4707.7  389.83  4907.7  389.08  4947.7  388.04  4977.7  385.68  5011.2  385.51
  5011.5  385.01  5015.2  385.51  5396.5  392.29  5478.4  396.17  5529.6  394.59
  5570.6   397.8  5621.7  399.01  5724.1  398.77    5806  401.75  5940.9  403.76
#Mann= 3 ,-1 , 0
  3607.5     .05       0  5011.2     .03       0  5015.2     .05       0
Bank Sta=5011.2,5015.2
XS Rating Curve= 0 ,0
Exp/Cntr=0.3,0.1

Type RM Length L Ch R = 1 ,11773   ,317,317,317
BEGIN DESCRIPTION:
Mapping XS 005bd953
END DESCRIPTION:
XS GIS Cut Line= 4
      2674491.09      6854196.31      2673054.47      6854031.38
      2672781.03      6854027.04      2671819.22      6854438.63
#Sta/Elev= 30
  3291.5   401.5    3357  400.21    3382   396.3  3407.3  398.94  3466.1  396.31
  3477.8  397.82  3548.3  396.75  3588.5     393  3598.6   394.5  3644.4  394.47
  3669.1  391.55  3679.1   394.1  3822.7  392.56  3860.3  390.21  4182.4  385.06
  4212.6  387.24  4544.8  390.54    4756  388.08    4836  384.91    4876  387.93
    4906  387.74  4954.1  383.43  4954.3  382.93  4958.1  383.43  4966.1  385.02
  5103.5  384.45  5338.1  389.84  5385.3  389.42  5695.5  397.93  6057.2  402.61
#Mann= 3 ,-1 , 0
  3291.5     .05       0  4954.1     .04       0  4958.1     .05       0
Bank Sta=4954.1,4958.1
XS Rating Curve= 0 ,0
Exp/Cntr=0.3,0.1

Type RM Length L Ch R = 1 ,11456   ,257,257,257
BEGIN DESCRIPTION:
Kings Creek 32_3 24.0
END DESCRIPTION:
XS GIS Cut Line= 3
      2673716.36      6853007.47        2672726.        6853761.
        2672426.        6854061.
#Sta/Elev= 30
  3750.8  396.11    3861   395.7  3996.2  393.95  4039.8  392.09  4089.7  391.96
  4189.5  389.69    4367  384.33  4495.2  381.83  4609.6  381.14  4624.1  378.47
  4630.8  378.23  4644.9  380.78  4653.2  381.06  4888.2   382.7  4973.4  381.99
    4988  380.48  4990.1  377.73  4990.3  377.23  4994.1  377.73  4998.8  377.73
  5009.4  382.21  5037.7  381.27  5080.1  381.23  5108.4  384.27  5122.5  384.51
  5150.8  381.82  5164.9  382.84  5348.8  385.87  5405.4  387.91  5419.5   389.1
#Mann= 3 ,-1 , 0
  3750.8     .05       0  4990.1     .04       0  4994.1     .05       0
Bank Sta=4990.1,4994.1
XS Rating Curve= 0 ,0
Exp/Cntr=0.3,0.1

Type RM Length L Ch R = 1 ,11199   ,510,510,510
BEGIN DESCRIPTION:
Kings Creek 32_3 23.0
END DESCRIPTION:
XS GIS Cut Line= 3
      2673426.01      6852910.99        2672526.        6853611.
      2671926.01      6854210.99
#Sta/Elev= 30
  3864.8  395.71  3942.6  393.65  3992.4  390.97  4199.6  386.79  4257.5  384.67
  4634.9  380.22  4649.4  379.52  4655.7  376.89  4662.9  376.56  4670.2  376.49
  4676.5  379.58  4684.7  380.01    4805  379.94  4819.5  378.99  4825.6  375.81
  4825.9  375.31  4829.6  375.81  4840.3  380.77  4848.4  381.45  4869.3  380.29
  5061.6  379.94    5104  381.39  5118.1  383.52  5132.3  383.96  5160.6  381.83
    5599  391.34  5627.2  393.09  5768.7  394.57  5811.1  396.07  5853.5  402.54
#Mann= 3 ,-1 , 0
  3864.8     .05       0  4825.6     .04       0  4829.6     .05       0
Bank Sta=4825.6,4829.6
XS Rating Curve= 0 ,0
Exp/Cntr=0.3,0.1

Type RM Length L Ch R = 1 ,10689   ,257,257,257
BEGIN DESCRIPTION:
Kings Creek 32_3 21.0
END DESCRIPTION:
XS GIS Cut Line= 3
      2672725.99      6852711.02        2672376.        6853261.
      2671826.02      6853710.98
#Sta/Elev= 30
  4347.9  394.15  4464.7  390.96  4637.4  383.65  4825.4  378.63  4869.4  378.24
    4883   377.4  4896.2  374.19  4896.4  373.69  4900.2  374.19    4905  374.38
  4910.9  376.46  4913.4  378.54  4919.4  379.74  4928.7  378.49  4996.8  377.71
  5128.3  378.68  5177.8     380  5198.6  381.31  5241.7  380.76  5270.4  381.72
    5284  382.94  5297.7  382.95  5319.9  385.93  5334.3   385.9  5348.6  384.25
  5361.6  383.92  5375.9  385.33  5398.2  386.06  5668.1  393.35  5710.4  393.95
#Mann= 3 ,-1 , 0
  4347.9     .05       0  4896.2     .04       0  4900.2     .05       0
Bank Sta=4896.2,4900.2
XS Rating Curve= 0 ,0
Exp/Cntr=0.3,0.1

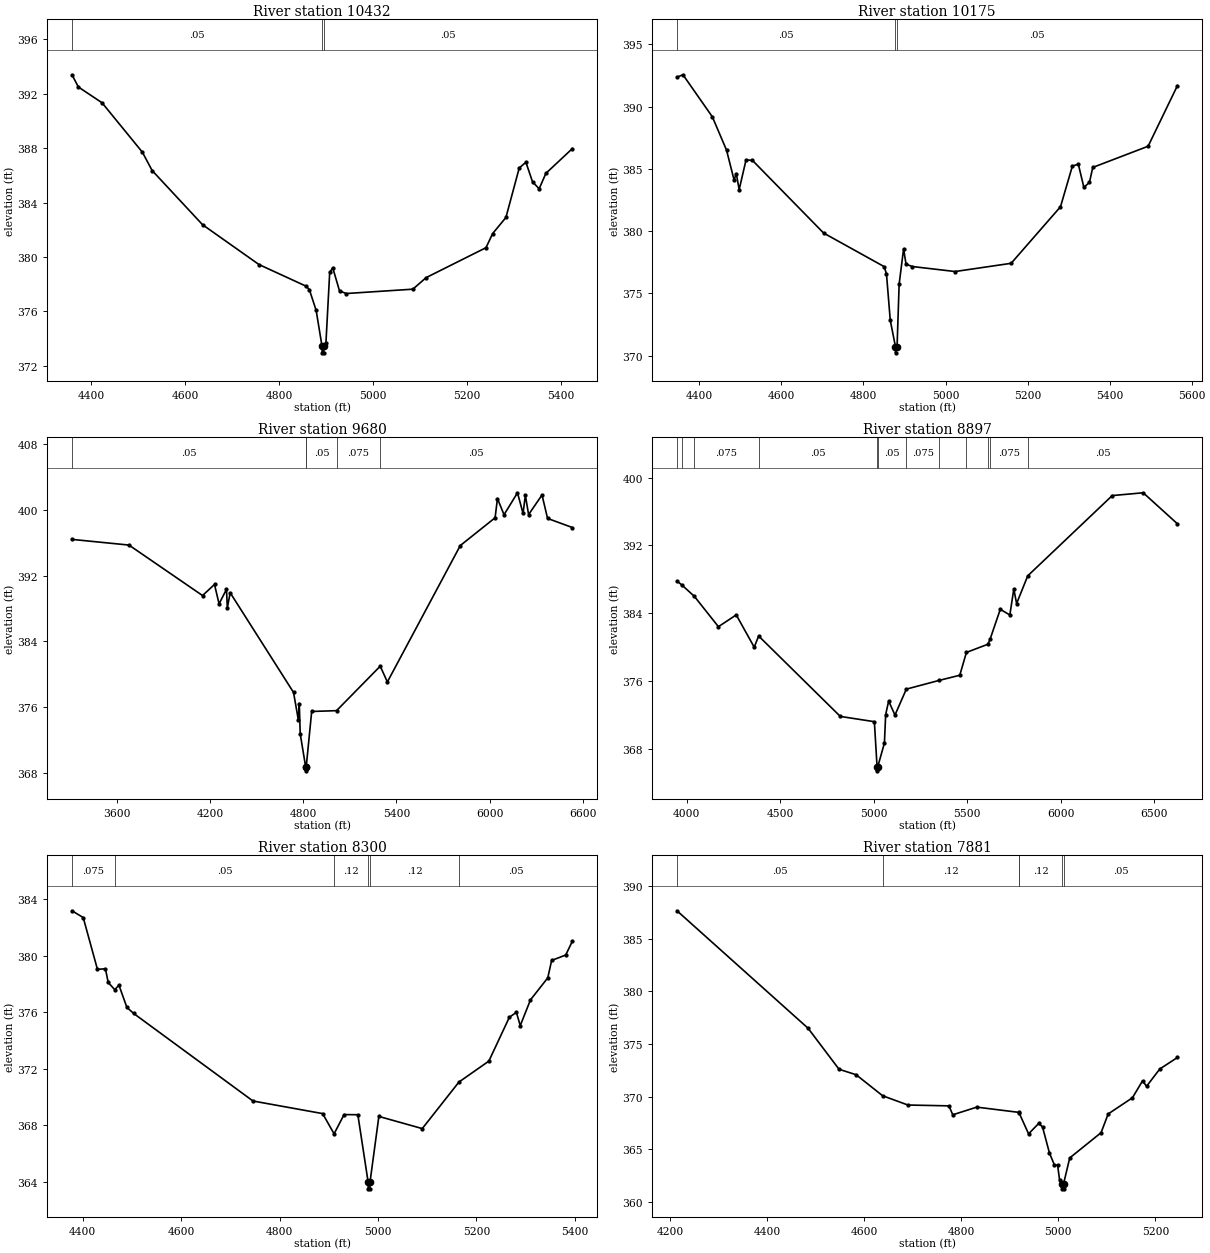
Type RM Length L Ch R = 1 ,10432   ,257,257,257
BEGIN DESCRIPTION:
Kings Creek 32_3 20.0
END DESCRIPTION:
XS GIS Cut Line= 3
      2672675.98      6852711.01        2672176.        6853111.
      2671875.97      6853411.03
#Sta/Elev= 30
  4359.5  393.39  4373.1  392.49  4423.5  391.33  4509.2   387.7    4530  386.35
  4637.2  382.37  4757.3  379.44  4858.1  377.84  4864.5  377.59  4878.9  376.07
  4891.3  373.45  4891.6  372.95  4895.1  372.95  4895.3  373.45  4899.7  373.68
  4907.7  378.86  4914.2   379.2  4928.6   377.5    4943  377.31  5084.6  377.63
  5112.9  378.48  5240.2  380.68  5254.4  381.72  5282.6   382.9  5310.9  386.54
  5325.1  386.96  5339.2  385.52  5353.3  385.01  5367.5  386.14  5424.1  387.97
#Mann= 3 ,-1 , 0
  4359.5     .05       0  4891.3     .04       0  4895.3     .05       0
Bank Sta=4891.3,4895.3
XS Rating Curve= 0 ,0
Exp/Cntr=0.3,0.1

Type RM Length L Ch R = 1 ,10175   ,495,495,495
BEGIN DESCRIPTION:
Kings Creek 32_3 19.0
END DESCRIPTION:
XS GIS Cut Line= 3
      2672225.99      6852361.03        2671976.        6852961.
      2671625.98      6853411.03
#Sta/Elev= 30
  4345.3  392.37  4359.9  392.56  4431.4  389.19  4466.1  386.51  4484.5  384.11
  4489.9  384.63  4496.9  383.34  4513.7  385.73  4529.4  385.68  4702.8  379.85
  4850.6  377.15  4856.1  376.55  4865.3  372.84  4877.9  370.73  4878.1  370.23
  4881.9  370.73  4886.9  375.74  4897.8  378.58  4903.7  377.35  4919.4  377.16
  5023.3  376.76    5160  377.42  5280.3  381.96  5309.3  385.23  5323.8  385.38
  5337.3  383.52  5350.9  383.92    5359  385.12  5493.9  386.82  5565.4  391.69
#Mann= 3 ,-1 , 0
  4345.3     .05       0  4877.9     .04       0  4881.9     .05       0
Bank Sta=4877.9,4881.9
XS Rating Curve= 0 ,0
Exp/Cntr=0.3,0.1

Type RM Length L Ch R = 1 ,9680    ,783,783,783
BEGIN DESCRIPTION:
Mapping XS 96eb210e
END DESCRIPTION:
XS GIS Cut Line= 5
      2672330.96      6851236.65      2671929.94      6852210.56
      2671601.81      6852767.86      2671013.27      6853694.94
      2670769.57      6854047.53
#Sta/Elev= 30
  3307.8   396.4  3675.1  395.71  4149.4  389.57  4226.6  390.92    4256  388.56
  4303.9  390.33  4309.3  388.08  4327.8  389.91  4736.1  377.79  4767.4  374.43
  4773.2  376.44  4779.3  372.75  4814.1  368.75  4814.4  368.25  4818.1  368.75
  4853.2  375.47  5013.5  375.57  5295.2  380.98  5341.2  379.06  5811.3  395.65
  6035.8  399.03    6051  401.37  6093.4   399.4  6180.2  402.07    6216  399.56
  6230.9  401.76  6251.8  399.42  6338.3   401.8  6374.1  398.95  6534.5  397.84
#Mann= 5 ,-1 , 0
  3307.8     .05       0  4814.1     .03       0  4818.1     .05       0
  5013.5    .075       0  5295.2     .05       0
Bank Sta=4814.1,4818.1
XS Rating Curve= 0 ,0
Exp/Cntr=0.3,0.1

Type RM Length L Ch R = 1 ,8897    ,597,597,597
BEGIN DESCRIPTION:
Mapping XS ad4c52a5
END DESCRIPTION:
XS GIS Cut Line= 4
      2671768.46      6851299.13      2671241.36      6852210.13
      2671065.35       6852543.9      2670377.87      6853585.54
#Sta/Elev= 30
  3947.5   387.8    3972  387.37  4040.4     386  4169.2  382.42  4264.6  383.81
  4360.8     380  4384.5  381.32  4821.5  371.83  5003.7  371.21  5018.1  365.91
  5018.3  365.41  5022.1  365.91  5057.5  368.69  5064.1  372.04  5080.1  373.64
    5114  371.99  5174.7  375.05    5350  376.08  5460.8  376.69  5496.1  379.38
  5611.5  380.35  5623.2  380.96  5677.5  384.47  5728.7   383.8  5749.8  386.86
  5764.9  385.15  5824.4  388.42  6276.6  397.89  6442.2  398.22  6625.4  394.56
#Mann= 12 ,-1 , 0
  3947.5    .075       0    3972     .05       0  4040.4    .075       0
  4384.5     .05       0  5018.1     .03       0  5022.1     .05       0
  5174.7    .075       0    5350     .05       0  5496.1    .075       0
  5611.5     .05       0  5623.2    .075       0  5824.4     .05       0
Bank Sta=5018.1,5022.1
XS Rating Curve= 0 ,0
Exp/Cntr=0.3,0.1

Type RM Length L Ch R = 1 ,8300    ,419,419,419
BEGIN DESCRIPTION:
Kings Creek 32_3 14.0
END DESCRIPTION:
XS GIS Cut Line= 3
        2671426.        6851461.        2670876.        6851761.
        2670576.        6852011.
#Sta/Elev= 30
  4378.1  383.17  4400.9  382.69  4429.8  379.03    4446  379.07  4451.7   378.1
    4465  377.59  4473.5  377.91  4489.6  376.34  4503.4  375.91  4745.9  369.72
  4887.4  368.83  4910.7   367.4    4931  368.76    4959  368.75  4979.8  364.01
  4980.1  363.51  4983.6  363.51  4983.8  364.01  5001.7  368.63  5089.9  367.77
  5164.4  371.06  5225.2  372.54  5266.9  375.64  5281.2  375.99    5289  375.05
  5309.8  376.87    5345  378.43  5352.8  379.66  5381.4  380.04  5395.1  381.03
#Mann= 6 ,-1 , 0
  4378.1    .075       0    4465     .05       0  4910.7     .12       0
  4979.8     .07       0  4983.8     .12       0  5164.4     .05       0
Bank Sta=4979.8,4983.8
XS Rating Curve= 0 ,0
Exp/Cntr=0.3,0.1

Type RM Length L Ch R = 1 ,7881    ,476,476,476
BEGIN DESCRIPTION:
Kings Creek 32_3 13.0
END DESCRIPTION:
XS GIS Cut Line= 3
      2671276.03      6850910.97        2670676.        6851411.
      2670475.98      6851561.02
#Sta/Elev= 30
  4214.4  387.67  4484.5   376.5  4548.3   372.6  4583.5  372.08  4638.1  370.08
  4690.2   369.2  4774.8  369.12  4782.6  368.27  4832.1     369    4919   368.5
  4919.6  368.42  4938.8  366.46  4959.7  367.45  4967.5  367.12  4981.8  364.64
  4992.2  363.48  4998.6  363.48  5002.8  362.05    5007  361.73  5007.3  361.23
  5010.8  361.23    5011  361.73  5023.6  364.17  5088.2  366.57  5102.8  368.35
  5152.8  369.89  5173.6   371.5  5181.9  370.98    5209  372.62  5245.5  373.72
#Mann= 6 ,-1 , 0
  4214.4     .05       0  4638.1     .12       0    4919     .05       0
  4919.6     .12       0    5007     .07       0    5011     .05       0
Bank Sta=5007,5011
XS Rating Curve= 0 ,0
Exp/Cntr=0.3,0.1

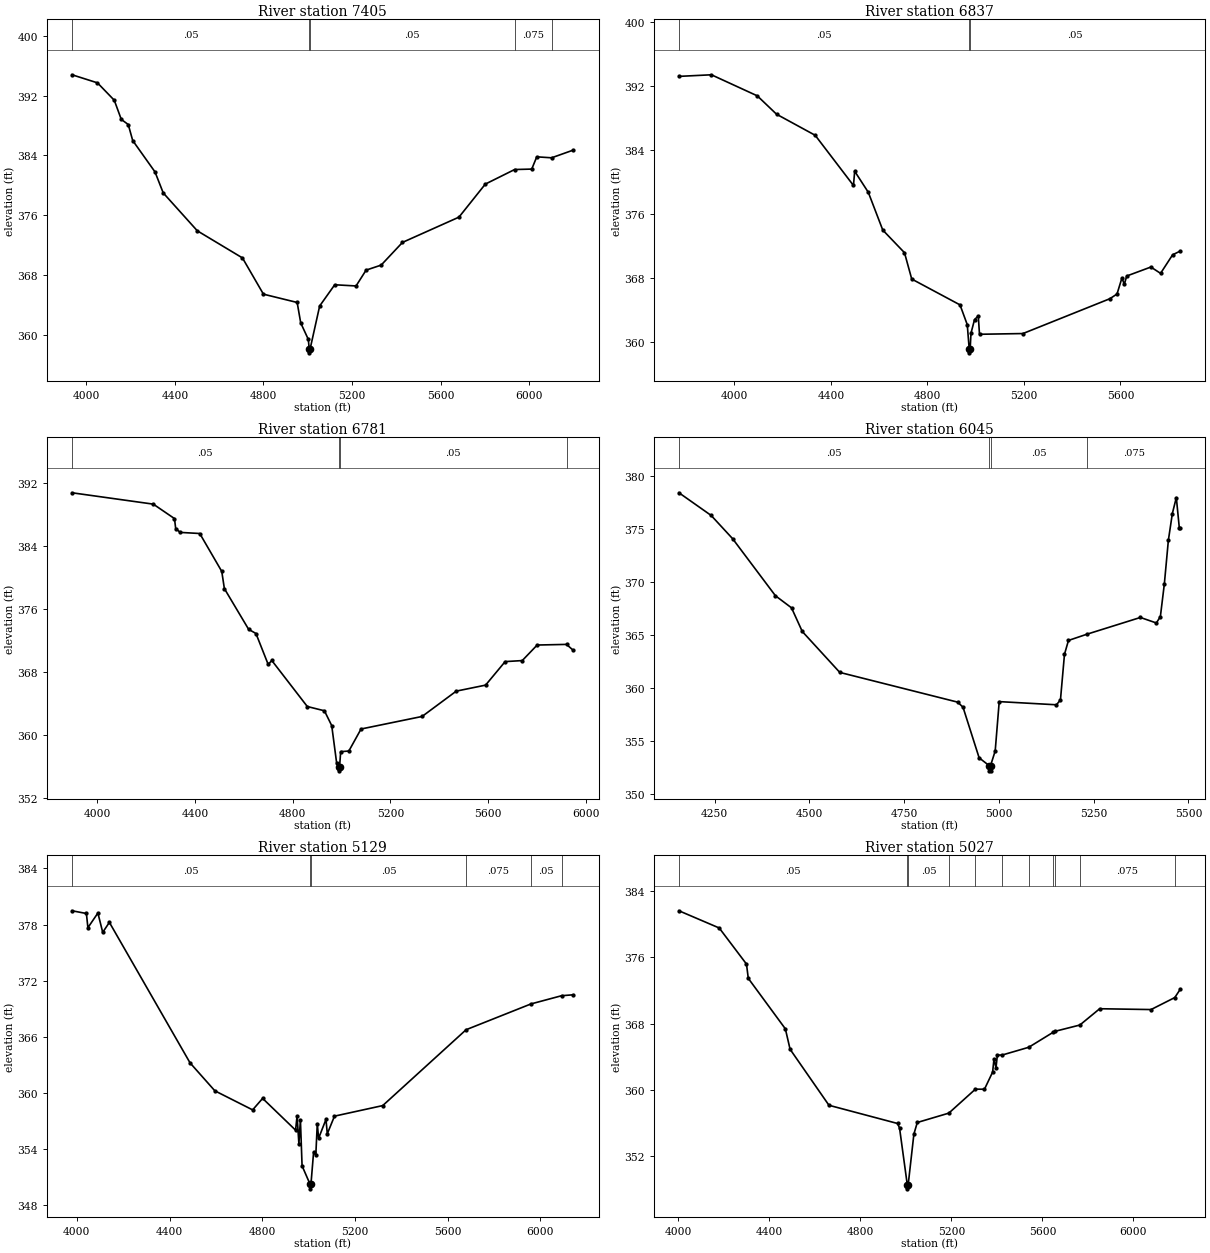
Type RM Length L Ch R = 1 ,7405    ,568,568,568
BEGIN DESCRIPTION:
Kings Creek 32_3 12.0
END DESCRIPTION:
XS GIS Cut Line= 3
       2671487.2      6850679.32        2670476.        6851011.
      2669393.45      6851528.29
#Sta/Elev= 30
  3935.8  394.78  4050.5   393.7  4126.5  391.37  4158.1  388.81  4189.6  388.12
  4209.7  385.98  4310.4  381.78  4347.5  378.97  4501.4   373.9  4705.3  370.27
    4800  365.42  4952.3  364.31  4968.4  361.57  5002.8  359.36  5006.6  358.07
  5006.8  357.57  5010.6  358.07  5053.9  363.84  5121.9  366.68  5218.2  366.52
  5263.6  368.64  5331.6  369.31  5427.9  372.35  5682.9  375.73  5801.9  380.15
  5934.2   382.1  6011.5  382.16  6034.2   383.8  6101.1  383.67  6199.8  384.71
#Mann= 5 ,-1 , 0
  3935.8     .05       0  5006.6     .03       0  5010.6     .05       0
  5934.2    .075       0  6101.1     .05       0
Bank Sta=5006.6,5010.6
XS Rating Curve= 0 ,0
Exp/Cntr=0.3,0.1

Type RM Length L Ch R = 1 ,6837    ,56,56,56
BEGIN DESCRIPTION:
Mapping XS 8d196263
END DESCRIPTION:
XS GIS Cut Line= 4
      2671560.45      6850485.91      2670350.03      6850502.72
      2670223.43      6850516.55      2669483.97      6850531.05
#Sta/Elev= 30
  3770.5  393.18    3905  393.38    4095  390.75    4175  388.45    4335  385.82
  4493.6  379.55  4498.6  381.33    4555   378.7    4615  373.98    4705  371.15
    4735  367.86  4935.1  364.63  4965.1  362.16  4973.1  359.14  4973.3  358.64
  4977.1  359.14  4980.6   361.1  4995.2  362.79  5010.7  363.25  5015.8  360.96
  5195.8  361.05  5555.9   365.4  5585.6  365.99  5605.9  367.99  5615.9  367.21
  5625.9  368.24  5725.9  369.36    5766  368.57    5816  370.89    5848  371.36
#Mann= 3 ,-1 , 0
  3770.5     .05       0  4973.1     .04       0  4977.1     .05       0
Bank Sta=4973.1,4977.1
XS Rating Curve= 0 ,0
Exp/Cntr=0.3,0.1

Type RM Length L Ch R = 1 ,6781    ,736,736,736
BEGIN DESCRIPTION:
Mapping XS 495e9021
END DESCRIPTION:
XS GIS Cut Line= 4
      2671428.48      6850394.77      2670327.77      6850450.32
      2669897.21      6850460.74      2669376.42      6850439.91
#Sta/Elev= 30
  3896.2   390.7  4229.1  389.26  4315.8  387.43  4320.8  386.17  4339.2  385.68
  4419.3  385.54  4509.5  380.74  4520.2  378.56  4619.6   373.4  4649.6  372.87
  4699.7  368.95  4714.5  369.45  4859.9  363.62    4930  363.08    4960   361.2
  4980.1  356.47  4988.1  355.97  4988.3  355.47  4992.1  355.97  4996.7   357.9
  5030.1  357.98  5080.1  360.77  5330.2  362.36  5470.2  365.57  5590.3  366.33
  5670.4  369.31  5740.5  369.44  5801.6  371.41  5921.8  371.49  5950.2  370.72
#Mann= 4 ,-1 , 0
  3896.2     .05       0  4988.1     .04       0  4992.1     .05       0
  5921.8    .075       0
Bank Sta=4988.1,4992.1
XS Rating Curve= 0 ,0
Exp/Cntr=0.3,0.1

Type RM Length L Ch R = 1 ,6045    ,916,916,916
BEGIN DESCRIPTION:
Kings Creek 32_3 9.0
END DESCRIPTION:
XS GIS Cut Line= 3
        2670526.        6849311.        2669926.        6849911.
      2669475.98      6850061.01
#Sta/Elev= 30
  4155.9  378.42  4240.8  376.28  4297.3  374.09  4410.5  368.69  4452.9  367.55
  4481.2  365.32  4580.2  361.45  4891.3  358.64  4905.4  358.16  4947.9  353.38
  4974.1  352.65  4974.4  352.15  4977.9  352.15  4978.1  352.65  4990.3  354.03
  5000.9  358.69    5152  358.39  5162.5  358.86  5173.1  363.16  5183.6  364.47
  5232.5  365.06  5373.4  366.64  5415.5  366.12  5426.1  366.72  5436.6  369.81
  5447.2  373.93  5457.7  376.46  5468.2  377.97  5476.1  375.09  5478.8  375.09
#Mann= 4 ,-1 , 0
  4155.9     .05       0  4974.1     .03       0  4978.1     .05       0
  5232.5    .075       0
Bank Sta=4974.1,4978.1
XS Rating Curve= 0 ,0
Exp/Cntr=0.3,0.1

Type RM Length L Ch R = 1 ,5129    ,102,102,102
BEGIN DESCRIPTION:
Mapping XS 42f60bc8
END DESCRIPTION:
XS GIS Cut Line= 6
      2670404.13      6848502.87      2669765.27      6849284.09
       2669680.5      6849433.45       2669560.4      6849607.01
      2669431.93      6849843.12      2669217.13      6850296.98
#Sta/Elev= 30
  3979.3  379.47  4041.2  379.18  4047.7  377.66  4090.8  379.23  4111.6  377.16
  4140.3  378.23  4488.4  363.19  4595.4   360.2  4758.3  358.16  4801.4  359.39
  4943.6  355.99    4950  357.51  4957.9  354.53  4964.4   357.1  4971.6  352.17
  5005.9  350.21  5006.2  349.71  5009.9  350.21  5021.3  353.64  5030.9  353.36
  5037.2  356.68  5042.9  355.12  5074.7  357.14  5080.4   355.6  5111.4  357.49
  5319.5  358.62  5679.2  366.74    5959   369.5  6091.2  370.38  6142.2  370.48
#Mann= 6 ,-1 , 0
  3979.3     .05       0  5005.9     .05       0  5009.9     .05       0
  5679.2    .075       0    5959     .05       0  6091.2    .075       0
Bank Sta=5005.9,5009.9
XS Rating Curve= 0 ,0
Exp/Cntr=0.3,0.1

Type RM Length L Ch R = 1 ,5027    ,607,607,607
BEGIN DESCRIPTION:
Mapping XS 7970e363
END DESCRIPTION:
XS GIS Cut Line= 5
      2670296.93      6848433.85      2669849.03      6848982.44
      2669671.95      6849246.33      2669296.95        6849788.
      2669105.97      6850270.67
#Sta/Elev= 30
  4002.3  381.63  4179.3  379.55  4299.1  375.19  4307.1  373.46    4470  367.36
  4490.8  364.89  4661.7  358.12    4963  355.92  4971.9  355.38  5005.9  348.52
  5006.2  348.02  5009.9  348.52    5035  354.64  5049.9  356.04  5188.4  357.17
  5305.5  360.07  5345.2  360.06    5381  362.13  5387.1  363.72  5395.9  362.65
  5401.9  364.19  5422.6  364.19  5539.8  365.13  5648.1  366.96  5656.9  367.07
  5764.5  367.82  5851.7  369.79  6077.5  369.69  6181.7  371.14  6206.2  372.16
#Mann= 11 ,-1 , 0
  4002.3     .05       0  5005.9     .05       0  5009.9     .05       0
  5188.4    .075       0  5305.5     .05       0  5422.6      .1       0
  5539.8     .05       0  5648.1    .075       0  5656.9     .05       0
  5764.5    .075       0  6181.7      .1       0
Bank Sta=5005.9,5009.9
XS Rating Curve= 0 ,0
Exp/Cntr=0.3,0.1

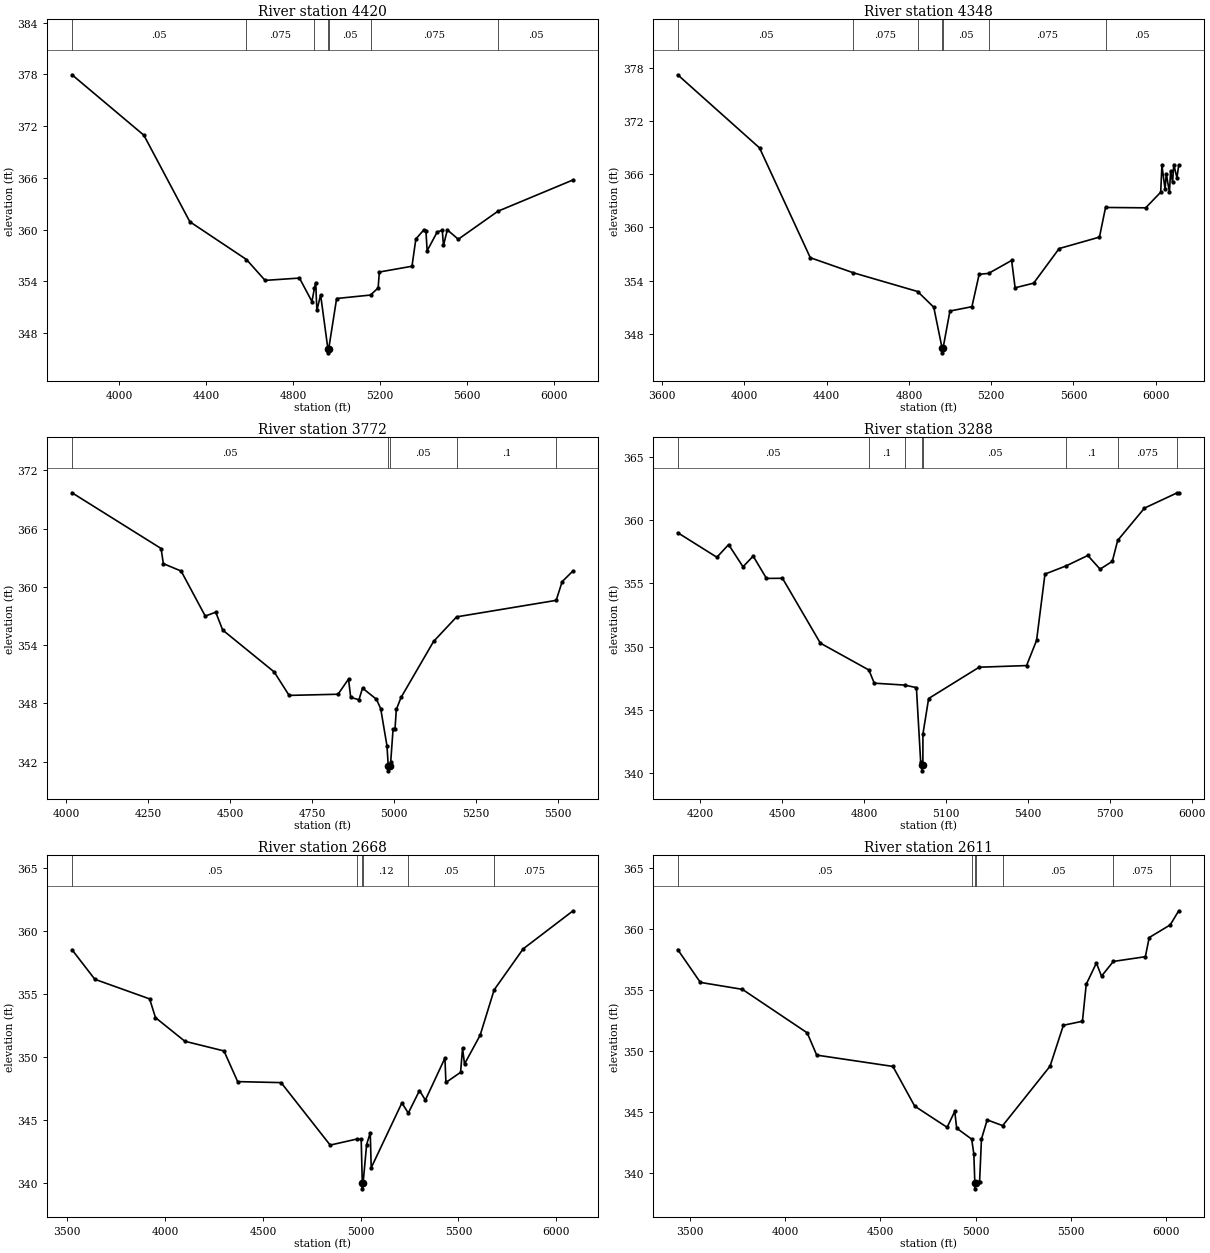
Type RM Length L Ch R = 1 ,4420    ,72,72,72
BEGIN DESCRIPTION:
Mapping XS 4f8ac0b2
END DESCRIPTION:
XS GIS Cut Line= 5
      2670126.52      6848183.13      2669595.29      6848165.77
      2669296.68      6848794.24       2669081.4      6849276.88
       2668817.5      6849759.55
#Sta/Elev= 30
  3782.1  377.94  4112.8  370.93  4324.3   360.9  4584.9  356.52  4670.6   354.1
  4828.7  354.37  4886.2  351.65  4897.5  353.18  4903.4  353.85  4908.9  350.62
  4926.1  352.42  4959.4   346.2  4959.8   345.7  4963.6   346.2  4999.8     352
  5155.7   352.4  5190.9  353.23  5196.3  355.07  5346.6  355.74  5364.4   358.9
  5400.1  359.93  5410.8  359.84  5416.3  357.53  5462.8  359.72    5486  359.91
  5491.5  358.15  5509.2  359.96  5559.6  358.87  5742.2  362.12    6088  365.75
#Mann= 7 ,-1 , 0
  3782.1     .05       0  4584.9    .075       0  4897.5     .05       0
  4959.4     .05       0  4963.6     .05       0  5155.7    .075       0
  5742.2     .05       0
Bank Sta=4959.4,4963.6
XS Rating Curve= 0 ,0
Exp/Cntr=0.3,0.1

Type RM Length L Ch R = 1 ,4348    ,576,576,576
BEGIN DESCRIPTION:
Mapping XS fd736ca0
END DESCRIPTION:
XS GIS Cut Line= 5
      2670143.76      6848131.31       2669497.9      6848103.53
      2669244.43      6848749.37      2668938.88      6849377.84
      2668727.09      6849714.62
#Sta/Elev= 30
  3675.1  377.19  4073.2  368.95    4320  356.58  4529.5  354.88  4842.1  352.77
  4920.5     351  4961.3  346.36  4961.6  345.86  4965.5  346.36  4999.2  350.57
  5106.1  351.06  5141.3  354.71    5187  354.81  5299.2  356.27  5316.2  353.19
  5406.3  353.71  5530.3  357.61  5726.4   358.9    5756  362.24  5951.3   362.2
  6024.3  363.96  6030.2  366.98  6045.5  364.28  6051.4  366.03  6066.7  363.97
  6072.6  366.36    6082  365.08  6087.9  367.08  6103.2  365.58    6112  367.01
#Mann= 7 ,-1 , 0
  3675.1     .05       0  4529.5    .075       0  4842.1     .05       0
  4961.3     .05       0  4965.5     .05       0    5187    .075       0
    5756     .05       0
Bank Sta=4961.3,4965.5
XS Rating Curve= 0 ,0
Exp/Cntr=0.3,0.1

Type RM Length L Ch R = 1 ,3772    ,484,484,484
BEGIN DESCRIPTION:
Kings Creek 32_3 5.0
END DESCRIPTION:
XS GIS Cut Line= 3
      2669897.22      6847922.97        2668976.        6848261.
      2668550.47      6848603.15
#Sta/Elev= 30
  4018.2  369.68  4289.7  363.94  4296.5  362.38  4350.7  361.62  4424.3  356.98
  4456.2  357.38  4477.5  355.54  4634.3  351.23  4679.9  348.81    4829  348.93
    4861  350.49  4867.6  348.61  4892.8  348.36  4903.6  349.56  4946.2  348.41
  4959.1  347.44  4978.2  343.61  4982.1  341.54  4982.5  341.04  4986.3  341.54
  4989.6  341.95  4996.8  345.36  5002.7  345.36  5006.7  347.36  5021.1   348.6
  5120.3  354.37  5190.5   356.9    5494   358.6  5512.2  360.53  5545.5  361.64
#Mann= 5 ,-1 , 0
  4018.2     .05       0  4982.1     .03       0  4986.3     .05       0
  5190.5      .1       0    5494     .05       0
Bank Sta=4982.1,4986.3
XS Rating Curve= 0 ,0
Exp/Cntr=0.3,0.1

Type RM Length L Ch R = 1 ,3288    ,620,620,620
BEGIN DESCRIPTION:
Mapping XS 7c0e03ec
END DESCRIPTION:
XS GIS Cut Line= 3
      2669675.02      6847353.52      2668900.68      6847808.39
      2668484.67      6848647.36
#Sta/Elev= 30
  4118.3  358.99  4261.8  357.05  4304.7  358.05  4357.5   356.3  4394.7  357.14
  4443.4  355.38    4502  355.39  4640.7  350.27  4818.3  348.15    4838  347.11
  4948.9  346.96  4992.3  346.76    5008  340.86  5011.7  340.69    5012  340.19
    5016  340.69  5016.2   343.1  5037.1   345.9    5222  348.37  5395.7   348.5
  5432.3  350.49    5463  355.72  5541.6  356.38  5619.9  357.19  5664.8  356.11
  5709.6  356.73  5729.2  358.38  5827.3  360.93  5947.4  362.14  5952.8  362.09
#Mann= 8 ,-1 , 0
  4118.3     .05       0  4818.3      .1       0  4948.9     .05       0
  5011.7     .03       0    5016     .05       0  5541.6      .1       0
  5729.2    .075       0  5947.4     .05       0
Bank Sta=5011.7,5016
XS Rating Curve= 0 ,0
Exp/Cntr=0.3,0.1

Type RM Length L Ch R = 1 ,2668    ,57,57,57
BEGIN DESCRIPTION:
Mapping XS dad99a24
END DESCRIPTION:
XS GIS Cut Line= 5
      2669612.54      6847176.45      2668515.27      6847134.78
       2668473.6      6847513.26      2668449.29      6847978.53
      2668442.35      6848596.26
#Sta/Elev= 30
  3523.9  358.52  3640.5  356.17  3920.7  354.61  3950.7  353.12  4100.9  351.24
    4301  350.47    4371  348.03  4593.1  347.95  4844.1  342.98  4980.4  343.46
  5002.7  343.44  5008.3     340  5008.7   339.5  5012.7     340  5030.5  343.02
    5049  343.97    5054  341.18  5210.7  346.33  5243.7  345.53  5300.9  347.32
  5330.9  346.56    5431   349.9    5436  347.96  5511.1  348.77  5521.1   350.7
  5531.1  349.43  5611.1  351.72  5682.7  355.33  5831.1  358.59  6086.4  361.62
#Mann= 6 ,-1 , 0
  3523.9     .05       0  4980.4     .12       0  5008.3     .07       0
  5012.7     .12       0  5243.7     .05       0  5682.7    .075       0
Bank Sta=5008.3,5012.7
XS Rating Curve= 0 ,0
Exp/Cntr=0.3,0.1

Type RM Length L Ch R = 1 ,2611    ,517,517,517
BEGIN DESCRIPTION:
Mapping XS 73cca679
END DESCRIPTION:
XS GIS Cut Line= 5
      2669605.52       6847082.7      2668438.88      6847113.95
      2668416.07      6847510.93      2668397.21      6848301.45
      2668376.38      6848575.72
#Sta/Elev= 30
  3435.3  358.33  3554.2  355.63  3774.9  355.06  4115.1  351.49  4165.1  349.66
  4565.2  348.73  4679.5  345.47  4849.8  343.73  4889.9  345.04  4899.9  343.66
  4978.7  342.76    4990  341.55  4995.3  339.18  4995.7  338.68  4999.7  339.18
  5020.1  339.21  5030.1  342.77  5060.1  344.34  5141.4  343.87  5390.2  348.75
  5460.2  352.11  5560.2  352.44  5580.2  355.48  5633.5  357.22  5660.3  356.14
  5722.3  357.35  5890.6  357.74  5910.6  359.31  6020.9  360.35  6065.8  361.51
#Mann= 7 ,-1 , 0
  3435.3     .05       0  4978.7     .12       0  4995.3     .07       0
  4999.7     .12       0  5141.4     .05       0  5722.3    .075       0
  6020.9     .05       0
Bank Sta=4995.3,4999.7
XS Rating Curve= 0 ,0
Exp/Cntr=0.3,0.1

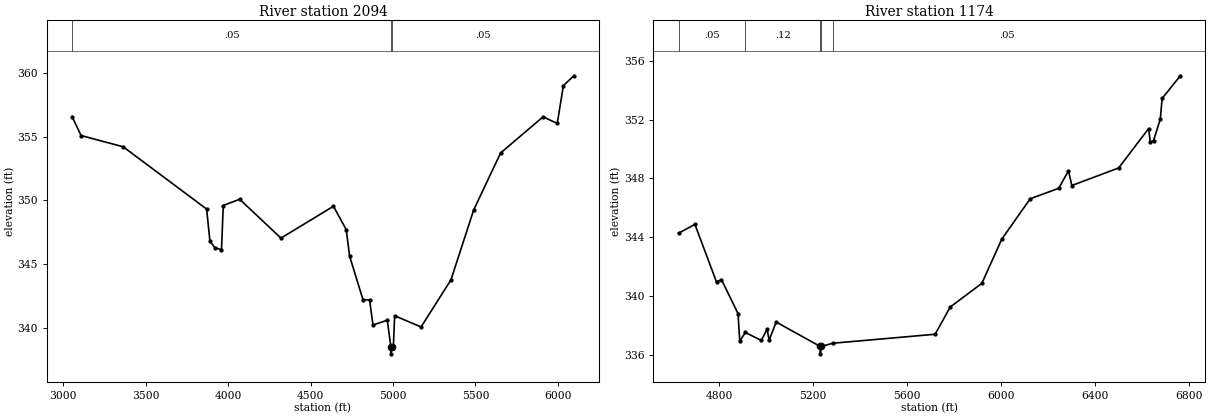
Type RM Length L Ch R = 1 ,2094    ,920,920,920
BEGIN DESCRIPTION:
Kings Creek 32_3 2.0
END DESCRIPTION:
XS GIS Cut Line= 4
      2669540.64      6846985.48       2667972.9      6847089.64
      2667915.95      6847461.11      2668295.82      6848490.67
#Sta/Elev= 30
    3053  356.58  3107.8  355.09  3362.9  354.21  3869.4  349.32  3889.5  346.79
  3919.5  346.29  3959.6  346.13  3970.3   349.6  4069.9  350.09  4320.4  347.04
  4638.8  349.54  4716.6   347.7  4736.9  345.62  4817.8  342.22  4858.3  342.18
  4878.5  340.22  4965.6   340.6  4987.6  338.46    4988  337.96    4992  338.46
  5002.6  338.55  5009.9  340.95  5170.4  340.07  5351.6  343.76  5490.2  349.27
  5652.8  353.72  5910.7  356.56  5996.7  356.04  6033.8  359.01  6097.4  359.78
#Mann= 3 ,-1 , 0
    3053     .05       0  4987.6     .03       0    4992     .05       0
Bank Sta=4987.6,4992
XS Rating Curve= 0 ,0
Exp/Cntr=0.3,0.1

Type RM Length L Ch R = 1 ,1174    ,0,0,0
BEGIN DESCRIPTION:
Kings Creek 32_3 1.0
END DESCRIPTION:
XS GIS Cut Line= 4
      2667415.64      6846771.91      2667153.87      6847038.89
       2667160.4      6847370.89      2668066.62      6848480.23
#Sta/Elev= 30
  4626.1  344.28  4695.9  344.88  4787.9  340.97    4809  341.13  4879.7  338.82
  4886.9  336.96    4911  337.54  4978.7     337  5003.6  337.77  5012.1  337.01
  5042.1  338.25    5230  336.59  5230.4  336.09  5234.4  336.59    5283  336.81
  5719.6  337.42  5784.1  339.27  5918.8  340.88  6003.7  343.88  6124.8  346.62
  6246.2  347.33  6287.8  348.52  6302.2  347.52  6501.7  348.71  6629.5  351.39
  6636.4  350.45  6650.3  350.57  6679.1  352.03    6687  353.43  6764.5  354.97
#Mann= 5 ,-1 , 0
  4626.1     .05       0    4911     .12       0    5230     .07       0
  5234.4     .12       0    5283     .05       0
Bank Sta=5230,5234.4
XS Rating Curve= 0 ,0
Exp/Cntr=0.3,0.1

Chan Stop Cuts=-1
Use User Specified Reach Order=0
Composite Channel Slope=5