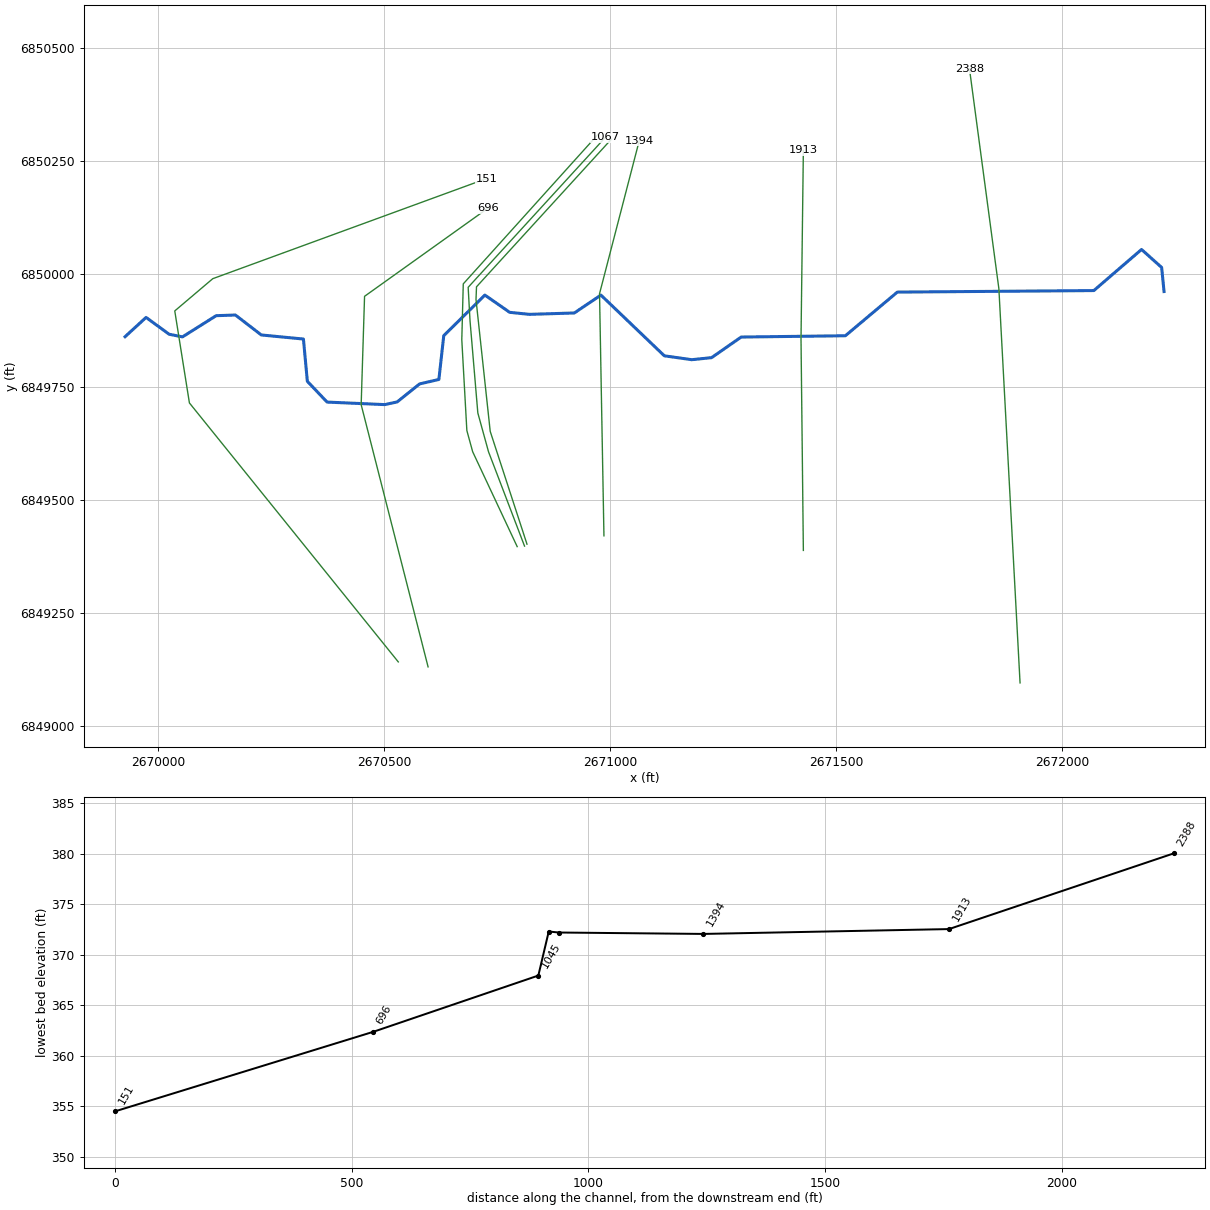
--- Kings Creek 32_3_1.prj (project) ---

Proj Title=Kings Creek 32_3_1 Base Level Engineering
Current Plan=p01
Default Exp/Contr=0.3,0.1
English Units
Geom File=g01
Flow File=f01
Plan File=p01
Y Axis Title=Elevation
X Axis Title(PF)=Main Channel Distance
X Axis Title(XS)=Station
BEGIN DESCRIPTION:
Kings Creek 32_3_1
END DESCRIPTION:
DSS Export Rating Curves= 0
DSS Export Rating Curve Sorted= 0
DSS Export Volume Flow Curves= 0
DXF OffsetX= 0
DXF OffsetY= 0
DXF ScaleX= 1
DXF ScaleY= 10

--- Kings Creek 32_3_1.p01 (plan) ---

Plan Title=Multiple Run
Short Identifier=Multiple
Geom File=g01
Flow File=f01
Subcritical Flow
K Sum by GR= 0
Std Step Tol= 0.01
Critical Tol= 0.01
Num of Std Step Trials= 20
Max Error Tol= 0.3
Flow Tol Ratio= 0.001
Split Flow NTrial= 30
Split Flow Tol= 0.02
Split Flow Ratio= 0.02
Log Output Level= 0
Friction Slope Method= 1
Unsteady Friction Slope Method= 2
Unsteady Bridges Friction Slope Method= 1
Parabolic Critical Depth
Global Vel Dist=  1 , 1 , 1
Global Log Level= 0
CheckData=True
Encroach Param= -1, 0, 0, 0
BEGIN DESCRIPTION:
Multiple Run
END DESCRIPTION:

--- Kings Creek 32_3_1.f01 (steady flow) ---

Flow Title=Multiple
Number of Profiles=7
Profile Names=10-year,25-year,50-year,1pct_min,100-year,1pct_plu,500-year
River Rch & RM= Kings Creek 32_3,Reach-1,2388
     115     138     154      86     171     341     211
Boundary for River Rch & Prof#=Kings Creek 32_3,Reach-1,1
Up Type=0
Dn Type=3
Dn Slope=0.005
Boundary for River Rch & Prof#=Kings Creek 32_3,Reach-1,2
Up Type=0
Dn Type=3
Dn Slope=0.005
Boundary for River Rch & Prof#=Kings Creek 32_3,Reach-1,3
Up Type=0
Dn Type=3
Dn Slope=0.005
Boundary for River Rch & Prof#=Kings Creek 32_3,Reach-1,4
Up Type=0
Dn Type=3
Dn Slope=0.005
Boundary for River Rch & Prof#=Kings Creek 32_3,Reach-1,5
Up Type=0
Dn Type=3
Dn Slope=0.005
Boundary for River Rch & Prof#=Kings Creek 32_3,Reach-1,6
Up Type=0
Dn Type=3
Dn Slope=0.005
Boundary for River Rch & Prof#=Kings Creek 32_3,Reach-1,7
Up Type=0
Dn Type=3
Dn Slope=0.005

--- Kings Creek 32_3_1.g01 (geometry) ---

Geom Title=Existing Conditions
Program Version=4.10

River Reach=Kings Creek 32_3,Reach-1
Reach XY= 30
        2672226.        6849961.      2672220.69      6850014.37
      2672176.17      6850054.17      2672070.56      6849963.19
      2671635.59      6849959.79      2671520.55      6849863.18
      2671289.92      6849860.31       2671224.4       6849814.7
      2671180.56      6849810.17      2671119.83      6849818.76
      2670979.42       6849953.2      2670920.55      6849913.58
      2670821.28      6849910.54      2670777.47      6849915.02
      2670722.57      6849953.21      2670631.55       6849863.4
      2670620.75      6849766.44      2670578.18       6849756.6
      2670528.39      6849716.68      2670501.09      6849710.76
      2670373.27      6849716.34      2670329.55      6849762.33
      2670320.89      6849855.89      2670227.66      6849864.92
      2670170.29      6849909.06      2670127.72       6849907.6
      2670053.17      6849860.67      2670023.68      6849866.48
      2669972.56      6849903.73        2669926.        6849861.

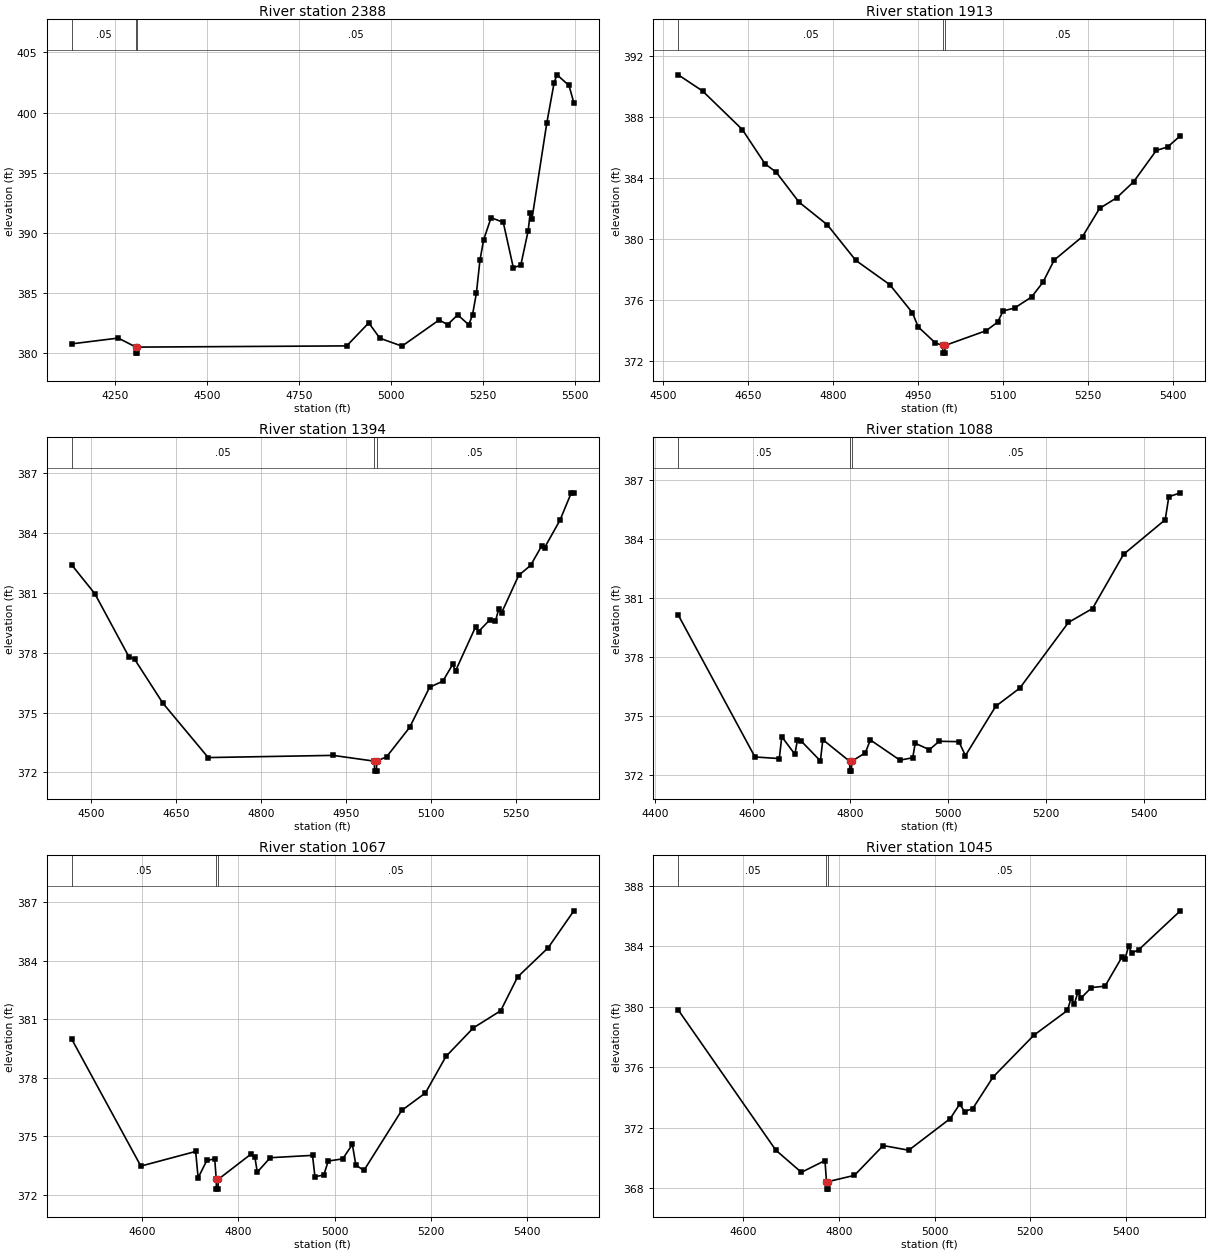
Type RM Length L Ch R = 1 ,2388    ,475,475,475
BEGIN DESCRIPTION:
Mapping XS c5689358
END DESCRIPTION:
XS GIS Cut Line= 3
      2671907.26      6849094.75      2671860.39      6849967.13
      2671795.29      6850454.06
#Sta/Elev= 30
  4132.5   380.8  4258.9  381.28    4307  380.53  4307.3  380.03  4310.8  380.03
    4311  380.53  4879.8  380.63  4939.9  382.54    4970  381.27  5030.2  380.61
  5131.1  382.78  5154.4   382.4  5181.6  383.21  5211.8  382.38  5221.9   383.2
  5232.5  385.02  5242.1  387.73  5252.2  389.44  5272.4  391.27  5305.5  390.89
  5332.9  387.12  5353.1  387.32  5373.2  390.18  5378.6  391.64  5383.6  391.18
  5423.7   399.1  5443.9  402.49  5451.6  403.13  5484.2  402.25  5497.4  400.81
#Mann= 3 ,-1 , 0
  4132.5     .05       0    4307     .03       0    4311     .05       0
Bank Sta=4307,4311
XS Rating Curve= 0 ,0
Exp/Cntr=0.3,0.1

Type RM Length L Ch R = 1 ,1913    ,519,519,519
BEGIN DESCRIPTION:
Mapping XS 2067222b
END DESCRIPTION:
XS GIS Cut Line= 3
      2671427.57      6849387.97      2671422.37      6849856.72
      2671427.57       6850273.4
#Sta/Elev= 30
    4527  390.75    4570  389.69    4640  387.17    4680  384.93    4700  384.37
    4740  382.42  4790.1  380.93  4840.1  378.61  4900.1  377.02  4940.1  375.18
  4950.1  374.26  4980.1  373.22  4993.4  373.04  4993.7  372.54  4997.2  372.54
  4997.4  373.04  5070.1  374.01  5090.1  374.56  5100.1   375.3  5120.1  375.49
  5150.1  376.21  5170.1  377.17  5190.1  378.63  5240.1  380.17  5270.1  382.01
  5300.1   382.7  5330.1  383.75  5370.1   385.8  5390.1  386.03  5412.5  386.76
#Mann= 3 ,-1 , 0
    4527     .05       0  4993.4     .03       0  4997.4     .05       0
Bank Sta=4993.4,4997.4
XS Rating Curve= 0 ,0
Exp/Cntr=0.3,0.1

Type RM Length L Ch R = 1 ,1394    ,306,306,306
BEGIN DESCRIPTION:
Mapping XS 5d3c316e
END DESCRIPTION:
XS GIS Cut Line= 3
      2670986.13      6849420.33      2670976.37      6849956.31
      2671064.25      6850294.82
#Sta/Elev= 30
  4466.6   382.4  4507.3  380.96  4567.3   377.8  4577.3  377.68  4627.3  375.47
  4707.3  372.74  4927.4  372.85  5000.5  372.56  5000.8  372.06  5004.3  372.06
  5004.5  372.56  5022.1  372.78  5062.6  374.25    5098  376.27  5121.2  376.57
  5138.6  377.41  5143.7  377.09  5179.1   379.3  5184.3  379.06  5203.8  379.64
  5214.1  379.58  5219.7  380.17  5224.9     380  5255.1  381.88  5276.1  382.38
  5295.7  383.36  5300.8  383.27  5327.8  384.64  5347.9  386.02  5352.4  386.02
#Mann= 3 ,-1 , 0
  4466.6     .05       0  5000.5     .04       0  5004.5     .05       0
Bank Sta=5000.5,5004.5
XS Rating Curve= 0 ,0
Exp/Cntr=0.3,0.1

Type RM Length L Ch R = 1 ,1088    ,21,21,21
BEGIN DESCRIPTION:
Mapping XS 7112895f
END DESCRIPTION:
XS GIS Cut Line= 5
      2670815.77      6849401.87       2670734.4      6849651.41
      2670702.93      6849943.29      2670704.02       6849971.5
      2671002.43      6850298.13
#Sta/Elev= 30
    4448  380.15  4604.9  372.92  4654.6  372.84  4659.8  373.95  4686.5  373.06
  4691.7  373.78  4699.5  373.73  4738.7  372.72  4743.7   373.8  4798.6   372.7
  4798.8   372.2  4802.3   372.2  4802.6   372.7  4830.6  373.13  4840.8  373.79
  4901.2  372.76  4927.5  372.88  4932.6  373.62  4961.5  373.29  4981.6  373.72
  5021.8   373.7  5035.3  372.99  5097.2   375.5  5146.6  376.43  5245.9  379.77
  5295.2  380.48  5358.7  383.24  5443.8     385  5451.2  386.17  5474.7  386.37
#Mann= 3 ,-1 , 0
    4448     .05       0  4798.6     .04       0  4802.6     .05       0
Bank Sta=4798.6,4802.6
XS Rating Curve= 0 ,0
Exp/Cntr=0.3,0.1

Type RM Length L Ch R = 1 ,1067    ,22,22,22
BEGIN DESCRIPTION:
Mapping XS 69f3e1c0
END DESCRIPTION:
XS GIS Cut Line= 6
      2670810.34      6849397.55      2670730.56      6849606.55
      2670706.95      6849692.32      2670689.59      6849897.52
      2670685.57      6849970.42      2670989.41      6850302.47
#Sta/Elev= 30
  4454.8  379.98  4598.1  373.48  4711.8  374.23    4717  372.88    4735  373.77
  4751.4  373.85  4754.6   372.8  4754.8   372.3  4758.3   372.3  4758.6   372.8
  4826.4  374.09  4834.7  373.94  4839.7  373.17  4866.5  373.91  4954.3  374.03
  4959.3  372.94  4977.7  373.02  4986.9  373.74  5016.9  373.85    5037  374.59
  5044.2  373.53    5061  373.26  5139.3  376.33  5188.6  377.23  5231.2   379.1
  5287.9  380.56  5344.7  381.44  5379.8  383.17  5443.3  384.67  5496.5  386.56
#Mann= 3 ,-1 , 0
  4454.8     .05       0  4754.6     .04       0  4758.6     .05       0
Bank Sta=4754.6,4758.6
XS Rating Curve= 0 ,0
Exp/Cntr=0.3,0.1

Type RM Length L Ch R = 1 ,1045    ,349,349,349
BEGIN DESCRIPTION:
Mapping XS 500ef8f3
END DESCRIPTION:
XS GIS Cut Line= 6
      2670794.08      6849396.41      2670695.49      6849606.55
      2670682.65      6849653.43      2670671.47      6849854.32
      2670674.72      6849978.01        2670972.      6850307.85
#Sta/Elev= 30
  4464.1  379.78    4668  370.52  4721.6  369.05  4770.9  369.83    4774  368.44
  4774.2  367.94  4777.7  367.94    4778  368.44  4832.5  368.85  4892.6  370.82
    4946  370.51  5032.7   372.6  5052.7  373.56  5062.7  373.06  5079.8  373.26
  5122.4  375.35  5207.6  378.11  5277.9  379.75  5285.4  380.56  5292.1  380.15
  5299.6  380.96  5306.3  380.57    5328  381.26  5356.4  381.35  5391.5  383.26
  5398.2  383.16  5405.7  383.99  5412.4  383.55  5426.6  383.75  5513.8  386.33
#Mann= 3 ,-1 , 0
  4464.1     .05       0    4774     .04       0    4778     .05       0
Bank Sta=4774,4778
XS Rating Curve= 0 ,0
Exp/Cntr=0.3,0.1

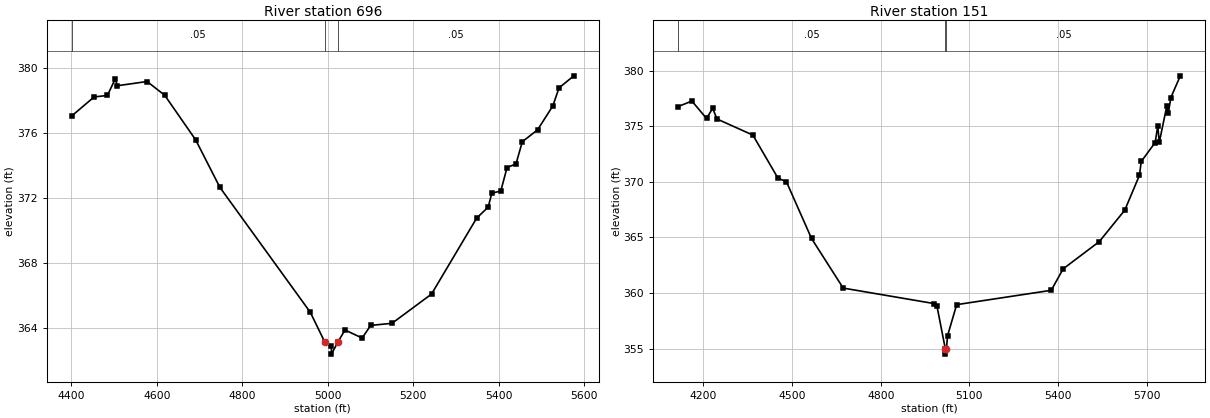
Type RM Length L Ch R = 1 ,696     ,545,545,545
BEGIN DESCRIPTION:
Kings Creek 32_3_1 2.0
END DESCRIPTION:
XS GIS Cut Line= 4
      2670596.84      6849130.19       2670448.7      6849710.58
      2670456.22      6849950.47      2670729.63      6850145.76
#Sta/Elev= 30
    4401  377.05  4453.4  378.22  4484.4  378.31  4502.7  379.33  4507.8  378.91
  4577.3  379.17  4618.6  378.32  4690.8  375.58  4747.8  372.64  4959.2  364.95
    4993  363.12  5008.4  362.87  5008.7  362.37 5024.44 363.144  5040.4  363.86
  5080.5  363.36  5100.5  364.14  5150.5  364.27  5242.9  366.07  5348.5  370.75
  5375.5  371.43  5384.1  372.29    5405  372.42  5419.7  373.87  5440.6  374.09
  5455.4  375.46    5491  376.19  5526.7  377.66  5541.4  378.78    5576  379.52
#Mann= 3 ,-1 , 0
    4401     .05       0    4993     .03       0 5024.44     .05       0
Bank Sta=4993,5024.44
XS Rating Curve= 0 ,0
Exp/Cntr=0.3,0.1

Type RM Length L Ch R = 1 ,151     ,0,0,0
BEGIN DESCRIPTION:
Kings Creek 32_3_1 1.0
END DESCRIPTION:
XS GIS Cut Line= 5
      2670530.87      6849141.22       2670068.5      6849714.46
      2670036.08      6849918.13      2670120.28      6849989.53
      2670725.96      6850210.99
#Sta/Elev= 30
  4115.3  376.78  4161.4  377.27    4211  375.71  4231.8  376.62  4246.2  375.66
  4367.7  374.21  4452.5  370.34  4481.3  370.01  4566.1  364.91  4673.2  360.45
  4979.9  359.06    4990  358.87  5018.4  355.01  5018.7  354.51  5022.4  355.01
  5026.1  356.16  5056.9  358.96  5376.8  360.25  5417.1  362.18  5539.3  364.63
  5625.5  367.46  5674.9  370.58  5681.3  371.84  5728.2  373.54    5737  375.03
  5742.3  373.57  5767.5  376.81  5772.9   376.2  5781.4  377.59  5813.3  379.54
#Mann= 3 ,-1 , 0
  4115.3     .05       0  5018.4      .6       0  5022.4     .05       0
Bank Sta=5018.4,5022.4
XS Rating Curve= 0 ,0
Exp/Cntr=0.3,0.1

Chan Stop Cuts=-1
Use User Specified Reach Order=0
Composite Channel Slope=5