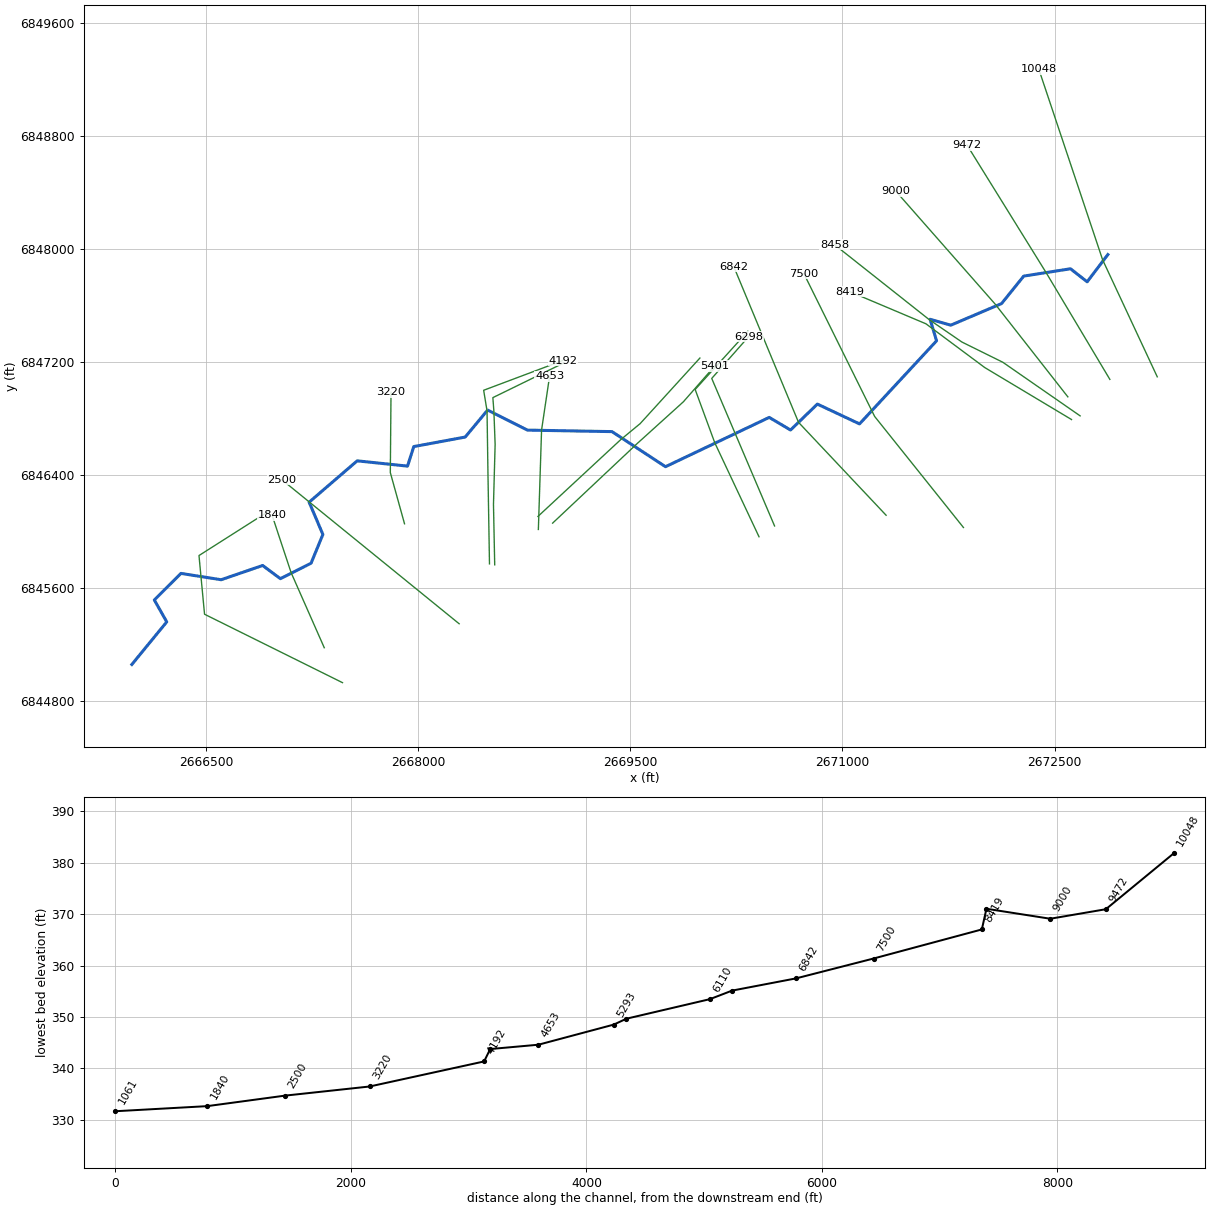
--- Kings Creek 32_4.prj (project) ---

Proj Title=Kings Creek 32_4 Base Level Engineering
Current Plan=p01
Default Exp/Contr=0.3,0.1
English Units
Geom File=g01
Flow File=f01
Plan File=p01
BEGIN DESCRIPTION:
Kings Creek 32_4
END DESCRIPTION:

--- Kings Creek 32_4.p01 (plan) ---

Plan Title=Multiple Run
Short Identifier=Multiple
Geom File=g01
Flow File=f01
Subcritical Flow
K Sum by GR= 0
Std Step Tol= 0.01
Critical Tol= 0.01
Num of Std Step Trials= 20
Max Error Tol= 0.3
Flow Tol Ratio= 0.001
Split Flow NTrial= 30
Split Flow Tol= 0.02
Split Flow Ratio= 0.02
Log Output Level= 0
Friction Slope Method= 1
Unsteady Friction Slope Method= 2
Unsteady Bridges Friction Slope Method= 1
Parabolic Critical Depth
Global Vel Dist=  1 , 1 , 1
Global Log Level= 0
CheckData=True
Encroach Param= -1, 0, 0, 0
BEGIN DESCRIPTION:
Multiple Run
END DESCRIPTION:

--- Kings Creek 32_4.f01 (steady flow) ---

Flow Title=Multiple
Number of Profiles=7
Profile Names=10-year,25-year,50-year,1pct_min,100-year,1pct_plu,500-year
River Rch & RM= Kings Creek 32_4,Reach-1,10048
     317     406     475     276     551    1100     740
Boundary for River Rch & Prof#=Kings Creek 32_4,Reach-1,1
Up Type=0
Dn Type=3
Dn Slope=0.005
Boundary for River Rch & Prof#=Kings Creek 32_4,Reach-1,2
Up Type=0
Dn Type=3
Dn Slope=0.005
Boundary for River Rch & Prof#=Kings Creek 32_4,Reach-1,3
Up Type=0
Dn Type=3
Dn Slope=0.005
Boundary for River Rch & Prof#=Kings Creek 32_4,Reach-1,4
Up Type=0
Dn Type=3
Dn Slope=0.005
Boundary for River Rch & Prof#=Kings Creek 32_4,Reach-1,5
Up Type=0
Dn Type=3
Dn Slope=0.005
Boundary for River Rch & Prof#=Kings Creek 32_4,Reach-1,6
Up Type=0
Dn Type=3
Dn Slope=0.005
Boundary for River Rch & Prof#=Kings Creek 32_4,Reach-1,7
Up Type=0
Dn Type=3
Dn Slope=0.005

--- Kings Creek 32_4.g01 (geometry) ---

Geom Title=Existing Conditions

River Reach=Kings Creek 32_4,Reach-1
Reach XY= 30
      2672876.00      6847961.00      2672729.62      6847768.48
      2672611.94      6847860.84      2672281.26      6847808.90
      2672124.55      6847614.53      2671765.38      6847461.60
      2671619.28      6847503.52      2671665.04      6847351.00
      2671120.44      6846763.26      2670822.66      6846903.40
      2670632.67      6846719.96      2670482.13      6846809.22
      2669748.79      6846460.43      2669370.48      6846708.65
      2668772.78      6846719.27      2668491.24      6846861.16
      2668332.75      6846670.14      2667969.32      6846602.86
      2667925.00      6846464.54      2667569.24      6846501.88
      2667229.45      6846209.51      2667326.67      6845981.08
      2667243.06      6845777.49      2667025.92      6845668.30
      2666900.86      6845761.55      2666607.54      6845660.76
      2666323.57      6845705.48      2666134.96      6845517.67
      2666222.90      6845362.65      2665976.00      6845061.00

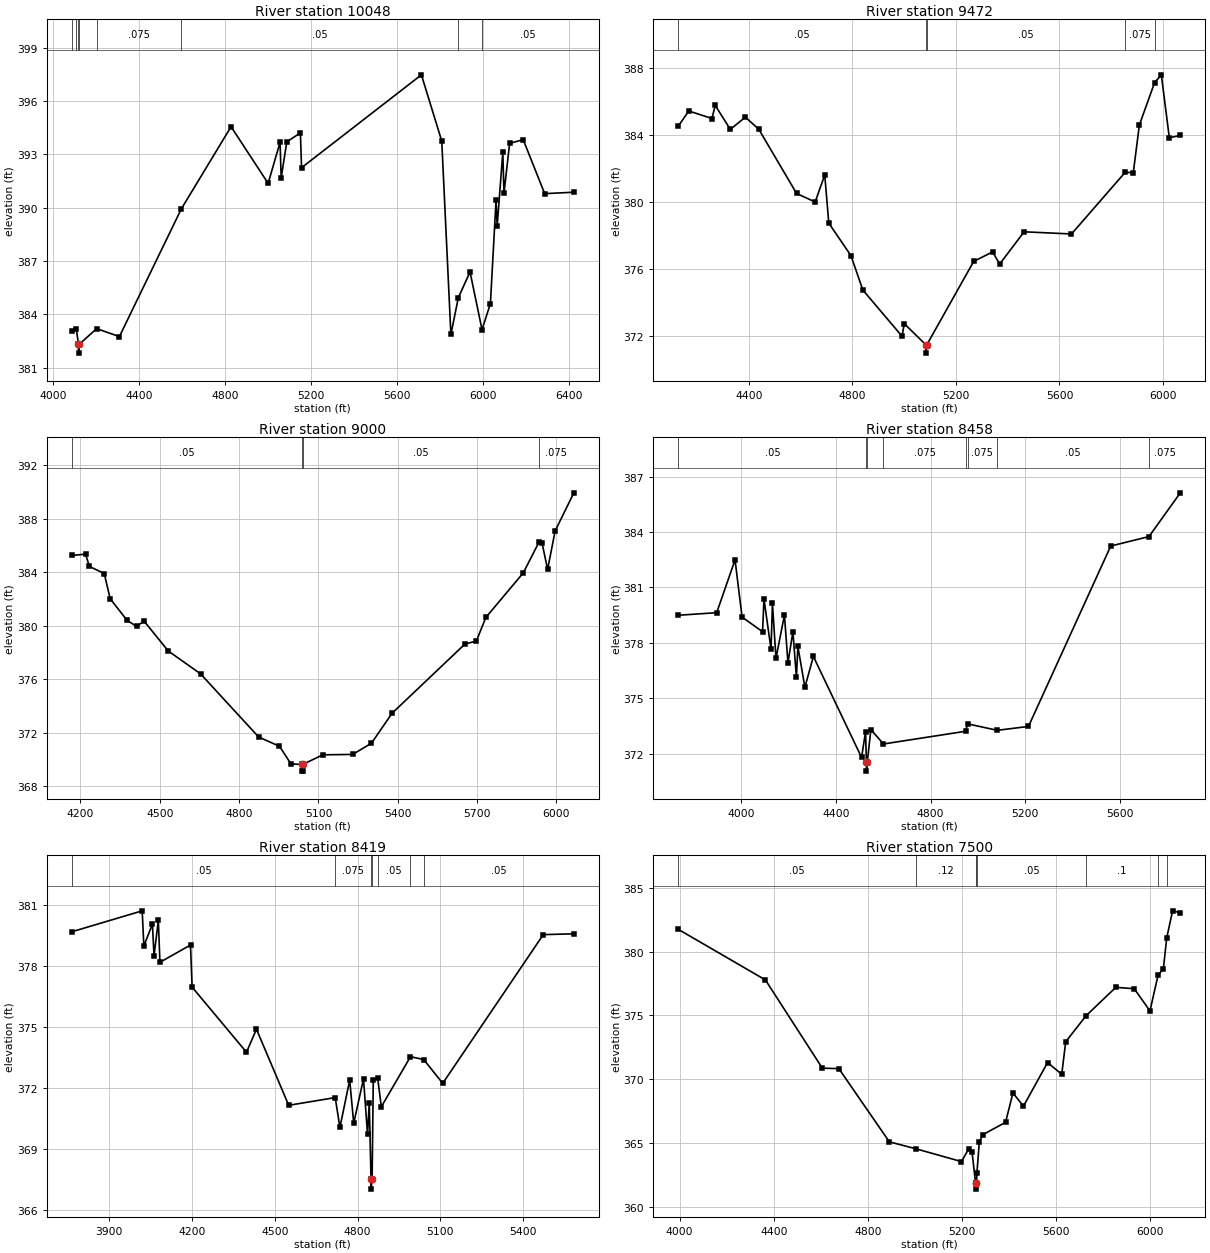
Type RM Length L Ch R = 1,10048,576,576,576
BEGIN DESCRIPTION:
Kings Creek 32_4 20.0
END DESCRIPTION:
XS GIS Cut Line= 3
      2673225.26      6847096.35      2672838.95      6847924.48
      2672387.60      6849273.68
#Sta/Elev= 30
  4086.2  383.04  4107.1  383.19  4117.4  382.31  4117.7  381.81  4121.4  382.31
  4201.9  383.19  4307.8  382.74  4596.0  389.93  4827.4  394.56  5000.0  391.37
  5055.5  393.68  5060.7  391.68  5087.0  393.71  5150.2  394.21  5155.5  392.25
  5713.3  397.48  5808.0  393.75  5850.5  382.86  5885.3  384.94  5939.6  386.38
  5995.4  383.13  6034.4  384.60  6060.7  390.43  6065.9  388.96  6092.2  393.12
  6097.5  390.81  6123.8  393.62  6187.0  393.83  6287.0  390.79  6422.7  390.87
#Mann=8,-1,0
  4086.2   0.075       0  4107.1    0.05       0  4117.4    0.05       0
  4121.4    0.05       0  4201.9   0.075       0  4596.0    0.05       0
  5885.3     0.1       0  5995.4    0.05       0
Bank Sta=4117.4,4121.4
Exp/Cntr=0.3,0.1

Type RM Length L Ch R = 1,9472,472,472,472
BEGIN DESCRIPTION:
Mapping XS 9b6a88b1
END DESCRIPTION:
XS GIS Cut Line= 3
      2672890.19      6847078.12      2672439.68      6847833.32
      2671880.68      6848735.51
#Sta/Elev= 30
  4126.5  384.52  4167.3  385.43  4256.8  384.98  4269.6  385.76  4327.8  384.33
  4386.0  385.06  4437.8  384.34  4584.0  380.50  4655.8  379.99  4692.8  381.61
  4708.4  378.73  4794.0  376.79  4840.1  374.73  4991.5  371.97  5000.3  372.72
  5083.5  371.46  5083.7  370.96  5087.5  371.46  5268.5  376.44  5341.8  377.01
  5368.9  376.28  5463.4  378.21  5646.6  378.08  5854.4  381.77  5885.4  381.74
  5908.9  384.59  5967.9  387.13  5993.9  387.59  6024.7  383.83  6067.2  383.97
#Mann=5,-1,0
  4126.5    0.05       0  5083.5    0.03       0  5087.5    0.05       0
  5854.4   0.075       0  5967.9    0.05       0
Bank Sta=5083.5,5087.5
Exp/Cntr=0.3,0.1

Type RM Length L Ch R = 1,9000,542,542,542
BEGIN DESCRIPTION:
Kings Creek 32_4 18.0
END DESCRIPTION:
XS GIS Cut Line= 3
      2672593.06      6846954.70      2672079.48      6847610.54
      2671375.97      6848411.03
#Sta/Elev= 30
  4167.0  385.25  4219.2  385.35  4233.7  384.43  4289.8  383.90  4312.3  382.01
  4376.5  380.39  4411.8  379.95  4440.7  380.33  4532.1  378.10  4654.1  376.39
  4873.9  371.66  4952.5  370.97  4995.9  369.65  5036.5  369.61  5036.8  369.11
  5040.3  369.11  5040.5  369.61  5116.3  370.33  5229.3  370.36  5300.4  371.20
  5378.2  373.44  5654.3  378.63  5697.0  378.84  5732.8  380.61  5874.5  383.95
  5933.9  386.25  5945.6  386.17  5966.5  384.21  5995.0  387.09  6065.7  389.94
#Mann=4,-1,0
  4167.0    0.05       0  5036.5    0.03       0  5040.5    0.05       0
  5933.9   0.075       0
Bank Sta=5036.5,5040.5
Exp/Cntr=0.3,0.1

Type RM Length L Ch R = 1,8458,39,39,39
BEGIN DESCRIPTION:
Mapping XS 60bf30d8
END DESCRIPTION:
XS GIS Cut Line= 5
      2672679.86      6846820.18      2672133.42      6847199.42
      2671844.29      6847342.41      2671612.13      6847501.62
      2670943.76      6848031.11
#Sta/Elev= 30
  3733.7  379.49  3896.2  379.63  3973.8  382.49  4003.5  379.39  4090.0  378.60
  4096.1  380.37  4125.8  377.65  4131.9  380.13  4146.7  377.16  4182.5  379.50
  4197.4  376.91  4218.3  378.60  4233.2  376.12  4239.3  377.80  4269.0  375.59
  4304.8  377.26  4508.5  371.79  4525.4  373.19  4528.9  371.55  4529.2  371.05
  4532.9  371.55  4547.8  373.30  4601.1  372.52  4948.8  373.21  4956.2  373.61
  5082.3  373.26  5213.9  373.47  5561.6  383.24  5723.1  383.75  5855.6  386.12
#Mann=8,-1,0
  3733.7    0.05       0  4528.9    0.07       0  4532.9    0.05       0
  4601.1   0.075       0  4948.8    0.05       0  4956.2   0.075       0
  5082.3    0.05       0  5723.1   0.075       0
Bank Sta=4528.9,4532.9
Exp/Cntr=0.3,0.1

Type RM Length L Ch R = 1,8419,919,919,919
BEGIN DESCRIPTION:
Mapping XS 1e205763
END DESCRIPTION:
XS GIS Cut Line= 4
      2672619.07      6846794.15      2672005.76      6847161.86
      2671590.43      6847471.23      2671050.11      6847699.66
#Sta/Elev= 30
  3763.9  379.68  4019.2  380.71  4025.1  378.98  4056.2  380.06  4062.0  378.50
  4077.6  380.24  4083.4  378.18  4194.2  379.03  4200.0  376.96  4397.1  373.76
  4433.3  374.89  4550.1  371.15  4718.7  371.53  4735.7  370.06  4771.1  372.39
  4785.7  370.27  4821.2  372.45  4835.8  369.72  4842.0  371.28  4848.4  367.53
  4848.6  367.03  4852.4  367.53  4856.6  372.37  4872.7  372.47  4885.8  371.08
  4991.5  373.54  5039.3  373.40  5108.3  372.23  5472.7  379.54  5583.5  379.58
#Mann=7,-1,0
  3763.9    0.05       0  4718.7   0.075       0  4848.4    0.07       0
  4852.4   0.075       0  4872.7    0.05       0  4991.5   0.075       0
  5039.3    0.05       0
Bank Sta=4848.4,4852.4
Exp/Cntr=0.3,0.1

Type RM Length L Ch R = 1,7500,658,658,658
BEGIN DESCRIPTION:
Kings Creek 32_4 15.0
END DESCRIPTION:
XS GIS Cut Line= 3
      2671855.18      6846030.26      2671227.13      6846816.26
      2670727.01      6847826.55
#Sta/Elev= 30
  3993.9  381.76  4364.3  377.79  4606.1  370.87  4676.5  370.83  4890.9  365.09
  5002.6  364.55  5197.4  363.54  5228.5  364.55  5242.2  364.32  5257.1  361.88
  5257.3  361.38  5261.1  361.88  5263.2  362.68  5273.1  365.05  5287.1  365.64
  5384.7  366.62  5416.1  368.92  5460.9  367.89  5563.2  371.31  5623.5  370.39
  5640.3  372.94  5727.3  374.99  5853.4  377.21  5931.4  377.10  5998.4  375.36
  6032.9  378.18  6055.2  378.65  6069.6  381.09  6094.5  383.21  6127.3  383.06
#Mann=8,-1,0
  3993.9    0.05       0  5002.6    0.12       0  5257.1    0.03       0
  5261.1    0.12       0  5263.2    0.05       0  5727.3     0.1       0
  6032.9    0.05       0  6069.6   0.075       0
Bank Sta=5257.1,5261.1
Exp/Cntr=0.3,0.1

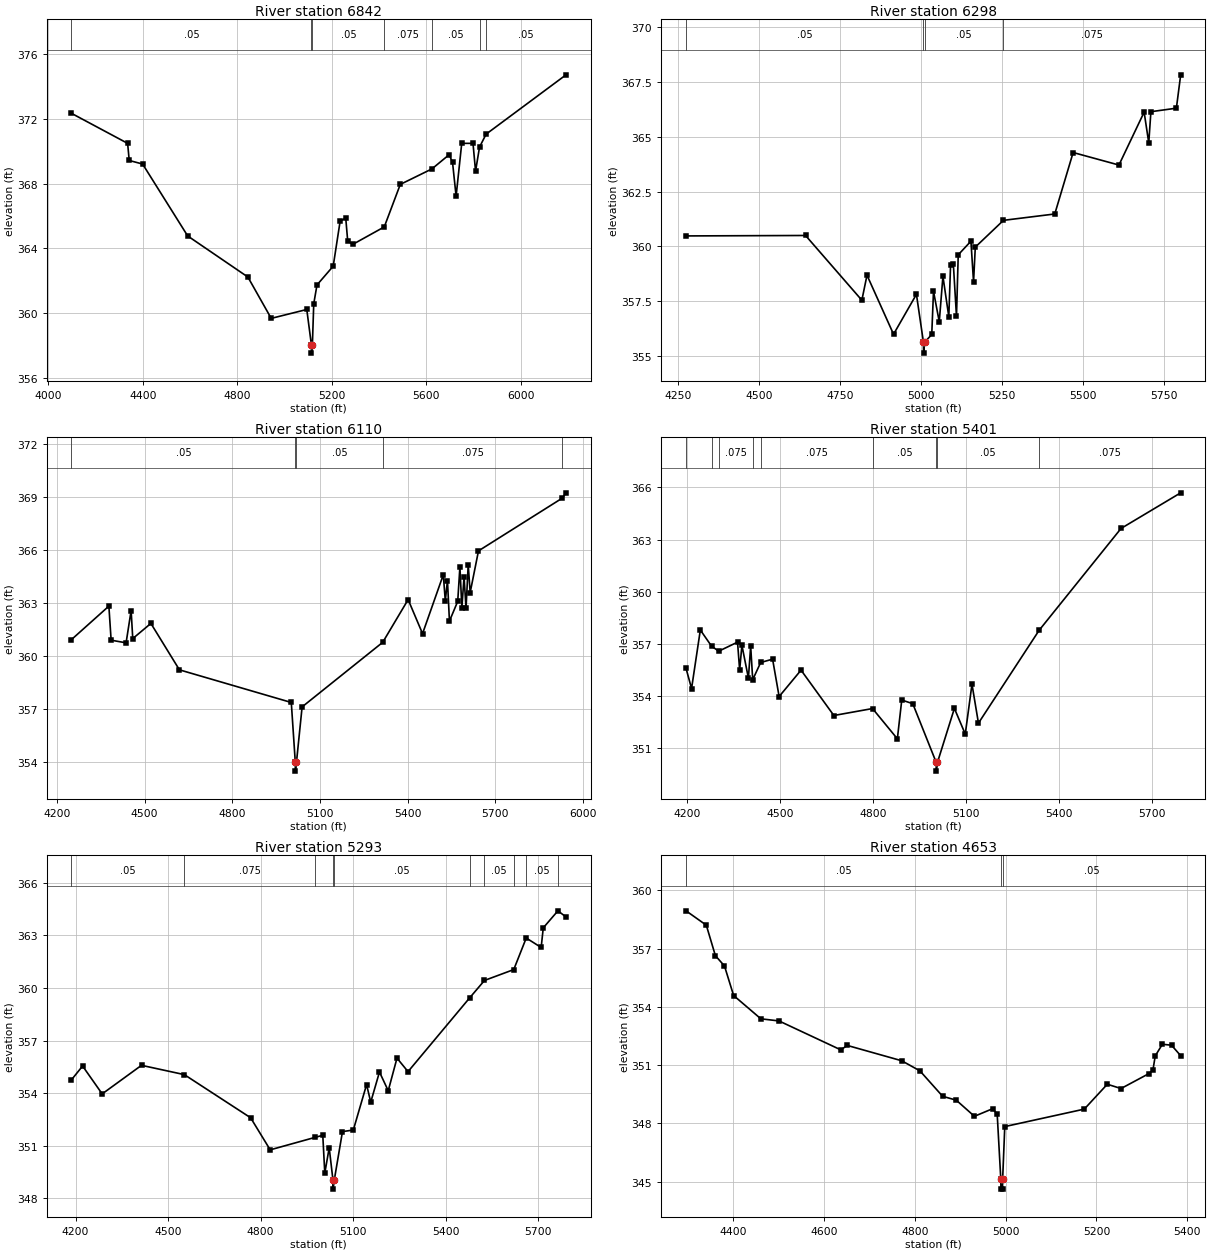
Type RM Length L Ch R = 1,6842,544,544,544
BEGIN DESCRIPTION:
Kings Creek 32_4 14.0
END DESCRIPTION:
XS GIS Cut Line= 3
      2671308.33      6846117.05      2670689.33      6846774.09
      2670231.94      6847874.84
#Sta/Elev= 30
  4097.3  372.36  4335.4  370.50  4342.2  369.44  4398.9  369.22  4589.8  364.77
  4844.6  362.23  4943.5  359.67  5094.1  360.22  5113.8  358.02  5114.0  357.52
  5117.8  358.02  5123.6  360.57  5137.4  361.74  5206.0  362.90  5235.3  365.68
  5259.1  365.88  5267.4  364.46  5289.0  364.25  5422.3  365.33  5490.1  367.96
  5624.2  368.92  5697.2  369.80  5711.4  369.32  5726.5  367.23  5750.3  370.50
  5798.0  370.50  5808.9  368.78  5825.7  370.27  5853.6  371.07  6192.0  374.74
#Mann=7,-1,0
  4097.3    0.05       0  5113.8    0.03       0  5117.8    0.05       0
  5422.3   0.075       0  5624.2    0.05       0  5825.7   0.075       0
  5853.6    0.05       0
Bank Sta=5113.8,5117.8
Exp/Cntr=0.3,0.1

Type RM Length L Ch R = 1,6298,188,188,188
BEGIN DESCRIPTION:
Mapping XS edeb35bf
END DESCRIPTION:
XS GIS Cut Line= 4
      2670519.74      6846041.34      2670236.26      6846707.34
      2670075.67      6847084.95      2670336.11      6847380.12
#Sta/Elev= 30
  4274.1  360.48  4643.2  360.50  4817.1  357.55  4833.0  358.69  4915.0  356.00
  4985.7  357.82  5007.3  355.64  5007.6  355.14  5011.3  355.64  5033.0  355.99
  5038.4  357.96  5056.2  356.57  5067.5  358.64  5085.7  356.80  5091.1  359.15
  5099.7  359.20  5109.4  356.81  5114.8  359.62  5154.0  360.24  5162.1  358.38
  5167.5  359.97  5254.5  361.19  5413.0  361.48  5469.7  364.28  5611.2  363.71
  5689.0  366.12  5703.3  364.72  5709.9  366.14  5788.6  366.30  5801.9  367.82
#Mann=4,-1,0
  4274.1    0.05       0  5007.3    0.03       0  5011.3    0.05       0
  5254.5   0.075       0
Bank Sta=5007.3,5011.3
Exp/Cntr=0.3,0.1

Type RM Length L Ch R = 1,6110,709,709,709
BEGIN DESCRIPTION:
Mapping XS e2d7639e
END DESCRIPTION:
XS GIS Cut Line= 4
      2670409.78      6845964.95      2670097.37      6846629.22
      2669958.48      6847006.82      2670331.36      6847418.72
#Sta/Elev= 30
  4249.5  360.93  4377.7  362.83  4385.4  360.90  4436.6  360.75  4453.8  362.58
  4459.4  360.99  4521.4  361.85  4619.0  359.22  5001.7  357.37  5015.4  353.98
  5015.7  353.48  5019.4  353.98  5038.7  357.12  5314.5  360.78  5401.4  363.20
  5450.7  361.27  5521.7  364.61  5528.5  363.13  5535.9  364.28  5542.7  361.98
  5571.0  363.10  5578.5  365.05  5585.2  362.74  5592.7  364.50  5599.4  362.70
  5606.9  365.18  5613.6  363.60  5642.0  365.96  5928.7  368.95  5941.5  369.25
#Mann=5,-1,0
  4249.5    0.05       0  5015.4    0.03       0  5019.4    0.05       0
  5314.5   0.075       0  5928.7    0.05       0
Bank Sta=5015.4,5019.4
Exp/Cntr=0.3,0.1

Type RM Length L Ch R = 1,5401,108,108,108
BEGIN DESCRIPTION:
Mapping XS 8597b052
END DESCRIPTION:
XS GIS Cut Line= 4
      2668950.80      6846061.23      2669548.04      6846623.74
      2669874.43      6846918.88      2670096.67      6847172.38
#Sta/Elev= 30
  4196.0  355.59  4213.8  354.43  4242.1  357.80  4278.3  356.87  4301.5  356.58
  4362.3  357.10  4369.1  355.49  4376.4  356.92  4397.4  355.03  4404.7  356.87
  4411.3  354.94  4437.0  355.93  4475.5  356.12  4496.6  353.97  4567.4  355.49
  4673.4  352.88  4798.3  353.28  4878.5  351.54  4892.7  353.77  4928.3  353.56
  5004.0  350.18  5004.2  349.68  5008.0  350.18  5062.7  353.29  5097.8  351.81
  5119.5  354.68  5140.4  352.44  5336.3  357.78  5600.9  363.64  5793.6  365.69
#Mann=9,-1,0
  4196.0    0.05       0  4278.3     0.1       0  4301.5   0.075       0
  4411.3     0.1       0  4437.0   0.075       0  4798.3    0.05       0
  5004.0    0.05       0  5008.0    0.05       0  5336.3   0.075       0
Bank Sta=5004,5008
Exp/Cntr=0.3,0.1

Type RM Length L Ch R = 1,5293,640,640,640
BEGIN DESCRIPTION:
Mapping XS 9d5c1065
END DESCRIPTION:
XS GIS Cut Line= 4
      2668847.19      6846108.73      2669430.50      6846650.37
      2669569.39      6846764.96      2669992.00      6847229.14
#Sta/Elev= 30
  4186.3  354.76  4222.6  355.55  4286.1  353.96  4413.6  355.59  4552.4  355.06
  4767.4  352.60  4830.9  350.77  4976.2  351.48  5001.4  351.60  5007.9  349.44
  5022.2  350.89  5034.5  349.03  5034.8  348.53  5038.5  349.03  5065.2  351.81
  5100.4  351.90  5143.4  354.49  5156.9  353.49  5185.2  355.21  5213.6  354.14
  5242.0  356.00  5277.8  355.23  5477.3  359.43  5525.7  360.43  5620.6  361.05
  5661.1  362.85  5709.5  362.31  5716.3  363.43  5763.8  364.40  5790.1  364.05
#Mann=10,-1,0
  4186.3    0.05       0  4552.4   0.075       0  4976.2    0.05       0
  5034.5    0.05       0  5038.5    0.05       0  5477.3   0.075       0
  5525.7    0.05       0  5620.6   0.075       0  5661.1    0.05       0
  5763.8   0.075       0
Bank Sta=5034.5,5038.5
Exp/Cntr=0.3,0.1

Type RM Length L Ch R = 1,4653,409,409,409
BEGIN DESCRIPTION:
Kings Creek 32_4 9.0
END DESCRIPTION:
XS GIS Cut Line= 3
      2668849.98      6846016.40      2668872.66      6846719.54
      2668929.32      6847100.85
#Sta/Elev= 30
  4296.5  358.95  4341.1  358.21  4361.1  356.64  4381.1  356.11  4401.2  354.59
  4461.2  353.39  4501.2  353.28  4637.3  351.79  4651.3  352.02  4771.3  351.23
  4811.4  350.71  4861.4  349.40  4891.4  349.20  4931.4  348.37  4971.4  348.76
  4981.5  348.49  4989.5  345.12  4989.7  344.62  4993.2  344.62  4993.5  345.12
  4998.2  347.84  5173.3  348.74  5223.9  350.02  5254.2  349.80  5314.9  350.56
  5324.4  350.75  5329.5  351.48  5345.2  352.08  5365.4  352.03  5385.5  351.49
#Mann=3,-1,0
  4296.5    0.05       0  4989.5    0.03       0  4993.5    0.05       0
Bank Sta=4989.5,4993.5
Exp/Cntr=0.3,0.1

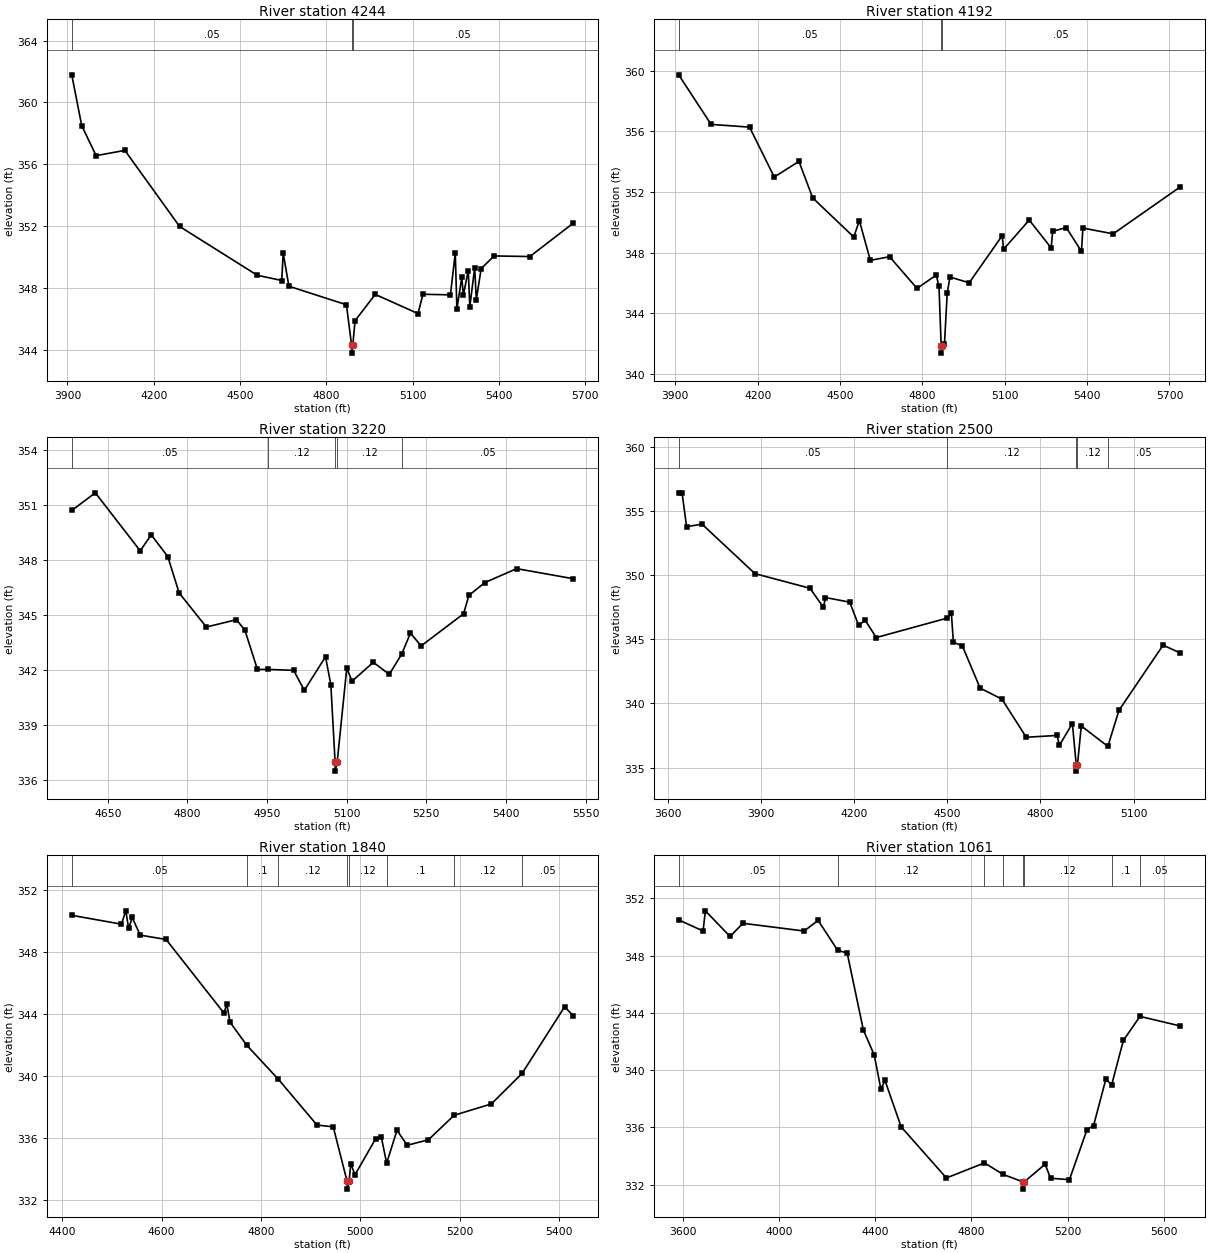
Type RM Length L Ch R = 1,4244,52,52,52
BEGIN DESCRIPTION:
Mapping XS 1f02ffb9
END DESCRIPTION:
XS GIS Cut Line= 6
      2668541.38      6845766.32      2668532.70      6846193.89
      2668544.37      6846619.36      2668535.65      6846850.81
      2668528.36      6846949.10      2669031.96      6847195.49
#Sta/Elev= 30
  3915.1  361.79  3949.8  358.50  3999.8  356.56  4099.8  356.90  4289.9  351.98
  4559.9  348.82  4645.2  348.48  4650.2  350.26  4670.0  348.11  4870.1  346.91
  4888.1  344.28  4888.4  343.78  4892.1  344.28  4900.1  345.88  4970.2  347.58
  5119.0  346.34  5136.0  347.59  5231.6  347.55  5248.5  350.26  5254.1  346.63
  5271.0  348.68  5276.6  347.54  5293.5  349.12  5299.1  346.79  5316.0  349.32
  5321.6  347.24  5338.5  349.25  5383.6  350.07  5507.8  350.03  5659.2  352.20
#Mann=3,-1,0
  3915.1    0.05       0  4888.1    0.03       0  4892.1    0.05       0
Bank Sta=4888.1,4892.1
Exp/Cntr=0.3,0.1

Type RM Length L Ch R = 1,4192,972,972,972
BEGIN DESCRIPTION:
Mapping XS 607f1c1f
END DESCRIPTION:
XS GIS Cut Line= 5
      2668504.49      6845772.89      2668493.64      6846415.24
      2668487.13      6846855.78      2668463.26      6847001.18
      2669022.09      6847211.28
#Sta/Elev= 30
  3912.2  359.73  4030.3  356.46  4170.3  356.28  4260.4  352.99  4350.4  354.02
  4400.4  351.61  4550.0  349.03  4570.4  350.11  4610.4  347.49  4680.4  347.73
  4780.4  345.64  4850.4  346.52  4860.4  345.78  4868.4  341.87  4868.7  341.37
  4872.4  341.87  4880.4  341.97  4890.4  345.33  4900.4  346.39  4970.5  346.01
  5090.7  349.12  5095.8  348.22  5189.1  350.15  5269.2  348.31  5274.5  349.41
  5324.3  349.65  5379.4  348.08  5384.7  349.62  5495.0  349.24  5739.6  352.34
#Mann=3,-1,0
  3912.2    0.05       0  4868.4    0.03       0  4872.4    0.05       0
Bank Sta=4868.4,4872.4
Exp/Cntr=0.3,0.1

Type RM Length L Ch R = 1,3220,720,720,720
BEGIN DESCRIPTION:
Kings Creek 32_4 6.0
END DESCRIPTION:
XS GIS Cut Line= 3
      2667903.81      6846056.70      2667803.44      6846418.70
      2667808.38      6846987.93
#Sta/Elev= 30
  4582.1  350.70  4626.5  351.66  4711.1  348.50  4731.8  349.37  4763.0  348.19
  4784.3  346.21  4835.6  344.35  4892.4  344.75  4908.3  344.17  4931.8  342.04
  4952.5  342.04  5000.1  341.99  5020.1  340.90  5060.1  342.73  5070.1  341.21
  5078.1  337.00  5078.3  336.50  5082.1  337.00  5100.1  342.11  5110.1  341.40
  5150.1  342.43  5180.1  341.77  5203.3  342.86  5220.1  344.02  5240.1  343.32
  5320.1  345.07  5330.1  346.07  5360.1  346.77  5420.1  347.53  5527.0  346.98
#Mann=5,-1,0
  4582.1    0.05       0  4952.5    0.12       0  5078.1    0.07       0
  5082.1    0.12       0  5203.3    0.05       0
Bank Sta=5078.1,5082.1
Exp/Cntr=0.3,0.1

Type RM Length L Ch R = 1,2500,660,660,660
BEGIN DESCRIPTION:
Kings Creek 32_4 5.0
END DESCRIPTION:
XS GIS Cut Line= 3
      2668290.06      6845349.29      2667230.25      6846211.13
      2667035.71      6846369.26
#Sta/Elev= 30
  3634.0  356.41  3645.2  356.36  3659.5  353.77  3709.1  353.97  3880.0  350.11
  4057.4  348.97  4100.5  347.48  4107.0  348.25  4185.3  347.89  4214.0  346.08
  4234.8  346.49  4270.8  345.13  4498.4  346.64  4512.8  347.03  4519.3  344.76
  4548.0  344.49  4605.5  341.19  4675.8  340.33  4754.1  337.36  4853.2  337.50
  4861.2  336.74  4902.8  338.43  4915.2  335.22  4915.4  334.72  4919.2  335.22
  4931.5  338.24  5017.2  336.65  5052.9  339.46  5195.2  344.54  5250.7  343.92
#Mann=5,-1,0
  3634.0    0.05       0  4498.4    0.12       0  4915.2    0.07       0
  4919.2    0.12       0  5017.2    0.05       0
Bank Sta=4915.2,4919.2
Exp/Cntr=0.3,0.1

Type RM Length L Ch R = 1,1840,779,779,779
BEGIN DESCRIPTION:
Mapping XS e3329ebe
END DESCRIPTION:
XS GIS Cut Line= 3
      2667336.44      6845179.70      2667102.07      6845710.94
      2666967.30      6846117.86
#Sta/Elev= 30
  4419.3  350.36  4519.1  349.79  4528.2  350.65  4533.7  349.51  4541.0  350.22
  4557.0  349.08  4609.1  348.80  4725.7  344.04  4731.2  344.64  4737.7  343.46
  4771.7  341.96  4834.8  339.78  4912.6  336.82  4945.4  336.70  4973.3  333.18
  4973.5  332.68  4977.3  333.18  4980.7  334.33  4989.1  333.60  5030.8  335.94
  5042.1  336.05  5052.8  334.36  5073.7  336.48  5094.2  335.51  5137.0  335.87
  5188.7  337.45  5263.4  338.18  5325.3  340.15  5410.8  344.45  5428.6  343.87
#Mann=8,-1,0
  4419.3    0.05       0  4771.7     0.1       0  4834.8    0.12       0
  4973.3    0.07       0  4977.3    0.12       0  5052.8     0.1       0
  5188.7    0.12       0  5325.3    0.05       0
Bank Sta=4973.3,4977.3
Exp/Cntr=0.3,0.1

Type RM Length L Ch R = 1,1061,0,0,0
BEGIN DESCRIPTION:
Kings Creek 32_4 4.0
END DESCRIPTION:
XS GIS Cut Line= 4
      2667465.41      6844932.61      2666490.09      6845416.67
      2666450.79      6845831.87      2666940.28      6846143.56
#Sta/Elev= 30
  3582.4  350.49  3683.9  349.71  3693.4  351.12  3796.0  349.33  3849.7  350.25
  4104.1  349.71  4162.3  350.45  4242.9  348.38  4283.4  348.16  4350.6  342.79
  4395.5  341.06  4423.5  338.66  4440.3  339.28  4507.5  336.04  4695.7  332.47
  4854.1  333.52  4931.2  332.72  5015.1  332.19  5015.4  331.69  5019.1  332.19
  5106.3  333.43  5128.7  332.45  5207.4  332.35  5280.2  335.83  5307.9  336.13
  5358.9  339.37  5383.0  338.97  5431.7  342.07  5500.7  343.75  5668.6  343.08
#Mann=8,-1,0
  3582.4    0.05       0  4242.9    0.12       0  4854.1     0.1       0
  4931.2    0.12       0  5015.1    0.07       0  5019.1    0.12       0
  5383.0     0.1       0  5500.7    0.05       0
Bank Sta=5015.1,5019.1
Exp/Cntr=0.3,0.1

Chan Stop Cuts=-1