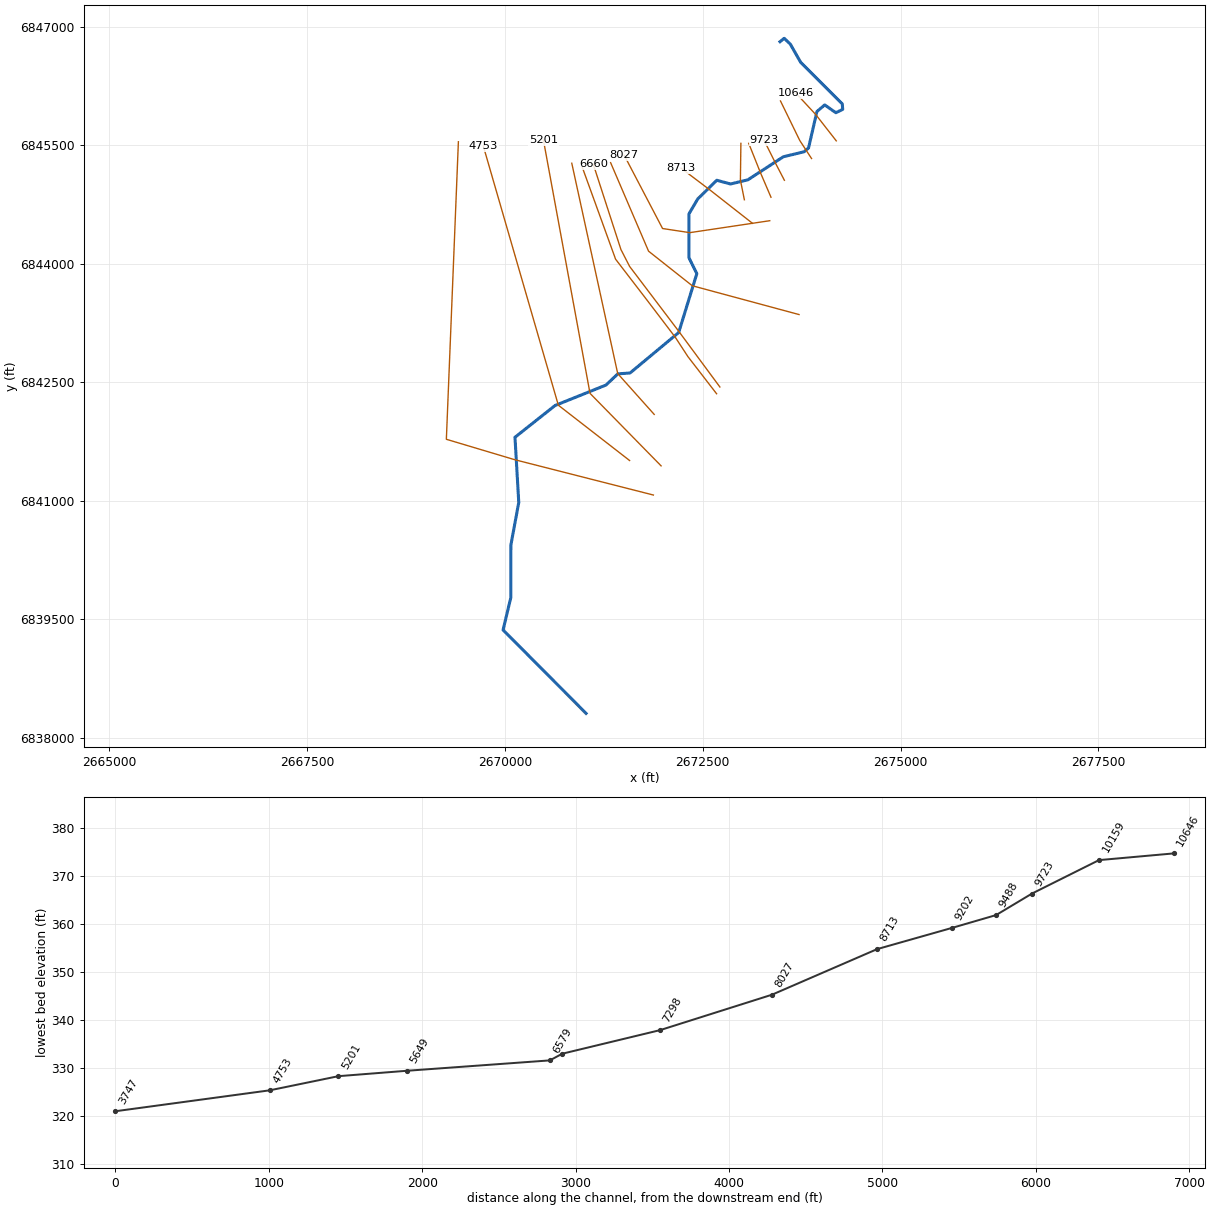
--- Kings Creek 33.prj (project) ---

Proj Title=Kings Creek 33 Base Level Engineering
Current Plan=p01
Default Exp/Contr=0.3,0.1
English Units
Geom File=g01
Flow File=f01
Plan File=p01
Y Axis Title=Elevation
X Axis Title(PF)=Main Channel Distance
X Axis Title(XS)=Station
BEGIN DESCRIPTION:
Kings Creek 33
END DESCRIPTION:
DSS Export Rating Curves= 0
DSS Export Rating Curve Sorted= 0
DSS Export Volume Flow Curves= 0
DXF OffsetX= 0
DXF OffsetY= 0
DXF ScaleX= 1
DXF ScaleY= 10

--- Kings Creek 33.p01 (plan) ---

Plan Title=Multiple Run
Short Identifier=Multiple
Geom File=g01
Flow File=f01
Subcritical Flow
K Sum by GR= 0
Std Step Tol= 0.01
Critical Tol= 0.01
Num of Std Step Trials= 20
Max Error Tol= 0.3
Flow Tol Ratio= 0.001
Split Flow NTrial= 30
Split Flow Tol= 0.02
Split Flow Ratio= 0.02
Log Output Level= 0
Friction Slope Method= 1
Unsteady Friction Slope Method= 2
Unsteady Bridges Friction Slope Method= 1
Parabolic Critical Depth
Global Vel Dist=  1 , 1 , 1
Global Log Level= 0
CheckData=True
Encroach Param= -1, 0, 0, 0
BEGIN DESCRIPTION:
Multiple Run
END DESCRIPTION:

--- Kings Creek 33.f01 (steady flow) ---

Flow Title=Multiple
Number of Profiles=7
Profile Names=10-year,25-year,50-year,1pct_min,100-year,1pct_plu,500-year
River Rch & RM= Kings Creek 33,Reach-1,10646
     195     242     276     157     313     624     401
River Rch & RM= Kings Creek 33,Reach-1,8713
     478     629     748     442     881    1758    1221
Boundary for River Rch & Prof#=Kings Creek 33,Reach-1,1
Up Type=0
Dn Type=3
Dn Slope=0.005
Boundary for River Rch & Prof#=Kings Creek 33,Reach-1,2
Up Type=0
Dn Type=3
Dn Slope=0.005
Boundary for River Rch & Prof#=Kings Creek 33,Reach-1,3
Up Type=0
Dn Type=3
Dn Slope=0.005
Boundary for River Rch & Prof#=Kings Creek 33,Reach-1,4
Up Type=0
Dn Type=3
Dn Slope=0.005
Boundary for River Rch & Prof#=Kings Creek 33,Reach-1,5
Up Type=0
Dn Type=3
Dn Slope=0.005
Boundary for River Rch & Prof#=Kings Creek 33,Reach-1,6
Up Type=0
Dn Type=3
Dn Slope=0.005
Boundary for River Rch & Prof#=Kings Creek 33,Reach-1,7
Up Type=0
Dn Type=3
Dn Slope=0.005

--- Kings Creek 33.g01 (geometry) ---

Geom Title=Existing Conditions
Program Version=4.10

River Reach=Kings Creek 33  ,Reach-1
Reach XY= 30
        2673476.        6846811.      2673529.35      6846853.76
      2673606.22      6846781.17      2673736.78      6846551.32
       2674262.9       6846024.2      2674268.66      6845954.57
       2674182.1      6845912.57      2674041.36      6846011.11
      2673942.63      6845927.72      2673836.99      6845466.44
      2673779.69      6845418.27      2673518.18      6845354.81
      2673070.14      6845063.07        2672851.       6845010.6
      2672677.28      6845057.63      2672436.53      6844820.77
      2672325.55      6844631.24      2672326.39      6844076.16
      2672425.62      6843876.28      2672196.41      6843130.77
      2671582.18      6842618.83      2671427.47      6842607.46
      2671278.43      6842466.52      2670634.62      6842207.16
      2670128.06      6841805.15      2670175.93      6840981.03
      2670076.07      6840440.97      2670075.48      6839776.22
      2669977.62      6839367.03        2671026.        6838311.

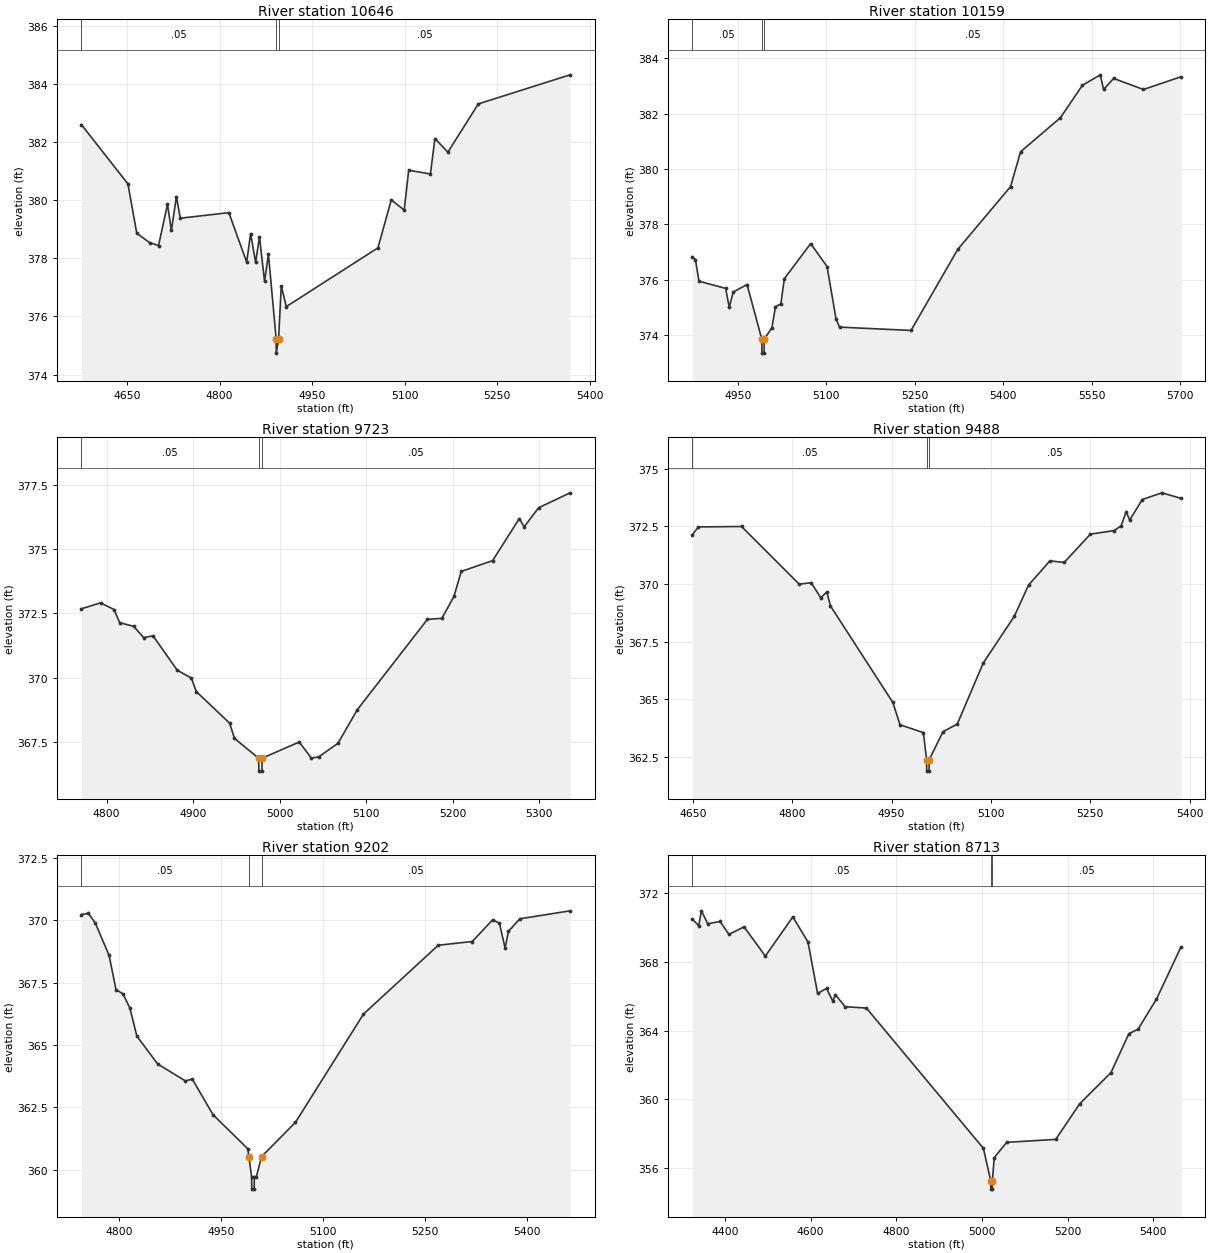
Type RM Length L Ch R = 1 ,10646   ,487,487,487
BEGIN DESCRIPTION:
Kings Creek 33 22.0
END DESCRIPTION:
XS GIS Cut Line= 3
      2674187.24      6845556.29      2673926.31      6845890.88
      2673675.98      6846161.02
#Sta/Elev= 30
  4575.7   382.6  4651.2  380.56  4665.6  378.86  4686.4  378.54  4700.9  378.44
  4715.4  379.86  4721.7  378.96  4729.9  380.12  4736.2  379.38  4814.9  379.57
  4843.8  377.87  4850.2  378.85  4858.3  377.86  4864.6  378.74  4872.8  377.21
  4879.1  378.14  4891.6  375.24  4891.8  374.74  4895.6  375.24  4899.9  377.05
  4908.1  376.34  5056.7  378.36  5078.3  380.01  5099.3  379.66  5106.6  381.03
  5141.8   380.9  5149.1  382.12  5170.1  381.65  5219.5  383.31  5368.3  384.31
#Mann= 3 ,-1 , 0
  4575.7     .05       0  4891.6     .03       0  4895.6     .05       0
Bank Sta=4891.6,4895.6
XS Rating Curve= 0 ,0
Exp/Cntr=0.3,0.1

Type RM Length L Ch R = 1 ,10159   ,436,436,436
BEGIN DESCRIPTION:
Kings Creek 33 21.0
END DESCRIPTION:
XS GIS Cut Line= 3
      2673874.77      6845332.73        2673726.        6845561.
      2673482.22      6846061.41
#Sta/Elev= 30
  4872.4  376.82  4877.8  376.72  4883.8  375.94  4929.1  375.68  4935.1     375
    4942  375.55  4965.4  375.82  4990.4  373.84  4990.7  373.34  4994.2  373.34
  4994.4  373.84  5007.5  374.26  5013.6  375.02  5022.7  375.12  5028.6  376.03
  5073.3   377.3  5101.1  376.47  5116.2  374.59  5122.2  374.28  5243.5  374.16
  5322.8  377.09  5412.4  379.36  5429.4  380.62    5497  381.85  5534.2  383.02
  5564.6   383.4  5570.2  382.87  5587.2  383.27  5637.8  382.87  5701.5  383.33
#Mann= 3 ,-1 , 0
  4872.4     .05       0  4990.4     .04       0  4994.4     .05       0
Bank Sta=4990.4,4994.4
XS Rating Curve= 0 ,0
Exp/Cntr=0.3,0.1

Type RM Length L Ch R = 1 ,9723    ,235,235,235
BEGIN DESCRIPTION:
Kings Creek 33 20.0
END DESCRIPTION:
XS GIS Cut Line= 3
      2673531.83      6845057.39        2673426.        6845261.
      2673275.99      6845561.02
#Sta/Elev= 30
  4770.8  372.68    4793  372.91  4808.7  372.65  4815.1  372.14  4831.2     372
  4842.9  371.56  4853.7  371.63  4881.5   370.3    4898  369.99  4903.6  369.47
  4942.2  368.24  4947.8  367.65  4975.7  366.88    4976  366.38  4979.5  366.38
  4979.7  366.88  5022.6  367.51  5036.6  366.89    5045  366.93  5067.4  367.46
  5089.7  368.76  5170.8  372.27  5187.5  372.31  5201.5  373.16  5209.9  374.13
  5246.2  374.55    5277  376.18  5282.6  375.86  5299.3   376.6  5335.7  377.18
#Mann= 3 ,-1 , 0
  4770.8     .05       0  4975.7     .04       0  4979.7     .05       0
Bank Sta=4975.7,4979.7
XS Rating Curve= 0 ,0
Exp/Cntr=0.3,0.1

Type RM Length L Ch R = 1 ,9488    ,286,286,286
BEGIN DESCRIPTION:
Kings Creek 33 19.0
END DESCRIPTION:
XS GIS Cut Line= 3
      2673362.47      6844842.58        2673226.        6845161.
       2673081.2      6845524.92
#Sta/Elev= 30
    4649  372.13  4658.2  372.47  4723.4  372.49  4810.5  369.99  4828.6  370.05
  4843.1   369.4  4852.2  369.65  4857.6  369.05  4951.9  364.86  4962.8  363.89
  4998.1  363.55  5002.9  362.38  5003.1  361.88  5006.6  361.88  5006.9  362.38
  5027.7  363.59  5049.2  363.92  5088.5  366.57  5135.3  368.59  5156.9  369.95
  5189.2     371  5210.7  370.93  5250.4  372.16    5286  372.31  5296.8  372.52
  5304.3  373.13  5309.7  372.77  5328.6  373.66  5358.3  373.95  5387.1  373.71
#Mann= 3 ,-1 , 0
    4649     .05       0  5002.9     .03       0  5006.9     .05       0
Bank Sta=5002.9,5006.9
XS Rating Curve= 0 ,0
Exp/Cntr=0.3,0.1

Type RM Length L Ch R = 1 ,9202    ,489,489,489
BEGIN DESCRIPTION:
Kings Creek 33 18.0
END DESCRIPTION:
XS GIS Cut Line= 3
        2673026.      6844810.98        2672976.        6845061.
      2672982.24      6845524.88
#Sta/Elev= 30
  4744.7  370.23  4754.9  370.28  4765.1   369.9  4785.5  368.59  4795.7  367.22
  4805.9  367.05  4816.1  366.48  4826.3  365.36  4856.9  364.24  4897.7  363.56
  4907.9  363.63  4938.5   362.2  4989.5  360.84 4991.16 360.508  4995.1  359.72
  4995.4  359.22  4998.9  359.22  4999.1  359.72  5002.2  359.72  5009.7  360.52
  5059.7   361.9  5159.7  366.24  5269.7     369  5319.7  369.15  5349.7  370.02
  5359.7  369.88    5368  368.89    5373  369.56  5389.7  370.06  5463.6  370.38
#Mann= 3 ,-1 , 0
  4744.7     .05       0 4991.16     .05       0  5009.7     .05       0
Bank Sta=4991.16,5009.7
XS Rating Curve= 0 ,0
Exp/Cntr=0.3,0.1

Type RM Length L Ch R = 1 ,8713    ,686,686,686
BEGIN DESCRIPTION:
Kings Creek 33 16.0
END DESCRIPTION:
XS GIS Cut Line= 3
      2673128.32      6844513.05      2672596.47      6844930.64
        2672226.        6845211.
#Sta/Elev= 30
  4323.8  370.49  4338.9  370.09  4345.3  370.96  4359.8  370.21  4388.7  370.34
  4409.5  369.59  4444.7  370.03  4494.4  368.33  4558.6  370.61  4593.9  369.15
  4616.4  366.16  4637.2  366.45  4651.7  365.72  4658.1  366.08  4680.6  365.39
  4730.3  365.31  5003.4  357.16  5020.4  355.29  5020.7  354.79  5024.2  354.79
  5024.4  355.29  5028.7  356.62  5057.8  357.51  5172.2  357.68  5228.5  359.76
  5301.2  361.56  5342.9  363.82  5364.3  364.08  5407.4  365.83  5464.6  368.86
#Mann= 3 ,-1 , 0
  4323.8     .05       0  5020.4     .08       0  5024.4     .05       0
Bank Sta=5020.4,5024.4
XS Rating Curve= 0 ,0
Exp/Cntr=0.3,0.1

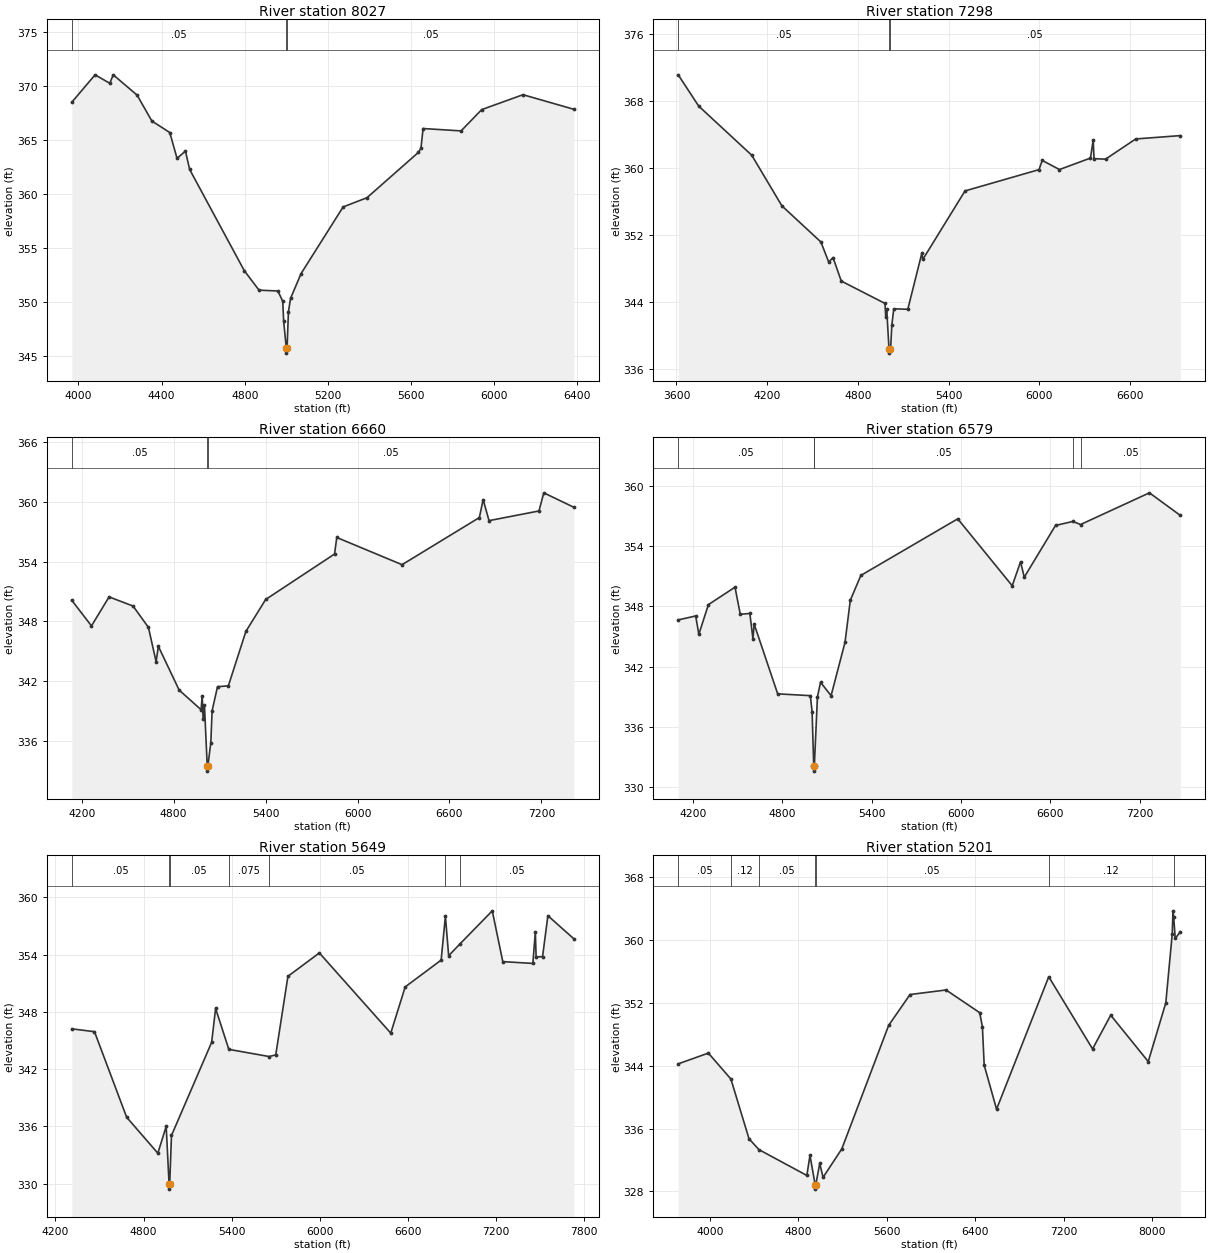
Type RM Length L Ch R = 1 ,8027    ,729,729,729
BEGIN DESCRIPTION:
Mapping XS 8e1b42a5
END DESCRIPTION:
XS GIS Cut Line= 4
      2673346.84      6844545.75      2672336.41      6844394.71
      2671992.66      6844446.79      2671508.29      6845373.85
#Sta/Elev= 30
  3967.8   368.5  4079.9  371.04  4150.6  370.26  4167.4  371.04  4282.1  369.16
  4352.9  366.77  4439.2   365.7  4474.2  363.31  4514.6  363.98  4534.9  362.28
  4797.8  352.91  4868.5  351.11  4959.5  351.03  4982.8  350.07  4987.1  348.24
  4999.6  345.78  4999.8  345.28  5003.6  345.78  5010.1   349.1  5020.2  350.34
  5070.8  352.64  5273.1  358.81  5388.3  359.67  5635.2  363.86  5647.6  364.24
  5657.8  366.07  5840.7  365.85  5939.8  367.82  6138.5   369.2  6383.1  367.85
#Mann= 3 ,-1 , 0
  3967.8     .05       0  4999.6     .06       0  5003.6     .05       0
Bank Sta=4999.6,5003.6
XS Rating Curve= 0 ,0
Exp/Cntr=0.3,0.1

Type RM Length L Ch R = 1 ,7298    ,638,638,638
BEGIN DESCRIPTION:
Mapping XS 1e480e49
END DESCRIPTION:
XS GIS Cut Line= 4
       2673716.6      6843358.25      2672367.66      6843722.83
      2671815.57      6844160.33      2671336.39      6845280.16
#Sta/Elev= 30
  3611.5   371.1  3746.8  367.37  4097.5  361.51  4296.9  355.47  4554.8  351.16
  4606.6  348.76  4635.1   349.3  4689.4   346.5  4978.5  343.83  4983.7  342.16
  4989.8  343.19  5005.1   338.4  5005.4   337.9  5009.1   338.4  5015.6  338.41
  5023.7  341.21  5036.5  343.19  5129.4  343.13  5222.4  349.83  5228.7  349.08
  5507.6  357.25  5996.8  359.79  6018.5  360.89  6132.2   359.8  6337.2  361.17
  6355.3  363.33  6360.8   361.1    6437  361.04  6636.5  363.45  6931.3  363.85
#Mann= 3 ,-1 , 0
  3611.5     .05       0  5005.1     .04       0  5009.1     .05       0
Bank Sta=5005.1,5009.1
XS Rating Curve= 0 ,0
Exp/Cntr=0.3,0.1

Type RM Length L Ch R = 1 ,6660    ,81,81,81
BEGIN DESCRIPTION:
Mapping XS 813b252c
END DESCRIPTION:
XS GIS Cut Line= 5
      2672716.62      6842441.58      2672190.57      6843155.12
      2671575.99      6843967.62      2671466.62      6844181.16
       2671118.2      6845257.61
#Sta/Elev= 30
    4135  350.12  4263.6  347.55  4378.5  350.46  4535.1  349.54  4635.3   347.4
  4685.4  343.96  4700.1   345.5  4835.8  341.11  4979.1  339.14  4986.2  340.53
  4992.4  338.23  5000.8  339.62  5019.1  333.48  5019.4  332.98  5023.1  333.48
  5042.5  335.84  5050.8  339.04  5086.2  341.45    5157  341.54  5271.4     347
  5400.4   350.2  5849.9  354.76  5864.4  356.42  6290.5  353.69    6795  358.42
  6819.6  360.22  6858.1  358.11  7183.9  359.08  7215.5   360.9  7411.6  359.45
#Mann= 3 ,-1 , 0
    4135     .05       0  5019.1     .04       0  5023.1     .05       0
Bank Sta=5019.1,5023.1
XS Rating Curve= 0 ,0
Exp/Cntr=0.3,0.1

Type RM Length L Ch R = 1 ,6579    ,930,930,930
BEGIN DESCRIPTION:
Mapping XS 4a544f88
END DESCRIPTION:
XS GIS Cut Line= 6
      2672674.98      6842356.11      2672312.48      6842826.49
      2672154.13      6843069.67        2671826.      6843501.96
      2671398.92      6844059.25      2670977.04      6845225.94
#Sta/Elev= 30
  4102.1  346.66  4219.4  347.05  4240.3  345.22  4304.6  348.18  4483.1  349.92
  4518.4  347.22  4582.7   347.3  4603.5  344.77  4611.7  346.24  4769.5  339.29
  4988.7  339.11  5000.4  337.52  5011.5  332.09  5011.8  331.59  5015.5  332.09
  5036.3  338.99  5057.2  340.44  5127.9  339.11  5221.5  344.43  5256.8  348.61
  5327.6  351.09  5977.9  356.73  6343.5  350.06  6399.5  352.45  6424.2  350.91
  6634.1  356.07  6750.8  356.47  6802.2  356.16  7264.3  359.32  7471.6  357.07
#Mann= 5 ,-1 , 0
  4102.1     .05       0  5011.5     .04       0  5015.5     .05       0
  6750.8     .12       0  6802.2     .05       0
Bank Sta=5011.5,5015.5
XS Rating Curve= 0 ,0
Exp/Cntr=0.3,0.1

Type RM Length L Ch R = 1 ,5649    ,448,448,448
BEGIN DESCRIPTION:
Kings Creek 33 9.0
END DESCRIPTION:
XS GIS Cut Line= 3
       2671887.2      6842094.34        2671426.        6842611.
      2670845.53       6845273.6
#Sta/Elev= 30
  4311.6  346.22  4466.2  345.92  4685.2  336.96  4897.6  333.19  4954.4  336.01
  4974.1  329.93  4974.4  329.43  4978.1  329.93  4990.4  335.05  5263.8  344.81
  5290.7  348.35  5380.7  344.07  5654.8  343.32  5700.1  343.49    5783  351.72
  5996.9  354.17    6483  345.77  6581.2  350.61    6826  353.42  6854.9  358.02
  6877.1  353.88  6954.6  355.12    7174  358.58  7245.6  353.26  7450.3  353.07
  7467.3  356.38  7472.4  353.74  7516.3  353.78  7552.6  358.07  7729.3  355.65
#Mann= 7 ,-1 , 0
  4311.6     .05       0  4974.1     .04       0  4978.1     .05       0
  5380.7    .075       0  5654.8     .05       0  6854.9     .12       0
  6954.6     .05       0
Bank Sta=4974.1,4978.1
XS Rating Curve= 0 ,0
Exp/Cntr=0.3,0.1

Type RM Length L Ch R = 1 ,5201    ,448,448,448
BEGIN DESCRIPTION:
Kings Creek 33 8.0
END DESCRIPTION:
XS GIS Cut Line= 3
      2671973.98      6841443.33        2671076.        6842361.
       2670487.5      6845566.29
#Sta/Elev= 30
    3712  344.24  3984.7  345.61  4188.4  342.31  4352.4  334.71  4441.8  333.33
  4875.7  330.04    4904   332.6  4951.6   328.8  4951.8   328.3  4955.6   328.8
  4992.4  331.57  5022.5   329.8    5192  333.42  5616.1  349.14  5809.3  353.06
  6135.4  353.64  6439.7  350.75  6464.2  348.95  6480.3  344.07  6592.2  338.47
  7064.4  355.32  7460.8  346.14  7625.2  350.43  7964.7  344.53  8123.5     352
  8181.7  360.76  8188.4  363.71  8195.2  362.88  8208.8  360.19  8254.8  361.05
#Mann= 7 ,-1 , 0
    3712     .05       0  4188.4     .12       0  4441.8     .05       0
  4951.6     .04       0  4955.6     .05       0  7064.4     .12       0
  8195.2     .05       0
Bank Sta=4951.6,4955.6
XS Rating Curve= 0 ,0
Exp/Cntr=0.3,0.1

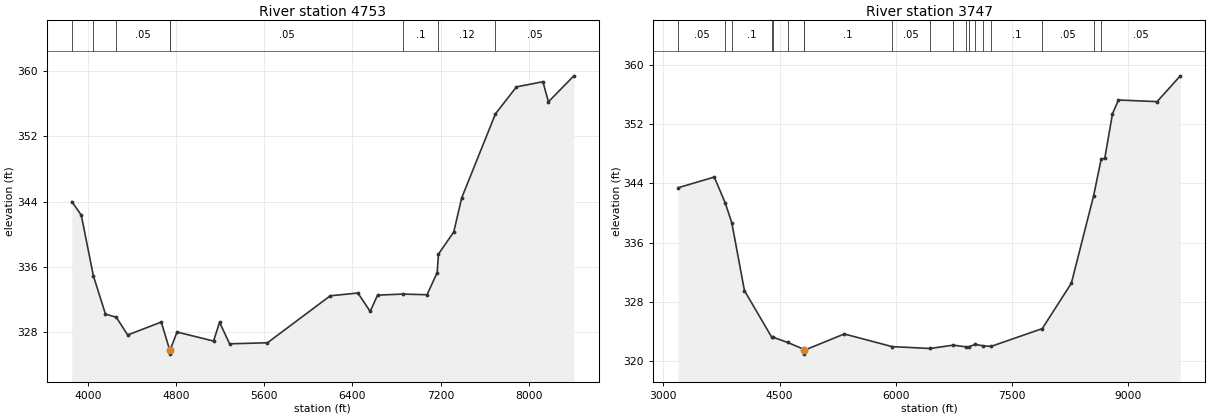
Type RM Length L Ch R = 1 ,4753    ,1006,1006,1006
BEGIN DESCRIPTION:
Kings Creek 33 7.0
END DESCRIPTION:
XS GIS Cut Line= 3
      2671576.01      6841510.99        2670676.        6842211.
       2669727.9      6845490.62
#Sta/Elev= 30
    3855     344    3941  342.35  4050.8  334.93  4160.9  330.24    4259  329.86
  4361.8  327.69  4666.7  329.27  4743.4  325.85  4743.7  325.35  4747.4  325.85
  4809.7  328.05  5140.9  326.95  5195.7  329.24  5286.7  326.61  5630.3  326.74
  6199.5  332.48  6450.4  332.82  6561.7  330.57  6628.9  332.56  6857.4  332.69
  7077.1  332.61  7169.6  335.31  7180.9  337.57  7319.7  340.28  7392.1  344.46
    7698  354.72  7888.8  358.02  8128.4  358.65  8178.6  356.19  8409.1  359.37
#Mann= 8 ,-1 , 0
    3855     .05       0  4050.8     .12       0    4259     .05       0
  4743.4     .04       0  4747.4     .05       0  6857.4      .1       0
  7180.9     .12       0    7698     .05       0
Bank Sta=4743.4,4747.4
XS Rating Curve= 0 ,0
Exp/Cntr=0.3,0.1

Type RM Length L Ch R = 1 ,3747    ,0,0,0
BEGIN DESCRIPTION:
Kings Creek 33 6.0
END DESCRIPTION:
XS GIS Cut Line= 4
      2671876.46       6841074.3      2670125.95      6841520.98
      2669261.15      6841779.67      2669413.08      6845545.25
#Sta/Elev= 30
  3193.4  343.43  3658.3  344.87  3802.4  341.31  3884.7  338.69  4047.5  329.56
  4398.6  323.29  4413.1  323.28  4604.2  322.57  4809.8  321.66  4811.5  321.49
  4811.8  320.99  4815.5  321.49  5335.4  323.71  5954.1     322  6444.5  321.75
  6738.8   322.2  6909.5  321.97  6940.7  321.99  7025.2  322.29  7131.2  322.11
  7229.2  322.03  7890.1  324.43  8265.9  330.56  8552.2  342.32  8650.6   347.3
  8696.3  347.38  8796.3  353.41  8873.5  355.26  9371.7  355.04  9671.3  358.52
#Mann= 20 ,-1 , 0
  3193.4     .05       0  3802.4     .12       0  3884.7      .1       0
  4398.6     .12       0  4413.1     .05       0  4604.2     .12       0
  4809.8      .1       0  4811.5     .07       0  4815.5      .1       0
  5954.1     .05       0  6444.5     .12       0  6738.8     .05       0
  6909.5     .12       0  6940.7     .05       0  7025.2     .12       0
  7131.2     .05       0  7229.2      .1       0  7890.1     .05       0
  8552.2     .12       0  8650.6     .05       0
Bank Sta=4811.5,4815.5
XS Rating Curve= 0 ,0
Exp/Cntr=0.3,0.1

Chan Stop Cuts=-1
Use User Specified Reach Order=0
Composite Channel Slope=5