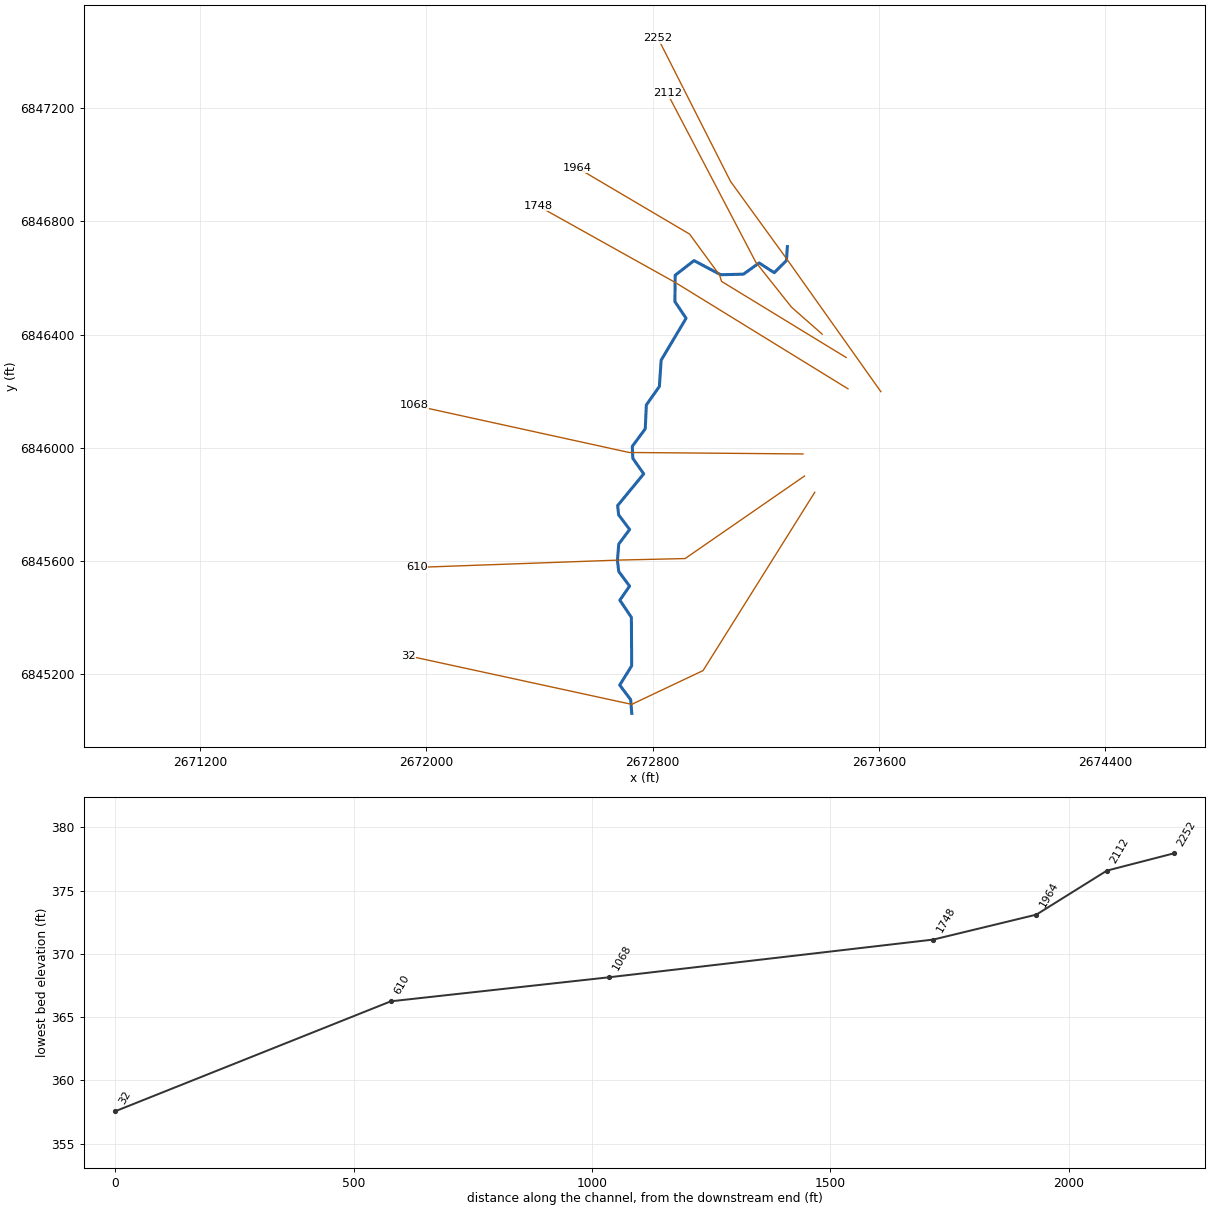
--- Kings Creek 33_1.prj (project) ---

Proj Title=Kings Creek 33_1 Base Level Engineering
Current Plan=p01
Default Exp/Contr=0.3,0.1
English Units
Geom File=g01
Flow File=f01
Plan File=p01
BEGIN DESCRIPTION:
Kings Creek 33_1
END DESCRIPTION:

--- Kings Creek 33_1.p01 (plan) ---

Plan Title=Multiple Run
Short Identifier=Multiple
Geom File=g01
Flow File=f01
Subcritical Flow
K Sum by GR= 0
Std Step Tol= 0.01
Critical Tol= 0.01
Num of Std Step Trials= 20
Max Error Tol= 0.3
Flow Tol Ratio= 0.001
Split Flow NTrial= 30
Split Flow Tol= 0.02
Split Flow Ratio= 0.02
Log Output Level= 0
Friction Slope Method= 1
Unsteady Friction Slope Method= 2
Unsteady Bridges Friction Slope Method= 1
Parabolic Critical Depth
Global Vel Dist=  1 , 1 , 1
Global Log Level= 0
CheckData=True
Encroach Param= -1, 0, 0, 0
BEGIN DESCRIPTION:
Multiple Run
END DESCRIPTION:

--- Kings Creek 33_1.f01 (steady flow) ---

Flow Title=Multiple
Number of Profiles=7
Profile Names=10-year,25-year,50-year,1pct_min,100-year,1pct_plu,500-year
River Rch & RM= Kings Creek 33_1,Reach-1,2252
      84      98     107      59     117     234     139
Boundary for River Rch & Prof#=Kings Creek 33_1,Reach-1,1
Up Type=0
Dn Type=3
Dn Slope=0.005
Boundary for River Rch & Prof#=Kings Creek 33_1,Reach-1,2
Up Type=0
Dn Type=3
Dn Slope=0.005
Boundary for River Rch & Prof#=Kings Creek 33_1,Reach-1,3
Up Type=0
Dn Type=3
Dn Slope=0.005
Boundary for River Rch & Prof#=Kings Creek 33_1,Reach-1,4
Up Type=0
Dn Type=3
Dn Slope=0.005
Boundary for River Rch & Prof#=Kings Creek 33_1,Reach-1,5
Up Type=0
Dn Type=3
Dn Slope=0.005
Boundary for River Rch & Prof#=Kings Creek 33_1,Reach-1,6
Up Type=0
Dn Type=3
Dn Slope=0.005
Boundary for River Rch & Prof#=Kings Creek 33_1,Reach-1,7
Up Type=0
Dn Type=3
Dn Slope=0.005

--- Kings Creek 33_1.g01 (geometry) ---

Geom Title=Existing Conditions

River Reach=Kings Creek 33_1,Reach-1
Reach XY= 30
      2673276.00      6846711.00      2673272.73      6846661.64
      2673229.53      6846618.72      2673176.11      6846653.21
      2673120.52      6846613.48      2673039.97      6846611.57
      2672946.01      6846661.45      2672879.37      6846609.78
      2672878.48      6846516.49      2672917.95      6846457.68
      2672829.83      6846309.42      2672823.53      6846216.57
      2672777.49      6846151.29      2672773.62      6846066.97
      2672727.86      6846004.87      2672729.62      6845962.63
      2672768.16      6845907.60      2672676.02      6845795.64
      2672679.58      6845762.65      2672718.40      6845711.01
      2672679.94      6845659.50      2672675.29      6845600.93
      2672679.93      6845562.50      2672718.20      6845510.90
      2672683.79      6845461.10      2672724.63      6845400.57
      2672725.68      6845229.22      2672683.31      6845160.96
      2672722.00      6845109.64      2672726.00      6845061.00

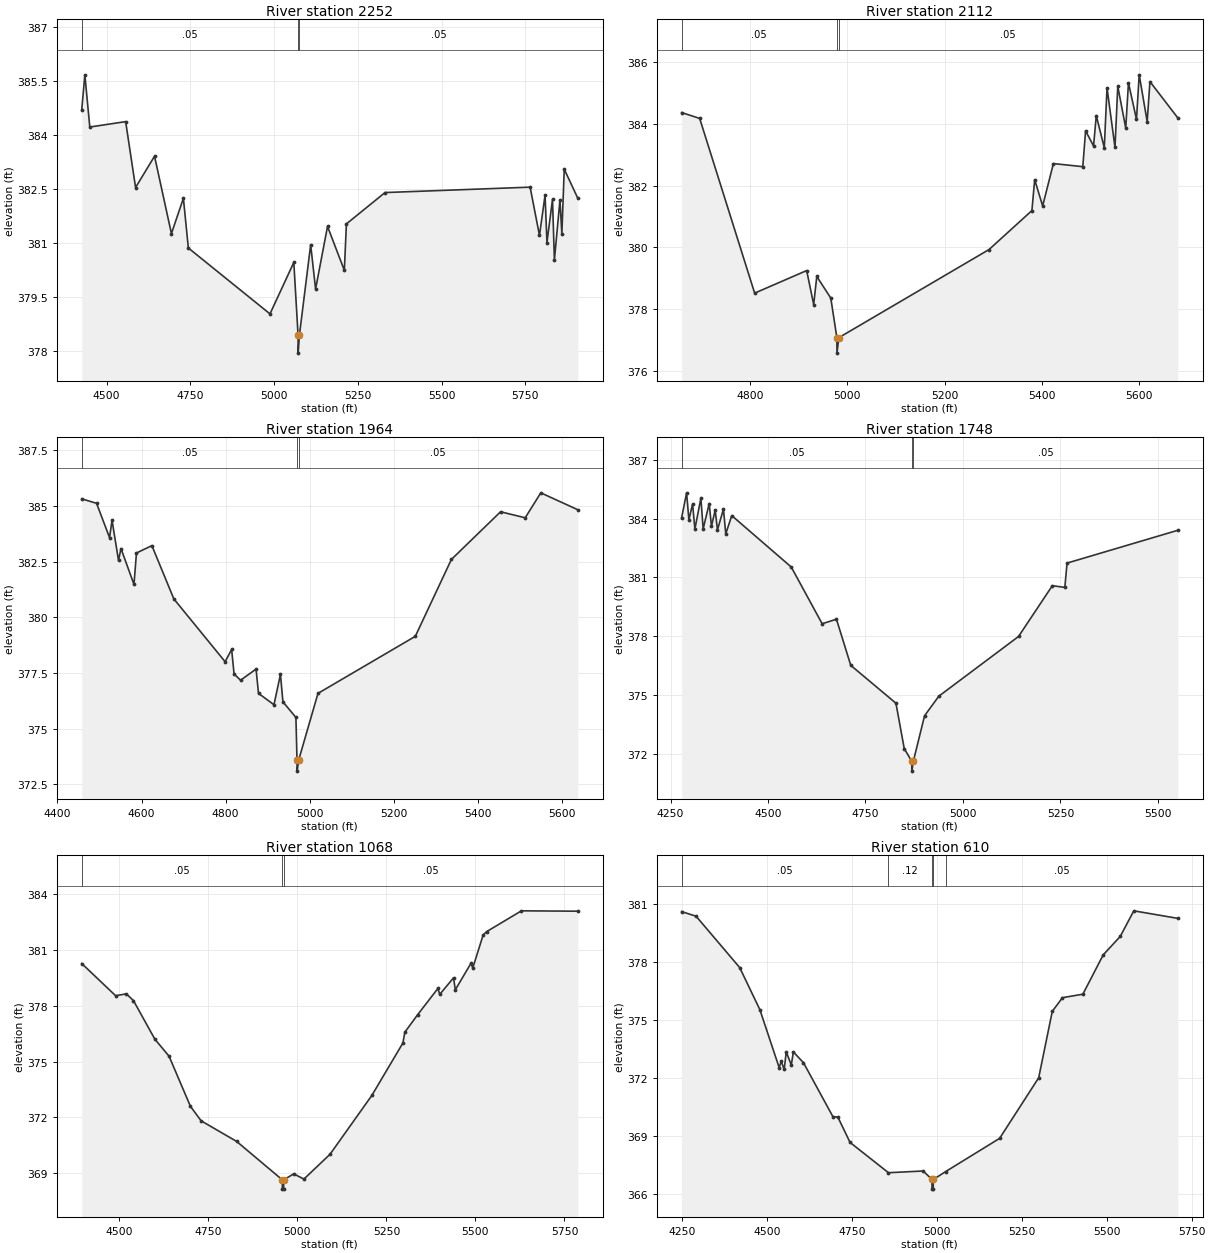
Type RM Length L Ch R = 1,2252,140,140,140
BEGIN DESCRIPTION:
Mapping XS 49b0e9dc
END DESCRIPTION:
XS GIS Cut Line= 4
      2673606.36      6846198.33      2673274.32      6846666.54
      2673075.12      6846941.36      2672818.75      6847447.18
#Sta/Elev= 30
  4426.0  384.69  4435.3  385.67  4450.1  384.22  4557.1  384.37  4586.7  382.54
  4643.3  383.41  4693.7  381.26  4729.4  382.24  4744.2  380.86  4987.8  379.03
  5058.9  380.46  5071.6  378.44  5071.9  377.94  5075.6  378.44  5109.2  380.95
  5123.9  379.72  5159.5  381.46  5209.7  380.24  5215.9  381.53  5331.1  382.40
  5764.1  382.55  5792.0  381.21  5808.7  382.33  5814.3  381.01  5830.9  382.21
  5836.5  380.52  5853.2  382.20  5858.8  381.25  5865.9  383.05  5906.5  382.24
#Mann=3,-1,0
  4426.0    0.05       0  5071.6    0.05       0  5075.6    0.05       0
Bank Sta=5071.6,5075.6
Exp/Cntr=0.3,0.1

Type RM Length L Ch R = 1,2112,148,148,148
BEGIN DESCRIPTION:
Mapping XS a1c900bc
END DESCRIPTION:
XS GIS Cut Line= 4
      2673398.96      6846401.56      2673290.49      6846497.01
      2673164.63      6846655.43      2672852.12      6847252.23
#Sta/Elev= 30
  4659.2  384.36  4696.3  384.17  4809.4  378.52  4916.4  379.25  4930.8  378.15
  4937.2  379.06  4966.0  378.36  4978.5  377.08  4978.7  376.58  4982.5  377.08
  5291.5  379.93  5379.7  381.19  5385.4  382.19  5401.8  381.34  5423.9  382.71
  5484.4  382.61  5490.1  383.77  5506.5  383.28  5512.1  384.26  5528.6  383.22
  5534.2  385.16  5550.6  383.23  5556.3  385.21  5572.7  383.86  5578.3  385.32
  5594.8  384.14  5600.4  385.58  5616.8  384.07  5622.5  385.36  5679.7  384.19
#Mann=3,-1,0
  4659.2    0.05       0  4978.5    0.03       0  4982.5    0.05       0
Bank Sta=4978.5,4982.5
Exp/Cntr=0.3,0.1

Type RM Length L Ch R = 1,1964,216,216,216
BEGIN DESCRIPTION:
Mapping XS 871aabfb
END DESCRIPTION:
XS GIS Cut Line= 5
      2673483.61      6846319.08      2673043.10      6846588.15
      2673036.59      6846609.86      2672930.25      6846755.26
      2672533.13      6846989.62
#Sta/Elev= 30
  4457.8  385.32  4493.1  385.12  4524.0  383.58  4529.9  384.36  4545.3  382.56
  4551.2  383.09  4582.1  381.48  4588.0  382.89  4624.7  383.22  4676.9  380.83
  4798.9  378.01  4814.4  378.56  4820.2  377.46  4835.7  377.18  4872.5  377.68
  4878.3  376.59  4915.1  376.08  4930.5  377.44  4936.4  376.21  4967.3  375.51
  4969.9  373.60  4970.2  373.10  4973.9  373.60  5019.8  376.59  5251.3  379.15
  5337.1  382.60  5454.1  384.74  5512.7  384.47  5549.8  385.59  5637.9  384.83
#Mann=3,-1,0
  4457.8    0.05       0  4969.9    0.03       0  4973.9    0.05       0
Bank Sta=4969.9,4973.9
Exp/Cntr=0.3,0.1

Type RM Length L Ch R = 1,1748,680,680,680
BEGIN DESCRIPTION:
Mapping XS 2ef4489a
END DESCRIPTION:
XS GIS Cut Line= 3
      2673490.19      6846208.36      2672880.34      6846583.81
      2672394.26      6846855.06
#Sta/Elev= 30
  4278.3  384.04  4291.0  385.31  4296.9  383.94  4306.4  384.74  4312.3  383.46
  4327.7  385.04  4333.5  383.47  4349.0  384.76  4354.8  383.61  4364.4  384.43
  4370.2  383.42  4385.6  384.48  4391.5  383.22  4406.9  384.15  4559.5  381.53
  4638.8  378.64  4675.5  378.87  4712.2  376.52  4828.1  374.59  4849.4  372.28
  4868.7  371.63  4868.9  371.13  4872.7  371.63  4901.5  373.95  4938.2  374.95
  5142.6  377.99  5229.4  380.58  5261.4  380.49  5267.1  381.73  5551.1  383.40
#Mann=3,-1,0
  4278.3    0.05       0  4868.7    0.04       0  4872.7    0.05       0
Bank Sta=4868.7,4872.7
Exp/Cntr=0.3,0.1

Type RM Length L Ch R = 1,1068,458,458,458
BEGIN DESCRIPTION:
Mapping XS e5fa1ca3
END DESCRIPTION:
XS GIS Cut Line= 3
      2673331.15      6845978.04      2672716.62      6845983.25
      2671956.22      6846149.91
#Sta/Elev= 30
  4394.6  380.27  4489.8  378.54  4519.8  378.64  4539.8  378.28  4599.8  376.21
  4639.8  375.29  4699.8  372.60  4729.8  371.82  4829.8  370.71  4957.8  368.65
  4958.0  368.15  4961.5  368.15  4961.8  368.65  4989.8  368.97  5018.5  368.69
  5091.7  370.02  5209.1  373.18  5296.4  376.00  5301.9  376.58  5337.4  377.51
  5394.7  378.93  5399.8  378.61  5438.5  379.50  5443.6  378.86  5487.5  380.28
  5492.6  380.03  5521.7  381.80  5531.3  381.98  5629.2  383.10  5787.6  383.08
#Mann=3,-1,0
  4394.6    0.05       0  4957.8    0.03       0  4961.8    0.05       0
Bank Sta=4957.8,4961.8
Exp/Cntr=0.3,0.1

Type RM Length L Ch R = 1,610,578,578,578
BEGIN DESCRIPTION:
Mapping XS 10793d5a
END DESCRIPTION:
XS GIS Cut Line= 4
      2673336.41      6845899.92      2672914.53      6845608.25
      2672685.37      6845603.04      2671966.65      6845577.00
#Sta/Elev= 30
  4247.8  380.63  4290.4  380.39  4418.8  377.73  4478.2  375.55  4535.0  372.55
  4541.1  372.87  4549.9  372.46  4556.0  373.36  4570.8  372.68  4576.9  373.36
  4606.7  372.80  4693.2  370.01  4708.0  369.98  4743.9  368.67  4857.0  367.10
  4959.3  367.19  4985.1  366.75  4985.3  366.25  4988.8  366.25  4989.1  366.75
  5025.5  367.16  5184.4  368.88  5299.5  372.02  5339.5  375.46  5369.5  376.17
  5429.6  376.35  5489.6  378.39  5539.6  379.34  5579.7  380.67  5709.1  380.28
#Mann=5,-1,0
  4247.8    0.05       0  4857.0    0.12       0  4985.1    0.07       0
  4989.1    0.12       0  5025.5    0.05       0
Bank Sta=4985.1,4989.1
Exp/Cntr=0.3,0.1

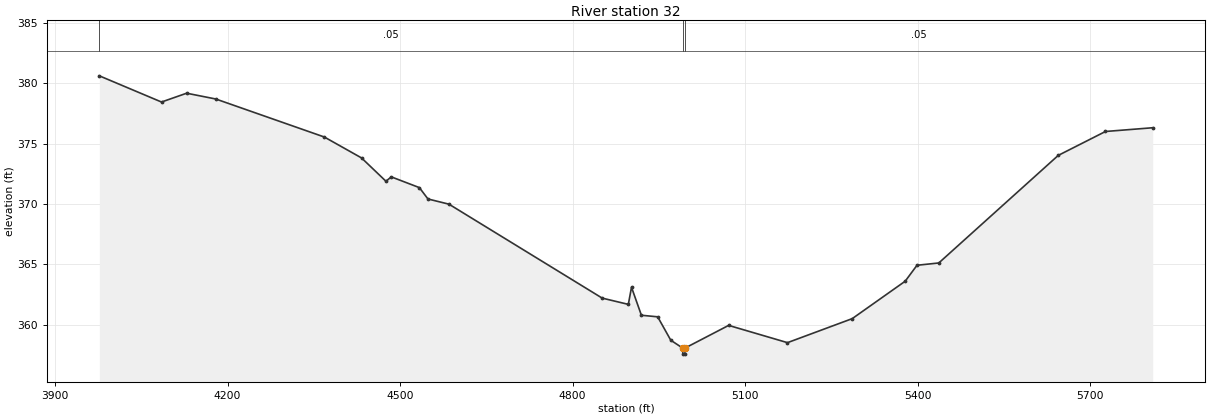
Type RM Length L Ch R = 1,32,0,0,0
BEGIN DESCRIPTION:
Kings Creek 33_1 1.0
END DESCRIPTION:
XS GIS Cut Line= 4
      2673372.85      6845842.59      2672978.04      6845212.33
      2672725.69      6845092.88      2671935.41      6845264.49
#Sta/Elev= 30
  3977.1  380.61  4085.2  378.44  4128.9  379.17  4179.6  378.69  4368.4  375.54
  4433.0  373.81  4475.4  371.88  4484.8  372.24  4533.6  371.35  4548.5  370.41
  4585.0  369.98  4851.4  362.20  4896.9  361.68  4902.4  363.10  4919.6  360.78
  4947.9  360.65  4970.7  358.71  4991.4  358.06  4991.7  357.56  4995.2  357.56
  4995.4  358.06  5071.3  359.94  5173.6  358.51  5286.2  360.50  5378.3  363.60
  5398.8  364.92  5436.7  365.11  5644.4  374.02  5726.5  376.00  5808.7  376.31
#Mann=3,-1,0
  3977.1    0.05       0  4991.4    0.04       0  4995.4    0.05       0
Bank Sta=4991.4,4995.4
Exp/Cntr=0.3,0.1

Chan Stop Cuts=-1