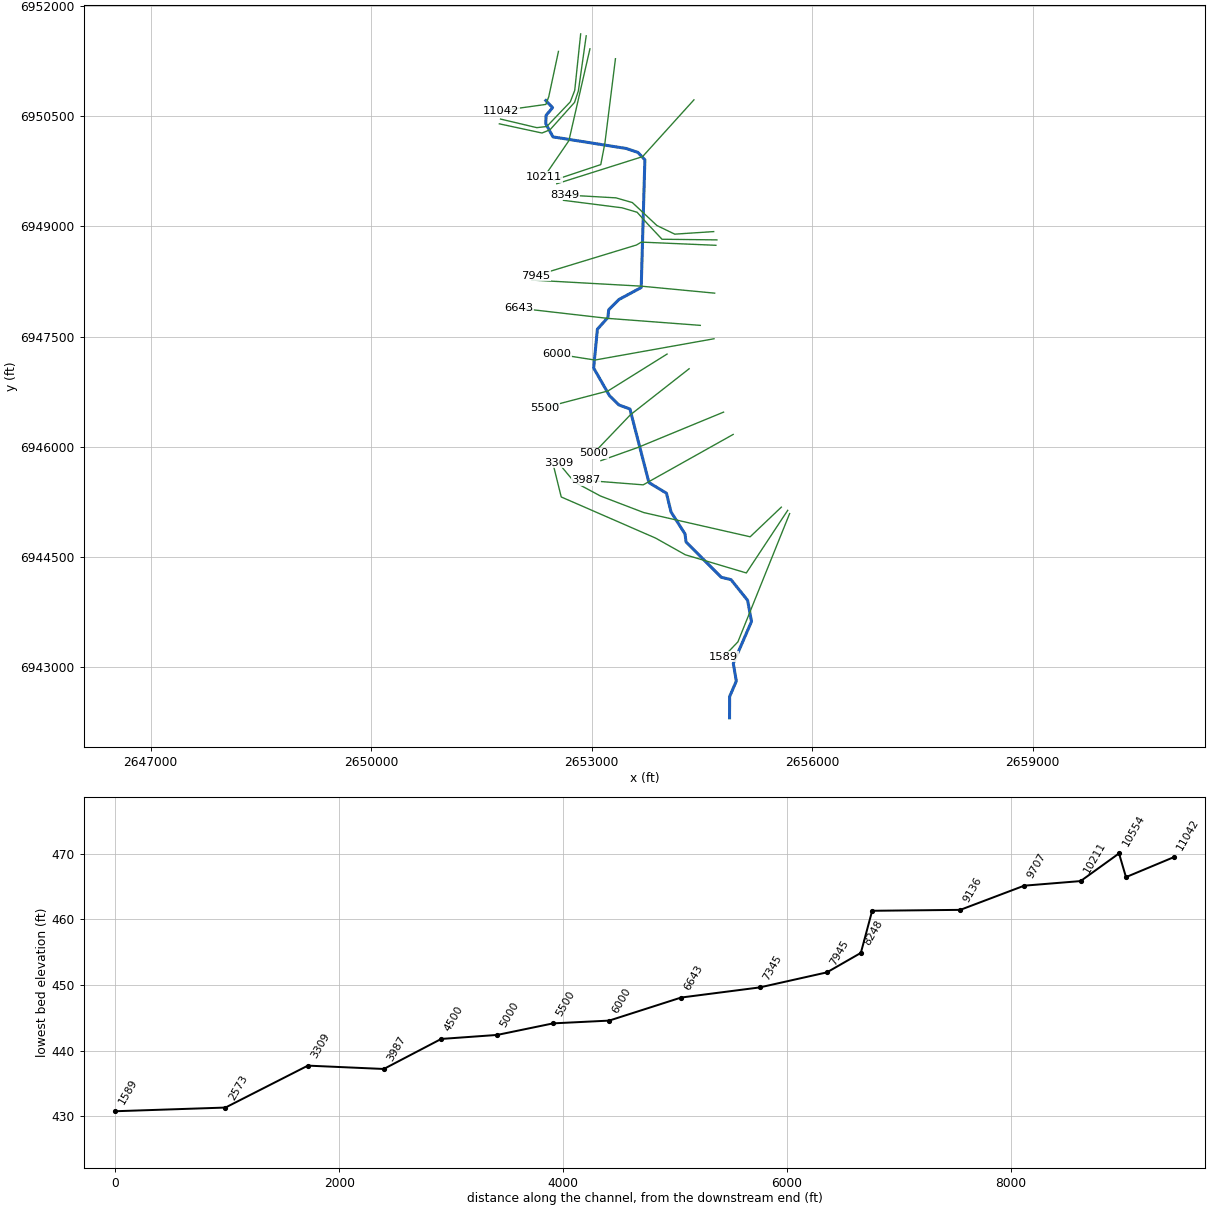
--- Kings Creek Trib 1.prj (project) ---

Proj Title=Kings Creek Trib 1 Base Level Engineering
Current Plan=p01
Default Exp/Contr=0.3,0.1
English Units
Geom File=g01
Flow File=f01
Plan File=p01
BEGIN DESCRIPTION:
Kings Creek Trib 1
END DESCRIPTION:

--- Kings Creek Trib 1.p01 (plan) ---

Plan Title=Multiple Run
Short Identifier=Multiple
Geom File=g01
Flow File=f01
Subcritical Flow
K Sum by GR= 0
Std Step Tol= 0.01
Critical Tol= 0.01
Num of Std Step Trials= 20
Max Error Tol= 0.3
Flow Tol Ratio= 0.001
Split Flow NTrial= 30
Split Flow Tol= 0.02
Split Flow Ratio= 0.02
Log Output Level= 0
Friction Slope Method= 1
Unsteady Friction Slope Method= 2
Unsteady Bridges Friction Slope Method= 1
Parabolic Critical Depth
Global Vel Dist=  1 , 1 , 1
Global Log Level= 0
CheckData=True
Encroach Param= -1, 0, 0, 0
BEGIN DESCRIPTION:
Multiple Run
END DESCRIPTION:

--- Kings Creek Trib 1.f01 (steady flow) ---

Flow Title=Multiple
Number of Profiles=7
Profile Names=10-year,25-year,50-year,1pct_min,100-year,1pct_plu,500-year
River Rch & RM= Kings Creek Trib,Reach-1,11042
     556     743     894     534    1066    2126    1513
River Rch & RM= Kings Creek Trib,Reach-1,7345
     987    1359    1666    1012    2018    4027    2963
Boundary for River Rch & Prof#=Kings Creek Trib,Reach-1,1
Up Type=0
Dn Type=3
Dn Slope=0.005
Boundary for River Rch & Prof#=Kings Creek Trib,Reach-1,2
Up Type=0
Dn Type=3
Dn Slope=0.005
Boundary for River Rch & Prof#=Kings Creek Trib,Reach-1,3
Up Type=0
Dn Type=3
Dn Slope=0.005
Boundary for River Rch & Prof#=Kings Creek Trib,Reach-1,4
Up Type=0
Dn Type=3
Dn Slope=0.005
Boundary for River Rch & Prof#=Kings Creek Trib,Reach-1,5
Up Type=0
Dn Type=3
Dn Slope=0.005
Boundary for River Rch & Prof#=Kings Creek Trib,Reach-1,6
Up Type=0
Dn Type=3
Dn Slope=0.005
Boundary for River Rch & Prof#=Kings Creek Trib,Reach-1,7
Up Type=0
Dn Type=3
Dn Slope=0.005

--- Kings Creek Trib 1.g01 (geometry) ---

Geom Title=Existing Conditions

River Reach=Kings Creek Trib,Reach-1
Reach XY= 30
      2652376.00      6950711.00      2652468.22      6950614.26
      2652379.55      6950509.53      2652375.52      6950395.84
      2652473.30      6950216.36      2653470.06      6950058.74
      2653628.44      6950005.48      2653723.95      6949905.16
      2653674.03      6948166.65      2653369.95      6948002.84
      2653231.52      6947863.43      2653220.46      6947758.58
      2653077.92      6947599.05      2653026.94      6947071.48
      2653242.65      6946694.33      2653369.83      6946568.86
      2653520.59      6946513.71      2653779.44      6945512.23
      2654017.87      6945367.08      2654079.76      6945112.56
      2654270.46      6944813.42      2654283.86      6944704.83
      2654762.70      6944224.40      2654896.15      6944191.37
      2655122.18      6943909.42      2655174.81      6943621.50
      2654927.22      6943050.50      2654968.44      6942811.00
      2654877.22      6942600.50      2654876.00      6942311.00

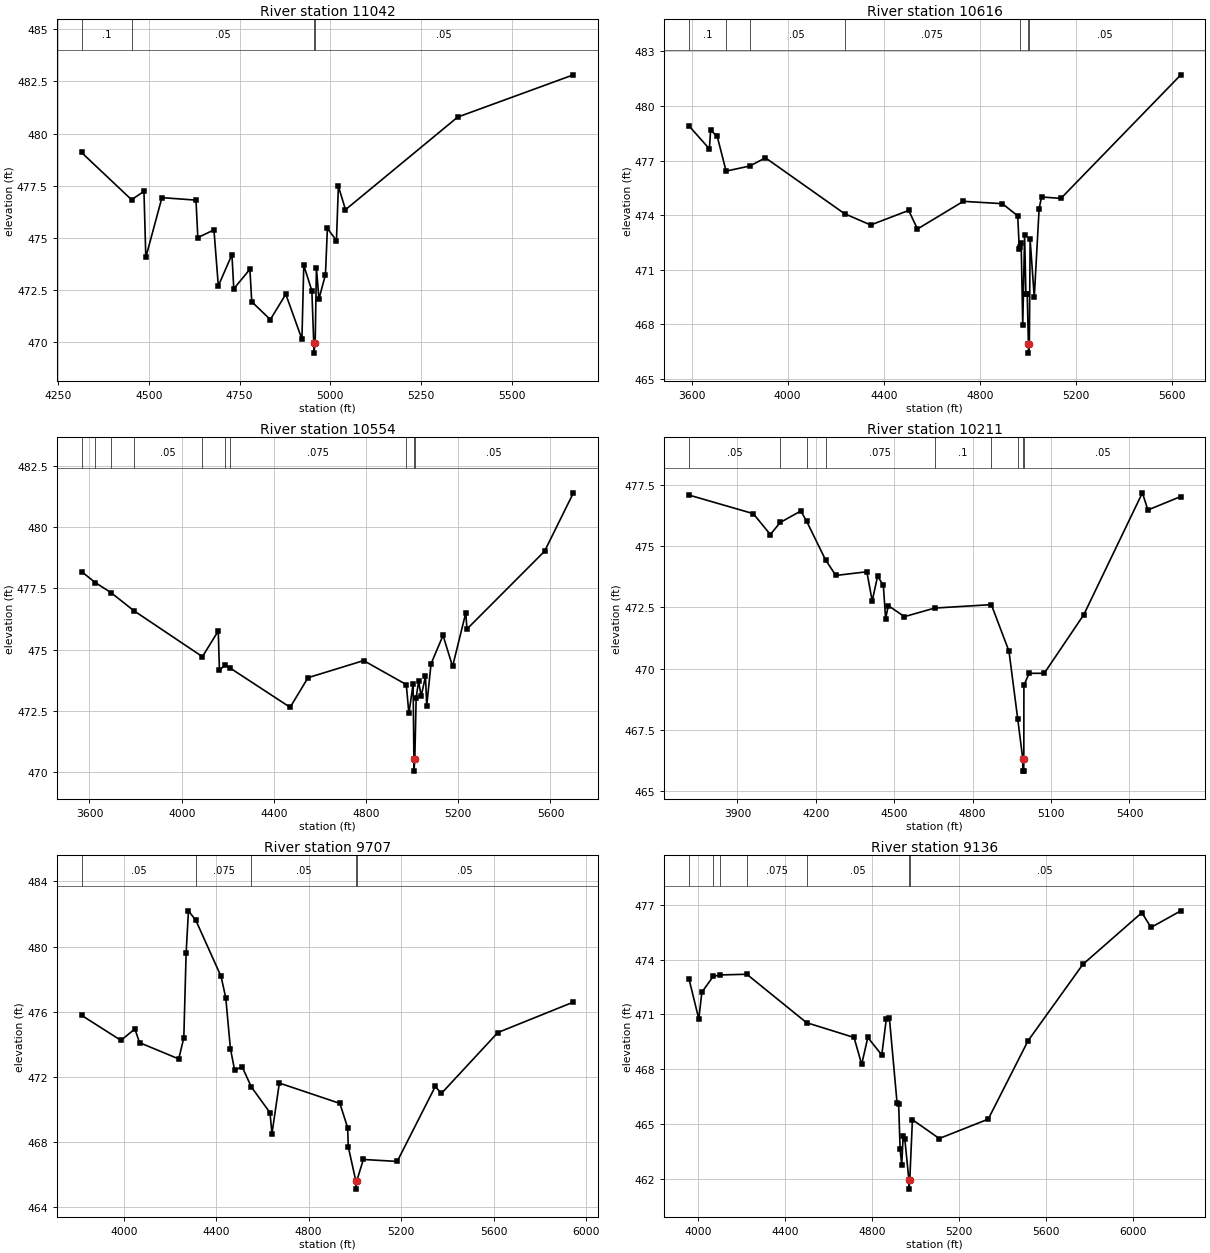
Type RM Length L Ch R = 1,11042,426,426,426
BEGIN DESCRIPTION:
Mapping XS 14a63abc
END DESCRIPTION:
XS GIS Cut Line= 4
      2652547.96      6951379.48      2652416.01      6950762.28
      2652376.95      6950658.11      2651770.27      6950573.85
#Sta/Elev= 30
  4314.7  479.09  4452.5  476.82  4486.7  477.22  4491.8  474.05  4536.2  476.92
  4630.0  476.80  4635.1  475.00  4679.5  475.37  4691.5  472.68  4729.0  474.18
  4734.1  472.54  4778.5  473.48  4783.6  471.92  4834.7  471.06  4877.4  472.28
  4921.8  470.12  4926.9  473.67  4949.2  472.44  4954.3  469.95  4954.6  469.45
  4958.3  469.95  4961.7  473.54  4968.6  472.05  4986.6  473.22  4991.9  475.44
  5016.9  474.86  5022.2  477.47  5041.8  476.34  5350.8  480.79  5669.6  482.82
#Mann=4,-1,0
  4314.7     0.1       0  4452.5    0.05       0  4954.3    0.03       0
  4958.3    0.05       0
Bank Sta=4954.3,4958.3
Exp/Cntr=0.3,0.1

Type RM Length L Ch R = 1,10616,62,62,62
BEGIN DESCRIPTION:
Mapping XS 83387897
END DESCRIPTION:
XS GIS Cut Line= 6
      2652850.22      6951618.04      2652769.48      6950849.78
      2652709.59      6950693.53      2652389.27      6950357.59
      2652253.86      6950341.97      2651760.07      6950458.92
#Sta/Elev= 30
  3588.7  478.91  3674.0  477.64  3679.1  478.67  3706.4  478.34  3743.6  476.42
  3842.3  476.70  3907.5  477.15  4236.9  474.08  4345.8  473.46  4503.9  474.26
  4540.6  473.24  4731.5  474.76  4894.2  474.63  4958.1  473.96  4964.7  472.12
  4967.9  472.27  4972.4  472.49  4979.0  467.94  4986.7  472.89  4992.2  469.66
  4997.7  469.66  5002.6  466.92  5002.9  466.42  5006.6  466.92  5009.7  472.67
  5027.0  469.49  5047.2  474.36  5057.2  475.00  5137.9  474.92  5637.3  481.71
#Mann=7,-1,0
  3588.7     0.1       0  3743.6   0.075       0  3842.3    0.05       0
  4236.9   0.075       0  4967.9    0.05       0  5002.6    0.05       0
  5006.6    0.05       0
Bank Sta=5002.6,5006.6
Exp/Cntr=0.3,0.1

Type RM Length L Ch R = 1,10554,343,343,343
BEGIN DESCRIPTION:
Mapping XS a419ee8e
END DESCRIPTION:
XS GIS Cut Line= 6
      2652925.74      6951592.00      2652818.96      6950841.97
      2652766.88      6950685.72      2652433.55      6950313.32
      2652324.17      6950269.05      2651743.47      6950394.05
#Sta/Elev= 30
  3565.4  478.19  3625.2  477.74  3693.1  477.33  3792.5  476.59  4089.9  474.71
  4158.7  475.76  4163.7  474.15  4189.0  474.38  4210.9  474.24  4470.5  472.64
  4548.0  473.85  4789.3  474.55  4974.3  473.57  4985.7  472.39  5004.0  473.59
  5007.4  470.53  5007.7  470.03  5011.4  470.53  5017.2  473.03  5028.0  473.71
  5038.9  473.09  5057.7  473.91  5063.0  472.70  5081.8  474.42  5133.9  475.58
  5175.2  474.31  5232.5  476.50  5237.6  475.84  5574.2  479.02  5699.5  481.41
#Mann=10,-1,0
  3565.4   0.075       0  3625.2     0.1       0  3693.1   0.075       0
  3792.5    0.05       0  4089.9   0.075       0  4189.0     0.1       0
  4210.9   0.075       0  4974.3    0.05       0  5007.4    0.05       0
  5011.4    0.05       0
Bank Sta=5007.4,5011.4
Exp/Cntr=0.3,0.1

Type RM Length L Ch R = 1,10211,504,504,504
BEGIN DESCRIPTION:
Mapping XS dfcbac63
END DESCRIPTION:
XS GIS Cut Line= 3
      2652976.38      6951414.62      2652689.91      6950164.60
      2652351.34      6949669.77
#Sta/Elev= 30
  3714.4  477.08  3960.8  476.32  4025.9  475.47  4063.8  475.96  4142.6  476.43
  4164.8  476.01  4237.0  474.44  4276.5  473.80  4395.2  473.95  4415.7  472.76
  4436.3  473.77  4458.3  473.40  4467.0  472.04  4477.3  472.57  4538.9  472.12
  4654.7  472.47  4871.5  472.61  4939.0  470.71  4972.4  467.95  4991.7  466.32
  4991.9  465.82  4995.4  465.82  4995.7  466.32  4996.1  469.32  5016.0  469.81
  5073.9  469.81  5225.2  472.20  5449.4  477.17  5470.4  476.47  5596.4  477.02
#Mann=9,-1,0
  3714.4    0.05       0  4063.8   0.075       0  4164.8     0.1       0
  4237.0   0.075       0  4654.7     0.1       0  4871.5   0.075       0
  4972.4    0.05       0  4991.7    0.03       0  4995.7    0.05       0
Bank Sta=4991.7,4995.7
Exp/Cntr=0.3,0.1

Type RM Length L Ch R = 1,9707,571,571,571
BEGIN DESCRIPTION:
Mapping XS 4e80fd14
END DESCRIPTION:
XS GIS Cut Line= 4
      2653323.59      6951280.05      2653180.36      6950134.21
      2653123.94      6949839.07      2652485.89      6949626.39
#Sta/Elev= 30
  3817.4  475.79  3987.8  474.25  4048.2  474.95  4068.4  474.11  4238.0  473.11
  4259.9  474.41  4269.9  479.60  4280.0  482.20  4312.1  481.61  4421.1  478.17
  4441.3  476.87  4461.4  473.75  4479.9  472.41  4511.8  472.64  4552.0  471.39
  4632.7  469.81  4641.2  468.52  4673.1  471.63  4935.1  470.38  4968.7  468.88
  4971.3  467.72  5004.0  465.62  5004.2  465.12  5008.0  465.62  5036.5  466.94
  5183.0  466.82  5347.6  471.42  5373.9  470.99  5618.3  474.73  5945.2  476.60
#Mann=5,-1,0
  3817.4    0.05       0  4312.1   0.075       0  4552.0    0.05       0
  5004.0    0.05       0  5008.0    0.05       0
Bank Sta=5004,5008
Exp/Cntr=0.3,0.1

Type RM Length L Ch R = 1,9136,787,787,787
BEGIN DESCRIPTION:
Mapping XS de77578d
END DESCRIPTION:
XS GIS Cut Line= 3
      2654391.32      6950720.17      2653692.51      6949947.58
      2652524.95      6949578.65
#Sta/Elev= 30
  3956.4  472.96  4002.0  470.75  4016.2  472.22  4068.4  473.08  4100.0  473.16
  4223.0  473.20  4498.3  470.55  4717.1  469.74  4752.3  468.27  4780.7  469.74
  4844.9  468.78  4865.8  470.75  4880.0  470.81  4915.2  466.18  4922.6  466.11
  4929.4  463.64  4936.8  462.76  4943.6  464.37  4951.0  464.19  4969.9  461.94
  4970.2  461.44  4973.9  461.94  4986.1  465.24  5109.8  464.21  5335.3  465.27
  5518.9  469.56  5771.3  473.74  6043.2  476.57  6085.2  475.76  6222.6  476.67
#Mann=7,-1,0
  3956.4    0.05       0  4068.4   0.075       0  4100.0     0.1       0
  4223.0   0.075       0  4498.3    0.05       0  4969.9    0.03       0
  4973.9    0.05       0
Bank Sta=4969.9,4973.9
Exp/Cntr=0.3,0.1

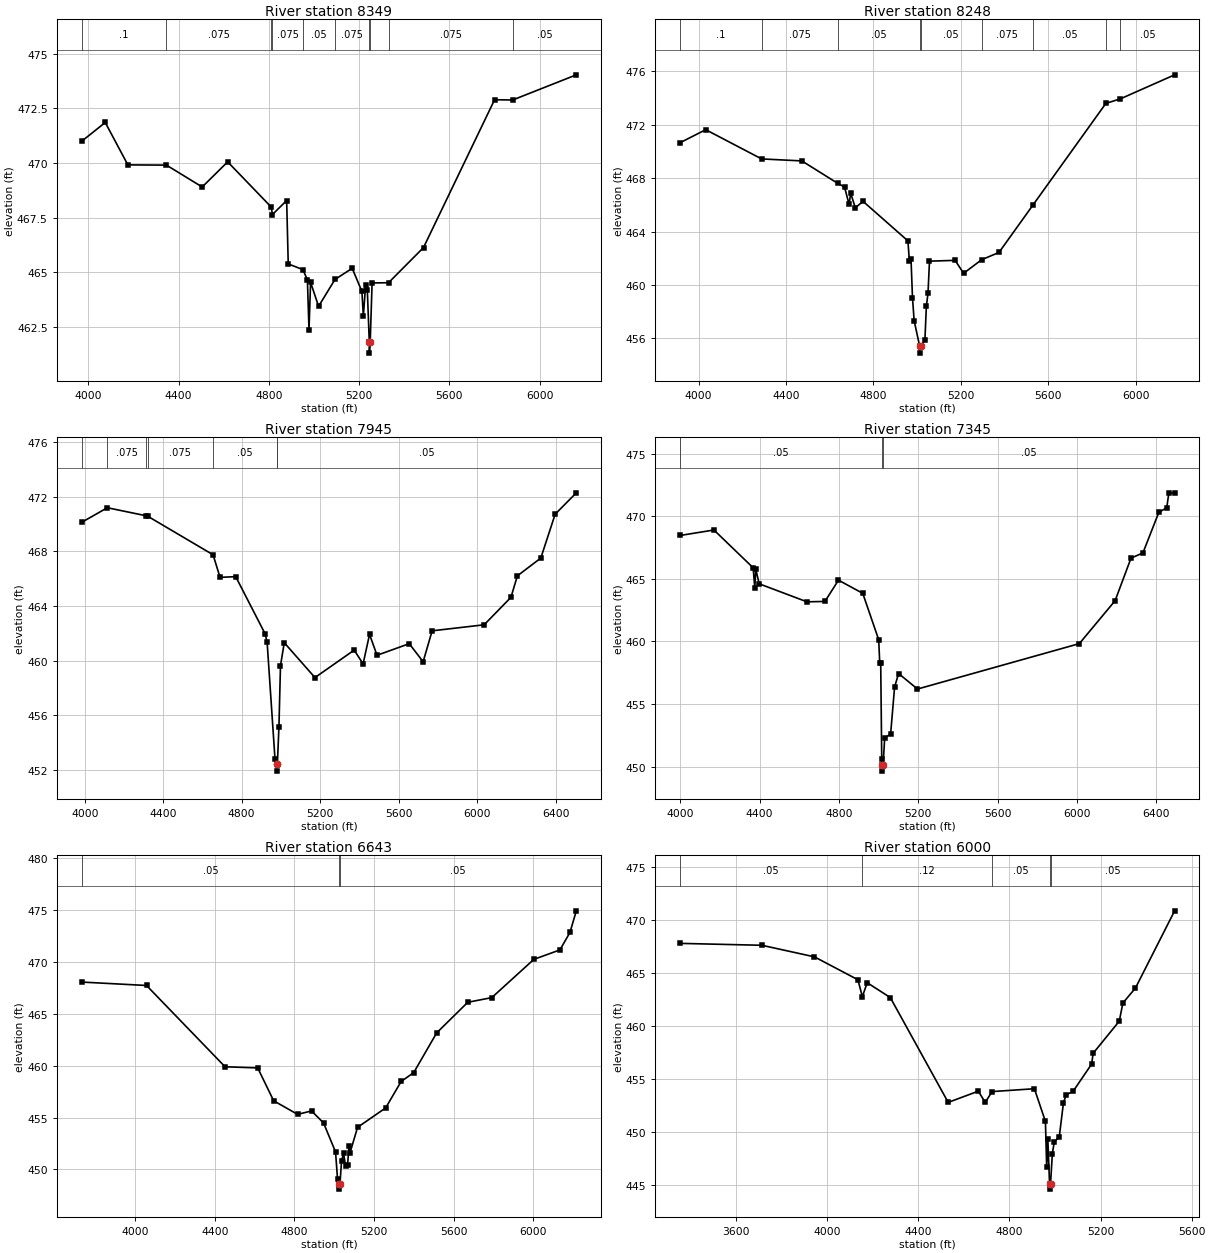
Type RM Length L Ch R = 1,8349,101,101,101
BEGIN DESCRIPTION:
Mapping XS 5110bebf
END DESCRIPTION:
XS GIS Cut Line= 6
      2654660.37      6948927.61      2654130.88      6948892.89
      2653887.83      6949010.08      2653553.63      6949322.58
      2653330.32      6949386.72      2652630.04      6949426.70
#Sta/Elev= 30
  3970.7  470.99  4075.3  471.85  4175.5  469.91  4346.5  469.90  4504.9  468.90
  4617.8  470.05  4811.0  467.98  4816.1  467.64  4879.2  468.28  4886.2  465.38
  4951.3  465.12  4971.1  464.65  4978.2  462.36  4985.2  464.54  5020.6  463.44
  5093.3  464.67  5169.7  465.18  5212.6  464.12  5219.1  462.99  5229.1  464.42
  5236.6  464.21  5245.4  461.80  5245.6  461.30  5249.4  461.80  5257.8  464.51
  5330.6  464.52  5485.7  466.13  5800.5  472.89  5881.0  472.88  6162.8  474.03
#Mann=10,-1,0
  3970.7     0.1       0  4346.5   0.075       0  4811.0    0.05       0
  4816.1   0.075       0  4951.3    0.05       0  5093.3   0.075       0
  5245.4    0.05       0  5249.4   0.075       0  5330.6   0.075       0
  5881.0    0.05       0
Bank Sta=5245.4,5249.4
Exp/Cntr=0.3,0.1

Type RM Length L Ch R = 1,8248,303,303,303
BEGIN DESCRIPTION:
Mapping XS 33245d81
END DESCRIPTION:
XS GIS Cut Line= 6
      2654703.85      6948814.77      2653957.27      6948823.45
      2653760.87      6949032.55      2653618.51      6949190.54
      2653413.65      6949251.30      2652616.15      6949352.96
#Sta/Elev= 30
  3914.9  470.65  4032.8  471.63  4288.6  469.44  4472.8  469.29  4636.8  467.61
  4667.9  467.34  4688.9  466.03  4696.2  466.88  4717.2  465.78  4752.8  466.26
  4958.1  463.30  4964.8  461.78  4972.3  461.93  4979.0  459.05  4986.5  457.33
  5012.2  455.39  5012.4  454.89  5016.2  455.39  5035.8  455.86  5042.6  458.41
  5050.0  459.37  5056.8  461.78  5174.1  461.84  5213.0  460.87  5295.6  461.89
  5374.7  462.43  5529.7  465.97  5864.0  473.60  5930.3  473.94  6178.7  475.74
#Mann=9,-1,0
  3914.9     0.1       0  4288.6   0.075       0  4636.8    0.05       0
  5012.2    0.05       0  5016.2    0.05       0  5295.6   0.075       0
  5529.7    0.05       0  5864.0   0.075       0  5930.3    0.05       0
Bank Sta=5012.2,5016.2
Exp/Cntr=0.3,0.1

Type RM Length L Ch R = 1,7945,600,600,600
BEGIN DESCRIPTION:
Mapping XS 09056463
END DESCRIPTION:
XS GIS Cut Line= 4
      2654690.76      6948740.98      2653675.15      6948784.39
      2653610.05      6948745.32      2652242.89      6948328.67
#Sta/Elev= 30
  3984.3  470.12  4115.3  471.19  4313.8  470.60  4321.0  470.57  4654.3  467.75
  4689.7  466.10  4769.8  466.15  4919.9  461.96  4929.9  461.34  4970.0  452.80
  4978.0  452.43  4978.2  451.93  4982.0  452.43  4990.0  455.15  4997.9  459.64
  5017.2  461.32  5173.6  458.77  5373.7  460.78  5419.1  459.77  5451.9  461.93
  5490.0  460.40  5654.2  461.25  5725.1  459.93  5771.0  462.19  6036.2  462.63
  6172.8  464.64  6205.6  466.21  6325.0  467.51  6398.2  470.72  6506.0  472.28
#Mann=7,-1,0
  3984.3     0.1       0  4115.3   0.075       0  4313.8    0.05       0
  4321.0   0.075       0  4654.3    0.05       0  4978.0    0.03       0
  4982.0    0.05       0
Bank Sta=4978,4982
Exp/Cntr=0.3,0.1

Type RM Length L Ch R = 1,7345,702,702,702
BEGIN DESCRIPTION:
Mapping XS 36a20540
END DESCRIPTION:
XS GIS Cut Line= 3
      2654673.38      6948089.95      2653670.81      6948185.43
      2652186.40      6948267.90
#Sta/Elev= 30
  3998.4  468.47  4169.6  468.91  4367.4  465.89  4375.6  464.29  4380.6  465.78
  4397.6  464.61  4638.7  463.17  4729.1  463.20  4797.5  464.90  4919.9  463.85
  5000.3  460.14  5005.4  458.31  5010.4  458.31  5015.6  450.64  5018.5  450.14
  5018.8  449.64  5022.6  450.14  5030.4  452.29  5060.4  452.61  5080.4  456.36
  5100.5  457.44  5195.8  456.20  6011.9  459.83  6192.1  463.26  6272.3  466.66
  6332.4  467.08  6412.5  470.32  6452.5  470.69  6462.8  471.85  6492.2  471.88
#Mann=3,-1,0
  3998.4    0.05       0  5018.5    0.03       0  5022.6    0.05       0
Bank Sta=5018.5,5022.6
Exp/Cntr=0.3,0.1

Type RM Length L Ch R = 1,6643,643,643,643
BEGIN DESCRIPTION:
Mapping XS db468199
END DESCRIPTION:
XS GIS Cut Line= 3
      2654478.06      6947651.58      2653215.08      6947747.06
      2652004.10      6947885.95
#Sta/Elev= 30
  3730.6  468.07  4056.6  467.74  4451.1  459.90  4615.2  459.79  4695.4  456.62
  4815.7  455.31  4885.9  455.64  4946.1  454.48  5006.3  451.69  5016.4  449.04
  5024.3  448.60  5024.7  448.10  5028.6  448.60  5036.5  450.83  5046.6  451.54
  5056.7  450.34  5066.7  450.40  5073.7  452.22  5078.7  451.58  5117.0  454.06
  5258.0  455.93  5336.2  458.49  5398.9  459.33  5514.5  463.17  5670.7  466.12
  5791.4  466.57  6002.8  470.26  6133.7  471.17  6184.0  472.85  6216.1  474.94
#Mann=3,-1,0
  3730.6    0.05       0  5024.3    0.04       0  5028.6    0.05       0
Bank Sta=5024.3,5028.6
Exp/Cntr=0.3,0.1

Type RM Length L Ch R = 1,6000,500,500,500
BEGIN DESCRIPTION:
Kings Creek Trib 1 12.0
END DESCRIPTION:
XS GIS Cut Line= 3
      2654664.75      6947469.28      2653044.93      6947179.70
      2652525.96      6947261.01
#Sta/Elev= 30
  3354.5  467.77  3714.0  467.59  3944.5  466.50  4135.4  464.34  4154.9  462.74
  4176.1  464.06  4277.5  462.66  4531.6  452.77  4663.7  453.83  4694.2  452.77
  4724.0  453.79  4910.0  454.06  4958.3  450.97  4963.8  446.66  4968.9  449.30
  4976.4  445.09  4976.8  444.59  4980.7  445.09  4988.8  447.95  4996.9  449.02
  5019.2  449.55  5037.5  452.75  5049.5  453.48  5079.9  453.82  5160.9  456.38
  5167.9  457.41  5282.3  460.43  5298.3  462.15  5353.2  463.55  5525.3  470.84
#Mann=5,-1,0
  3354.5    0.05       0  4154.9    0.12       0  4724.0    0.05       0
  4976.4    0.04       0  4980.7    0.05       0
Bank Sta=4976.4,4980.7
Exp/Cntr=0.3,0.1

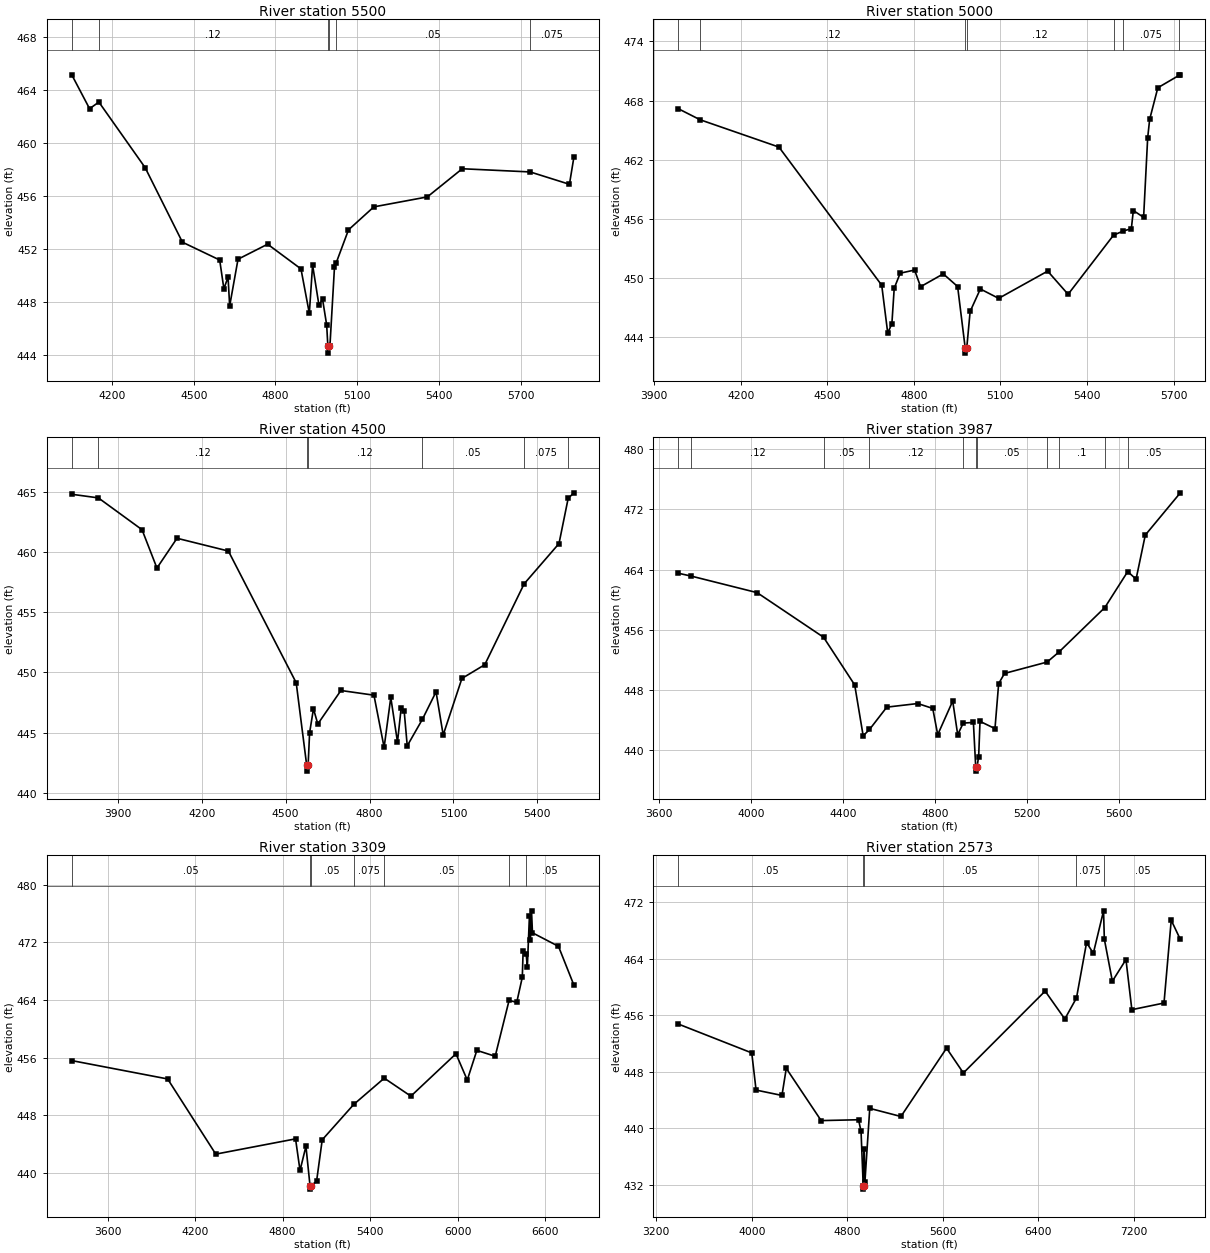
Type RM Length L Ch R = 1,5500,500,500,500
BEGIN DESCRIPTION:
Kings Creek Trib 1 11.0
END DESCRIPTION:
XS GIS Cut Line= 3
      2654025.98      6947260.99      2653222.11      6946759.06
      2652355.72      6946531.79
#Sta/Elev= 30
  4052.3  465.12  4117.7  462.57  4151.8  463.07  4321.8  458.13  4458.6  452.52
  4595.4  451.18  4610.8  449.01  4626.1  449.90  4632.0  447.72  4662.7  451.24
  4771.4  452.37  4893.8  450.51  4924.5  447.17  4936.5  450.80  4960.0  447.76
  4972.9  448.25  4988.2  446.29  4992.6  444.67  4993.0  444.17  4996.9  444.67
  5000.0  444.67  5016.9  450.65  5023.6  450.99  5068.3  453.45  5161.4  455.18
  5357.8  455.93  5486.0  458.05  5735.3  457.81  5879.5  456.88  5895.7  458.90
#Mann=6,-1,0
  4052.3    0.05       0  4151.8    0.12       0  4992.6    0.07       0
  4996.9    0.12       0  5023.6    0.05       0  5735.3   0.075       0
Bank Sta=4992.6,4996.9
Exp/Cntr=0.3,0.1

Type RM Length L Ch R = 1,5000,500,500,500
BEGIN DESCRIPTION:
Kings Creek Trib 1 10.0
END DESCRIPTION:
XS GIS Cut Line= 3
      2654326.03      6947061.02      2653526.11      6946433.80
      2653025.99      6945910.99
#Sta/Elev= 30
  3983.5  467.18  4059.1  466.06  4332.5  463.29  4688.7  449.29  4709.5  444.45
  4723.9  445.39  4732.0  448.99  4752.8  450.51  4802.6  450.83  4823.4  449.14
  4902.0  450.44  4951.7  449.16  4978.1  442.91  4978.8  442.41  4983.3  442.91
  4995.1  446.63  5030.5  448.91  5094.0  447.96  5263.8  450.72  5334.6  448.37
  5492.0  454.36  5525.3  454.78  5553.8  455.02  5560.7  456.86  5596.3  456.17
  5610.4  464.23  5617.3  466.10  5645.6  469.30  5719.3  470.56  5723.5  470.61
#Mann=7,-1,0
  3983.5    0.05       0  4059.1    0.12       0  4978.1    0.07       0
  4983.3    0.12       0  5492.0    0.05       0  5525.3   0.075       0
  5719.3     0.1       0
Bank Sta=4978.1,4983.3
Exp/Cntr=0.3,0.1

Type RM Length L Ch R = 1,4500,513,513,513
BEGIN DESCRIPTION:
Kings Creek Trib 1 9.0
END DESCRIPTION:
XS GIS Cut Line= 3
      2654794.95      6946471.02      2653625.70      6945989.01
      2653125.96      6945810.99
#Sta/Elev= 30
  3735.3  464.77  3830.4  464.47  3986.5  461.83  4039.8  458.65  4111.6  461.12
  4295.3  460.06  4537.8  449.13  4575.2  442.30  4575.9  441.80  4580.4  442.30
  4585.7  444.99  4599.5  446.97  4615.0  445.71  4697.6  448.49  4815.8  448.10
  4852.1  443.77  4876.0  447.91  4899.9  444.21  4913.1  447.04  4923.9  446.76
  4934.8  443.90  4989.0  446.10  5037.8  448.38  5063.3  444.80  5130.3  449.49
  5212.0  450.63  5352.8  457.34  5477.4  460.68  5510.2  464.43  5530.5  464.89
#Mann=7,-1,0
  3735.3    0.05       0  3830.4    0.12       0  4575.2    0.03       0
  4580.4    0.12       0  4989.0    0.05       0  5352.8   0.075       0
  5510.2     0.1       0
Bank Sta=4575.2,4580.4
Exp/Cntr=0.3,0.1

Type RM Length L Ch R = 1,3987,678,678,678
BEGIN DESCRIPTION:
Kings Creek Trib 1 8.0
END DESCRIPTION:
XS GIS Cut Line= 3
      2654925.17      6946167.21      2653701.20      6945481.44
      2652924.27      6945542.20
#Sta/Elev= 30
  3683.5  463.52  3741.1  463.13  4026.4  460.94  4315.3  455.01  4450.5  448.68
  4487.3  441.92  4514.8  442.76  4590.0  445.73  4724.6  446.21  4789.7  445.56
  4811.4  442.07  4876.5  446.54  4898.2  442.07  4922.3  443.61  4966.4  443.70
  4976.6  437.73  4977.3  437.23  4981.9  437.73  4989.3  439.17  4995.2  443.84
  5060.2  442.88  5076.2  448.85  5101.7  450.21  5286.9  451.72  5338.6  453.06
  5537.7  458.96  5637.2  463.74  5673.5  462.73  5713.6  468.59  5865.8  474.20
#Mann=11,-1,0
  3683.5    0.05       0  3741.1    0.12       0  4315.3    0.05       0
  4514.8    0.12       0  4922.3    0.05       0  4976.6    0.03       0
  4981.9    0.05       0  5286.9   0.075       0  5338.6     0.1       0
  5537.7   0.075       0  5637.2    0.05       0
Bank Sta=4976.6,4981.9
Exp/Cntr=0.3,0.1

Type RM Length L Ch R = 1,3309,736,736,736
BEGIN DESCRIPTION:
Mapping XS 5319193a
END DESCRIPTION:
XS GIS Cut Line= 6
      2655580.51      6945177.59      2655156.71      6944774.74
      2653709.88      6945103.83      2653119.60      6945329.53
      2652763.70      6945520.50      2652546.66      6945780.94
#Sta/Elev= 30
  3353.4  455.59  4011.1  453.04  4341.2  442.60  4888.6  444.72  4919.3  440.33
  4959.9  443.69  4987.7  438.24  4988.4  437.74  4993.0  438.24  5032.6  438.80
  5071.6  444.59  5288.2  449.51  5497.2  453.15  5679.8  450.65  5989.1  456.54
  6066.6  452.89  6132.4  457.01  6258.2  456.19  6353.5  463.95  6406.0  463.68
  6444.2  467.16  6449.9  470.87  6470.8  470.33  6478.8  468.60  6493.1  475.68
  6499.6  472.28  6507.4  476.39  6513.9  473.34  6692.3  471.46  6797.8  466.09
#Mann=7,-1,0
  3353.4    0.05       0  4987.7    0.03       0  4993.0    0.05       0
  5288.2   0.075       0  5497.2    0.05       0  6353.5   0.075       0
  6470.8    0.05       0
Bank Sta=4987.7,4993
Exp/Cntr=0.3,0.1

Type RM Length L Ch R = 1,2573,984,984,984
BEGIN DESCRIPTION:
Mapping XS 1d17f964
END DESCRIPTION:
XS GIS Cut Line= 6
      2655667.34      6945134.21      2655104.62      6944282.55
      2654273.90      6944529.95      2653870.47      6944756.61
      2652585.74      6945316.50      2652477.25      6945754.84
#Sta/Elev= 30
  3384.6  454.73  4000.2  450.64  4036.3  445.38  4253.0  444.62  4289.2  448.45
  4581.3  441.06  4894.3  441.18  4915.2  439.56  4933.4  431.86  4934.1  431.36
  4938.8  431.86  4942.1  436.98  4947.4  432.32  4988.2  442.79  5249.1  441.64
  5631.3  451.31  5772.0  447.80  6456.6  459.39  6621.5  455.44  6719.2  458.42
  6803.6  466.25  6860.2  464.74  6945.8  470.75  6952.3  466.75  7019.6  460.79
  7133.4  463.85  7182.8  456.76  7451.9  457.70  7512.4  469.42  7588.5  466.71
#Mann=5,-1,0
  3384.6    0.05       0  4933.4    0.03       0  4938.8    0.05       0
  6719.2   0.075       0  6952.3    0.05       0
Bank Sta=4933.4,4938.8
Exp/Cntr=0.3,0.1

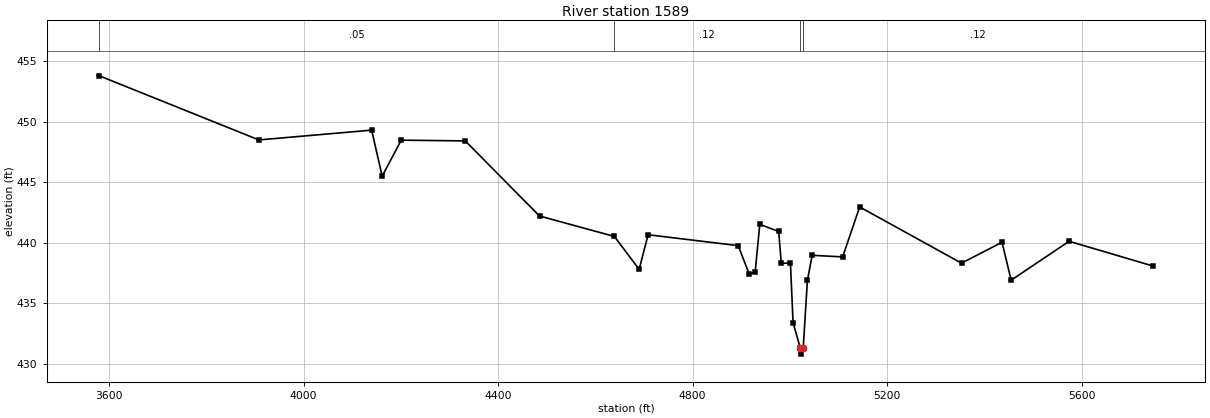
Type RM Length L Ch R = 1,1589,0,0,0
BEGIN DESCRIPTION:
Kings Creek Trib 1 4.0
END DESCRIPTION:
XS GIS Cut Line= 3
      2655693.67      6945090.20      2654989.65      6943344.22
      2654793.66      6943140.17
#Sta/Elev= 30
  3580.3  453.81  3908.3  448.51  4140.1  449.32  4161.7  445.51  4200.9  448.49
  4332.5  448.43  4485.2  442.22  4639.0  440.53  4690.0  437.81  4708.4  440.67
  4893.6  439.77  4916.4  437.40  4928.5  437.60  4938.0  441.53  4976.8  440.94
  4982.2  438.31  5001.0  438.33  5006.4  433.40  5021.3  431.30  5022.3  430.80
  5027.3  431.30  5035.9  436.92  5045.8  438.97  5108.4  438.84  5143.3  442.97
  5352.7  438.32  5436.0  440.05  5454.7  436.91  5573.9  440.13  5745.8  438.09
#Mann=4,-1,0
  3580.3    0.05       0  4639.0    0.12       0  5021.3    0.07       0
  5027.3    0.12       0
Bank Sta=5021.3,5027.3
Exp/Cntr=0.3,0.1

Chan Stop Cuts=-1