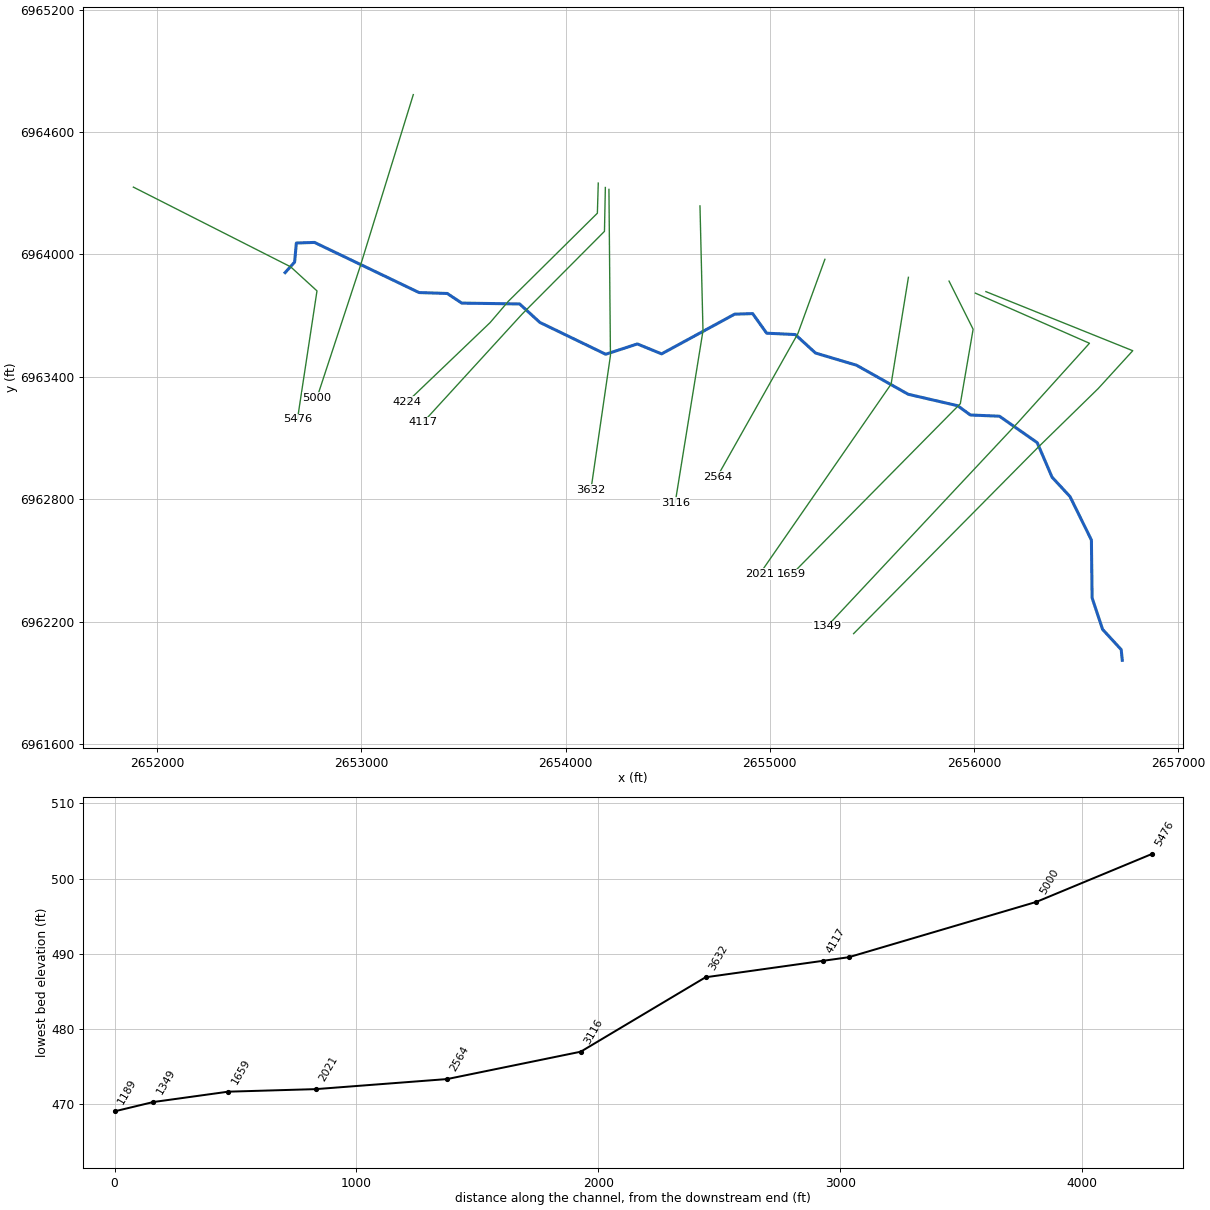
--- Kings Creek Trib 10.prj (project) ---

Proj Title=Kings Creek Trib 10 Base Level Engineering
Current Plan=p01
Default Exp/Contr=0.3,0.1
English Units
Geom File=g01
Flow File=f01
Plan File=p01
BEGIN DESCRIPTION:
Kings Creek Trib 10
END DESCRIPTION:

--- Kings Creek Trib 10.p01 (plan) ---

Plan Title=Multiple Run
Short Identifier=Multiple
Geom File=g01
Flow File=f01
Subcritical Flow
K Sum by GR= 0
Std Step Tol= 0.01
Critical Tol= 0.01
Num of Std Step Trials= 20
Max Error Tol= 0.3
Flow Tol Ratio= 0.001
Split Flow NTrial= 30
Split Flow Tol= 0.02
Split Flow Ratio= 0.02
Log Output Level= 0
Friction Slope Method= 1
Unsteady Friction Slope Method= 2
Unsteady Bridges Friction Slope Method= 1
Parabolic Critical Depth
Global Vel Dist=  1 , 1 , 1
Global Log Level= 0
CheckData=True
Encroach Param= -1, 0, 0, 0
BEGIN DESCRIPTION:
Multiple Run
END DESCRIPTION:

--- Kings Creek Trib 10.f01 (steady flow) ---

Flow Title=Multiple
Number of Profiles=7
Profile Names=10-year,25-year,50-year,1pct_min,100-year,1pct_plu,500-year
River Rch & RM= Kings Creek Trib,Reach-1,5476
     400     524     622     367     733    1462    1015
River Rch & RM= Kings Creek Trib,Reach-1,3116
     467     618     738     438     874    1743    1223
Boundary for River Rch & Prof#=Kings Creek Trib,Reach-1,1
Up Type=0
Dn Type=3
Dn Slope=0.005
Boundary for River Rch & Prof#=Kings Creek Trib,Reach-1,2
Up Type=0
Dn Type=3
Dn Slope=0.005
Boundary for River Rch & Prof#=Kings Creek Trib,Reach-1,3
Up Type=0
Dn Type=3
Dn Slope=0.005
Boundary for River Rch & Prof#=Kings Creek Trib,Reach-1,4
Up Type=0
Dn Type=3
Dn Slope=0.005
Boundary for River Rch & Prof#=Kings Creek Trib,Reach-1,5
Up Type=0
Dn Type=3
Dn Slope=0.005
Boundary for River Rch & Prof#=Kings Creek Trib,Reach-1,6
Up Type=0
Dn Type=3
Dn Slope=0.005
Boundary for River Rch & Prof#=Kings Creek Trib,Reach-1,7
Up Type=0
Dn Type=3
Dn Slope=0.005

--- Kings Creek Trib 10.g01 (geometry) ---

Geom Title=Existing Conditions

River Reach=Kings Creek Trib,Reach-1
Reach XY= 30
      2652626.00      6963911.00      2652672.56      6963962.51
      2652681.07      6964056.08      2652769.94      6964058.90
      2653281.93      6963813.25      2653420.06      6963808.73
      2653491.22      6963761.52      2653774.53      6963757.45
      2653873.71      6963666.85      2654196.10      6963510.89
      2654351.00      6963561.39      2654469.89      6963512.80
      2654827.59      6963707.33      2654915.66      6963710.11
      2654984.32      6963614.11      2655124.52      6963607.44
      2655223.71      6963516.85      2655424.42      6963457.17
      2655677.58      6963314.83      2655920.02      6963258.64
      2655981.94      6963213.27      2656124.44      6963207.24
      2656309.37      6963077.71      2656381.85      6962908.71
      2656470.15      6962813.29      2656574.80      6962600.50
      2656578.26      6962316.94      2656629.61      6962162.50
      2656720.67      6962063.51      2656726.00      6962011.00

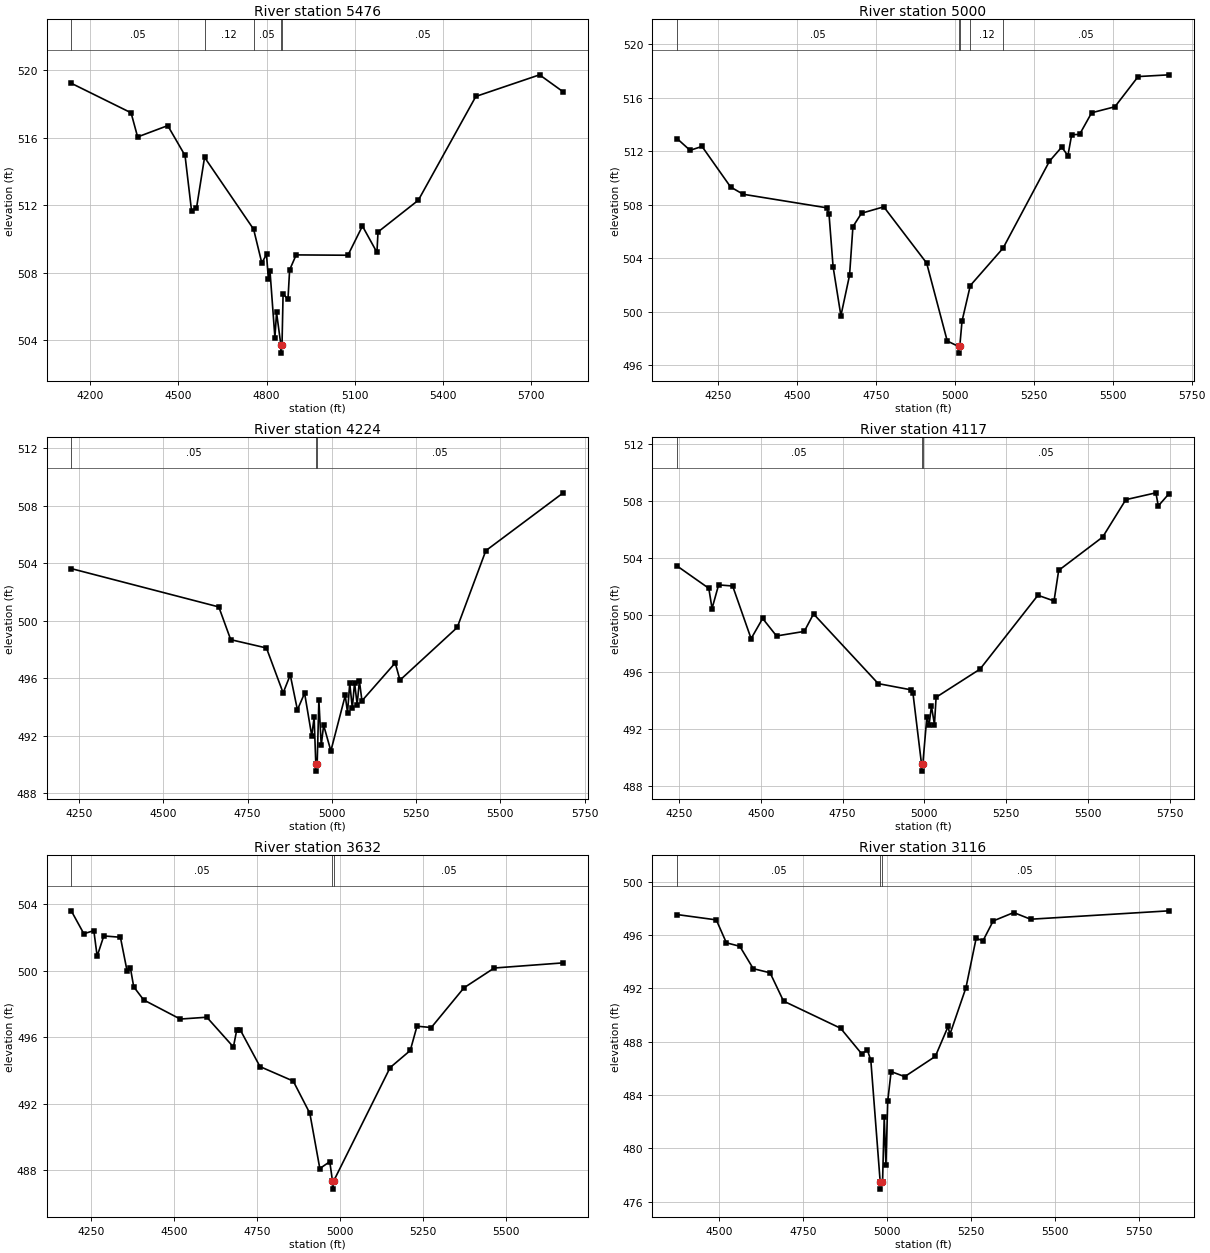
Type RM Length L Ch R = 1,5476,476,476,476
BEGIN DESCRIPTION:
Mapping XS 2e6094c9
END DESCRIPTION:
XS GIS Cut Line= 4
      2651882.94      6964329.98      2652653.14      6963939.36
      2652782.11      6963821.44      2652686.31      6963191.33
#Sta/Elev= 30
  4134.8  519.24  4338.5  517.49  4360.8  516.06  4463.4  516.73  4522.3  514.96
  4544.5  511.68  4561.2  511.83  4588.8  514.85  4755.9  510.59  4783.8  508.59
  4799.8  509.10  4806.1  507.66  4811.7  508.11  4828.4  504.17  4834.0  505.66
  4848.6  503.75  4848.9  503.25  4852.6  503.75  4856.3  506.77  4872.9  506.43
  4878.5  508.18  4900.8  509.07  5077.1  509.05  5126.5  510.78  5175.9  509.22
  5179.6  510.43  5316.9  512.31  5512.8  518.46  5729.9  519.74  5810.5  518.73
#Mann=5,-1,0
  4134.8    0.05       0  4588.8    0.12       0  4755.9    0.05       0
  4848.6    0.03       0  4852.6    0.05       0
Bank Sta=4848.6,4852.6
Exp/Cntr=0.3,0.1

Type RM Length L Ch R = 1,5000,776,776,776
BEGIN DESCRIPTION:
Kings Creek Trib 10 10.0
END DESCRIPTION:
XS GIS Cut Line= 3
      2653253.81      6964783.27      2652994.00      6963942.49
      2652782.11      6963298.14
#Sta/Elev= 30
  4120.0  512.95  4161.2  512.07  4199.1  512.36  4289.8  509.32  4329.6  508.78
  4593.4  507.77  4601.2  507.34  4614.3  503.35  4639.0  499.69  4666.4  502.72
  4677.1  506.36  4704.3  507.36  4774.8  507.84  4910.6  503.63  4975.8  497.80
  5011.5  497.39  5011.7  496.89  5015.5  497.39  5022.6  499.28  5048.9  501.95
  5152.7  504.75  5299.7  511.26  5338.4  512.31  5358.0  511.67  5370.0  513.24
  5395.0  513.26  5433.2  514.88  5506.9  515.33  5580.5  517.59  5678.3  517.72
#Mann=5,-1,0
  4120.0    0.05       0  5011.5    0.03       0  5015.5    0.05       0
  5048.9    0.12       0  5152.7    0.05       0
Bank Sta=5011.5,5015.5
Exp/Cntr=0.3,0.1

Type RM Length L Ch R = 1,4224,107,107,107
BEGIN DESCRIPTION:
Mapping XS 4af39917
END DESCRIPTION:
XS GIS Cut Line= 5
      2654159.67      6964349.74      2654155.33      6964202.20
      2653719.13      6963770.34      2653630.16      6963666.18
      2653224.32      6963277.71
#Sta/Elev= 30
  4226.7  503.63  4664.6  500.96  4699.9  498.68  4806.0  498.10  4855.5  494.97
  4876.7  496.22  4897.9  493.79  4919.2  494.95  4940.4  491.99  4947.5  493.26
  4952.5  490.02  4952.7  489.52  4956.5  490.02  4961.6  494.46  4968.6  491.31
  4975.7  492.72  4997.2  490.93  5039.9  494.79  5046.6  493.59  5053.2  495.65
  5060.9  493.91  5067.5  495.69  5075.2  494.16  5081.8  495.81  5089.5  494.42
  5188.2  497.06  5202.3  495.86  5372.2  499.53  5457.1  504.88  5686.9  508.91
#Mann=3,-1,0
  4226.7    0.05       0  4952.5    0.03       0  4956.5    0.05       0
Bank Sta=4952.5,4956.5
Exp/Cntr=0.3,0.1

Type RM Length L Ch R = 1,4117,485,485,485
BEGIN DESCRIPTION:
Mapping XS 48dcedff
END DESCRIPTION:
XS GIS Cut Line= 4
      2654194.39      6964328.12      2654190.05      6964113.23
      2653786.41      6963707.41      2653302.44      6963177.87
#Sta/Elev= 30
  4243.6  503.46  4340.7  501.89  4350.7  500.47  4370.7  502.13  4413.7  502.05
  4470.1  498.35  4505.4  499.77  4547.8  498.54  4632.7  498.86  4661.0  500.09
  4858.9  495.19  4957.9  494.76  4965.0  494.54  4991.3  489.54  4991.6  489.04
  4995.3  489.54  5007.5  492.81  5014.5  492.30  5021.6  493.61  5030.9  492.31
  5035.9  494.23  5170.3  496.21  5347.3  501.40  5396.6  501.00  5410.8  503.15
  5545.3  505.49  5616.2  508.12  5708.1  508.60  5715.5  507.68  5748.3  508.54
#Mann=3,-1,0
  4243.6    0.05       0  4991.3    0.03       0  4995.3    0.05       0
Bank Sta=4991.3,4995.3
Exp/Cntr=0.3,0.1

Type RM Length L Ch R = 1,3632,516,516,516
BEGIN DESCRIPTION:
Mapping XS 9f55519c
END DESCRIPTION:
XS GIS Cut Line= 3
      2654211.93      6964318.88      2654219.30      6963504.52
      2654123.56      6962845.43
#Sta/Elev= 30
  4191.3  503.59  4229.2  502.21  4259.2  502.40  4269.2  500.86  4289.2  502.08
  4339.2  502.00  4359.2  499.98  4369.2  500.16  4379.2  499.02  4409.2  498.23
  4519.2  497.08  4599.2  497.19  4679.2  495.40  4689.2  496.42  4699.2  496.45
  4759.2  494.22  4859.2  493.35  4909.2  491.41  4939.2  488.09  4969.2  488.50
  4977.2  487.35  4977.5  486.85  4981.2  487.35  5150.7  494.16  5211.4  495.19
  5231.6  496.65  5274.6  496.57  5373.0  498.96  5464.0  500.15  5671.7  500.46
#Mann=3,-1,0
  4191.3    0.05       0  4977.2    0.03       0  4981.2    0.05       0
Bank Sta=4977.2,4981.2
Exp/Cntr=0.3,0.1

Type RM Length L Ch R = 1,3116,552,552,552
BEGIN DESCRIPTION:
Mapping XS 7ee9e55d
END DESCRIPTION:
XS GIS Cut Line= 3
      2654657.82      6964237.88      2654672.56      6963626.13
      2654536.51      6962784.08
#Sta/Elev= 30
  4375.7  497.54  4492.6  497.14  4522.6  495.42  4562.6  495.16  4602.6  493.48
  4652.7  493.17  4692.7  491.05  4862.7  489.01  4925.2  487.10  4942.7  487.36
  4952.7  486.60  4980.7  477.44  4980.9  476.94  4984.7  477.44  4987.6  477.44
  4992.6  482.33  4997.7  478.76  5003.0  483.55  5013.1  485.76  5053.6  485.38
  5144.8  486.90  5182.9  489.15  5187.9  488.53  5235.9  492.05  5266.3  495.76
  5286.6  495.57  5317.0  497.06  5378.2  497.69  5428.4  497.19  5840.6  497.82
#Mann=3,-1,0
  4375.7    0.05       0  4980.7    0.03       0  4984.7    0.05       0
Bank Sta=4980.7,4984.7
Exp/Cntr=0.3,0.1

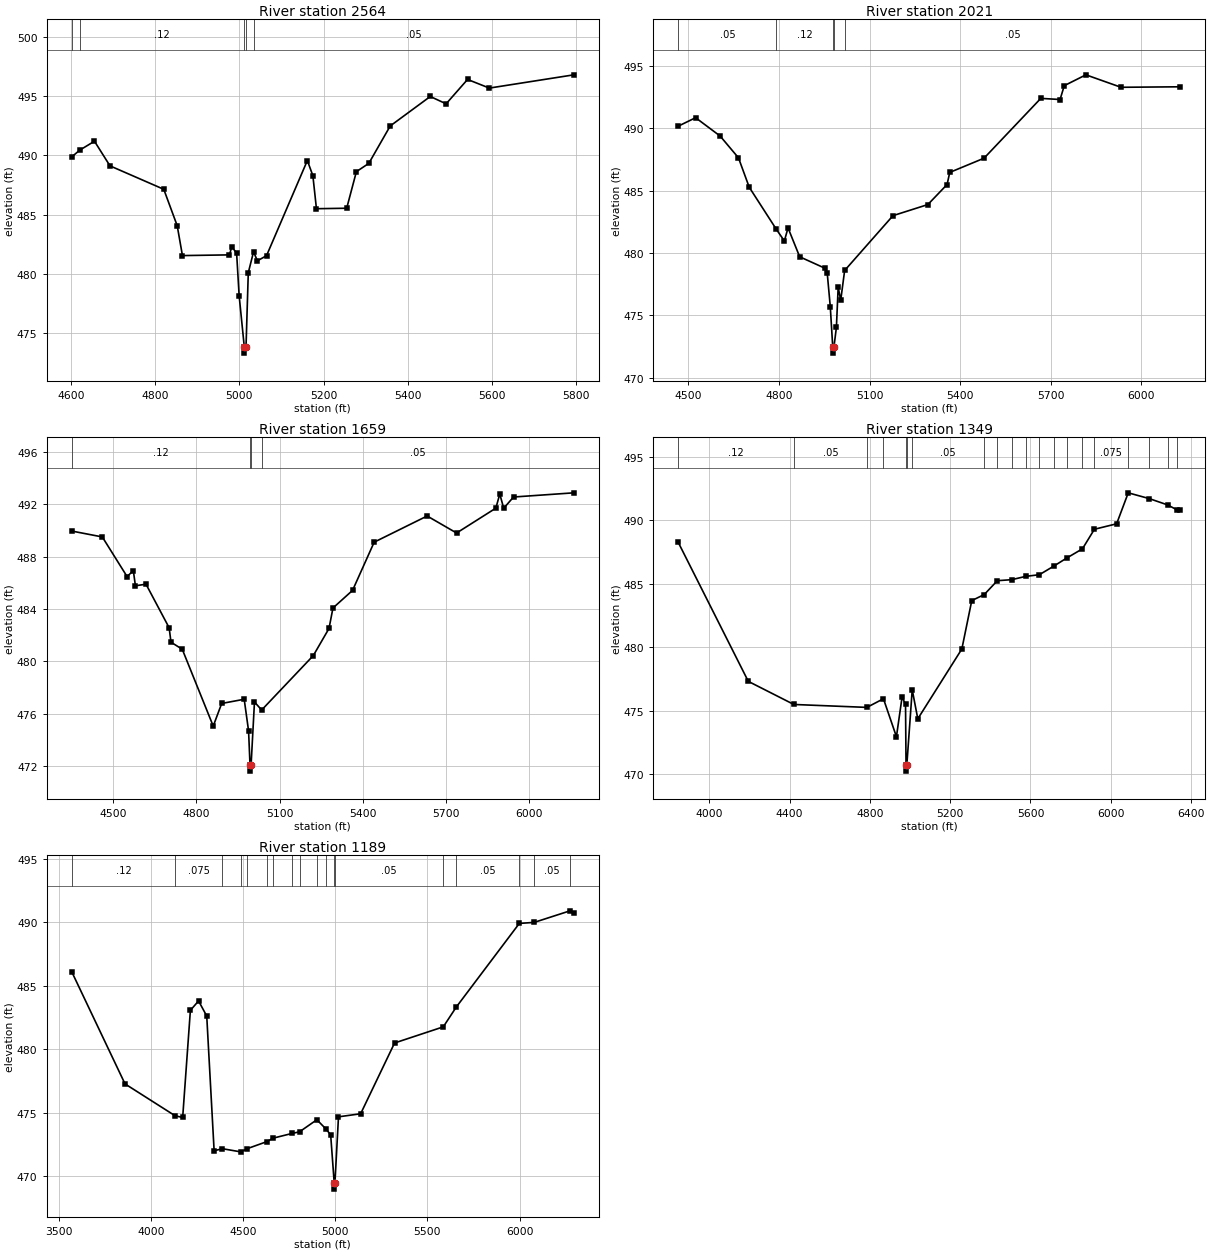
Type RM Length L Ch R = 1,2564,543,543,543
BEGIN DESCRIPTION:
Mapping XS b715bd37
END DESCRIPTION:
XS GIS Cut Line= 3
      2655269.55      6963976.23      2655136.88      6963611.39
      2654742.57      6962911.20
#Sta/Elev= 30
  4602.3  489.88  4621.3  490.45  4656.2  491.20  4693.0  489.12  4820.7  487.14
  4852.6  484.06  4865.0  481.54  4976.7  481.60  4982.0  482.29  4993.6  481.75
  4999.6  478.15  5011.9  473.80  5012.2  473.30  5015.9  473.80  5021.3  480.09
  5033.8  481.86  5042.9  481.10  5064.6  481.53  5161.5  489.57  5174.6  488.29
  5183.1  485.50  5254.9  485.54  5277.9  488.63  5307.4  489.33  5358.2  492.49
  5453.3  494.98  5490.9  494.36  5541.8  496.42  5593.5  495.69  5794.1  496.81
#Mann=5,-1,0
  4602.3    0.05       0  4621.3    0.12       0  5011.9    0.07       0
  5015.9    0.12       0  5033.8    0.05       0
Bank Sta=5011.9,5015.9
Exp/Cntr=0.3,0.1

Type RM Length L Ch R = 1,2021,362,362,362
BEGIN DESCRIPTION:
Mapping XS 9446397a
END DESCRIPTION:
XS GIS Cut Line= 3
      2655678.59      6963887.79      2655593.83      6963364.49
      2654950.00      6962433.68
#Sta/Elev= 30
  4466.7  490.17  4524.2  490.85  4605.3  489.38  4666.1  487.63  4701.7  485.27
  4791.8  481.88  4818.0  480.96  4830.1  482.01  4868.7  479.69  4953.4  478.76
  4959.8  478.40  4970.0  475.69  4978.1  472.46  4978.3  471.96  4982.1  472.46
  4990.2  474.02  4996.1  477.25  5004.5  476.20  5017.5  478.59  5177.5  482.99
  5292.9  483.88  5356.6  485.49  5365.4  486.46  5478.9  487.60  5666.8  492.40
  5730.6  492.31  5744.5  493.42  5816.1  494.29  5932.4  493.29  6128.6  493.33
#Mann=5,-1,0
  4466.7    0.05       0  4791.8    0.12       0  4978.1    0.07       0
  4982.1    0.12       0  5017.5    0.05       0
Bank Sta=4978.1,4982.1
Exp/Cntr=0.3,0.1

Type RM Length L Ch R = 1,1659,310,310,310
BEGIN DESCRIPTION:
Mapping XS f9ddf854
END DESCRIPTION:
XS GIS Cut Line= 4
      2655877.58      6963869.35      2655995.51      6963633.50
      2655932.86      6963268.67      2655107.38      6962432.14
#Sta/Elev= 30
  4351.0  489.96  4461.0  489.51  4550.4  486.48  4572.8  486.94  4580.3  485.78
  4618.5  485.90  4701.9  482.57  4708.5  481.47  4749.1  480.93  4860.7  475.06
  4891.2  476.79  4972.3  477.11  4988.1  474.69  4993.2  472.12  4993.4  471.62
  4997.2  472.12  5009.3  476.90  5035.3  476.29  5221.4  480.45  5277.9  482.52
  5292.1  484.08  5362.8  485.43  5440.6  489.11  5631.5  491.11  5737.6  489.81
  5879.1  491.71  5893.2  492.79  5907.4  491.70  5942.7  492.56  6160.1  492.88
#Mann=4,-1,0
  4351.0    0.12       0  4993.2    0.07       0  4997.2    0.12       0
  5035.3    0.05       0
Bank Sta=4993.2,4997.2
Exp/Cntr=0.3,0.1

Type RM Length L Ch R = 1,1349,160,160,160
BEGIN DESCRIPTION:
Mapping XS 5f689695
END DESCRIPTION:
XS GIS Cut Line= 4
      2656006.58      6963810.38      2656565.27      6963564.72
      2656215.88      6963177.35      2655280.80      6962178.11
#Sta/Elev= 30
  3845.8  488.26  4194.7  477.31  4421.6  475.49  4785.2  475.26  4867.8  475.94
  4932.5  472.95  4960.7  476.09  4977.8  475.49  4980.3  470.74  4980.5  470.24
  4984.3  470.74  5011.1  476.65  5038.9  474.36  5258.3  479.86  5307.6  483.67
  5370.0  484.15  5435.0  485.24  5507.1  485.32  5576.3  485.58  5644.2  485.71
  5717.6  486.40  5781.3  487.03  5858.9  487.75  5918.4  489.29  6029.1  489.72
  6087.0  492.16  6192.6  491.70  6282.7  491.21  6329.8  490.82  6346.3  490.81
#Mann=20,-1,0
  3845.8    0.12       0  4421.6    0.05       0  4785.2   0.075       0
  4867.8    0.05       0  4980.3    0.07       0  4984.3   0.075       0
  5011.1    0.05       0  5370.0   0.075       0  5435.0    0.05       0
  5507.1   0.075       0  5576.3    0.05       0  5644.2   0.075       0
  5717.6    0.05       0  5781.3   0.075       0  5858.9    0.05       0
  5918.4   0.075       0  6087.0    0.05       0  6192.6   0.075       0
  6282.7    0.05       0  6329.8   0.075       0
Bank Sta=4980.3,4984.3
Exp/Cntr=0.3,0.1

Type RM Length L Ch R = 1,1189,0,0,0
BEGIN DESCRIPTION:
Kings Creek Trib 10 3.0
END DESCRIPTION:
XS GIS Cut Line= 5
      2656058.14      6963817.76      2656777.32      6963528.24
      2656608.67      6963343.37      2656312.45      6963053.66
      2655410.30      6962141.77
#Sta/Elev= 30
  3571.9  486.10  3860.7  477.28  4132.6  474.77  4173.3  474.64  4215.1  483.07
  4259.5  483.81  4303.8  482.62  4343.8  472.02  4388.9  472.18  4489.0  471.93
  4524.4  472.19  4630.3  472.74  4663.5  473.01  4765.6  473.38  4807.0  473.51
  4900.9  474.46  4950.5  473.73  4975.8  473.27  4995.0  469.50  4995.2  469.00
  4999.0  469.50  5018.2  474.69  5138.4  474.93  5322.3  480.50  5586.5  481.77
  5656.6  483.32  5998.8  489.91  6079.6  489.99  6273.7  490.90  6294.5  490.76
#Mann=18,-1,0
  3571.9    0.12       0  4132.6   0.075       0  4388.9    0.05       0
  4489.0   0.075       0  4524.4    0.05       0  4630.3   0.075       0
  4663.5    0.05       0  4765.6   0.075       0  4807.0    0.05       0
  4900.9   0.075       0  4950.5    0.05       0  4995.0    0.03       0
  4999.0    0.05       0  5586.5   0.075       0  5656.6    0.05       0
  5998.8   0.075       0  6079.6    0.05       0  6273.7   0.075       0
Bank Sta=4995,4999
Exp/Cntr=0.3,0.1

Chan Stop Cuts=-1