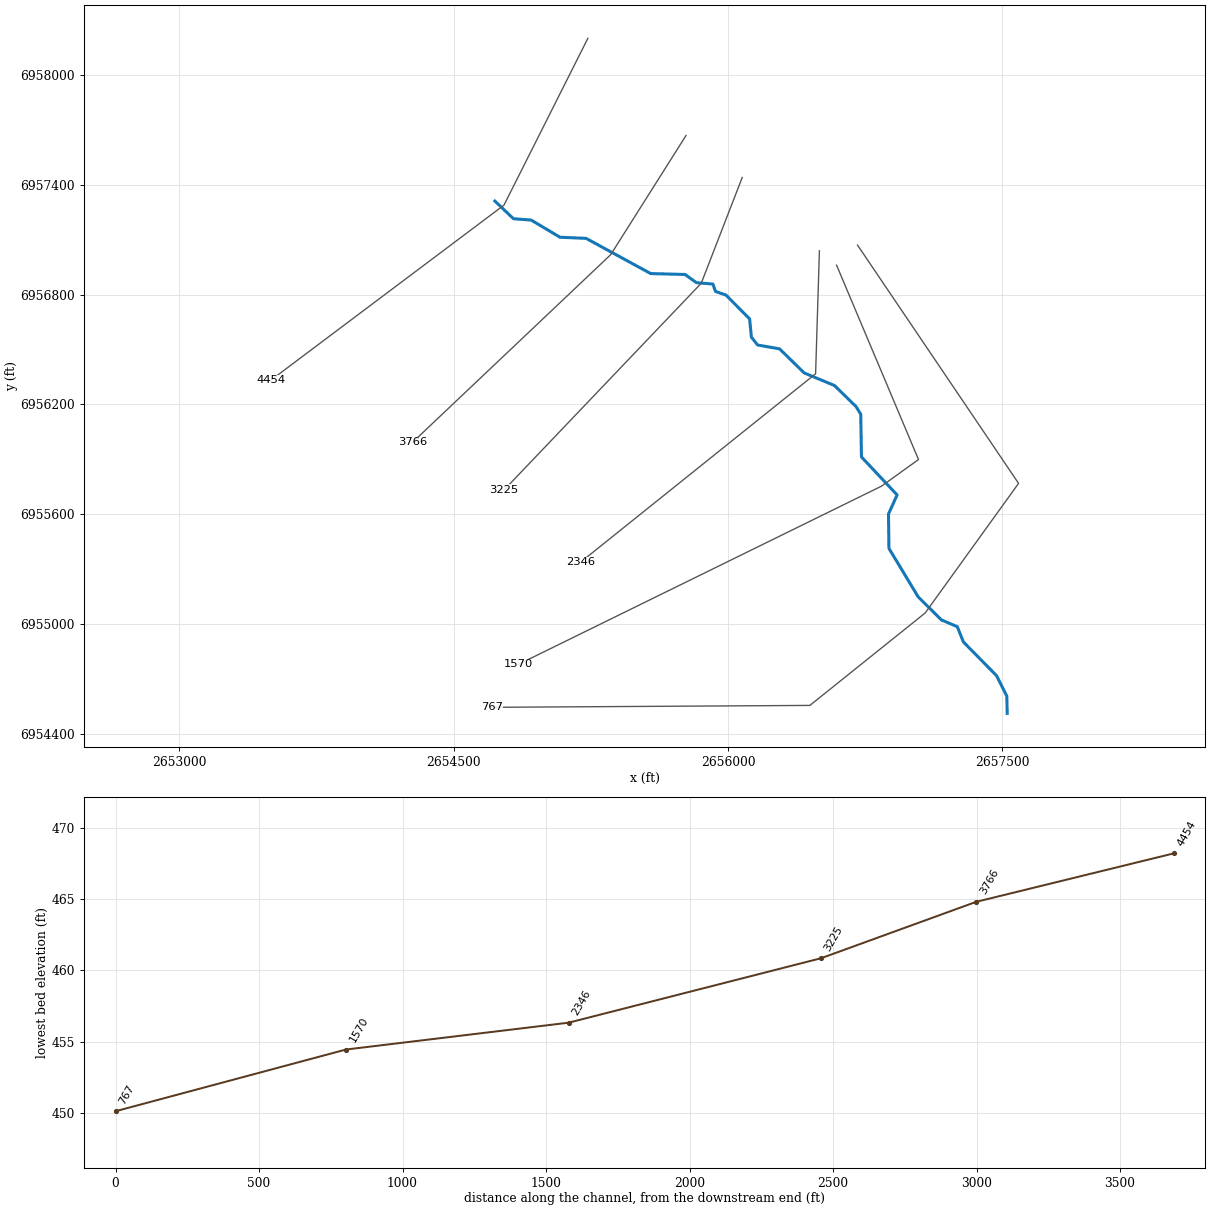
--- Kings Creek Trib 11.prj (project) ---

Proj Title=Kings Creek Trib 11 Base Level Engineering
Current Plan=p01
Default Exp/Contr=0.3,0.1
English Units
Geom File=g01
Flow File=f01
Plan File=p01
BEGIN DESCRIPTION:
Kings Creek Trib 11
END DESCRIPTION:

--- Kings Creek Trib 11.p01 (plan) ---

Plan Title=Multiple Run
Short Identifier=Multiple
Geom File=g01
Flow File=f01
Subcritical Flow
K Sum by GR= 0
Std Step Tol= 0.01
Critical Tol= 0.01
Num of Std Step Trials= 20
Max Error Tol= 0.3
Flow Tol Ratio= 0.001
Split Flow NTrial= 30
Split Flow Tol= 0.02
Split Flow Ratio= 0.02
Log Output Level= 0
Friction Slope Method= 1
Unsteady Friction Slope Method= 2
Unsteady Bridges Friction Slope Method= 1
Parabolic Critical Depth
Global Vel Dist=  1 , 1 , 1
Global Log Level= 0
CheckData=True
Encroach Param= -1, 0, 0, 0
BEGIN DESCRIPTION:
Multiple Run
END DESCRIPTION:

--- Kings Creek Trib 11.f01 (steady flow) ---

Flow Title=Multiple
Number of Profiles=7
Profile Names=10-year,25-year,50-year,1pct_min,100-year,1pct_plu,500-year
River Rch & RM= Kings Creek Trib,Reach-1,4454
     598     805     973     584    1165    2324    1670
River Rch & RM= Kings Creek Trib,Reach-1,2346
     692     938    1139     686    1369    2731    1977
Boundary for River Rch & Prof#=Kings Creek Trib,Reach-1,1
Up Type=0
Dn Type=3
Dn Slope=0.005
Boundary for River Rch & Prof#=Kings Creek Trib,Reach-1,2
Up Type=0
Dn Type=3
Dn Slope=0.005
Boundary for River Rch & Prof#=Kings Creek Trib,Reach-1,3
Up Type=0
Dn Type=3
Dn Slope=0.005
Boundary for River Rch & Prof#=Kings Creek Trib,Reach-1,4
Up Type=0
Dn Type=3
Dn Slope=0.005
Boundary for River Rch & Prof#=Kings Creek Trib,Reach-1,5
Up Type=0
Dn Type=3
Dn Slope=0.005
Boundary for River Rch & Prof#=Kings Creek Trib,Reach-1,6
Up Type=0
Dn Type=3
Dn Slope=0.005
Boundary for River Rch & Prof#=Kings Creek Trib,Reach-1,7
Up Type=0
Dn Type=3
Dn Slope=0.005

--- Kings Creek Trib 11.g01 (geometry) ---

Geom Title=Existing Conditions

River Reach=Kings Creek Trib,Reach-1
Reach XY= 30
      2654726.00      6957311.00      2654827.48      6957214.56
      2654924.41      6957207.17      2655081.93      6957113.25
      2655224.44      6957107.24      2655577.55      6956914.75
      2655765.50      6956909.78      2655827.67      6956864.88
      2655917.52      6956857.51      2655931.80      6956817.05
      2655989.00      6956797.31      2656118.14      6956667.17
      2656128.07      6956566.69      2656162.28      6956524.23
      2656282.17      6956503.14      2656416.32      6956371.77
      2656582.06      6956302.86      2656699.84      6956187.88
      2656725.62      6956145.84      2656729.54      6955912.46
      2656924.38      6955704.97      2656877.24      6955600.50
      2656879.75      6955412.55      2657039.63      6955147.79
      2657166.34      6955021.79      2657253.14      6954984.84
      2657286.79      6954901.34      2657467.86      6954717.06
      2657523.93      6954605.14      2657526.00      6954511.00

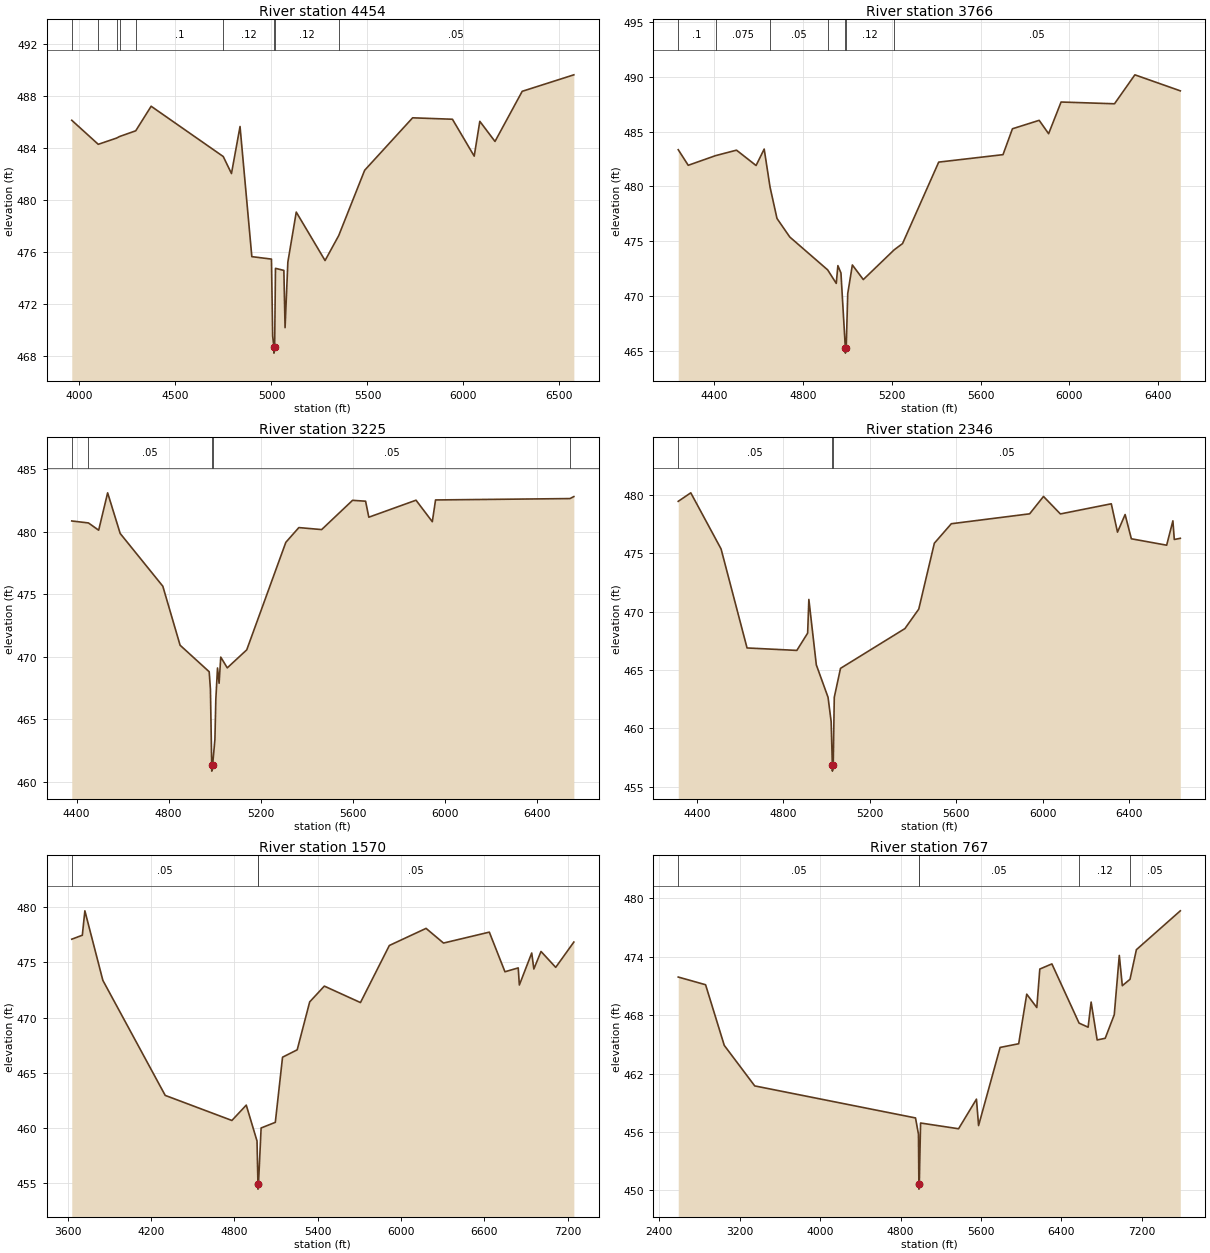
Type RM Length L Ch R = 1,4454,688,688,688
BEGIN DESCRIPTION:
Mapping XS faeae791
END DESCRIPTION:
XS GIS Cut Line= 3
      2655234.13      6958200.42      2654775.77      6957288.92
      2653500.36      6956331.06
#Sta/Elev= 30
  3959.8  486.12  4097.8  484.27  4193.4  484.75  4208.7  484.87  4293.0  485.31
  4373.3  487.20  4748.8  483.33  4791.7  482.02  4836.3  485.64  4897.7  475.62
  5000.0  475.43  5006.3  469.49  5012.6  468.69  5012.9  468.19  5016.6  468.69
  5020.9  474.72  5064.6  474.56  5070.9  470.15  5085.4  475.20  5129.2  479.05
  5279.2  475.32  5350.3  477.24  5485.4  482.27  5735.3  486.31  5942.7  486.20
  6056.1  483.36  6085.3  486.04  6164.4  484.49  6306.1  488.35  6575.1  489.62
#Mann=9,-1,0
  3959.8    0.05       0  4097.8   0.075       0  4193.4    0.05       0
  4208.7   0.075       0  4293.0     0.1       0  4748.8    0.12       0
  5012.6    0.07       0  5016.6    0.12       0  5350.3    0.05       0
Bank Sta=5012.6,5016.6
Exp/Cntr=0.3,0.1

Type RM Length L Ch R = 1,3766,541,541,541
BEGIN DESCRIPTION:
Mapping XS aff9555e
END DESCRIPTION:
XS GIS Cut Line= 3
      2655770.59      6957669.16      2655359.11      6957018.08
      2654275.78      6955992.05
#Sta/Elev= 30
  4237.6  483.35  4282.7  481.93  4405.8  482.81  4500.2  483.31  4588.4  481.91
  4624.9  483.41  4651.3  479.94  4682.6  477.08  4740.2  475.39  4911.0  472.39
  4949.6  471.16  4957.0  472.78  4970.8  472.11  4990.5  465.30  4990.8  464.80
  4994.5  465.30  5001.4  470.23  5022.2  472.84  5071.5  471.51  5211.1  474.23
  5248.3  474.79  5411.3  482.22  5701.0  482.90  5743.5  485.26  5864.0  486.03
  5906.5  484.81  5962.7  487.70  6203.4  487.54  6295.2  490.18  6499.9  488.72
#Mann=7,-1,0
  4237.6     0.1       0  4405.8   0.075       0  4651.3    0.05       0
  4911.0    0.12       0  4990.5    0.07       0  4994.5    0.12       0
  5211.1    0.05       0
Bank Sta=4990.5,4994.5
Exp/Cntr=0.3,0.1

Type RM Length L Ch R = 1,3225,879,879,879
BEGIN DESCRIPTION:
Mapping XS 13187f4e
END DESCRIPTION:
XS GIS Cut Line= 3
      2656077.86      6957439.97      2655853.90      6956861.83
      2654775.75      6955731.60
#Sta/Elev= 30
  4378.9  480.86  4451.6  480.70  4495.8  480.12  4534.8  483.11  4589.3  479.86
  4774.6  475.64  4849.7  470.92  4976.1  468.80  4981.5  467.40  4987.1  461.35
  4987.3  460.85  4991.1  461.35  5001.0  463.38  5005.0  466.60  5012.3  469.10
  5019.2  467.88  5026.4  469.97  5054.7  469.11  5139.3  470.55  5309.2  479.15
  5365.8  480.33  5464.9  480.17  5599.2  482.51  5655.8  482.44  5669.9  481.16
  5875.0  482.52  5945.8  480.80  5959.9  482.54  6544.2  482.65  6560.9  482.81
#Mann=5,-1,0
  4378.9   0.075       0  4451.6    0.05       0  4987.1    0.04       0
  4991.1    0.05       0  6544.2   0.075       0
Bank Sta=4987.1,4991.1
Exp/Cntr=0.3,0.1

Type RM Length L Ch R = 1,2346,776,776,776
BEGIN DESCRIPTION:
Mapping XS 1e7242db
END DESCRIPTION:
XS GIS Cut Line= 3
      2656499.73      6957038.95      2656478.90      6956367.04
      2655192.60      6955335.92
#Sta/Elev= 30
  4314.3  479.47  4372.3  480.20  4512.3  475.39  4632.4  466.90  4862.5  466.69
  4912.5  468.17  4918.1  471.06  4952.6  465.45  5006.8  462.67  5021.2  460.58
  5026.7  456.84  5026.9  456.34  5030.7  456.84  5035.6  462.67  5064.4  465.15
  5362.1  468.56  5426.1  470.23  5498.2  475.88  5576.6  477.55  5938.7  478.40
  6002.7  479.89  6080.7  478.39  6316.0  479.26  6344.8  476.83  6380.0  478.34
  6408.8  476.26  6572.0  475.71  6600.8  477.80  6607.3  476.20  6635.1  476.30
#Mann=3,-1,0
  4314.3    0.05       0  5026.7    0.03       0  5030.7    0.05       0
Bank Sta=5026.7,5030.7
Exp/Cntr=0.3,0.1

Type RM Length L Ch R = 1,1570,803,803,803
BEGIN DESCRIPTION:
Mapping XS bb26de90
END DESCRIPTION:
XS GIS Cut Line= 4
      2656593.48      6956960.79      2657041.40      6955898.29
      2656838.27      6955752.46      2654853.91      6954778.51
#Sta/Elev= 30
  3630.2  477.10  3706.2  477.46  3724.5  479.67  3854.0  473.37  4302.8  462.95
  4782.7  460.68  4886.1  462.07  4963.5  458.82  4970.1  454.96  4970.4  454.46
  4974.1  454.96  4993.0  460.00  5095.2  460.51  5147.2  466.41  5252.7  467.08
  5342.6  471.42  5448.0  472.85  5708.0  471.36  5915.9  476.53  6180.2  478.08
  6305.8  476.75  6635.5  477.74  6748.0  474.15  6843.5  474.50  6851.6  472.95
  6940.7  475.85  6955.9  474.40  7007.5  475.99  7113.3  474.55  7243.8  476.84
#Mann=3,-1,0
  3630.2    0.05       0  4970.1    0.04       0  4974.1    0.05       0
Bank Sta=4970.1,4974.1
Exp/Cntr=0.3,0.1

Type RM Length L Ch R = 1,767,0,0,0
BEGIN DESCRIPTION:
Mapping XS 2bee7555
END DESCRIPTION:
XS GIS Cut Line= 5
      2656708.07      6957070.16      2657588.27      6955768.08
      2657077.86      6955059.75      2656447.65      6954554.54
      2654709.54      6954544.13
#Sta/Elev= 30
  2590.5  471.92  2862.3  471.13  3048.2  464.90  3350.8  460.74  4949.0  457.45
  4978.4  455.78  4982.6  450.64  4982.8  450.14  4986.6  450.64  4999.3  456.93
  5377.1  456.34  5554.8  459.38  5575.9  456.67  5790.0  464.69  5974.6  465.07
  6054.6  470.16  6154.6  468.79  6184.6  472.74  6304.6  473.27  6574.8  467.19
  6664.6  466.77  6694.6  469.35  6754.6  465.46  6834.6  465.63  6924.6  468.05
  6974.6  474.14  7004.6  471.03  7081.2  471.69  7144.6  474.73  7581.1  478.72
#Mann=5,-1,0
  2590.5    0.05       0  4982.6    0.03       0  4986.6    0.05       0
  6574.8    0.12       0  7081.2    0.05       0
Bank Sta=4982.6,4986.6
Exp/Cntr=0.3,0.1

Chan Stop Cuts=-1