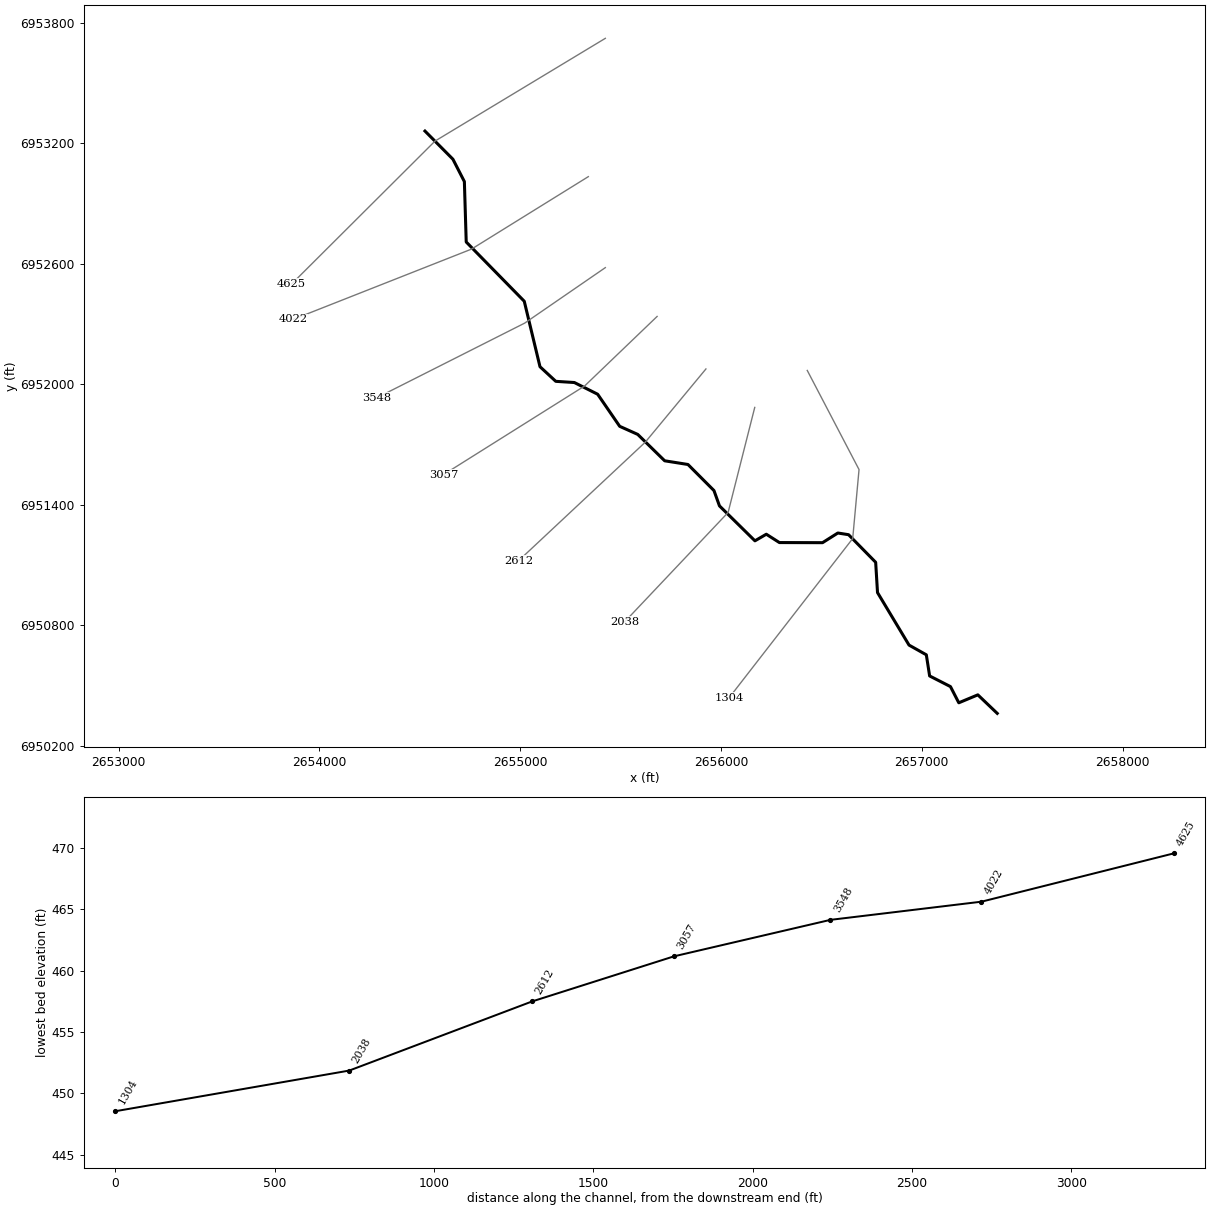
--- Kings Creek Trib 12.prj (project) ---

Proj Title=Kings Creek Trib 12 Base Level Engineering
Current Plan=p01
Default Exp/Contr=0.3,0.1
English Units
Geom File=g01
Flow File=f01
Plan File=p01
BEGIN DESCRIPTION:
Kings Creek Trib 12
END DESCRIPTION:

--- Kings Creek Trib 12.p01 (plan) ---

Plan Title=Multiple Run
Short Identifier=Multiple
Geom File=g01
Flow File=f01
Subcritical Flow
K Sum by GR= 0
Std Step Tol= 0.01
Critical Tol= 0.01
Num of Std Step Trials= 20
Max Error Tol= 0.3
Flow Tol Ratio= 0.001
Split Flow NTrial= 30
Split Flow Tol= 0.02
Split Flow Ratio= 0.02
Log Output Level= 0
Friction Slope Method= 1
Unsteady Friction Slope Method= 2
Unsteady Bridges Friction Slope Method= 1
Parabolic Critical Depth
Global Vel Dist=  1 , 1 , 1
Global Log Level= 0
CheckData=True
Encroach Param= -1, 0, 0, 0
BEGIN DESCRIPTION:
Multiple Run
END DESCRIPTION:

--- Kings Creek Trib 12.f01 (steady flow) ---

Flow Title=Multiple
Number of Profiles=7
Profile Names=10-year,25-year,50-year,1pct_min,100-year,1pct_plu,500-year
River Rch & RM= Kings Creek Trib,Reach-1,4625
     396     514     606     355     708    1412     963
River Rch & RM= Kings Creek Trib,Reach-1,2612
     519     685     818     484     966    1927    1347
Boundary for River Rch & Prof#=Kings Creek Trib,Reach-1,1
Up Type=0
Dn Type=3
Dn Slope=0.005
Boundary for River Rch & Prof#=Kings Creek Trib,Reach-1,2
Up Type=0
Dn Type=3
Dn Slope=0.005
Boundary for River Rch & Prof#=Kings Creek Trib,Reach-1,3
Up Type=0
Dn Type=3
Dn Slope=0.005
Boundary for River Rch & Prof#=Kings Creek Trib,Reach-1,4
Up Type=0
Dn Type=3
Dn Slope=0.005
Boundary for River Rch & Prof#=Kings Creek Trib,Reach-1,5
Up Type=0
Dn Type=3
Dn Slope=0.005
Boundary for River Rch & Prof#=Kings Creek Trib,Reach-1,6
Up Type=0
Dn Type=3
Dn Slope=0.005
Boundary for River Rch & Prof#=Kings Creek Trib,Reach-1,7
Up Type=0
Dn Type=3
Dn Slope=0.005

--- Kings Creek Trib 12.g01 (geometry) ---

Geom Title=Existing Conditions

River Reach=Kings Creek Trib,Reach-1
Reach XY= 30
      2654526.00      6953261.00      2654665.24      6953120.69
      2654722.25      6953009.45      2654731.46      6952708.55
      2655020.48      6952413.43      2655098.84      6952087.42
      2655177.48      6952014.61      2655270.03      6952008.67
      2655386.00      6951950.37      2655495.77      6951790.58
      2655585.68      6951750.22      2655719.83      6951618.86
      2655835.79      6951600.48      2655965.22      6951470.68
      2655992.65      6951394.33      2656169.33      6951220.30
      2656225.90      6951253.19      2656291.16      6951211.65
      2656505.97      6951211.09      2656582.14      6951259.22
      2656635.68      6951250.81      2656770.53      6951113.45
      2656779.76      6950962.56      2656936.71      6950701.03
      2657022.81      6950652.65      2657039.28      6950547.38
      2657143.00      6950494.40      2657184.51      6950413.69
      2657279.39      6950453.29      2657376.00      6950361.00

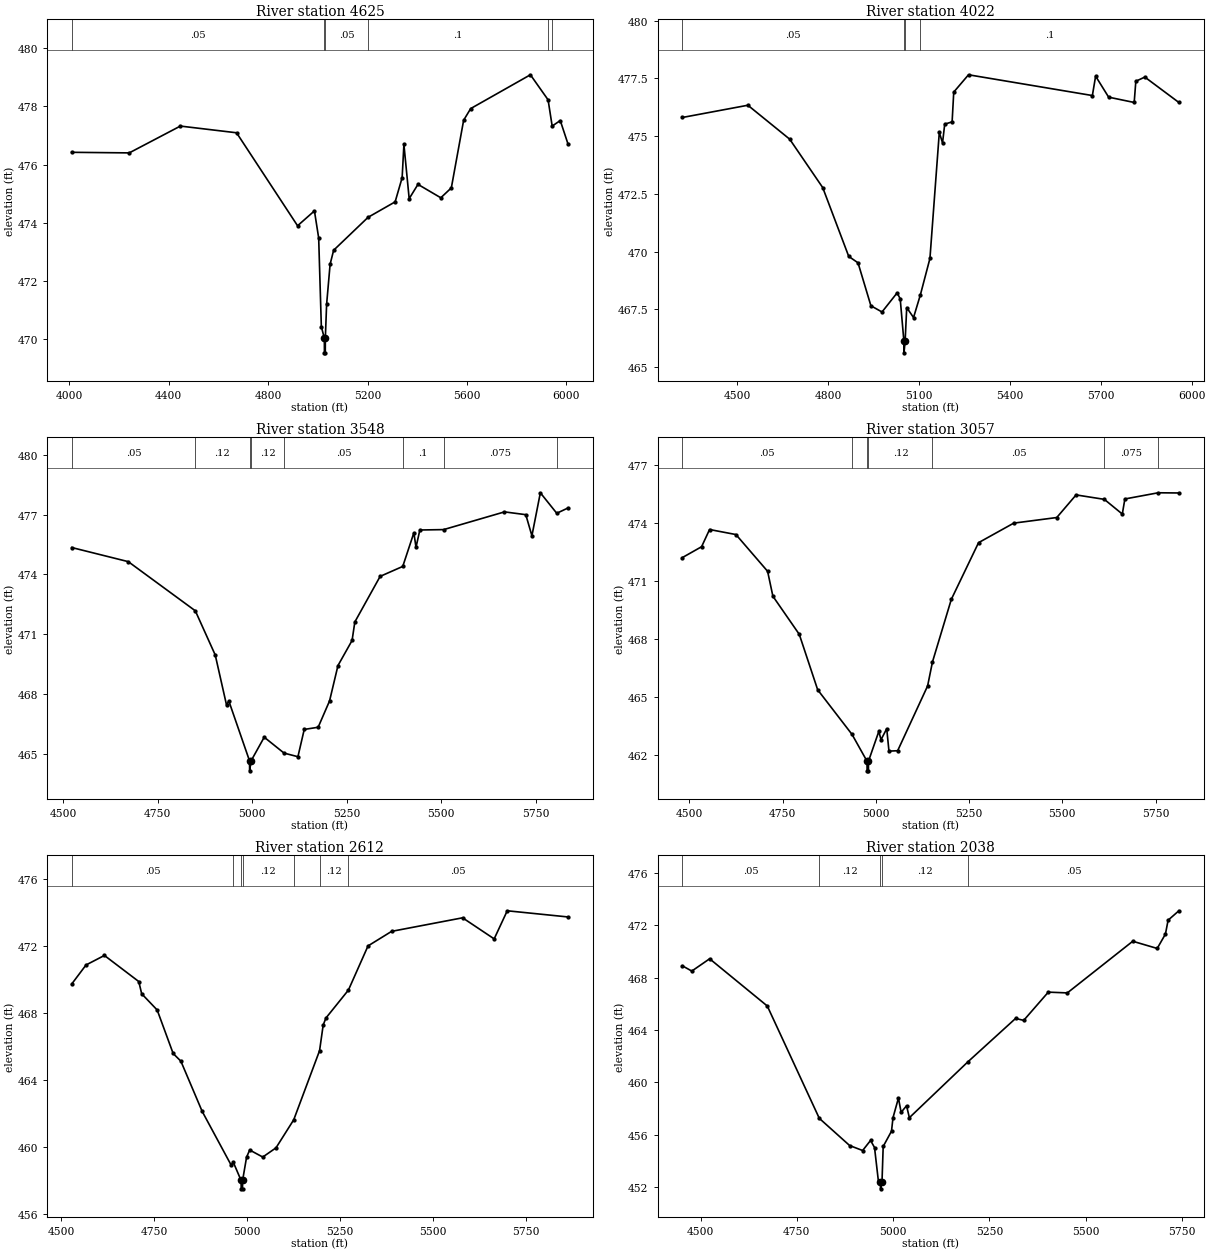
Type RM Length L Ch R = 1,4625,603,603,603
BEGIN DESCRIPTION:
Mapping XS 72fdb706
END DESCRIPTION:
XS GIS Cut Line= 3
      2655424.21      6953722.77      2654576.02      6953211.03
      2653862.40      6952499.84
#Sta/Elev= 30
  4009.4  476.42  4241.1  476.40  4446.8  477.32  4673.0  477.09  4918.5  473.90
  4986.4  474.41  5003.5  473.48  5014.2  470.44  5026.3  470.04  5026.6  469.54
  5030.1  469.54  5030.3  470.04  5035.4  471.20  5049.5  472.58  5063.7  473.06
  5202.3  474.19  5311.2  474.72  5339.4  475.55  5346.5  476.69  5367.7  474.83
  5403.1  475.32  5495.0  474.86  5537.4  475.20  5586.9  477.52  5615.2  477.92
  5855.6  479.08  5926.8  478.22  5943.2  477.32  5975.8  477.51  6007.5  476.69
#Mann=6,-1,0
  4009.4    0.05       0  5026.3    0.05       0  5030.3    0.05       0
  5202.3     0.1       0  5926.8   0.075       0  5943.2     0.1       0
Bank Sta=5026.3,5030.3
Exp/Cntr=0.3,0.1

Type RM Length L Ch R = 1,4022,474,474,474
BEGIN DESCRIPTION:
Mapping XS 0d7079b1
END DESCRIPTION:
XS GIS Cut Line= 3
      2655339.55      6953033.98      2654757.51      6952672.96
      2653870.36      6952323.26
#Sta/Elev= 30
  4319.4  475.81  4535.4  476.34  4673.4  474.87  4782.5  472.77  4868.3  469.79
  4899.0  469.51  4941.5  467.65  4978.1  467.38  5028.1  468.21  5038.2  467.95
  5050.4  466.11  5050.7  465.61  5054.4  466.11  5059.7  467.57  5082.2  467.14
  5104.7  468.12  5136.3  469.70  5167.2  475.16  5177.9  474.71  5185.1  475.52
  5209.5  475.62  5214.9  476.91  5263.6  477.66  5672.4  476.76  5683.1  477.60
  5726.1  476.69  5810.4  476.46  5815.8  477.38  5845.5  477.56  5957.9  476.46
#Mann=4,-1,0
  4319.4    0.05       0  5050.4    0.05       0  5054.4    0.05       0
  5104.7     0.1       0
Bank Sta=5050.4,5054.4
Exp/Cntr=0.3,0.1

Type RM Length L Ch R = 1,3548,491,491,491
BEGIN DESCRIPTION:
Mapping XS 40cea78e
END DESCRIPTION:
XS GIS Cut Line= 3
      2655424.22      6952580.86      2655022.73      6952304.60
      2654285.99      6951932.55
#Sta/Elev= 30
  4522.7  475.35  4672.3  474.64  4849.6  472.17  4902.3  469.95  4932.1  467.44
  4938.2  467.64  4993.0  464.63  4993.2  464.13  4997.0  464.63  5031.8  465.82
  5084.3  465.02  5120.9  464.84  5137.6  466.21  5174.4  466.32  5204.5  467.64
  5226.8  469.42  5264.1  470.68  5271.4  471.61  5338.3  473.90  5398.1  474.40
  5427.5  476.09  5433.1  475.36  5443.3  476.23  5506.2  476.25  5667.1  477.14
  5723.4  477.00  5739.6  475.94  5761.9  478.10  5805.3  477.07  5835.4  477.34
#Mann=8,-1,0
  4522.7    0.05       0  4849.6    0.12       0  4993.0    0.07       0
  4997.0    0.12       0  5084.3    0.05       0  5398.1     0.1       0
  5506.2   0.075       0  5805.3     0.1       0
Bank Sta=4993,4997
Exp/Cntr=0.3,0.1

Type RM Length L Ch R = 1,3057,445,445,445
BEGIN DESCRIPTION:
Mapping XS a5ae4869
END DESCRIPTION:
XS GIS Cut Line= 3
      2655682.09      6952337.75      2655321.10      6951991.50
      2654617.54      6951549.47
#Sta/Elev= 30
  4481.5  472.19  4532.9  472.75  4554.3  473.64  4625.0  473.38  4709.9  471.48
  4724.1  470.19  4794.8  468.22  4844.2  465.35  4936.4  463.04  4976.4  461.66
  4976.7  461.16  4980.2  461.16  4980.4  461.66  5008.1  463.20  5014.0  462.77
  5029.3  463.34  5035.3  462.18  5058.6  462.20  5138.9  465.55  5151.9  466.79
  5202.5  470.03  5275.5  472.96  5369.8  473.97  5485.2  474.26  5537.0  475.43
  5612.7  475.20  5660.9  474.44  5667.8  475.22  5757.1  475.54  5812.6  475.53
#Mann=7,-1,0
  4481.5    0.05       0  4936.4    0.12       0  4976.4    0.07       0
  4980.4    0.12       0  5151.9    0.05       0  5612.7   0.075       0
  5757.1     0.1       0
Bank Sta=4976.4,4980.4
Exp/Cntr=0.3,0.1

Type RM Length L Ch R = 1,2612,574,574,574
BEGIN DESCRIPTION:
Mapping XS 1c420656
END DESCRIPTION:
XS GIS Cut Line= 3
      2655925.24      6952076.25      2655623.16      6951711.54
      2654993.26      6951122.16
#Sta/Elev= 30
  4528.3  469.73  4566.9  470.87  4616.4  471.44  4708.9  469.88  4716.7  469.15
  4758.4  468.18  4801.4  465.58  4822.2  465.12  4879.5  462.12  4957.7  458.90
  4963.1  459.09  4984.3  457.99  4984.6  457.49  4988.1  457.49  4988.3  457.99
  4999.0  459.38  5007.4  459.81  5042.6  459.39  5078.2  459.94  5126.0  461.62
  5195.5  465.75  5205.2  467.28  5212.6  467.70  5273.1  469.37  5325.9  472.01
  5389.4  472.88  5580.4  473.69  5665.4  472.43  5700.6  474.11  5864.5  473.74
#Mann=7,-1,0
  4528.3    0.05       0  4963.1    0.12       0  4984.3    0.07       0
  4988.3    0.12       0  5126.0    0.05       0  5195.5    0.12       0
  5273.1    0.05       0
Bank Sta=4984.3,4988.3
Exp/Cntr=0.3,0.1

Type RM Length L Ch R = 1,2038,734,734,734
BEGIN DESCRIPTION:
Mapping XS 4f8ac5bd
END DESCRIPTION:
XS GIS Cut Line= 3
      2656168.33      6951884.65      2656035.72      6951361.60
      2655520.53      6950816.96
#Sta/Elev= 30
  4452.9  468.91  4477.3  468.51  4523.6  469.45  4673.3  465.84  4808.4  457.25
  4887.2  455.17  4920.9  454.79  4941.5  455.56  4951.8  455.02  4962.2  452.36
  4967.2  452.36  4967.4  451.86  4971.2  452.36  4974.3  455.10  4995.9  456.27
  4999.8  457.30  5013.9  458.80  5020.9  457.71  5035.0  458.21  5042.3  457.30
  5194.6  461.58  5318.2  464.89  5339.2  464.74  5403.1  466.90  5452.5  466.84
  5622.4  470.79  5685.9  470.24  5707.3  471.34  5714.2  472.40  5742.2  473.12
#Mann=5,-1,0
  4452.9    0.05       0  4808.4    0.12       0  4967.2    0.07       0
  4971.2    0.12       0  5194.6    0.05       0
Bank Sta=4967.2,4971.2
Exp/Cntr=0.3,0.1

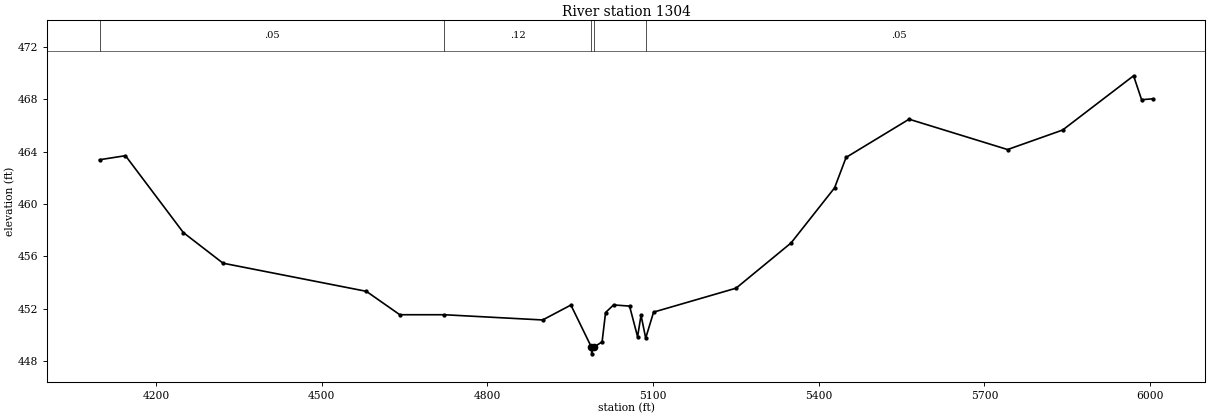
Type RM Length L Ch R = 1,1304,0,0,0
BEGIN DESCRIPTION:
Kings Creek Trib 12 3.0
END DESCRIPTION:
XS GIS Cut Line= 4
      2656429.86      6952068.86      2656687.72      6951575.25
      2656656.16      6951231.60      2656040.18      6950438.01
#Sta/Elev= 30
  4098.0  463.39  4145.0  463.70  4249.8  457.82  4321.6  455.48  4581.0  453.33
  4641.6  451.54  4722.1  451.54  4900.2  451.14  4951.3  452.28  4988.6  449.05
  4988.8  448.55  4992.6  449.05  5007.8  449.47  5014.1  451.71  5028.6  452.29
  5057.5  452.20  5072.0  449.86  5078.3  451.50  5086.7  449.75  5101.0  451.74
  5250.3  453.57  5349.9  457.03  5428.6  461.24  5449.5  463.57  5563.5  466.49
  5741.8  464.17  5841.4  465.66  5969.9  469.81  5984.4  467.98  6004.6  468.05
#Mann=5,-1,0
  4098.0    0.05       0  4722.1    0.12       0  4988.6    0.07       0
  4992.6    0.12       0  5086.7    0.05       0
Bank Sta=4988.6,4992.6
Exp/Cntr=0.3,0.1

Chan Stop Cuts=-1