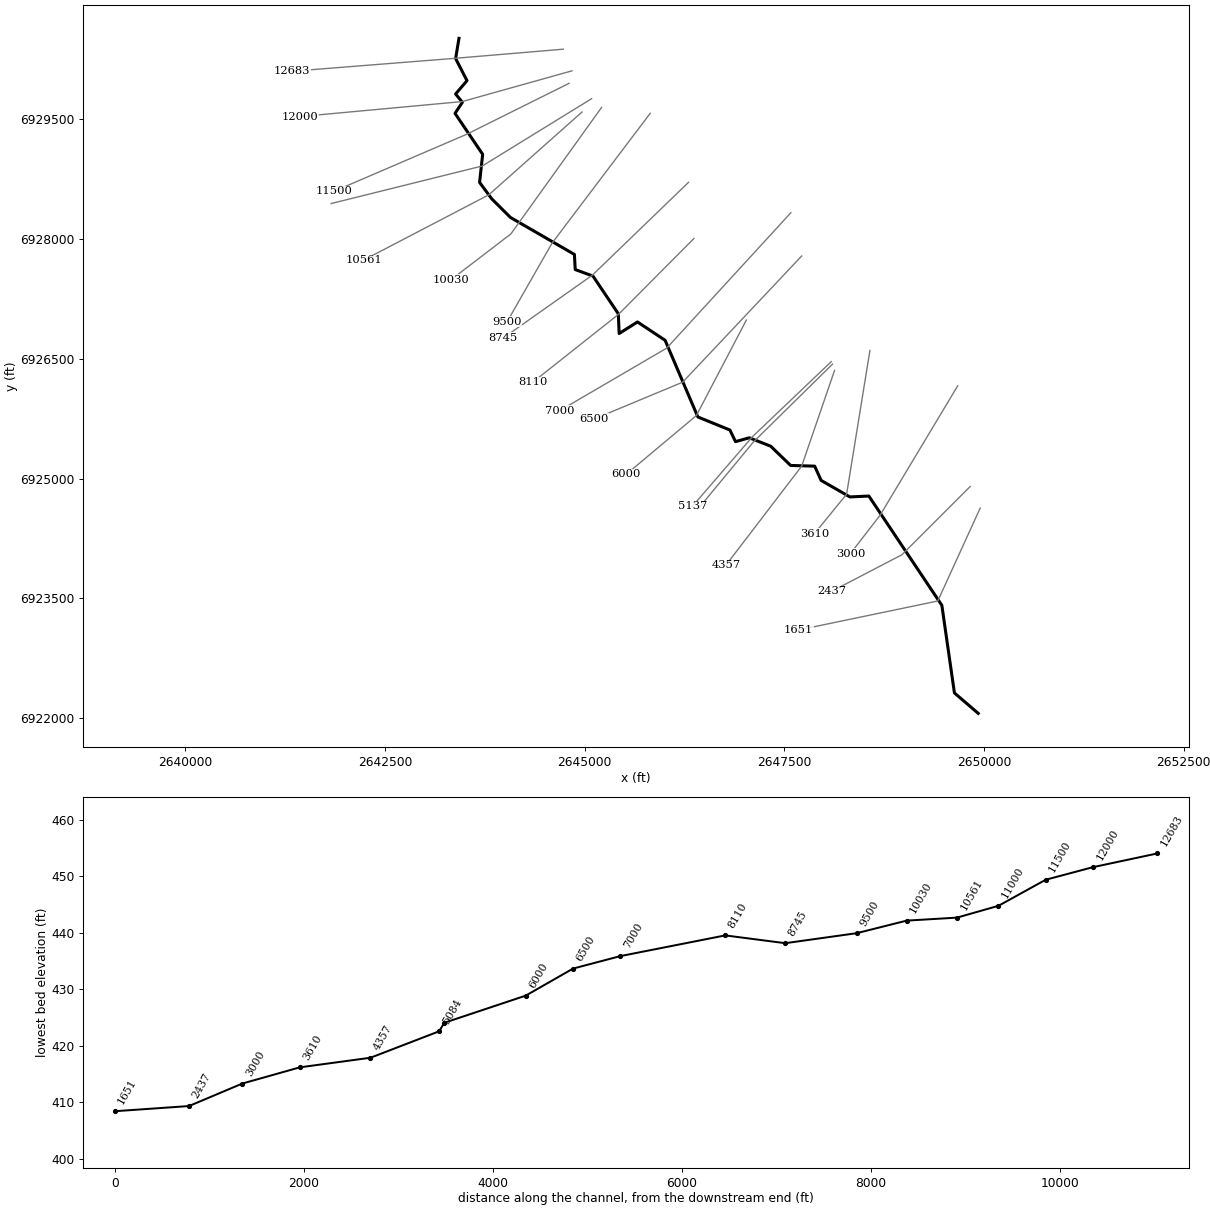
--- Kings Creek Trib 13.prj (project) ---

Proj Title=Kings Creek Trib 13 Base Level Engineering
Current Plan=p01
Default Exp/Contr=0.3,0.1
English Units
Geom File=g01
Flow File=f01
Plan File=p01
BEGIN DESCRIPTION:
Kings Creek Trib 13
END DESCRIPTION:

--- Kings Creek Trib 13.p01 (plan) ---

Plan Title=Multiple Run
Short Identifier=Multiple
Geom File=g01
Flow File=f01
Subcritical Flow
K Sum by GR= 0
Std Step Tol= 0.01
Critical Tol= 0.01
Num of Std Step Trials= 20
Max Error Tol= 0.3
Flow Tol Ratio= 0.001
Split Flow NTrial= 30
Split Flow Tol= 0.02
Split Flow Ratio= 0.02
Log Output Level= 0
Friction Slope Method= 1
Unsteady Friction Slope Method= 2
Unsteady Bridges Friction Slope Method= 1
Parabolic Critical Depth
Global Vel Dist=  1 , 1 , 1
Global Log Level= 0
CheckData=True
Encroach Param= -1, 0, 0, 0
BEGIN DESCRIPTION:
Multiple Run
END DESCRIPTION:

--- Kings Creek Trib 13.f01 (steady flow) ---

Flow Title=Multiple
Number of Profiles=7
Profile Names=10-year,25-year,50-year,1pct_min,100-year,1pct_plu,500-year
River Rch & RM= Kings Creek Trib,Reach-1,12683
     510     674     803     475     947    1890    1317
River Rch & RM= Kings Creek Trib,Reach-1,11500
     586     782     939     559    1115    2224    1572
River Rch & RM= Kings Creek Trib,Reach-1,10030
     956    1308    1598     966    1927    3845    2804
Boundary for River Rch & Prof#=Kings Creek Trib,Reach-1,1
Up Type=0
Dn Type=3
Dn Slope=0.005
Boundary for River Rch & Prof#=Kings Creek Trib,Reach-1,2
Up Type=0
Dn Type=3
Dn Slope=0.005
Boundary for River Rch & Prof#=Kings Creek Trib,Reach-1,3
Up Type=0
Dn Type=3
Dn Slope=0.005
Boundary for River Rch & Prof#=Kings Creek Trib,Reach-1,4
Up Type=0
Dn Type=3
Dn Slope=0.005
Boundary for River Rch & Prof#=Kings Creek Trib,Reach-1,5
Up Type=0
Dn Type=3
Dn Slope=0.005
Boundary for River Rch & Prof#=Kings Creek Trib,Reach-1,6
Up Type=0
Dn Type=3
Dn Slope=0.005
Boundary for River Rch & Prof#=Kings Creek Trib,Reach-1,7
Up Type=0
Dn Type=3
Dn Slope=0.005

--- Kings Creek Trib 13.g01 (geometry) ---

Geom Title=Existing Conditions

River Reach=Kings Creek Trib,Reach-1
Reach XY= 30
      2643426.00      6930511.00      2643384.10      6930257.71
      2643526.47      6929981.16      2643383.61      6929814.33
      2643468.89      6929711.00      2643376.56      6929571.64
      2643722.63      6929059.26      2643683.82      6928707.59
      2643836.78      6928501.32      2644069.94      6928269.14
      2644870.97      6927805.92      2644881.17      6927616.41
      2645103.32      6927534.99      2645420.54      6927063.45
      2645431.10      6926815.89      2645660.60      6926960.68
      2646006.37      6926731.15      2646416.19      6925771.51
      2646817.68      6925607.84      2646887.86      6925462.50
      2647060.61      6925510.91      2647328.31      6925405.17
      2647577.47      6925164.55      2647878.74      6925155.66
      2647958.87      6924977.45      2648319.38      6924770.41
      2648556.58      6924781.65      2649470.53      6923413.45
      2649627.96      6922316.88      2649926.00      6922061.00

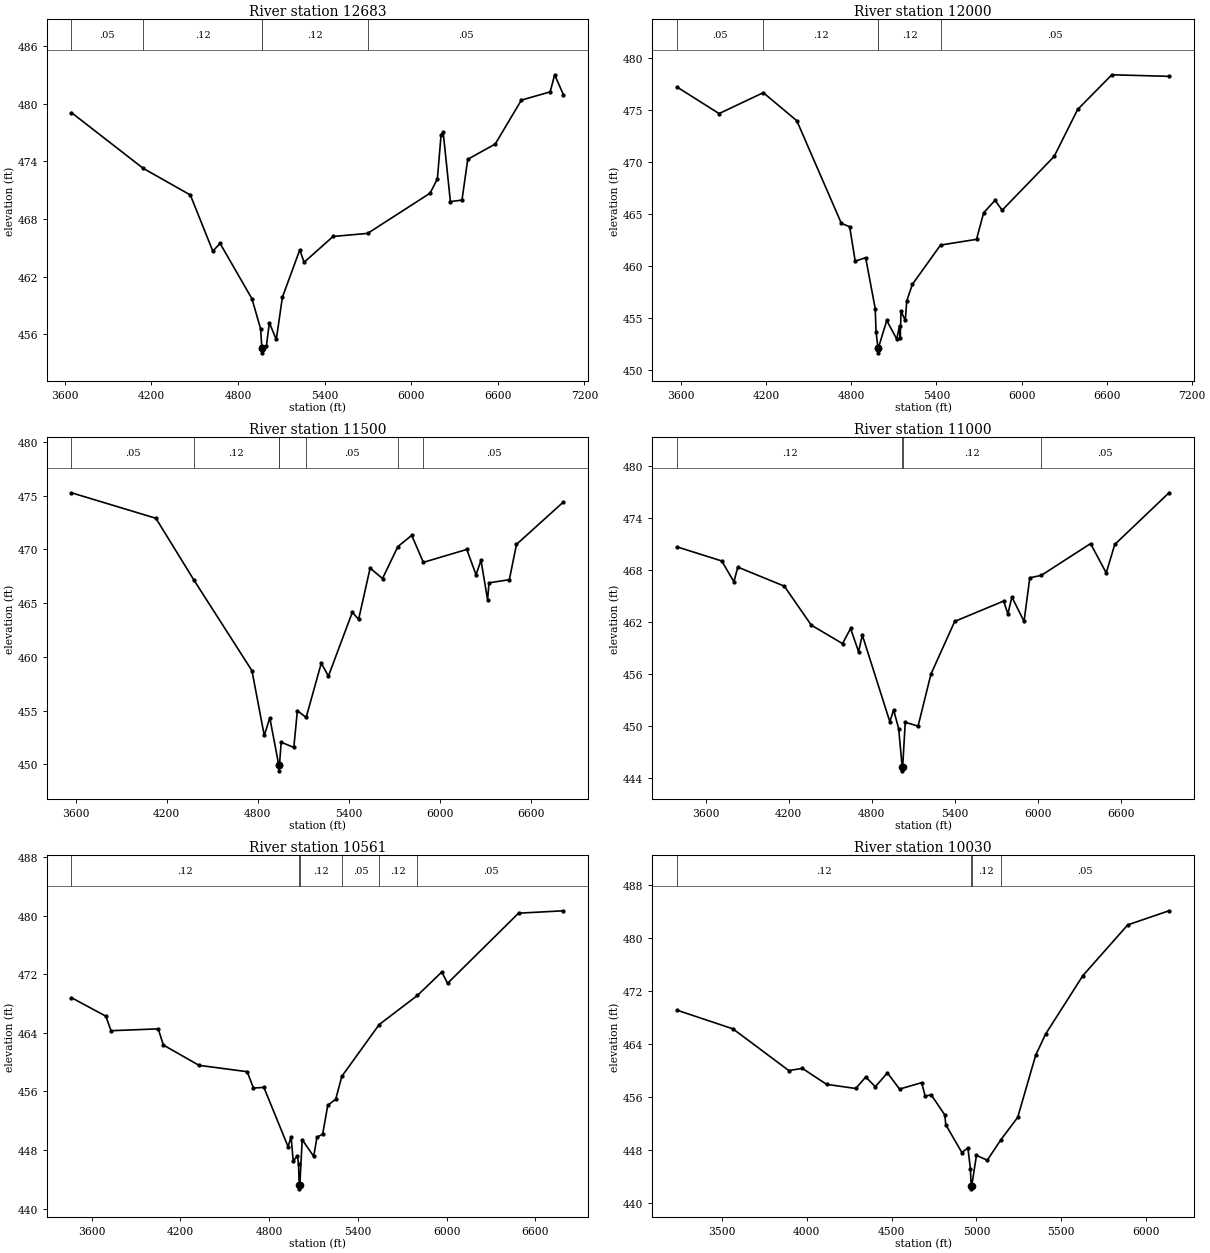
Type RM Length L Ch R = 1,12683,683,683,683
BEGIN DESCRIPTION:
Mapping XS fd84527d
END DESCRIPTION:
XS GIS Cut Line= 3
      2644731.79      6930375.14      2643372.37      6930260.55
      2641335.90      6930099.09
#Sta/Elev= 30
  3647.1  479.09  4143.7  473.29  4470.5  470.51  4626.3  464.66  4676.5  465.47
  4897.3  459.70  4957.5  456.55  4965.6  454.57  4965.8  454.07  4969.6  454.57
  4997.7  454.82  5017.7  457.20  5065.9  455.46  5108.0  459.85  5228.4  464.79
  5258.5  463.50  5459.1  466.19  5698.5  466.51  6131.2  470.70  6181.4  472.18
  6207.0  476.73  6221.5  477.08  6271.7  469.82  6351.9  469.98  6392.0  474.23
  6582.4  475.82  6763.2  480.39  6962.8  481.25  6993.9  483.03  7054.2  480.96
#Mann=5,-1,0
  3647.1    0.05       0  4143.7    0.12       0  4965.6    0.07       0
  4969.6    0.12       0  5698.5    0.05       0
Bank Sta=4965.6,4969.6
Exp/Cntr=0.3,0.1

Type RM Length L Ch R = 1,12000,500,500,500
BEGIN DESCRIPTION:
Kings Creek Trib 13 24.0
END DESCRIPTION:
XS GIS Cut Line= 3
      2644841.11      6930104.30      2643465.97      6929719.38
      2641434.85      6929531.38
#Sta/Elev= 30
  3572.0  477.18  3868.1  474.63  4179.9  476.64  4416.1  473.94  4730.0  464.08
  4788.5  463.75  4827.8  460.44  4901.3  460.78  4968.8  455.88  4974.7  453.66
  4987.6  452.13  4987.8  451.63  4991.6  452.13  5050.2  454.74  5120.5  452.95
  5140.4  454.25  5145.4  453.10  5150.6  455.64  5180.7  454.74  5190.8  456.61
  5231.0  458.22  5429.2  461.99  5682.8  462.54  5733.1  465.09  5813.4  466.29
  5863.6  465.34  6230.2  470.51  6395.9  475.03  6636.9  478.36  7039.8  478.21
#Mann=5,-1,0
  3572.0    0.05       0  4179.9    0.12       0  4987.6    0.07       0
  4991.6    0.12       0  5429.2    0.05       0
Bank Sta=4987.6,4991.6
Exp/Cntr=0.3,0.1

Type RM Length L Ch R = 1,11500,500,500,500
BEGIN DESCRIPTION:
Kings Creek Trib 13 23.0
END DESCRIPTION:
XS GIS Cut Line= 3
      2644804.63      6929948.03      2643525.36      6929311.24
      2641856.73      6928593.88
#Sta/Elev= 30
  3571.0  475.26  4128.0  472.89  4376.9  467.19  4762.0  458.71  4842.9  452.69
  4879.6  454.33  4939.1  449.90  4939.4  449.40  4943.1  449.90  4954.6  452.06
  5038.0  451.58  5061.5  454.99  5119.4  454.37  5219.1  459.41  5266.2  458.21
  5423.8  464.14  5465.5  463.49  5541.5  468.26  5623.1  467.28  5724.1  470.25
  5815.7  471.30  5892.8  468.79  6179.1  469.99  6240.2  467.64  6272.8  468.98
  6316.4  465.31  6325.8  466.88  6459.9  467.18  6507.0  470.46  6816.3  474.40
#Mann=7,-1,0
  3571.0    0.05       0  4376.9    0.12       0  4939.1    0.07       0
  4943.1    0.12       0  5119.4    0.05       0  5724.1    0.12       0
  5892.8    0.05       0
Bank Sta=4939.1,4943.1
Exp/Cntr=0.3,0.1

Type RM Length L Ch R = 1,11000,439,439,439
BEGIN DESCRIPTION:
Kings Creek Trib 13 22.0
END DESCRIPTION:
XS GIS Cut Line= 3
      2645085.92      6929755.34      2643717.64      6928913.15
      2641825.51      6928442.84
#Sta/Elev= 30
  3393.3  470.69  3716.2  469.06  3804.2  466.65  3832.2  468.35  4168.2  466.15
  4363.5  461.64  4589.5  459.50  4647.5  461.25  4705.4  458.57  4732.6  460.48
  4931.5  450.46  4958.6  451.83  4995.3  449.67  5020.3  445.28  5020.5  444.78
  5024.3  445.28  5042.9  450.40  5135.6  449.95  5228.4  455.96  5400.6  462.07
  5753.9  464.42  5784.8  462.94  5813.9  464.89  5901.8  462.07  5943.1  467.11
  6027.1  467.40  6382.5  471.07  6495.8  467.68  6557.6  470.97  6949.7  476.95
#Mann=4,-1,0
  3393.3    0.12       0  5020.3    0.07       0  5024.3    0.12       0
  6027.1    0.05       0
Bank Sta=5020.3,5024.3
Exp/Cntr=0.3,0.1

Type RM Length L Ch R = 1,10561,531,531,531
BEGIN DESCRIPTION:
Mapping XS a9c92e31
END DESCRIPTION:
XS GIS Cut Line= 3
      2644966.16      6929588.70      2643799.46      6928552.22
      2642233.22      6927735.27
#Sta/Elev= 30
  3463.1  468.80  3695.2  466.28  3730.8  464.29  4049.8  464.54  4084.9  462.33
  4325.7  459.56  4651.9  458.69  4693.9  456.46  4764.8  456.54  4927.8  448.47
  4948.7  449.76  4963.0  446.51  4991.4  447.17  4998.9  446.12  5003.6  443.19
  5003.9  442.69  5007.6  443.19  5023.7  449.40  5101.5  447.13  5123.6  449.73
  5162.1  450.17  5196.8  454.10  5250.5  454.93  5291.6  458.05  5544.1  465.12
  5803.3  469.11  5968.2  472.31  6006.7  470.76  6487.0  480.34  6790.2  480.67
#Mann=6,-1,0
  3463.1    0.12       0  5003.6    0.07       0  5007.6    0.12       0
  5291.6    0.05       0  5544.1    0.12       0  5803.3    0.05       0
Bank Sta=5003.6,5007.6
Exp/Cntr=0.3,0.1

Type RM Length L Ch R = 1,10030,530,530,530
BEGIN DESCRIPTION:
Kings Creek Trib 13 20.0
END DESCRIPTION:
XS GIS Cut Line= 3
      2645210.92      6929645.97      2644075.50      6928062.63
      2643321.61      6927485.52
#Sta/Elev= 30
  3236.7  469.15  3565.8  466.33  3895.0  460.03  3974.7  460.36  4117.2  457.95
  4289.1  457.32  4348.1  459.06  4404.6  457.59  4475.8  459.68  4547.2  457.23
  4677.2  458.20  4698.1  456.17  4733.7  456.36  4813.5  453.34  4819.7  451.84
  4914.2  447.65  4949.8  448.34  4964.6  445.20  4968.7  442.66  4969.0  442.16
  4972.7  442.66  5000.2  447.22  5064.0  446.48  5143.3  449.55  5243.2  452.96
  5349.2  462.35  5407.3  465.53  5627.6  474.39  5891.5  482.04  6134.5  484.17
#Mann=4,-1,0
  3236.7    0.12       0  4968.7    0.07       0  4972.7    0.12       0
  5143.3    0.05       0
Bank Sta=4968.7,4972.7
Exp/Cntr=0.3,0.1

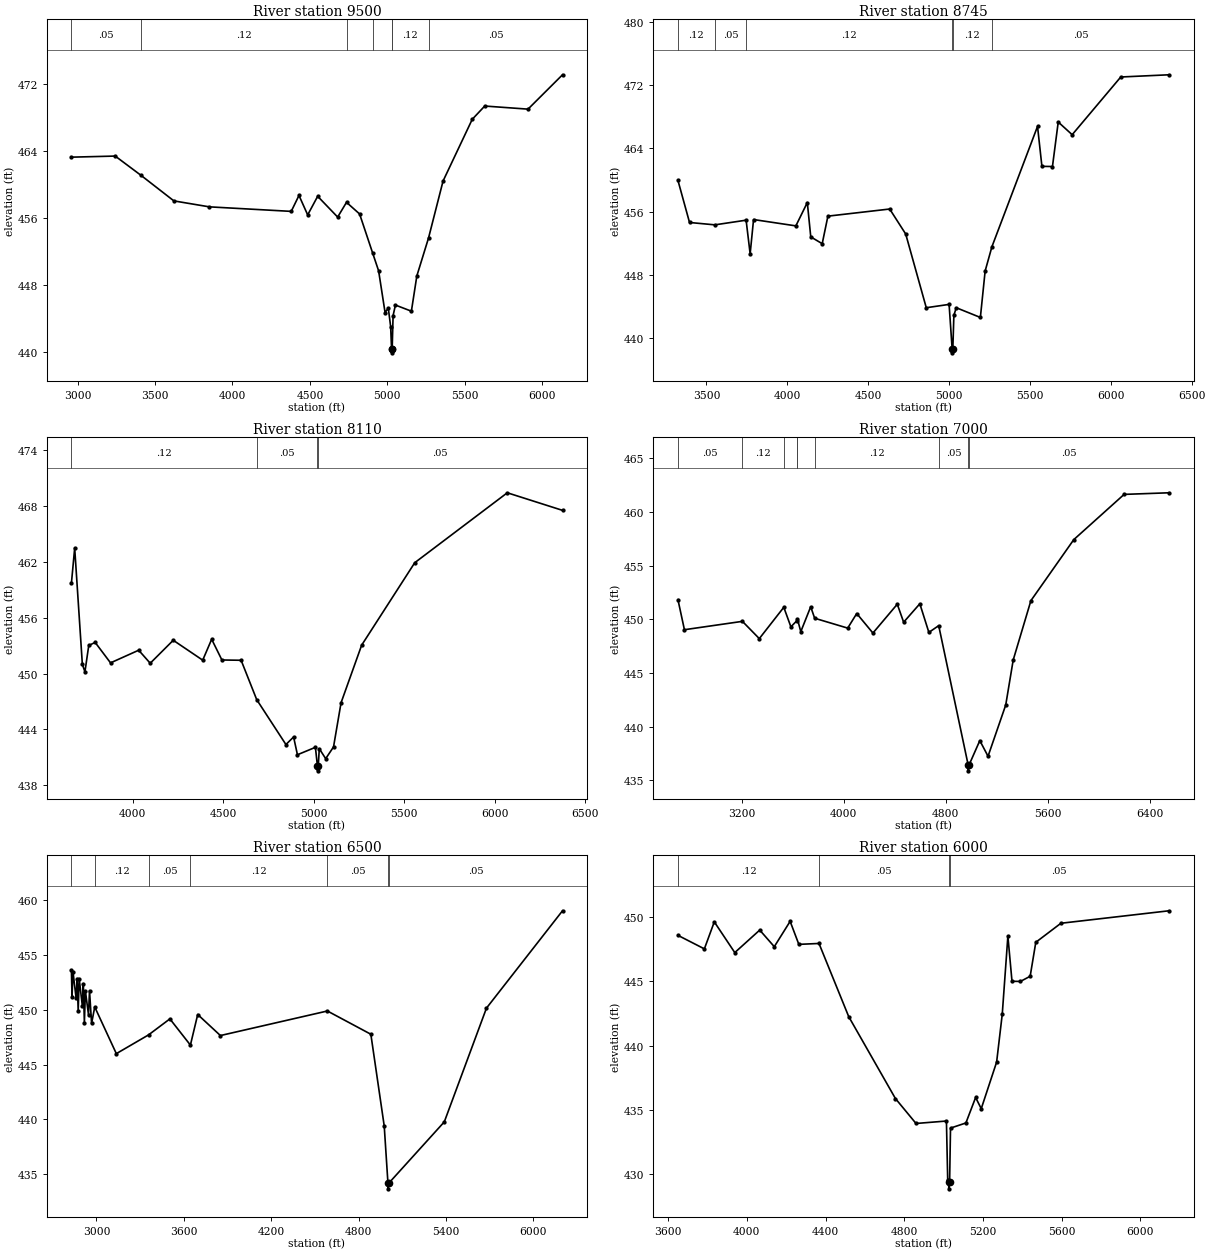
Type RM Length L Ch R = 1,9500,755,755,755
BEGIN DESCRIPTION:
Kings Creek Trib 13 19.0
END DESCRIPTION:
XS GIS Cut Line= 3
      2645820.31      6929573.08      2644590.50      6927946.20
      2644029.29      6926964.84
#Sta/Elev= 30
  2960.6  463.28  3243.3  463.41  3409.8  461.11  3622.1  458.06  3851.0  457.35
  4379.5  456.81  4429.5  458.71  4485.7  456.39  4550.2  458.61  4679.2  456.13
  4736.3  457.89  4820.8  456.50  4905.0  451.84  4943.5  449.72  4985.2  444.74
  5006.0  445.27  5021.2  443.07  5027.0  440.43  5027.3  439.93  5031.1  440.43
  5037.0  444.38  5052.1  445.63  5155.1  444.90  5190.3  449.11  5266.0  453.65
  5359.5  460.43  5548.0  467.80  5628.6  469.38  5907.9  469.01  6130.5  473.11
#Mann=7,-1,0
  2960.6    0.05       0  3409.8    0.12       0  4736.3    0.05       0
  4905.0    0.12       0  5027.0    0.07       0  5031.1    0.12       0
  5266.0    0.05       0
Bank Sta=5027,5031.1
Exp/Cntr=0.3,0.1

Type RM Length L Ch R = 1,8745,635,635,635
BEGIN DESCRIPTION:
Mapping XS 4b5a90b2
END DESCRIPTION:
XS GIS Cut Line= 3
      2646299.48      6928708.49      2645096.33      6927547.01
      2643981.77      6926760.57
#Sta/Elev= 30
  3323.8  459.94  3395.3  454.63  3551.9  454.33  3745.2  454.92  3770.1  450.67
  3791.2  455.00  4052.8  454.20  4123.6  457.15  4144.9  452.81  4215.7  451.95
  4250.9  455.43  4632.9  456.33  4732.0  453.17  4859.1  443.86  5000.2  444.28
  5019.1  438.66  5019.4  438.16  5023.3  438.66  5029.8  442.90  5044.6  443.86
  5193.6  442.63  5223.1  448.50  5264.9  451.56  5547.0  466.77  5574.1  461.72
  5639.3  461.70  5675.0  467.32  5761.2  465.72  6061.7  473.01  6360.2  473.29
#Mann=6,-1,0
  3323.8    0.12       0  3551.9    0.05       0  3745.2    0.12       0
  5019.1    0.07       0  5023.3    0.12       0  5264.9    0.05       0
Bank Sta=5019.1,5023.3
Exp/Cntr=0.3,0.1

Type RM Length L Ch R = 1,8110,1110,1110,1110
BEGIN DESCRIPTION:
Mapping XS d0c36c87
END DESCRIPTION:
XS GIS Cut Line= 3
      2646367.19      6928005.36      2645424.46      6927057.42
      2644346.33      6926203.25
#Sta/Elev= 30
  3661.8  459.70  3679.9  463.50  3722.3  450.98  3736.5  450.19  3757.6  453.02
  3793.0  453.35  3877.9  451.15  4033.4  452.51  4097.1  451.11  4224.3  453.58
  4387.0  451.44  4436.5  453.69  4493.0  451.46  4599.1  451.43  4685.4  447.19
  4846.6  442.37  4889.0  443.18  4910.2  441.27  5009.5  442.07  5020.7  440.04
  5021.1  439.54  5025.1  440.04  5030.9  441.92  5066.2  440.85  5109.5  442.11
  5151.1  446.86  5264.8  453.05  5558.1  461.92  6069.3  469.44  6374.2  467.55
#Mann=4,-1,0
  3661.8    0.12       0  4685.4    0.05       0  5020.7    0.03       0
  5025.1    0.05       0
Bank Sta=5020.7,5025.1
Exp/Cntr=0.3,0.1

Type RM Length L Ch R = 1,7000,500,500,500
BEGIN DESCRIPTION:
Kings Creek Trib 13 14.0
END DESCRIPTION:
XS GIS Cut Line= 3
      2647580.72      6928328.28      2646026.05      6926632.88
      2644684.88      6925849.10
#Sta/Elev= 30
  2699.7  451.83  2750.4  449.03  3205.5  449.81  3338.0  448.20  3530.2  451.12
  3585.9  449.30  3632.1  449.86  3636.7  450.05  3663.6  448.85  3741.3  451.17
  3772.5  450.10  4031.7  449.18  4102.6  450.54  4229.6  448.72  4420.8  451.41
  4470.7  449.73  4597.7  451.45  4668.7  448.78  4745.9  449.41  4977.8  436.37
  4978.2  435.87  4982.3  436.37  5068.4  438.69  5132.9  437.23  5271.8  442.01
  5330.5  446.21  5469.3  451.74  5805.7  457.43  6200.8  461.65  6553.4  461.80
#Mann=9,-1,0
  2699.7    0.05       0  3205.5    0.12       0  3530.2    0.05       0
  3632.1    0.12       0  3636.7    0.05       0  3772.5    0.12       0
  4745.9    0.05       0  4977.8    0.04       0  4982.3    0.05       0
Bank Sta=4977.8,4982.3
Exp/Cntr=0.3,0.1

Type RM Length L Ch R = 1,6500,500,500,500
BEGIN DESCRIPTION:
Kings Creek Trib 13 13.0
END DESCRIPTION:
XS GIS Cut Line= 3
      2647716.13      6927786.60      2646225.95      6926206.84
      2645118.42      6925745.45
#Sta/Elev= 30
  2828.3  453.59  2832.5  451.15  2839.3  453.44  2860.8  451.02  2867.6  452.84
  2874.9  449.91  2881.8  452.81  2903.3  450.36  2910.1  452.38  2917.4  448.81
  2924.3  451.71  2945.7  449.53  2952.6  451.74  2966.8  448.74  2988.4  450.25
  3136.7  445.99  3357.8  447.70  3504.4  449.16  3645.2  446.77  3695.4  449.56
  3851.2  447.64  4585.6  449.88  4884.0  447.76  4975.9  439.39  5001.5  434.16
  5002.0  433.66  5006.1  434.16  5388.4  439.77  5677.7  450.14  6199.8  459.02
#Mann=7,-1,0
  2828.3    0.05       0  2988.4    0.12       0  3357.8    0.05       0
  3645.2    0.12       0  4585.6    0.05       0  5001.5    0.04       0
  5006.1    0.05       0
Bank Sta=5001.5,5006.1
Exp/Cntr=0.3,0.1

Type RM Length L Ch R = 1,6000,863,863,863
BEGIN DESCRIPTION:
Kings Creek Trib 13 12.0
END DESCRIPTION:
XS GIS Cut Line= 3
      2647023.43      6926984.55      2646397.43      6925788.80
      2645519.58      6925053.37
#Sta/Elev= 30
  3650.3  448.57  3784.5  447.52  3834.9  449.62  3939.0  447.23  4065.7  448.98
  4139.7  447.69  4220.2  449.66  4264.4  447.87  4366.8  447.94  4517.9  442.25
  4755.0  435.89  4859.7  433.95  5014.2  434.14  5020.7  429.54  5025.7  429.37
  5026.2  428.87  5030.3  429.37  5035.0  433.59  5113.1  433.99  5162.5  435.97
  5191.1  435.10  5269.2  438.72  5297.8  442.44  5326.4  448.51  5347.3  445.00
  5390.2  444.99  5439.6  445.39  5468.2  448.03  5595.8  449.51  6145.2  450.48
#Mann=4,-1,0
  3650.3    0.12       0  4366.8    0.05       0  5025.7    0.04       0
  5030.3    0.05       0
Bank Sta=5025.7,5030.3
Exp/Cntr=0.3,0.1

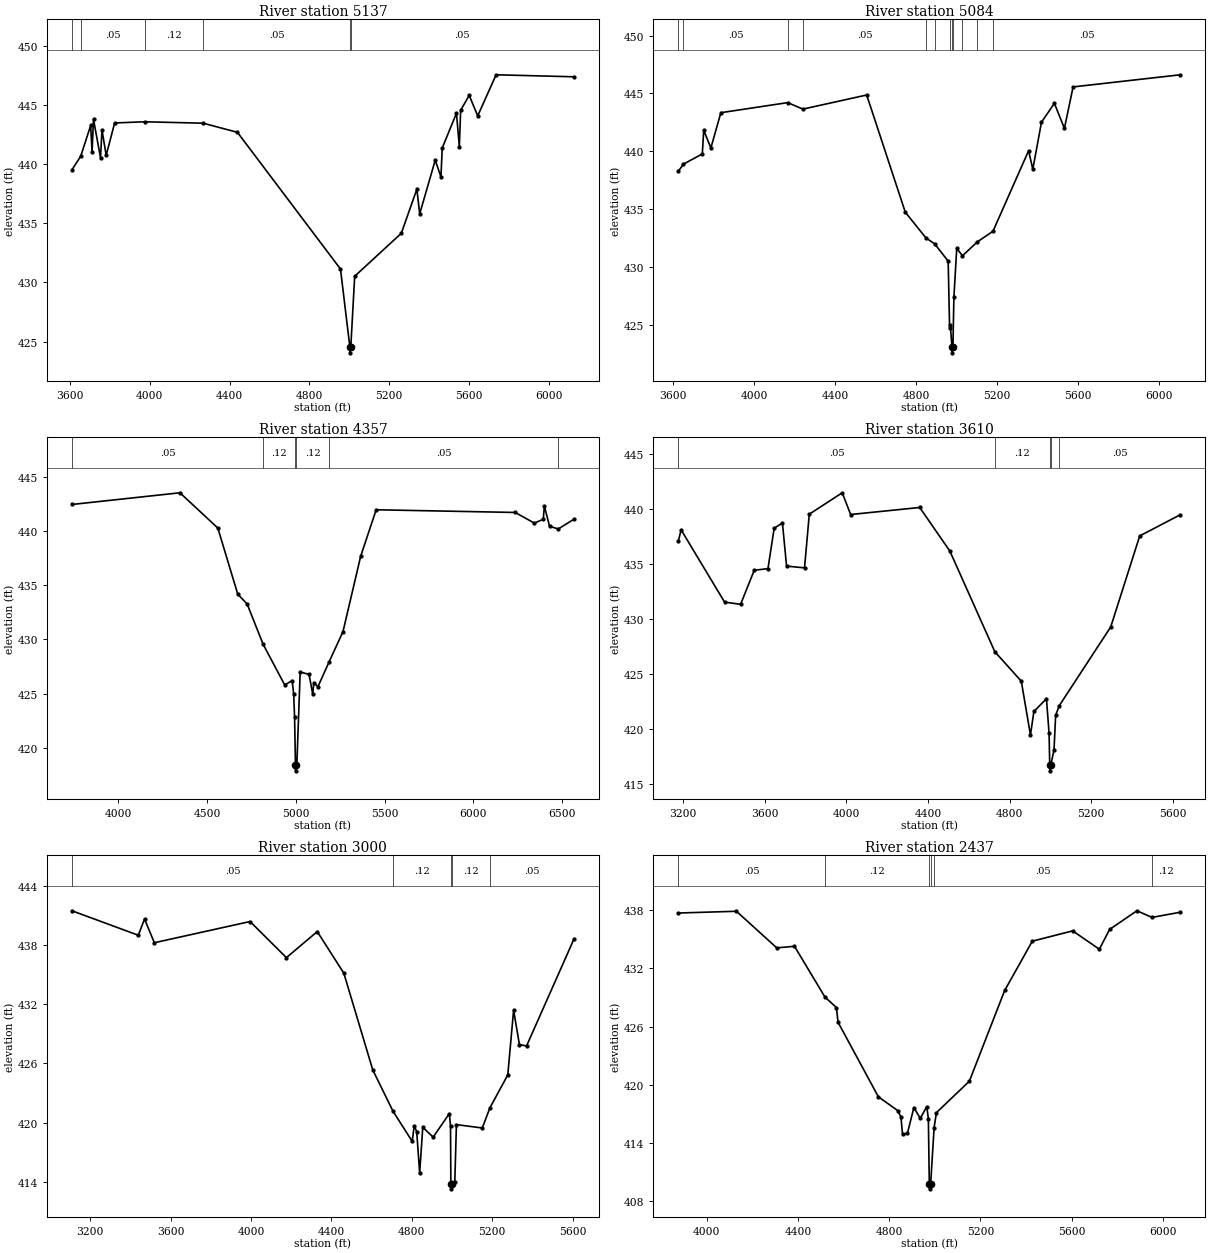
Type RM Length L Ch R = 1,5137,53,53,53
BEGIN DESCRIPTION:
Mapping XS 34b3ca2f
END DESCRIPTION:
XS GIS Cut Line= 3
      2648085.90      6926463.66      2647101.54      6925526.17
      2646346.33      6924651.17
#Sta/Elev= 30
  3610.4  439.51  3654.2  440.66  3704.3  443.26  3711.2  441.02  3718.4  443.78
  3753.6  440.52  3760.9  442.87  3782.0  440.74  3824.4  443.47  3975.3  443.57
  4267.3  443.45  4439.6  442.68  4956.1  431.13  5003.1  424.55  5003.6  424.05
  5007.8  424.55  5027.3  430.52  5261.0  434.15  5338.9  437.88  5353.1  435.79
  5431.0  440.33  5459.5  438.91  5466.1  441.36  5537.4  444.29  5551.7  441.46
  5558.3  444.54  5601.1  445.80  5643.8  444.07  5736.0  447.54  6125.6  447.37
#Mann=6,-1,0
  3610.4    0.12       0  3654.2    0.05       0  3975.3    0.12       0
  4267.3    0.05       0  5003.1    0.04       0  5007.8    0.05       0
Bank Sta=5003.1,5007.8
Exp/Cntr=0.3,0.1

Type RM Length L Ch R = 1,5084,727,727,727
BEGIN DESCRIPTION:
Mapping XS 7b9e8665
END DESCRIPTION:
XS GIS Cut Line= 3
      2648101.57      6926432.46      2647111.96      6925458.47
      2646414.56      6924615.34
#Sta/Elev= 30
  3625.2  438.27  3650.2  438.88  3743.4  439.76  3750.4  441.81  3785.8  440.28
  3835.2  443.33  4165.4  444.20  4241.2  443.64  4556.5  444.86  4747.4  434.72
  4849.8  432.49  4892.9  431.98  4959.6  430.48  4966.6  424.74  4970.1  424.95
  4978.4  423.05  4978.9  422.55  4983.1  423.05  4987.9  427.38  5002.0  431.59
  5030.3  430.95  5103.8  432.15  5181.2  433.07  5357.4  440.04  5378.2  438.44
  5421.2  442.51  5485.0  444.14  5534.5  441.97  5577.5  445.56  6107.9  446.61
#Mann=12,-1,0
  3625.2    0.12       0  3650.2    0.05       0  4165.4    0.12       0
  4241.2    0.05       0  4849.8    0.12       0  4892.9    0.05       0
  4970.1    0.12       0  4978.4    0.07       0  4983.1    0.12       0
  5030.3    0.05       0  5103.8    0.12       0  5181.2    0.05       0
Bank Sta=4978.4,4983.1
Exp/Cntr=0.3,0.1

Type RM Length L Ch R = 1,4357,747,747,747
BEGIN DESCRIPTION:
Mapping XS 1ba5c924
END DESCRIPTION:
XS GIS Cut Line= 3
      2648127.57      6926354.26      2647716.12      6925156.38
      2646768.18      6923916.77
#Sta/Elev= 30
  3738.3  442.48  4346.6  443.56  4560.0  440.30  4672.2  434.19  4725.1  433.28
  4814.8  429.57  4936.6  425.80  4978.8  426.20  4987.0  424.98  4992.3  422.84
  4997.4  418.36  4997.9  417.86  5002.2  418.36  5004.9  418.36  5023.9  426.99
  5073.7  426.78  5094.5  424.95  5100.8  426.02  5123.6  425.63  5187.1  427.94
  5265.0  430.73  5364.7  437.70  5451.9  441.99  6235.3  441.74  6343.3  440.75
  6393.1  441.12  6399.4  442.33  6428.5  440.46  6478.1  440.22  6565.4  441.11
#Mann=6,-1,0
  3738.3    0.05       0  4814.8    0.12       0  4997.4    0.07       0
  5002.2    0.12       0  5187.1    0.05       0  6478.1    0.12       0
Bank Sta=4997.4,5002.2
Exp/Cntr=0.3,0.1

Type RM Length L Ch R = 1,3610,610,610,610
BEGIN DESCRIPTION:
Kings Creek Trib 13 7.0
END DESCRIPTION:
XS GIS Cut Line= 3
      2648570.28      6926604.25      2648278.28      6924804.59
      2647875.97      6924310.97
#Sta/Elev= 30
  3176.8  437.13  3190.2  438.11  3403.0  431.53  3481.7  431.33  3548.4  434.43
  3615.7  434.58  3646.1  438.26  3686.6  438.74  3706.9  434.81  3794.9  434.65
  3818.3  439.54  3979.7  441.49  4020.9  439.51  4359.5  440.15  4507.2  436.18
  4727.7  427.01  4857.4  424.33  4902.3  419.42  4919.1  421.57  4980.7  422.73
  4993.5  419.58  4996.8  416.66  4997.4  416.16  5001.7  416.66  5017.8  418.08
  5025.7  421.22  5044.0  422.11  5295.7  429.27  5437.8  437.56  5636.8  439.49
#Mann=5,-1,0
  3176.8    0.05       0  4727.7    0.12       0  4996.8    0.07       0
  5001.7    0.12       0  5044.0    0.05       0
Bank Sta=4996.8,5001.7
Exp/Cntr=0.3,0.1

Type RM Length L Ch R = 1,3000,563,563,563
BEGIN DESCRIPTION:
Kings Creek Trib 13 6.0
END DESCRIPTION:
XS GIS Cut Line= 3
      2649669.24      6926161.58      2648696.79      6924540.72
      2648326.01      6924061.01
#Sta/Elev= 30
  3109.8  441.47  3439.8  438.99  3470.9  440.64  3519.5  438.23  3995.7  440.38
  4176.5  436.72  4330.0  439.36  4462.2  435.14  4606.0  425.34  4706.7  421.15
  4802.4  418.09  4812.1  419.69  4824.7  419.07  4839.3  414.88  4854.8  419.52
  4906.4  418.52  4987.0  420.91  4992.8  419.67  4994.5  413.78  4995.1  413.28
  4999.4  413.78  5014.0  413.94  5022.2  419.79  5150.8  419.45  5188.9  421.50
  5277.7  424.83  5306.6  431.39  5335.5  427.91  5370.9  427.76  5606.3  438.58
#Mann=5,-1,0
  3109.8    0.05       0  4706.7    0.12       0  4994.5    0.07       0
  4999.4    0.12       0  5188.9    0.05       0
Bank Sta=4994.5,4999.4
Exp/Cntr=0.3,0.1

Type RM Length L Ch R = 1,2437,786,786,786
BEGIN DESCRIPTION:
Kings Creek Trib 13 5.0
END DESCRIPTION:
XS GIS Cut Line= 3
      2649825.51      6924901.19      2648971.33      6924047.01
      2648091.11      6923588.67
#Sta/Elev= 30
  3875.9  437.71  4130.2  437.89  4307.0  434.12  4384.8  434.28  4518.4  429.05
  4568.7  427.97  4575.7  426.46  4752.5  418.78  4837.4  417.36  4851.5  416.70
  4858.6  414.91  4879.8  415.01  4908.1  417.67  4936.3  416.56  4964.6  417.77
  4971.7  416.53  4975.8  409.80  4976.8  409.30  4981.7  409.80  4996.9  415.61
  5007.1  417.15  5151.5  420.39  5306.2  429.73  5427.5  434.81  5604.3  435.87
  5721.3  433.98  5766.4  436.02  5886.0  437.94  5952.3  437.26  6076.3  437.79
#Mann=6,-1,0
  3875.9    0.05       0  4518.4    0.12       0  4975.8    0.03       0
  4981.7    0.12       0  4996.9    0.05       0  5952.3    0.12       0
Bank Sta=4975.8,4981.7
Exp/Cntr=0.3,0.1

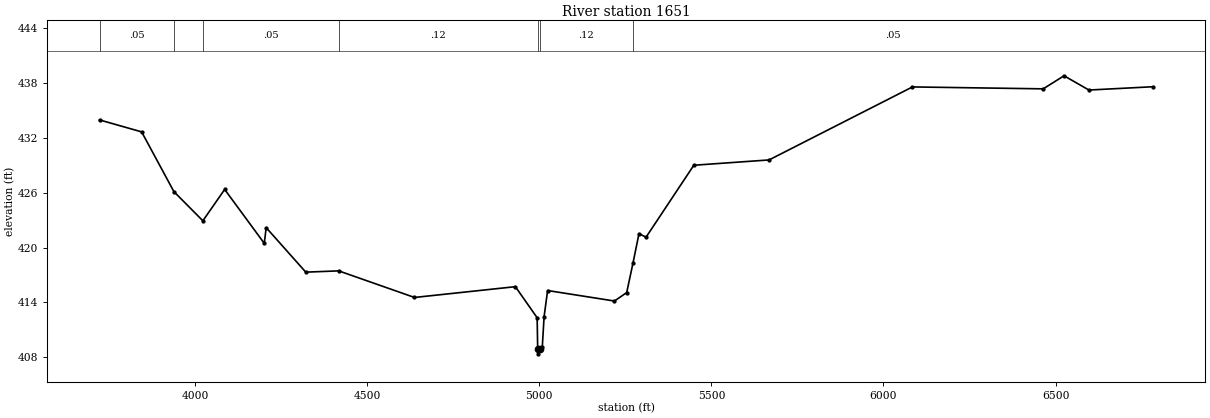
Type RM Length L Ch R = 1,1651,0,0,0
BEGIN DESCRIPTION:
Kings Creek Trib 13 4.0
END DESCRIPTION:
XS GIS Cut Line= 3
      2649950.48      6924630.31      2649419.49      6923467.73
      2647674.43      6923104.29
#Sta/Elev= 30
  3721.9  433.98  3844.3  432.67  3938.1  426.13  4022.2  422.94  4085.6  426.37
  4200.7  420.47  4206.2  422.19  4321.3  417.32  4416.9  417.46  4637.2  414.55
  4930.4  415.73  4993.6  412.33  4995.2  408.88  4996.2  408.38  5001.2  408.88
  5008.6  409.14  5013.8  412.45  5024.0  415.31  5218.1  414.16  5253.8  415.08
  5272.1  418.31  5289.6  421.54  5310.0  421.14  5448.9  429.02  5667.5  429.60
  6084.3  437.59  6464.2  437.38  6524.7  438.81  6597.0  437.25  6782.5  437.61
#Mann=7,-1,0
  3721.9    0.05       0  3938.1    0.12       0  4022.2    0.05       0
  4416.9    0.12       0  4995.2    0.07       0  5001.2    0.12       0
  5272.1    0.05       0
Bank Sta=4995.2,5001.2
Exp/Cntr=0.3,0.1

Chan Stop Cuts=-1