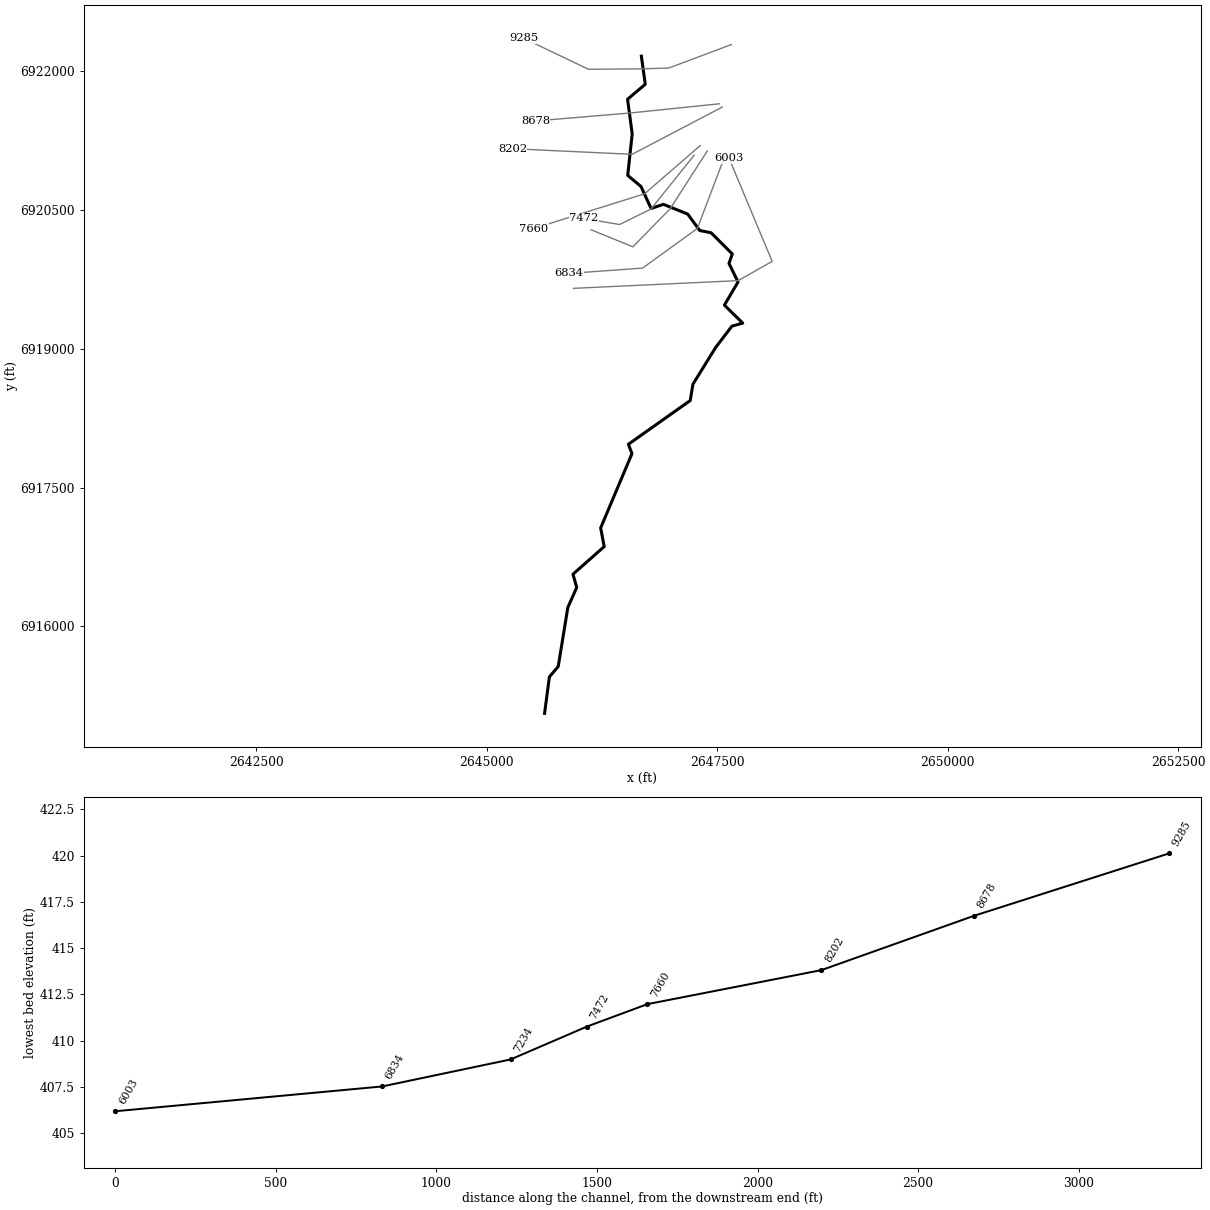
--- Kings Creek Trib 14.prj (project) ---

Proj Title=Kings Creek Trib 14 Base Level Engineering
Current Plan=p01
Default Exp/Contr=0.3,0.1
English Units
Geom File=g01
Flow File=f01
Plan File=p01
BEGIN DESCRIPTION:
Kings Creek Trib 14
END DESCRIPTION:

--- Kings Creek Trib 14.p01 (plan) ---

Plan Title=Multiple Run
Short Identifier=Multiple
Geom File=g01
Flow File=f01
Subcritical Flow
K Sum by GR= 0
Std Step Tol= 0.01
Critical Tol= 0.01
Num of Std Step Trials= 20
Max Error Tol= 0.3
Flow Tol Ratio= 0.001
Split Flow NTrial= 30
Split Flow Tol= 0.02
Split Flow Ratio= 0.02
Log Output Level= 0
Friction Slope Method= 1
Unsteady Friction Slope Method= 2
Unsteady Bridges Friction Slope Method= 1
Parabolic Critical Depth
Global Vel Dist=  1 , 1 , 1
Global Log Level= 0
CheckData=True
Encroach Param= -1, 0, 0, 0
BEGIN DESCRIPTION:
Multiple Run
END DESCRIPTION:

--- Kings Creek Trib 14.f01 (steady flow) ---

Flow Title=Multiple
Number of Profiles=7
Profile Names=10-year,25-year,50-year,1pct_min,100-year,1pct_plu,500-year
River Rch & RM= Kings Creek Trib,Reach-1,9285
     590     794     959     575    1148    2290    1642
River Rch & RM= Kings Creek Trib,Reach-1,7234
     667     900    1089     653    1303    2599    1866
Boundary for River Rch & Prof#=Kings Creek Trib,Reach-1,1
Up Type=0
Dn Type=3
Dn Slope=0.005
Boundary for River Rch & Prof#=Kings Creek Trib,Reach-1,2
Up Type=0
Dn Type=3
Dn Slope=0.005
Boundary for River Rch & Prof#=Kings Creek Trib,Reach-1,3
Up Type=0
Dn Type=3
Dn Slope=0.005
Boundary for River Rch & Prof#=Kings Creek Trib,Reach-1,4
Up Type=0
Dn Type=3
Dn Slope=0.005
Boundary for River Rch & Prof#=Kings Creek Trib,Reach-1,5
Up Type=0
Dn Type=3
Dn Slope=0.005
Boundary for River Rch & Prof#=Kings Creek Trib,Reach-1,6
Up Type=0
Dn Type=3
Dn Slope=0.005
Boundary for River Rch & Prof#=Kings Creek Trib,Reach-1,7
Up Type=0
Dn Type=3
Dn Slope=0.005

--- Kings Creek Trib 14.g01 (geometry) ---

Geom Title=Existing Conditions

River Reach=Kings Creek Trib,Reach-1
Reach XY= 30
      2646676.00      6922161.00      2646718.31      6921857.33
      2646526.25      6921695.79      2646576.45      6921321.19
      2646527.90      6920872.95      2646672.43      6920752.49
      2646781.25      6920515.63      2646915.30      6920560.23
      2647178.55      6920455.27      2647309.21      6920277.44
      2647432.17      6920253.14      2647662.46      6920024.38
      2647626.65      6919921.64      2647724.92      6919721.55
      2647576.82      6919471.44      2647775.94      6919276.79
      2647658.90      6919244.69      2647484.14      6919017.06
      2647235.58      6918617.55      2647206.24      6918440.87
      2646535.03      6917968.01      2646574.16      6917867.13
      2646234.23      6917064.23      2646272.85      6916862.64
      2645933.80      6916564.42      2645974.89      6916421.55
      2645878.26      6916205.06      2645773.92      6915566.86
      2645678.08      6915455.14      2645626.00      6915061.00

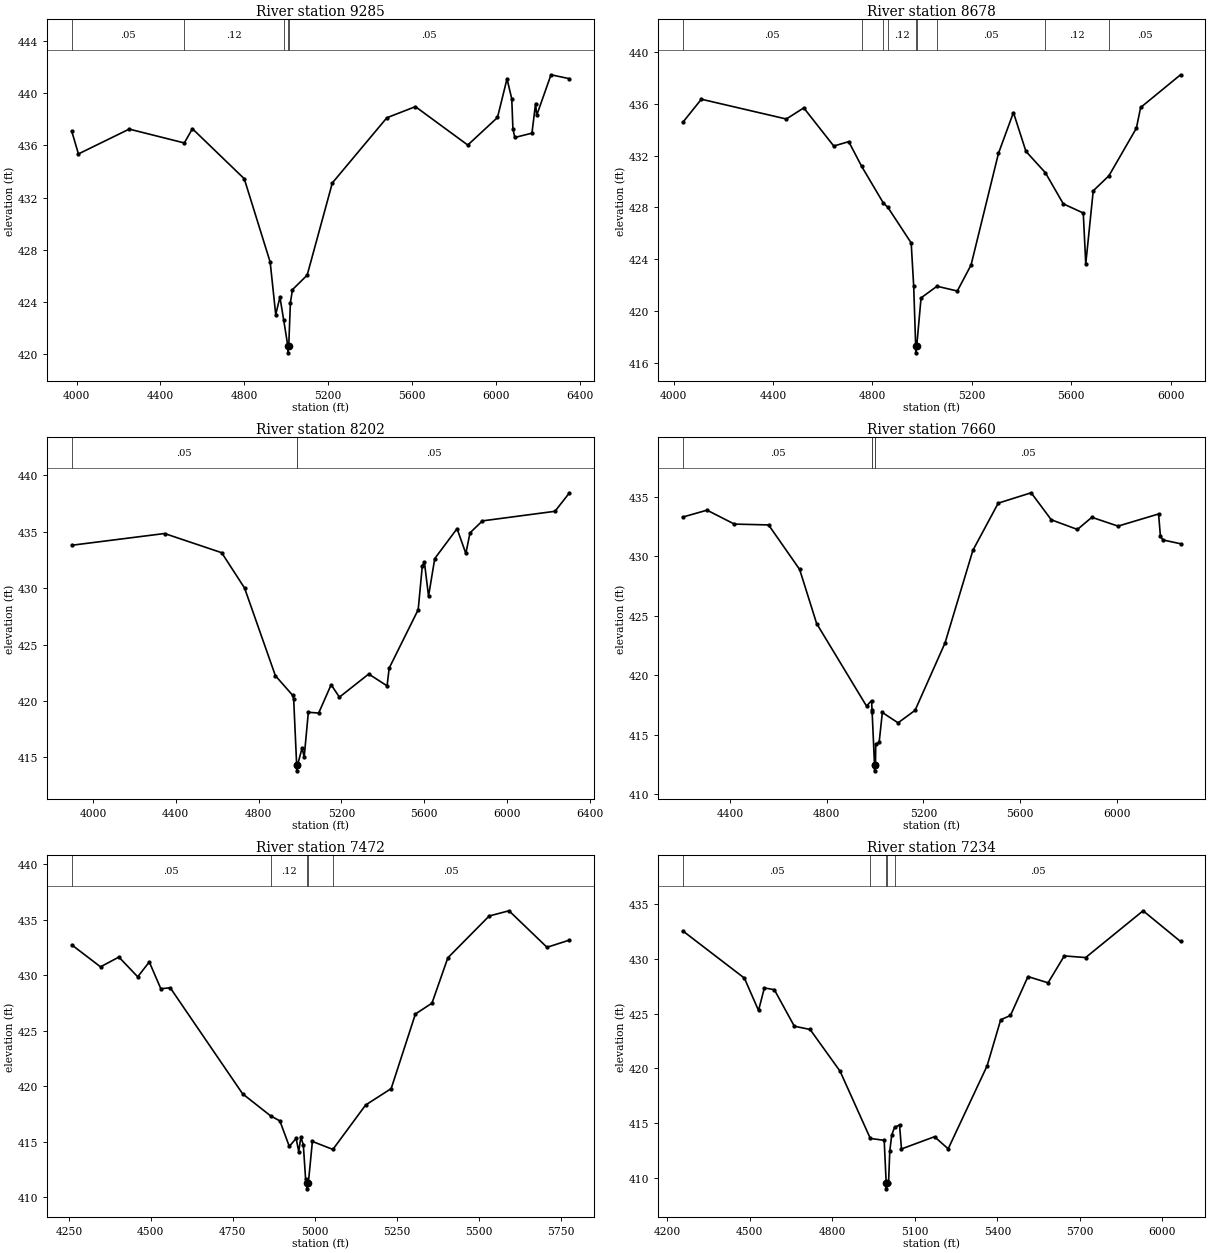
Type RM Length L Ch R = 1,9285,607,607,607
BEGIN DESCRIPTION:
Mapping XS d4f7d326
END DESCRIPTION:
XS GIS Cut Line= 5
      2647652.74      6922286.46      2646973.50      6922032.56
      2646682.70      6922023.88      2646101.11      6922019.54
      2645400.54      6922353.55
#Sta/Elev= 30
  3976.8  437.09  4008.7  435.35  4250.9  437.25  4513.8  436.19  4552.2  437.28
  4799.5  433.45  4923.1  427.07  4949.6  423.05  4969.6  424.39  4987.6  422.63
  5007.6  420.62  5007.8  420.12  5011.6  420.62  5019.6  423.96  5029.6  424.96
  5099.6  426.07  5219.6  433.13  5479.6  438.12  5615.8  438.97  5865.5  436.03
  6007.2  438.14  6052.6  441.10  6075.3  439.57  6080.8  437.27  6089.7  436.61
  6171.6  436.94  6188.8  439.21  6194.3  438.31  6262.4  441.41  6350.6  441.11
#Mann=5,-1,0
  3976.8    0.05       0  4513.8    0.12       0  4987.6    0.05       0
  5007.6    0.03       0  5011.6    0.05       0
Bank Sta=5007.6,5011.6
Exp/Cntr=0.3,0.1

Type RM Length L Ch R = 1,8678,476,476,476
BEGIN DESCRIPTION:
Kings Creek Trib 14 17.0
END DESCRIPTION:
XS GIS Cut Line= 3
      2647520.39      6921646.28      2646562.04      6921547.79
      2645525.97      6921461.00
#Sta/Elev= 30
  4036.6  434.57  4111.4  436.36  4453.2  434.83  4523.5  435.69  4644.2  432.74
  4704.5  433.08  4756.4  431.17  4844.2  428.32  4861.2  428.02  4955.8  425.25
  4965.9  421.89  4973.9  417.25  4974.2  416.75  4977.9  417.25  4995.5  421.00
  5059.7  421.90  5141.4  421.53  5196.7  423.54  5307.1  432.18  5367.3  435.33
  5417.5  432.33  5495.7  430.68  5568.0  428.27  5648.3  427.56  5658.3  423.63
  5688.4  429.28  5751.5  430.44  5862.0  434.12  5879.1  435.72  6039.7  438.25
#Mann=9,-1,0
  4036.6    0.05       0  4756.4    0.12       0  4844.2    0.05       0
  4861.2    0.12       0  4973.9    0.07       0  4977.9    0.12       0
  5059.7    0.05       0  5495.7    0.12       0  5751.5    0.05       0
Bank Sta=4973.9,4977.9
Exp/Cntr=0.3,0.1

Type RM Length L Ch R = 1,8202,542,542,542
BEGIN DESCRIPTION:
Kings Creek Trib 14 16.0
END DESCRIPTION:
XS GIS Cut Line= 3
      2647553.39      6921610.92      2646576.45      6921100.81
      2645276.04      6921161.00
#Sta/Elev= 30
  3897.9  433.80  4346.2  434.84  4622.0  433.14  4732.5  430.01  4881.4  422.24
  4964.1  420.52  4969.7  420.17  4984.2  414.31  4984.4  413.81  4988.2  414.31
  5010.5  415.84  5020.5  415.02  5040.5  419.00  5090.5  418.93  5150.6  421.44
  5190.7  420.34  5332.2  422.39  5420.9  421.34  5430.9  422.91  5571.1  428.09
  5591.1  431.99  5601.1  432.29  5621.1  429.29  5651.1  432.62  5758.7  435.27
  5801.3  433.07  5821.3  434.90  5881.4  435.96  6231.8  436.81  6301.8  438.45
#Mann=3,-1,0
  3897.9    0.05       0  4984.2    0.04       0  4988.2    0.05       0
Bank Sta=4984.2,4988.2
Exp/Cntr=0.3,0.1

Type RM Length L Ch R = 1,7660,188,188,188
BEGIN DESCRIPTION:
Mapping XS d6e1bb13
END DESCRIPTION:
XS GIS Cut Line= 3
      2647313.76      6921194.22      2646709.61      6920673.40
      2645506.46      6920298.39
#Sta/Elev= 30
  4205.0  433.28  4305.3  433.86  4418.3  432.69  4559.8  432.62  4688.2  428.88
  4758.4  424.34  4964.6  417.41  4985.5  417.87  4987.5  417.08  4987.9  416.92
  4997.7  412.47  4998.0  411.97  5001.7  412.47  5002.7  414.20  5016.9  414.37
  5030.1  416.87  5095.1  416.00  5165.4  417.05  5289.3  422.71  5404.5  430.49
  5509.2  434.45  5645.4  435.32  5728.6  433.05  5836.6  432.24  5896.4  433.26
  6004.4  432.52  6172.2  433.54  6179.6  431.70  6190.1  431.36  6262.9  431.04
#Mann=5,-1,0
  4205.0    0.05       0  4987.5    0.12       0  4987.9    0.05       0
  4997.7    0.04       0  5001.7    0.05       0
Bank Sta=4997.7,5001.7
Exp/Cntr=0.3,0.1

Type RM Length L Ch R = 1,7472,238,238,238
BEGIN DESCRIPTION:
Mapping XS 69aa8af4
END DESCRIPTION:
XS GIS Cut Line= 4
      2647248.85      6921090.91      2646780.12      6920509.34
      2646439.41      6920342.24      2646053.08      6920407.35
#Sta/Elev= 30
  4258.8  432.74  4346.6  430.76  4402.6  431.64  4460.1  429.86  4495.3  431.20
  4530.5  428.79  4559.3  428.87  4780.0  419.32  4865.1  417.34  4893.6  416.88
  4922.4  414.58  4943.2  415.31  4951.2  414.12  4957.6  415.40  4965.1  414.75
  4972.0  411.69  4976.4  411.26  4976.7  410.76  4980.4  411.26  4992.8  415.03
  5055.3  414.31  5155.1  418.31  5233.1  419.79  5307.0  426.51  5357.6  427.49
  5405.9  431.57  5532.0  435.34  5592.5  435.81  5708.4  432.52  5777.0  433.17
#Mann=5,-1,0
  4258.8    0.05       0  4865.1    0.12       0  4976.4    0.07       0
  4980.4    0.12       0  5055.3    0.05       0
Bank Sta=4976.4,4980.4
Exp/Cntr=0.3,0.1

Type RM Length L Ch R = 1,7234,400,400,400
BEGIN DESCRIPTION:
Mapping XS d723eff0
END DESCRIPTION:
XS GIS Cut Line= 4
      2647390.97      6921136.31      2646987.31      6920511.29
      2646583.67      6920101.13      2646130.51      6920285.43
#Sta/Elev= 30
  4257.0  432.58  4480.8  428.26  4532.3  425.30  4553.4  427.36  4589.7  427.20
  4662.3  423.86  4719.7  423.56  4828.6  419.74  4938.5  413.59  4988.9  413.42
  4996.2  409.48  4996.5  408.98  5000.2  409.48  5004.7  409.48  5009.2  412.44
  5016.3  413.91  5026.5  414.60  5044.6  414.83  5051.7  412.63  5171.8  413.75
  5221.4  412.64  5362.8  420.23  5412.3  424.45  5447.7  424.84  5511.3  428.40
  5584.4  427.83  5643.3  430.29  5720.9  430.14  5929.7  434.42  6065.7  431.61
#Mann=5,-1,0
  4257.0    0.05       0  4938.5    0.12       0  4996.2    0.07       0
  5000.2    0.12       0  5026.5    0.05       0
Bank Sta=4996.2,5000.2
Exp/Cntr=0.3,0.1

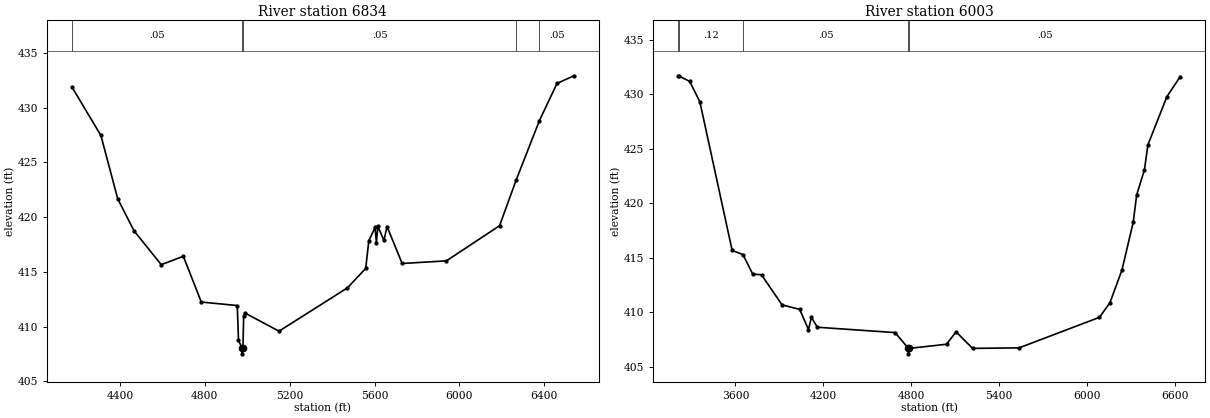
Type RM Length L Ch R = 1,6834,831,831,831
BEGIN DESCRIPTION:
Mapping XS bbc86984
END DESCRIPTION:
XS GIS Cut Line= 4
      2647579.39      6921074.40      2647282.53      6920298.40
      2646688.78      6919871.32      2645886.66      6919814.02
#Sta/Elev= 30
  4173.3  431.88  4309.8  427.46  4389.2  421.67  4466.0  418.75  4594.5  415.66
  4698.4  416.43  4783.2  412.25  4952.8  411.93  4958.5  408.77  4975.5  408.02
  4975.8  407.52  4979.5  408.02  4982.9  410.97  4990.7  411.23  5149.6  409.59
  5472.4  413.55  5558.3  415.32  5573.0  417.85  5602.5  419.06  5608.6  417.67
  5615.8  419.16  5644.2  417.88  5659.0  419.14  5730.2  415.77  5938.8  416.01
  6189.5  419.22  6267.1  423.36  6377.0  428.80  6460.2  432.21  6539.7  432.91
#Mann=5,-1,0
  4173.3    0.05       0  4975.5    0.03       0  4979.5    0.05       0
  6267.1    0.12       0  6377.0    0.05       0
Bank Sta=4975.5,4979.5
Exp/Cntr=0.3,0.1

Type RM Length L Ch R = 1,6003,0,0,0
BEGIN DESCRIPTION:
Kings Creek Trib 14 13.0
END DESCRIPTION:
XS GIS Cut Line= 4
      2645939.87      6919652.62      2647726.42      6919736.00
      2648095.03      6919944.23      2647626.01      6921060.98
#Sta/Elev= 30
  3211.5  431.69  3212.7  431.69  3288.4  431.17  3357.8  429.30  3578.0  415.67
  3652.0  415.28  3718.2  413.50  3778.2  413.43  3918.4  410.67  4038.5  410.26
  4098.6  408.41  4118.6  409.53  4158.7  408.62  4689.2  408.13  4780.3  406.68
  4780.5  406.18  4784.3  406.68  5040.2  407.06  5105.1  408.20  5217.7  406.68
  5535.4  406.73  6083.1  409.53  6154.4  410.86  6236.5  413.87  6313.2  418.24
  6337.0  420.76  6389.9  423.07  6413.7  425.36  6543.3  429.78  6634.6  431.62
#Mann=5,-1,0
  3211.5    0.05       0  3212.7    0.12       0  3652.0    0.05       0
  4780.3    0.04       0  4784.3    0.05       0
Bank Sta=4780.3,4784.3
Exp/Cntr=0.3,0.1

Chan Stop Cuts=-1