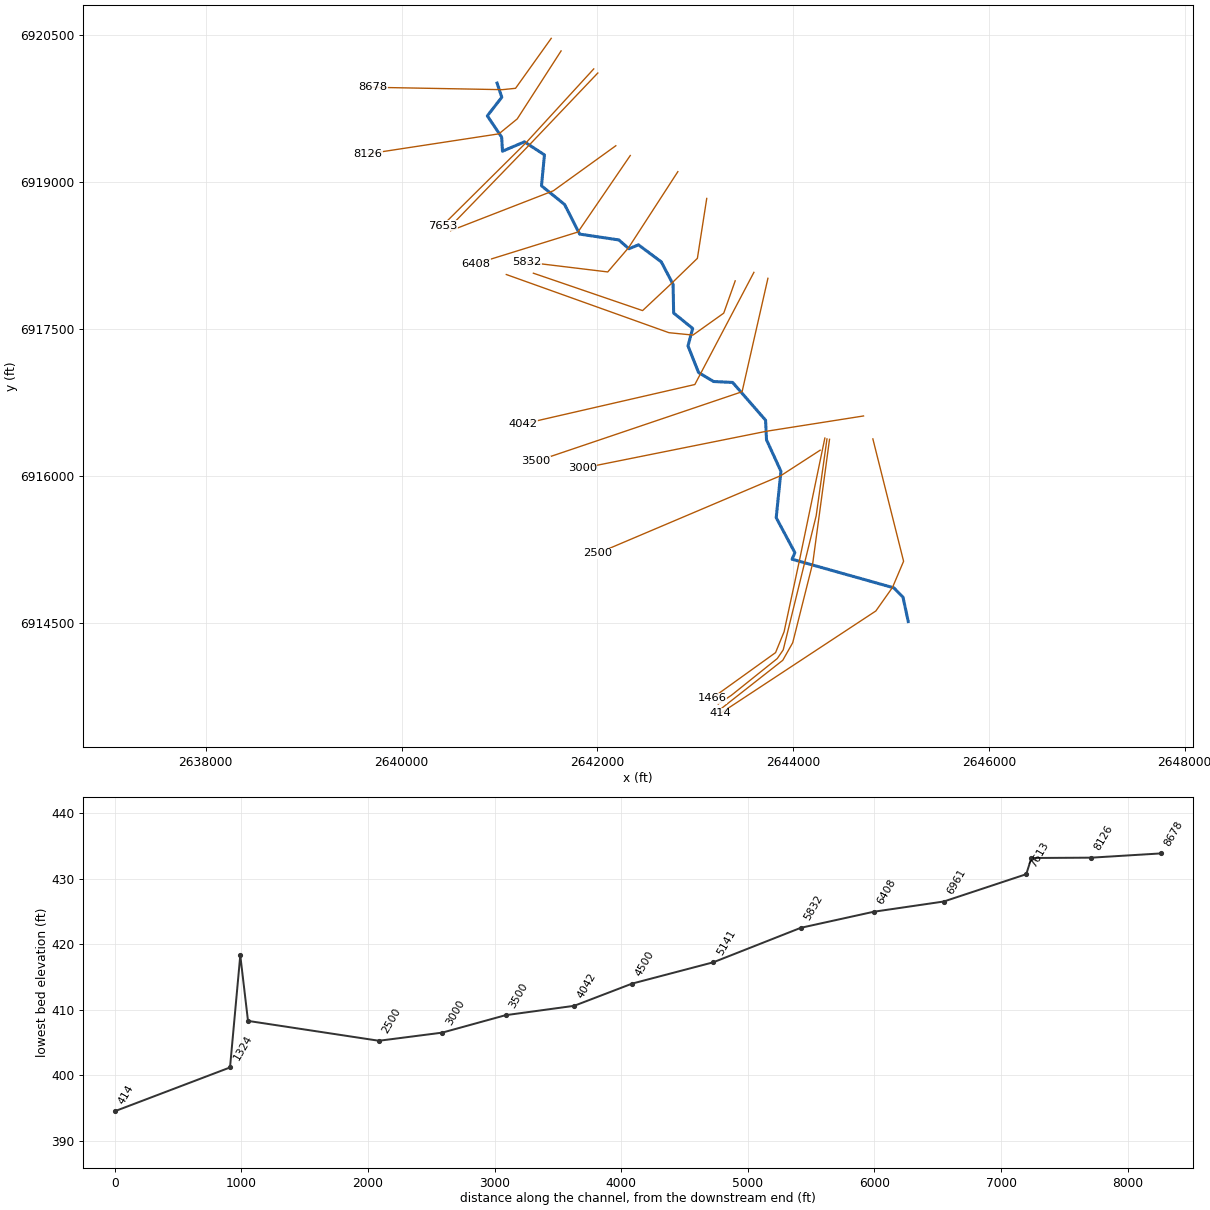
--- Kings Creek Trib 15.prj (project) ---

Proj Title=Kings Creek Trib 15 Base Level Engineering
Current Plan=p01
Default Exp/Contr=0.3,0.1
English Units
Geom File=g01
Flow File=f01
Plan File=p01
BEGIN DESCRIPTION:
Kings Creek Trib 15
END DESCRIPTION:

--- Kings Creek Trib 15.p01 (plan) ---

Plan Title=Multiple Run
Short Identifier=Multiple
Geom File=g01
Flow File=f01
Subcritical Flow
K Sum by GR= 0
Std Step Tol= 0.01
Critical Tol= 0.01
Num of Std Step Trials= 20
Max Error Tol= 0.3
Flow Tol Ratio= 0.001
Split Flow NTrial= 30
Split Flow Tol= 0.02
Split Flow Ratio= 0.02
Log Output Level= 0
Friction Slope Method= 1
Unsteady Friction Slope Method= 2
Unsteady Bridges Friction Slope Method= 1
Parabolic Critical Depth
Global Vel Dist=  1 , 1 , 1
Global Log Level= 0
CheckData=True
Encroach Param= -1, 0, 0, 0
BEGIN DESCRIPTION:
Multiple Run
END DESCRIPTION:

--- Kings Creek Trib 15.f01 (steady flow) ---

Flow Title=Multiple
Number of Profiles=7
Profile Names=10-year,25-year,50-year,1pct_min,100-year,1pct_plu,500-year
River Rch & RM= Kings Creek Trib,Reach-1,8678
     496     660     792     471     941    1877    1326
River Rch & RM= Kings Creek Trib,Reach-1,3500
     510     680     817     486     971    1937    1371
River Rch & RM= Kings Creek Trib,Reach-1,2500
     870    1198    1468     892    1779    3550    2615
River Rch & RM= Kings Creek Trib,Reach-1,1324
     913    1260    1548     942    1879    3750    2773
Boundary for River Rch & Prof#=Kings Creek Trib,Reach-1,1
Up Type=0
Dn Type=3
Dn Slope=0.005
Boundary for River Rch & Prof#=Kings Creek Trib,Reach-1,2
Up Type=0
Dn Type=3
Dn Slope=0.005
Boundary for River Rch & Prof#=Kings Creek Trib,Reach-1,3
Up Type=0
Dn Type=3
Dn Slope=0.005
Boundary for River Rch & Prof#=Kings Creek Trib,Reach-1,4
Up Type=0
Dn Type=3
Dn Slope=0.005
Boundary for River Rch & Prof#=Kings Creek Trib,Reach-1,5
Up Type=0
Dn Type=3
Dn Slope=0.005
Boundary for River Rch & Prof#=Kings Creek Trib,Reach-1,6
Up Type=0
Dn Type=3
Dn Slope=0.005
Boundary for River Rch & Prof#=Kings Creek Trib,Reach-1,7
Up Type=0
Dn Type=3
Dn Slope=0.005

--- Kings Creek Trib 15.g01 (geometry) ---

Geom Title=Existing Conditions

River Reach=Kings Creek Trib,Reach-1
Reach XY= 30
      2640976.00      6920011.00      2641024.05      6919866.88
      2640876.01      6919676.41      2641022.44      6919459.52
      2641031.19      6919315.56      2641255.90      6919411.11
      2641459.80      6919277.71      2641429.45      6918962.25
      2641665.56      6918771.08      2641819.48      6918468.68
      2642220.14      6918408.92      2642322.60      6918318.83
      2642419.90      6918359.17      2642653.27      6918184.89
      2642773.93      6917955.14      2642779.45      6917662.25
      2642974.04      6917505.12      2642926.09      6917326.39
      2643034.14      6917054.32      2643187.83      6916962.66
      2643382.19      6916953.19      2643718.57      6916567.35
      2643728.24      6916366.93      2643875.48      6916045.78
      2643827.22      6915571.50      2644017.98      6915214.32
      2643989.47      6915147.24      2645028.31      6914855.17
      2645122.46      6914759.54      2645176.00      6914511.00

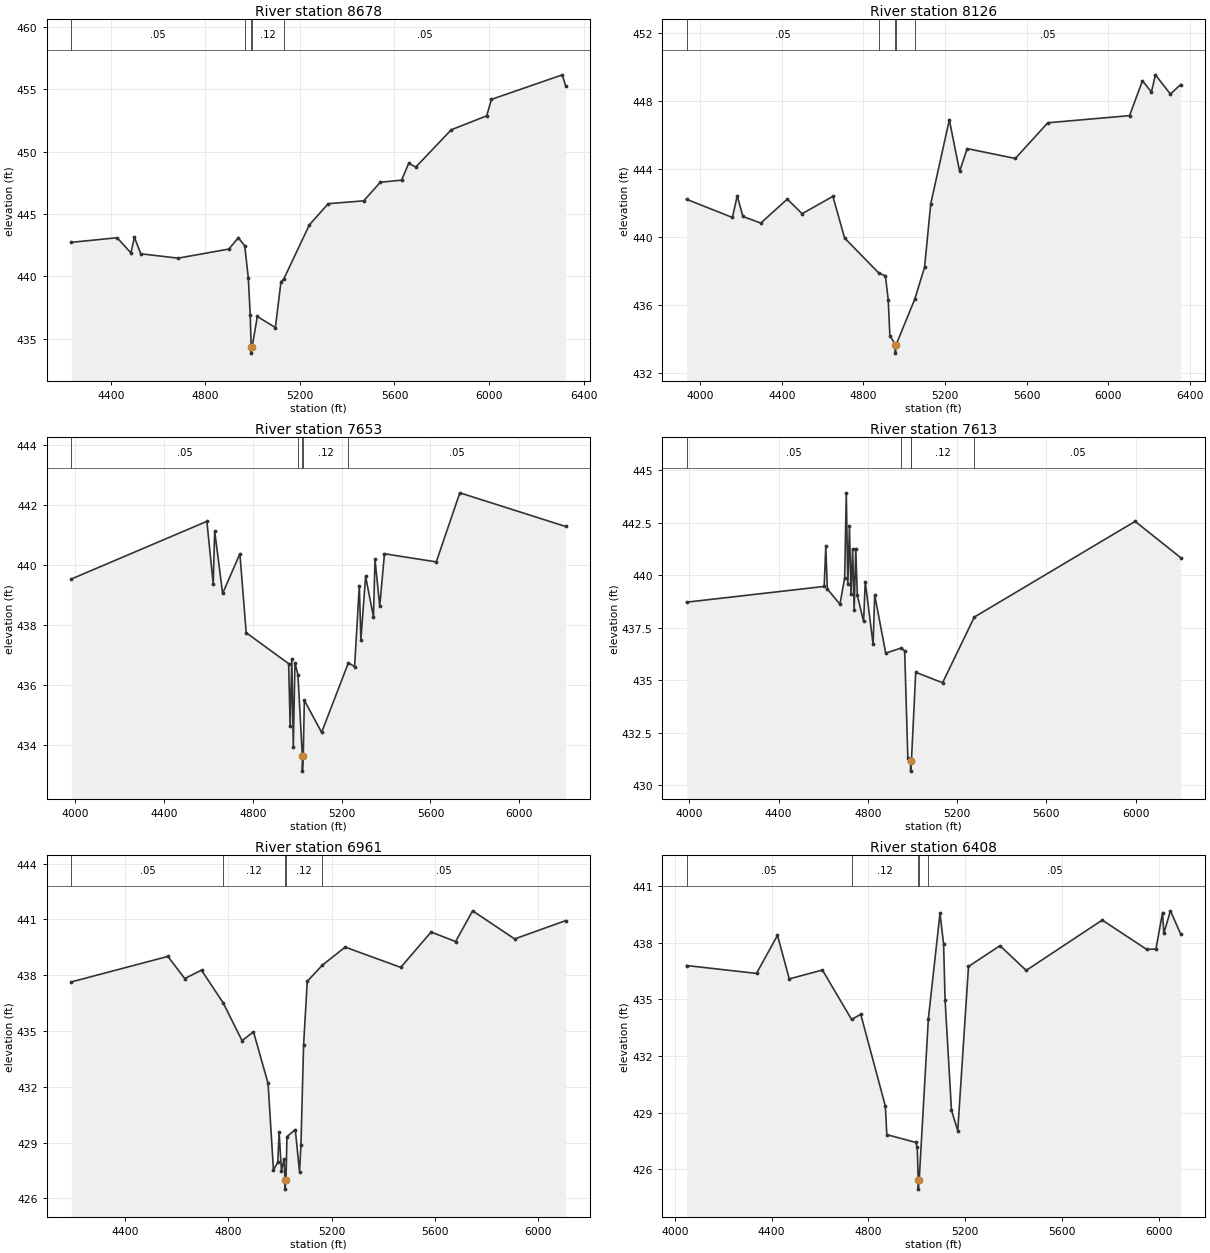
Type RM Length L Ch R = 1,8678,552,552,552
BEGIN DESCRIPTION:
Mapping XS 8d1d14ab
END DESCRIPTION:
XS GIS Cut Line= 4
      2641529.06      6920468.48      2641164.46      6919958.04
      2641029.05      6919944.16      2639702.68      6919968.46
#Sta/Elev= 30
  4233.5  442.73  4427.0  443.10  4485.3  441.88  4500.0  443.13  4527.1  441.81
  4685.1  441.46  4899.4  442.19  4939.7  443.10  4966.7  442.45  4981.9  439.87
  4989.9  436.90  4993.9  434.34  4994.2  433.84  4997.9  434.34  5020.0  436.78
  5096.3  435.89  5120.0  439.57  5131.9  439.79  5240.0  444.13  5320.0  445.83
  5470.0  446.06  5540.0  447.55  5630.1  447.72  5660.1  449.07  5690.1  448.77
  5840.1  451.76  5990.1  452.88  6010.1  454.20  6310.2  456.17  6323.5  455.30
#Mann=5,-1,0
  4233.5    0.05       0  4966.7    0.12       0  4993.9    0.07       0
  4997.9    0.12       0  5131.9    0.05       0
Bank Sta=4993.9,4997.9
Exp/Cntr=0.3,0.1

Type RM Length L Ch R = 1,8126,473,473,473
BEGIN DESCRIPTION:
Mapping XS 5cbf080a
END DESCRIPTION:
XS GIS Cut Line= 4
      2641629.74      6920339.98      2641181.83      6919645.54
      2640994.33      6919492.77      2639654.01      6919287.90
#Sta/Elev= 30
  3932.1  442.24  4157.0  441.17  4180.8  442.44  4208.5  441.23  4296.3  440.84
  4426.3  442.25  4498.9  441.39  4650.1  442.41  4707.5  439.96  4874.5  437.91
  4907.9  437.73  4921.6  436.30  4929.5  434.22  4956.3  433.69  4956.5  433.19
  4960.3  433.69  5052.2  436.38  5099.8  438.25  5130.1  441.98  5221.2  446.91
  5271.8  443.88  5308.5  445.22  5544.9  444.64  5704.3  446.74  6105.2  447.16
  6168.6  449.21  6212.6  448.55  6232.1  449.56  6305.6  448.43  6356.2  448.99
#Mann=5,-1,0
  3932.1    0.05       0  4874.5    0.12       0  4956.3    0.07       0
  4960.3    0.12       0  5052.2    0.05       0
Bank Sta=4956.3,4960.3
Exp/Cntr=0.3,0.1

Type RM Length L Ch R = 1,7653,40,40,40
BEGIN DESCRIPTION:
Mapping XS 5e6ef0f9
END DESCRIPTION:
XS GIS Cut Line= 3
      2641963.08      6920155.96      2641275.58      6919405.96
      2640418.30      6918555.63
#Sta/Elev= 30
  3983.3  439.54  4593.4  441.46  4621.8  439.38  4628.6  441.13  4664.3  439.06
  4742.0  440.38  4770.4  437.75  4961.5  436.72  4968.3  434.63  4975.7  436.89
  4982.5  433.96  4989.9  436.75  5003.4  436.35  5023.2  433.64  5023.4  433.14
  5027.2  433.64  5032.2  435.50  5110.0  434.43  5230.6  436.75  5258.5  436.62
  5279.7  439.32  5286.8  437.52  5308.0  439.63  5343.3  438.28  5350.4  440.19
  5371.6  438.63  5392.9  440.38  5626.2  440.11  5732.3  442.41  6208.2  441.29
#Mann=5,-1,0
  3983.3    0.05       0  5003.4    0.12       0  5023.2    0.03       0
  5027.2    0.12       0  5230.6    0.05       0
Bank Sta=5023.2,5027.2
Exp/Cntr=0.3,0.1

Type RM Length L Ch R = 1,7613,652,652,652
BEGIN DESCRIPTION:
Mapping XS ae04b158
END DESCRIPTION:
XS GIS Cut Line= 3
      2642004.74      6920114.29      2641320.71      6919395.54
      2640470.49      6918517.56
#Sta/Elev= 30
  3987.4  438.72  4604.2  439.47  4611.4  441.38  4618.3  439.35  4674.9  438.62
  4696.0  439.88  4703.2  443.93  4710.1  439.58  4717.4  442.34  4724.3  439.11
  4731.6  441.26  4738.5  438.33  4745.7  441.27  4752.6  439.04  4780.9  437.80
  4788.2  439.70  4823.4  436.71  4830.6  439.06  4880.0  436.29  4950.5  436.54
  4964.9  436.39  4979.1  431.29  4991.2  431.17  4991.5  430.67  4995.2  431.17
  5014.4  435.38  5134.7  434.88  5276.9  438.01  5997.5  442.57  6201.8  440.84
#Mann=5,-1,0
  3987.4    0.05       0  4950.5    0.12       0  4991.2    0.07       0
  4995.2    0.12       0  5276.9    0.05       0
Bank Sta=4991.2,4995.2
Exp/Cntr=0.3,0.1

Type RM Length L Ch R = 1,6961,553,553,553
BEGIN DESCRIPTION:
Mapping XS d0c52013
END DESCRIPTION:
XS GIS Cut Line= 3
      2642188.79      6919371.25      2641550.75      6918911.17
      2640500.70      6918503.30
#Sta/Elev= 30
  4192.4  437.64  4566.1  439.01  4631.2  437.82  4696.2  438.27  4780.6  436.50
  4853.2  434.48  4897.4  434.96  4953.9  432.18  4974.7  427.53  4991.4  427.94
  4996.7  429.56  5005.6  427.48  5015.9  428.14  5019.3  427.00  5019.5  426.50
  5023.3  427.00  5027.0  429.32  5059.2  429.70  5075.7  427.42  5081.1  428.87
  5091.4  434.26  5105.6  437.67  5164.0  438.54  5252.3  439.51  5467.5  438.42
  5584.9  440.32  5679.9  439.81  5745.8  441.46  5908.4  439.95  6105.5  440.93
#Mann=5,-1,0
  4192.4    0.05       0  4780.6    0.12       0  5019.3    0.07       0
  5023.3    0.12       0  5164.0    0.05       0
Bank Sta=5019.3,5023.3
Exp/Cntr=0.3,0.1

Type RM Length L Ch R = 1,6408,576,576,576
BEGIN DESCRIPTION:
Mapping XS 49dfb6aa
END DESCRIPTION:
XS GIS Cut Line= 3
      2642336.36      6919271.45      2641802.49      6918490.16
      2640756.44      6918164.63
#Sta/Elev= 30
  4048.2  436.80  4337.3  436.38  4424.0  438.40  4472.7  436.09  4609.6  436.56
  4730.1  433.94  4768.0  434.21  4869.7  429.34  4875.7  427.83  4994.5  427.42
  5001.3  427.19  5005.5  425.44  5005.7  424.94  5009.5  425.44  5047.3  433.97
  5095.5  439.57  5110.3  437.94  5116.5  434.96  5142.9  429.12  5168.8  428.04
  5213.2  436.75  5343.3  437.85  5451.6  436.54  5765.8  439.21  5949.9  437.65
  5987.7  437.68  6015.0  439.61  6020.2  438.50  6047.5  439.70  6090.0  438.47
#Mann=5,-1,0
  4048.2    0.05       0  4730.1    0.12       0  5005.5    0.07       0
  5009.5    0.12       0  5047.3    0.05       0
Bank Sta=5005.5,5009.5
Exp/Cntr=0.3,0.1

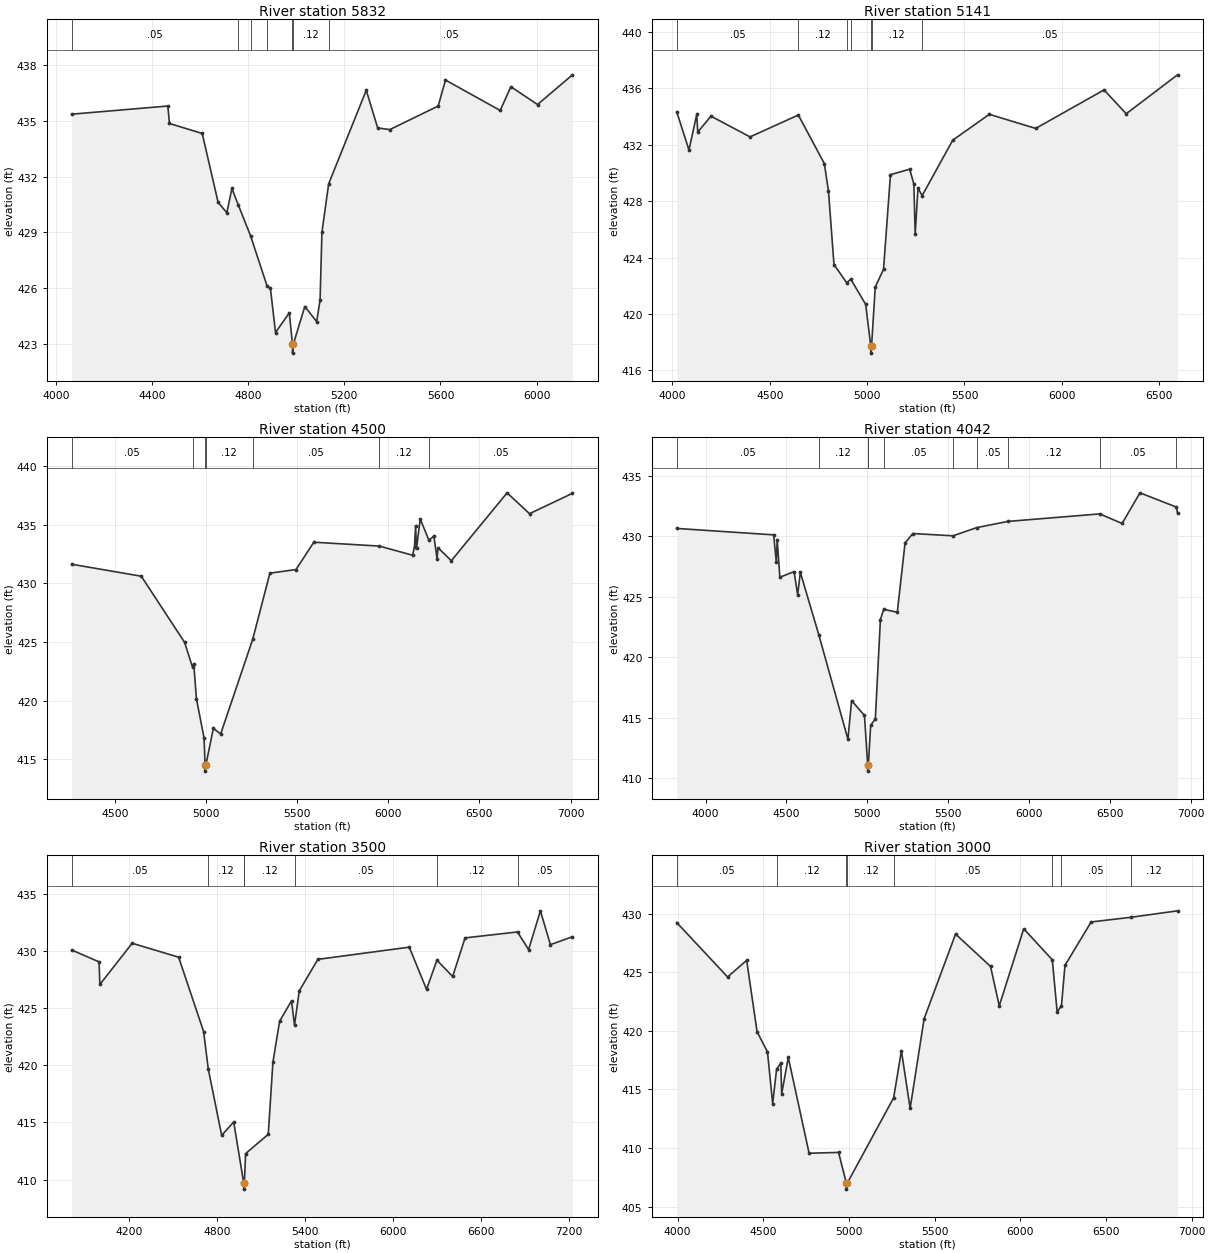
Type RM Length L Ch R = 1,5832,691,691,691
BEGIN DESCRIPTION:
Mapping XS 6be747cb
END DESCRIPTION:
XS GIS Cut Line= 4
      2642822.46      6919106.49      2642318.98      6918329.57
      2642106.30      6918082.18      2641281.66      6918182.00
#Sta/Elev= 30
  4066.4  435.36  4466.2  435.80  4472.9  434.86  4609.2  434.32  4675.3  430.61
  4711.6  430.05  4732.7  431.36  4759.9  430.45  4810.2  428.81  4878.4  426.13
  4892.9  425.98  4914.0  423.60  4971.4  424.66  4984.5  422.99  4984.8  422.49
  4988.5  422.99  5035.8  425.00  5085.2  424.19  5099.4  425.35  5107.1  429.00
  5135.1  431.61  5291.5  436.65  5338.9  434.62  5389.3  434.53  5590.7  435.80
  5620.9  437.20  5848.5  435.56  5892.9  436.84  6003.7  435.88  6149.1  437.48
#Mann=7,-1,0
  4066.4    0.05       0  4759.9    0.12       0  4810.2    0.05       0
  4878.4    0.12       0  4984.5    0.07       0  4988.5    0.12       0
  5135.1    0.05       0
Bank Sta=4984.5,4988.5
Exp/Cntr=0.3,0.1

Type RM Length L Ch R = 1,5141,641,641,641
BEGIN DESCRIPTION:
Mapping XS 7cf8336b
END DESCRIPTION:
XS GIS Cut Line= 5
      2643117.59      6918833.02      2643022.10      6918221.07
      2642744.33      6917951.97      2642462.21      6917687.21
      2641346.78      6918069.15
#Sta/Elev= 30
  4022.3  434.34  4085.1  431.63  4125.2  434.16  4130.2  432.90  4198.1  434.03
  4398.8  432.56  4646.8  434.11  4780.4  430.67  4801.7  428.71  4830.0  423.51
  4895.2  422.22  4916.2  422.47  4992.6  420.69  5018.9  417.73  5019.1  417.23
  5022.9  417.73  5041.9  421.92  5084.4  423.17  5120.0  429.88  5218.7  430.27
  5240.2  429.22  5247.0  425.67  5261.2  428.92  5282.9  428.40  5440.1  432.33
  5627.8  434.16  5865.8  433.16  6217.0  435.89  6330.9  434.20  6594.3  436.96
#Mann=7,-1,0
  4022.3    0.05       0  4646.8    0.12       0  4895.2    0.05       0
  4916.2    0.12       0  5018.9    0.07       0  5022.9    0.12       0
  5282.9    0.05       0
Bank Sta=5018.9,5022.9
Exp/Cntr=0.3,0.1

Type RM Length L Ch R = 1,4500,458,458,458
BEGIN DESCRIPTION:
Kings Creek Trib 15 8.0
END DESCRIPTION:
XS GIS Cut Line= 5
      2643408.38      6917990.99      2643291.20      6917661.17
      2642976.45      6917437.07      2642731.30      6917461.52
      2641070.14      6918055.72
#Sta/Elev= 30
  4263.6  431.62  4645.2  430.60  4882.5  424.97  4926.6  422.83  4933.0  423.14
  4947.7  420.16  4989.5  416.82  4995.2  414.48  4995.5  413.98  4999.2  414.48
  5040.6  417.62  5080.8  417.15  5256.7  425.23  5350.8  430.86  5494.1  431.17
  5591.8  433.50  5950.7  433.17  6133.5  432.39  6144.1  433.12  6149.9  434.90
  6155.2  432.98  6175.4  435.48  6223.1  433.67  6250.3  434.02  6267.7  432.10
  6273.0  433.03  6345.9  431.92  6651.9  437.71  6775.0  435.93  7010.6  437.67
#Mann=7,-1,0
  4263.6    0.05       0  4926.6    0.12       0  4995.2    0.07       0
  4999.2    0.12       0  5256.7    0.05       0  5950.7    0.12       0
  6223.1    0.05       0
Bank Sta=4995.2,4999.2
Exp/Cntr=0.3,0.1

Type RM Length L Ch R = 1,4042,542,542,542
BEGIN DESCRIPTION:
Kings Creek Trib 15 7.0
END DESCRIPTION:
XS GIS Cut Line= 3
      2643599.37      6918077.85      2642996.06      6916932.00
      2641239.64      6916528.68
#Sta/Elev= 30
  3821.7  430.63  4421.0  430.10  4437.4  427.87  4443.0  429.71  4459.4  426.60
  4547.5  427.06  4569.6  425.14  4586.0  427.01  4700.5  421.84  4880.5  413.22
  4903.1  416.41  4982.6  415.19  5002.8  411.09  5003.0  410.59  5006.8  411.09
  5021.0  414.37  5050.0  414.91  5081.4  423.11  5101.6  423.95  5185.8  423.71
  5233.8  429.43  5281.8  430.21  5530.3  430.02  5677.5  430.70  5870.4  431.21
  6437.3  431.83  6576.1  431.04  6686.6  433.57  6910.7  432.40  6918.8  431.92
#Mann=10,-1,0
  3821.7    0.05       0  4700.5    0.12       0  5002.8    0.07       0
  5006.8    0.12       0  5101.6    0.05       0  5530.3    0.12       0
  5677.5    0.05       0  5870.4    0.12       0  6437.3    0.05       0
  6910.7    0.12       0
Bank Sta=5002.8,5006.8
Exp/Cntr=0.3,0.1

Type RM Length L Ch R = 1,3500,500,500,500
BEGIN DESCRIPTION:
Kings Creek Trib 15 6.0
END DESCRIPTION:
XS GIS Cut Line= 3
      2643742.59      6918017.08      2643478.65      6916858.37
      2641372.84      6916146.43
#Sta/Elev= 30
  3811.6  430.10  3998.1  429.06  4003.2  427.08  4223.5  430.69  4540.0  429.47
  4710.1  422.96  4741.9  419.68  4833.2  413.87  4915.2  415.04  4983.7  409.66
  4983.9  409.16  4987.7  409.66  4996.1  412.27  5150.6  413.96  5182.3  420.28
  5227.9  423.87  5308.9  425.65  5329.3  423.51  5361.7  426.52  5488.4  429.28
  6111.2  430.35  6228.8  426.65  6299.5  429.21  6406.8  427.78  6491.2  431.16
  6848.4  431.68  6924.0  430.13  7004.4  433.53  7072.6  430.57  7222.9  431.26
#Mann=7,-1,0
  3811.6    0.05       0  4741.9    0.12       0  4983.7    0.07       0
  4987.7    0.12       0  5329.3    0.05       0  6299.5    0.12       0
  6848.4    0.05       0
Bank Sta=4983.7,4987.7
Exp/Cntr=0.3,0.1

Type RM Length L Ch R = 1,3000,500,500,500
BEGIN DESCRIPTION:
Kings Creek Trib 15 5.0
END DESCRIPTION:
XS GIS Cut Line= 3
      2644719.18      6916610.83      2643725.93      6916454.34
      2641845.93      6916076.98
#Sta/Elev= 30
  3994.5  429.23  4291.3  424.59  4402.7  426.01  4463.4  419.92  4524.1  418.20
  4554.5  413.79  4577.4  416.73  4601.9  417.23  4607.0  414.62  4645.6  417.73
  4767.1  409.56  4939.2  409.63  4984.6  407.00  4985.2  406.50  4989.5  407.00
  5260.6  414.29  5305.9  418.30  5356.9  413.39  5438.5  421.03  5622.1  428.25
  5826.1  425.49  5877.1  422.13  6019.9  428.70  6186.8  426.05  6214.9  421.62
  6239.9  422.12  6260.7  425.58  6413.4  429.28  6645.8  429.68  6917.5  430.23
#Mann=8,-1,0
  3994.5    0.05       0  4577.4    0.12       0  4984.6    0.07       0
  4989.5    0.12       0  5260.6    0.05       0  6186.8    0.12       0
  6239.9    0.05       0  6645.8    0.12       0
Bank Sta=4984.6,4989.5
Exp/Cntr=0.3,0.1

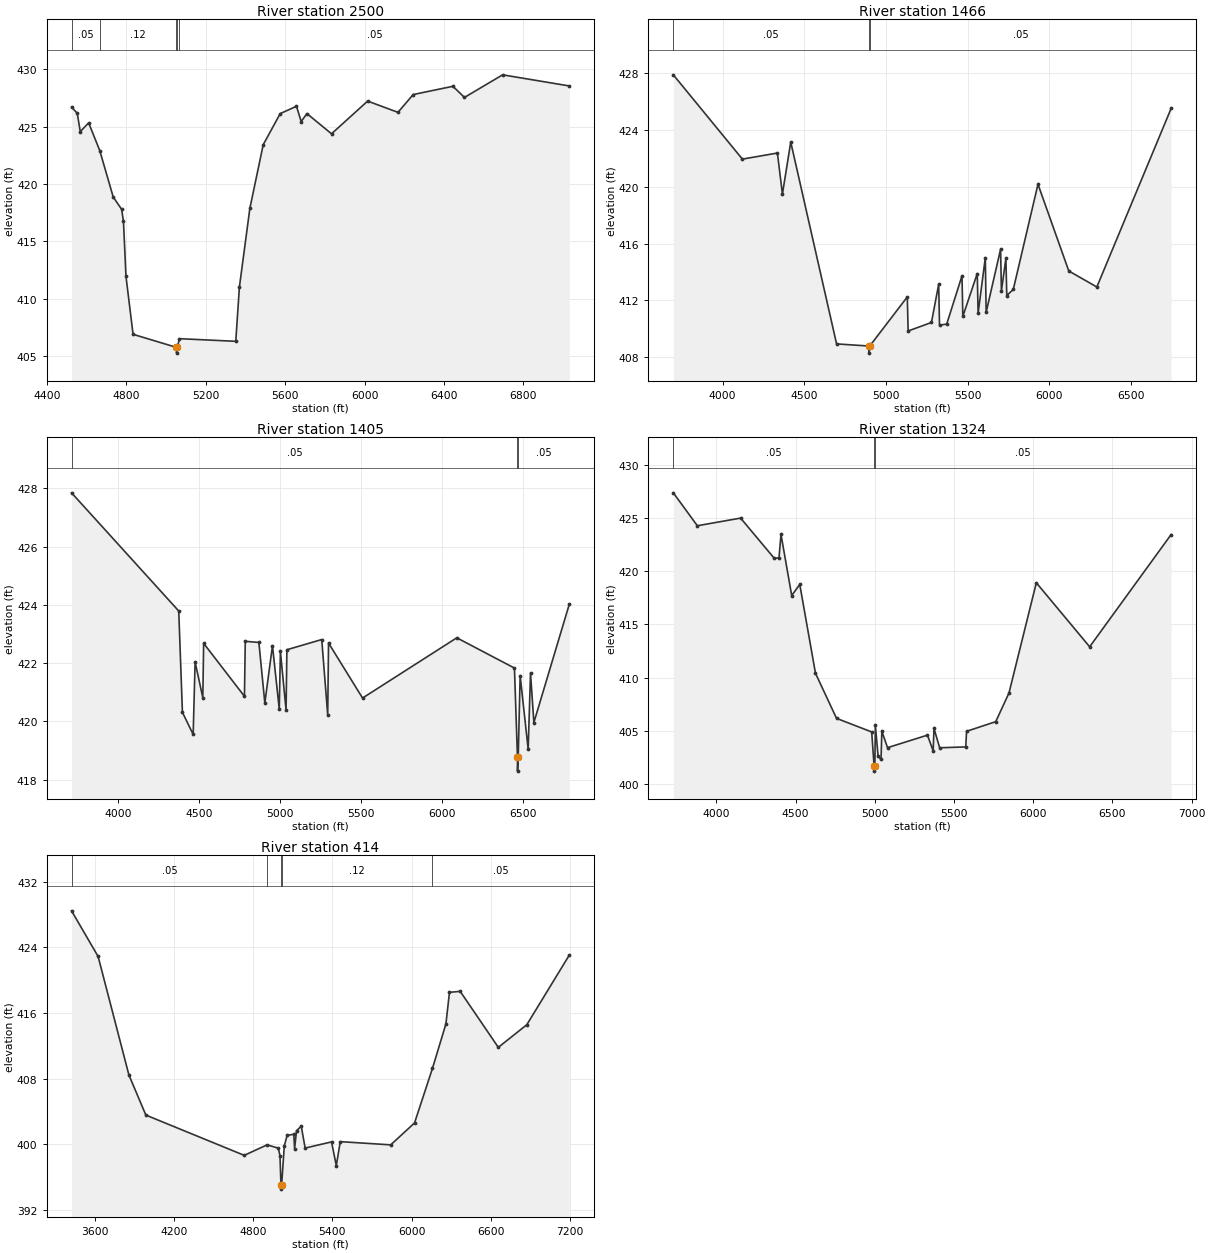
Type RM Length L Ch R = 1,2500,1034,1034,1034
BEGIN DESCRIPTION:
Kings Creek Trib 15 4.0
END DESCRIPTION:
XS GIS Cut Line= 3
      2644276.00      6916261.00      2643876.35      6916002.08
      2642006.51      6915208.93
#Sta/Elev= 30
  4523.8  426.71  4552.5  426.17  4567.6  424.57  4609.9  425.33  4666.0  422.91
  4733.8  418.86  4776.0  417.80  4785.2  416.75  4797.9  411.95  4833.6  406.90
  5052.2  405.76  5052.8  405.26  5057.1  405.76  5066.8  406.52  5350.9  406.29
  5369.2  411.02  5421.9  417.88  5489.2  423.43  5574.8  426.14  5656.7  426.78
  5680.3  425.45  5709.4  426.14  5833.2  424.38  6015.1  427.23  6168.0  426.25
  6244.4  427.80  6444.6  428.52  6502.8  427.55  6694.9  429.52  7031.1  428.55
#Mann=5,-1,0
  4523.8    0.05       0  4666.0    0.12       0  5052.2    0.07       0
  5057.1    0.12       0  5066.8    0.05       0
Bank Sta=5052.2,5057.1
Exp/Cntr=0.3,0.1

Type RM Length L Ch R = 1,1466,61,61,61
BEGIN DESCRIPTION:
Mapping XS de3ad4f5
END DESCRIPTION:
XS GIS Cut Line= 5
      2644324.19      6916385.13      2644063.77      6915130.79
      2643907.52      6914405.96      2643820.71      6914193.29
      2643174.05      6913728.91
#Sta/Elev= 30
  3698.2  427.90  4121.2  421.96  4335.6  422.39  4366.3  419.50  4417.3  423.16
  4698.0  408.94  4896.0  408.79  4896.6  408.29  4901.0  408.79  5131.1  412.25
  5136.2  409.85  5279.0  410.45  5323.2  413.14  5328.3  410.26  5372.5  410.34
  5466.0  413.74  5471.1  410.88  5559.5  413.90  5564.6  411.09  5608.8  415.02
  5613.9  411.17  5702.3  415.61  5707.4  412.68  5734.8  414.97  5740.2  412.35
  5780.1  412.78  5931.3  420.19  6119.9  414.08  6291.8  412.95  6746.6  425.53
#Mann=3,-1,0
  3698.2    0.05       0  4896.0    0.03       0  4901.0    0.05       0
Bank Sta=4896,4901
Exp/Cntr=0.3,0.1

Type RM Length L Ch R = 1,1405,81,81,81
BEGIN DESCRIPTION:
Mapping XS 627d2ac0
END DESCRIPTION:
XS GIS Cut Line= 6
      2644345.88      6916376.40      2644235.66      6915591.83
      2643898.85      6914221.17      2643837.92      6914132.63
      2643367.95      6913756.24      2643234.75      6913668.10
#Sta/Elev= 30
  3713.2  427.85  4375.0  423.79  4397.7  420.31  4464.0  419.55  4476.0  422.04
  4523.6  420.81  4528.7  422.68  4780.6  420.86  4785.7  422.75  4869.7  422.71
  4906.5  420.63  4953.6  422.60  4995.6  420.42  5002.6  422.40  5037.6  420.39
  5042.7  422.46  5257.8  422.81  5294.7  420.22  5299.8  422.69  5509.8  420.80
  6091.6  422.87  6447.6  421.83  6466.0  418.79  6466.6  418.29  6471.0  418.79
  6482.8  421.57  6532.4  419.04  6546.8  421.66  6567.6  419.96  6786.6  424.03
#Mann=3,-1,0
  3713.2    0.05       0  6466.0    0.03       0  6471.0    0.05       0
Bank Sta=6466,6471
Exp/Cntr=0.3,0.1

Type RM Length L Ch R = 1,1324,910,910,910
BEGIN DESCRIPTION:
Mapping XS 93381224
END DESCRIPTION:
XS GIS Cut Line= 5
      2644371.93      6916372.10      2644201.12      6915111.12
      2643996.08      6914294.95      2643894.50      6914115.16
      2643247.78      6913607.34
#Sta/Elev= 30
  3727.5  427.40  3879.2  424.30  4152.4  425.02  4364.4  421.24  4394.6  421.26
  4407.3  423.48  4474.9  417.73  4525.8  418.77  4625.0  410.41  4757.9  406.16
  4979.9  404.88  4995.0  401.69  4995.6  401.19  5000.0  401.69  5002.9  405.51
  5020.7  402.57  5038.9  402.31  5044.0  404.94  5080.0  403.40  5332.0  404.58
  5368.0  403.10  5373.2  405.21  5409.1  403.39  5573.7  403.47  5578.9  404.94
  5763.1  405.85  5846.7  408.55  6019.3  418.93  6356.0  412.90  6870.3  423.47
#Mann=3,-1,0
  3727.5    0.05       0  4995.0    0.03       0  5000.0    0.05       0
Bank Sta=4995,5000
Exp/Cntr=0.3,0.1

Type RM Length L Ch R = 1,414,0,0,0
BEGIN DESCRIPTION:
Kings Creek Trib 15 1.0
END DESCRIPTION:
XS GIS Cut Line= 5
      2644814.65      6916376.40      2645128.54      6915126.64
      2645015.38      6914859.50      2644845.02      6914618.63
      2643256.50      6913572.64
#Sta/Elev= 30
  3421.3  428.45  3622.8  422.88  3856.3  408.43  3984.9  403.54  4730.8  398.63
  4904.6  399.91  4989.3  399.51  5002.1  398.60  5009.5  395.01  5010.2  394.51
  5014.6  395.01  5034.9  399.79  5056.4  401.06  5106.9  401.20  5113.0  399.44
  5127.8  401.64  5163.5  402.18  5193.0  399.52  5393.2  400.27  5429.3  397.38
  5459.5  400.30  5842.0  399.91  6022.7  402.58  6158.6  409.23  6260.6  414.65
  6287.7  418.51  6369.0  418.63  6658.2  411.80  6874.3  414.56  7197.0  423.06
#Mann=5,-1,0
  3421.3    0.05       0  4904.6    0.12       0  5009.5    0.07       0
  5014.6    0.12       0  6158.6    0.05       0
Bank Sta=5009.5,5014.6
Exp/Cntr=0.3,0.1

Chan Stop Cuts=-1