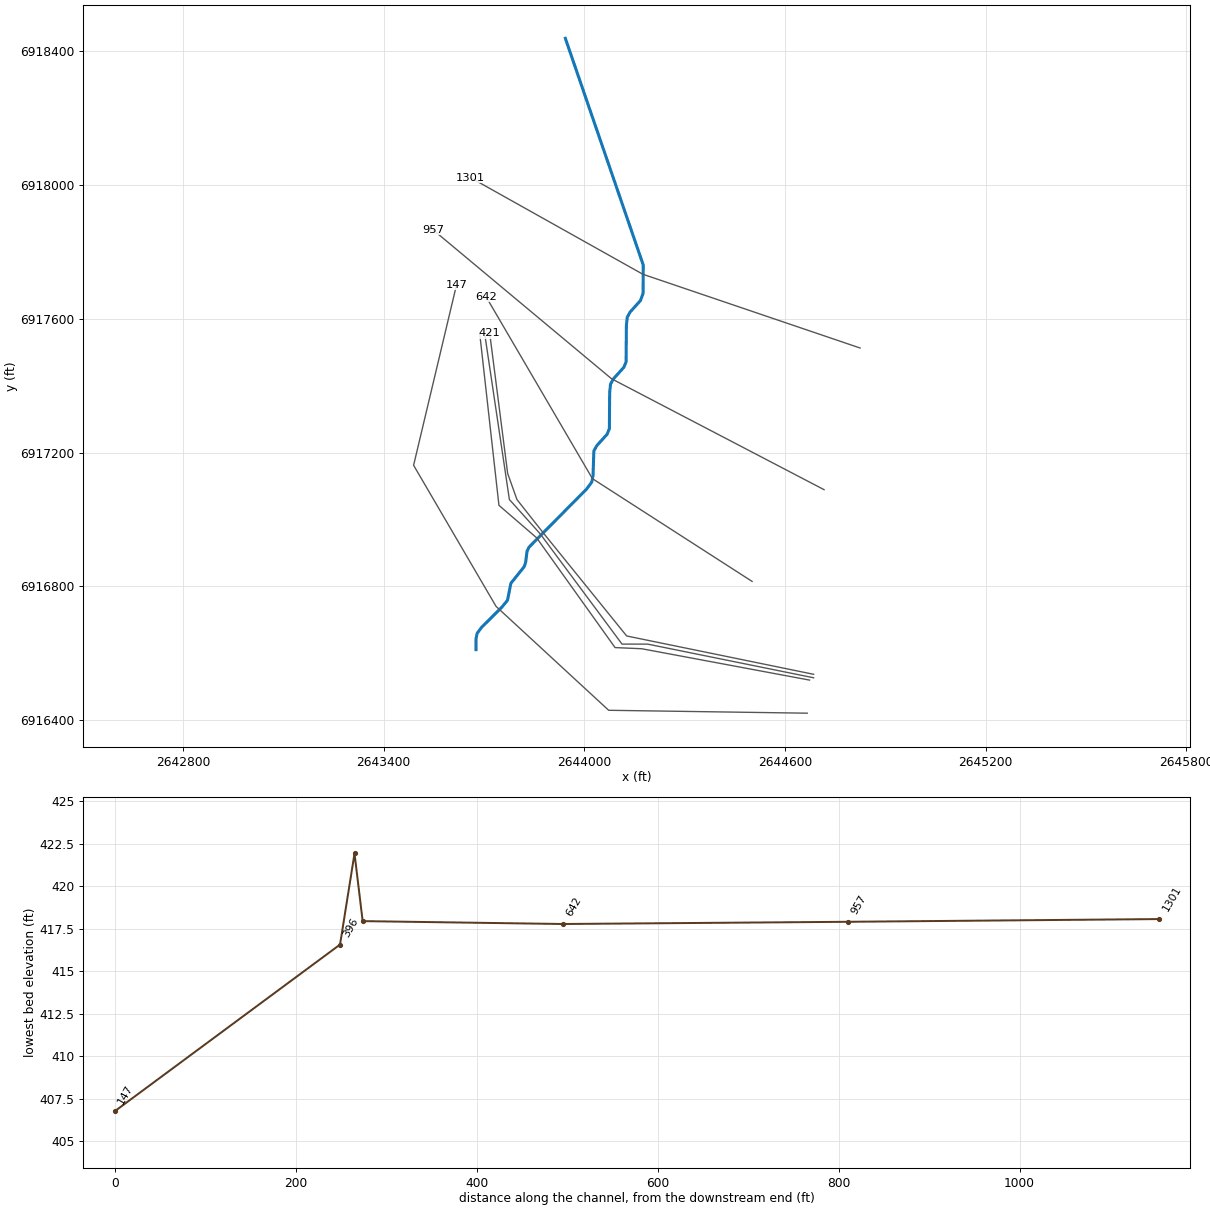
--- Kings Creek Trib 15_1.prj (project) ---

Proj Title=Kings Creek Trib 15_1 Base Level Engineering
Current Plan=p01
Default Exp/Contr=0.3,0.1
English Units
Geom File=g01
Flow File=f01
Plan File=p01
BEGIN DESCRIPTION:
Kings Creek Trib 15_1
END DESCRIPTION:

--- Kings Creek Trib 15_1.p01 (plan) ---

Plan Title=Multiple Run
Short Identifier=Multiple
Geom File=g01
Flow File=f01
Subcritical Flow
K Sum by GR= 0
Std Step Tol= 0.01
Critical Tol= 0.01
Num of Std Step Trials= 20
Max Error Tol= 0.3
Flow Tol Ratio= 0.001
Split Flow NTrial= 30
Split Flow Tol= 0.02
Split Flow Ratio= 0.02
Log Output Level= 0
Friction Slope Method= 1
Unsteady Friction Slope Method= 2
Unsteady Bridges Friction Slope Method= 1
Parabolic Critical Depth
Global Vel Dist=  1 , 1 , 1
Global Log Level= 0
CheckData=True
Encroach Param= -1, 0, 0, 0
BEGIN DESCRIPTION:
Multiple Run
END DESCRIPTION:

--- Kings Creek Trib 15_1.f01 (steady flow) ---

Flow Title=Multiple
Number of Profiles=7
Profile Names=10-year,25-year,50-year,1pct_min,100-year,1pct_plu,500-year
River Rch & RM= Kings Creek Trib,Reach-1,1301
     486     644     770     458     913    1822    1282
River Rch & RM= Kings Creek Trib,Reach-1,147
     510     680     817     486     971    1937    1371
Boundary for River Rch & Prof#=Kings Creek Trib,Reach-1,1
Up Type=0
Dn Type=3
Dn Slope=0.005
Boundary for River Rch & Prof#=Kings Creek Trib,Reach-1,2
Up Type=0
Dn Type=3
Dn Slope=0.005
Boundary for River Rch & Prof#=Kings Creek Trib,Reach-1,3
Up Type=0
Dn Type=3
Dn Slope=0.005
Boundary for River Rch & Prof#=Kings Creek Trib,Reach-1,4
Up Type=0
Dn Type=3
Dn Slope=0.005
Boundary for River Rch & Prof#=Kings Creek Trib,Reach-1,5
Up Type=0
Dn Type=3
Dn Slope=0.005
Boundary for River Rch & Prof#=Kings Creek Trib,Reach-1,6
Up Type=0
Dn Type=3
Dn Slope=0.005
Boundary for River Rch & Prof#=Kings Creek Trib,Reach-1,7
Up Type=0
Dn Type=3
Dn Slope=0.005

--- Kings Creek Trib 15_1.g01 (geometry) ---

Geom Title=Existing Conditions

River Reach=Kings Creek Trib,Reach-1
Reach XY= 30
      2643943.10      6918438.97      2644176.11      6917760.95
      2644175.54      6917676.19      2644167.87      6917654.94
      2644136.85      6917620.65      2644128.27      6917605.06
      2644125.68      6917581.13      2644124.77      6917471.51
      2644117.85      6917454.95      2644086.86      6917420.65
      2644078.27      6917405.06      2644075.68      6917381.13
      2644074.77      6917271.51      2644067.86      6917254.94
      2644036.90      6917220.63      2644028.36      6917205.02
      2644025.87      6917131.05      2644022.39      6917112.50
      2644006.37      6917090.84      2643834.14      6916917.06
      2643828.50      6916904.96      2643824.30      6916871.70
      2643819.90      6916858.81      2643780.19      6916809.27
      2643770.16      6916758.70      2643752.97      6916737.54
      2643692.62      6916677.69      2643679.29      6916659.64
      2643675.93      6916642.88      2643676.00      6916611.00

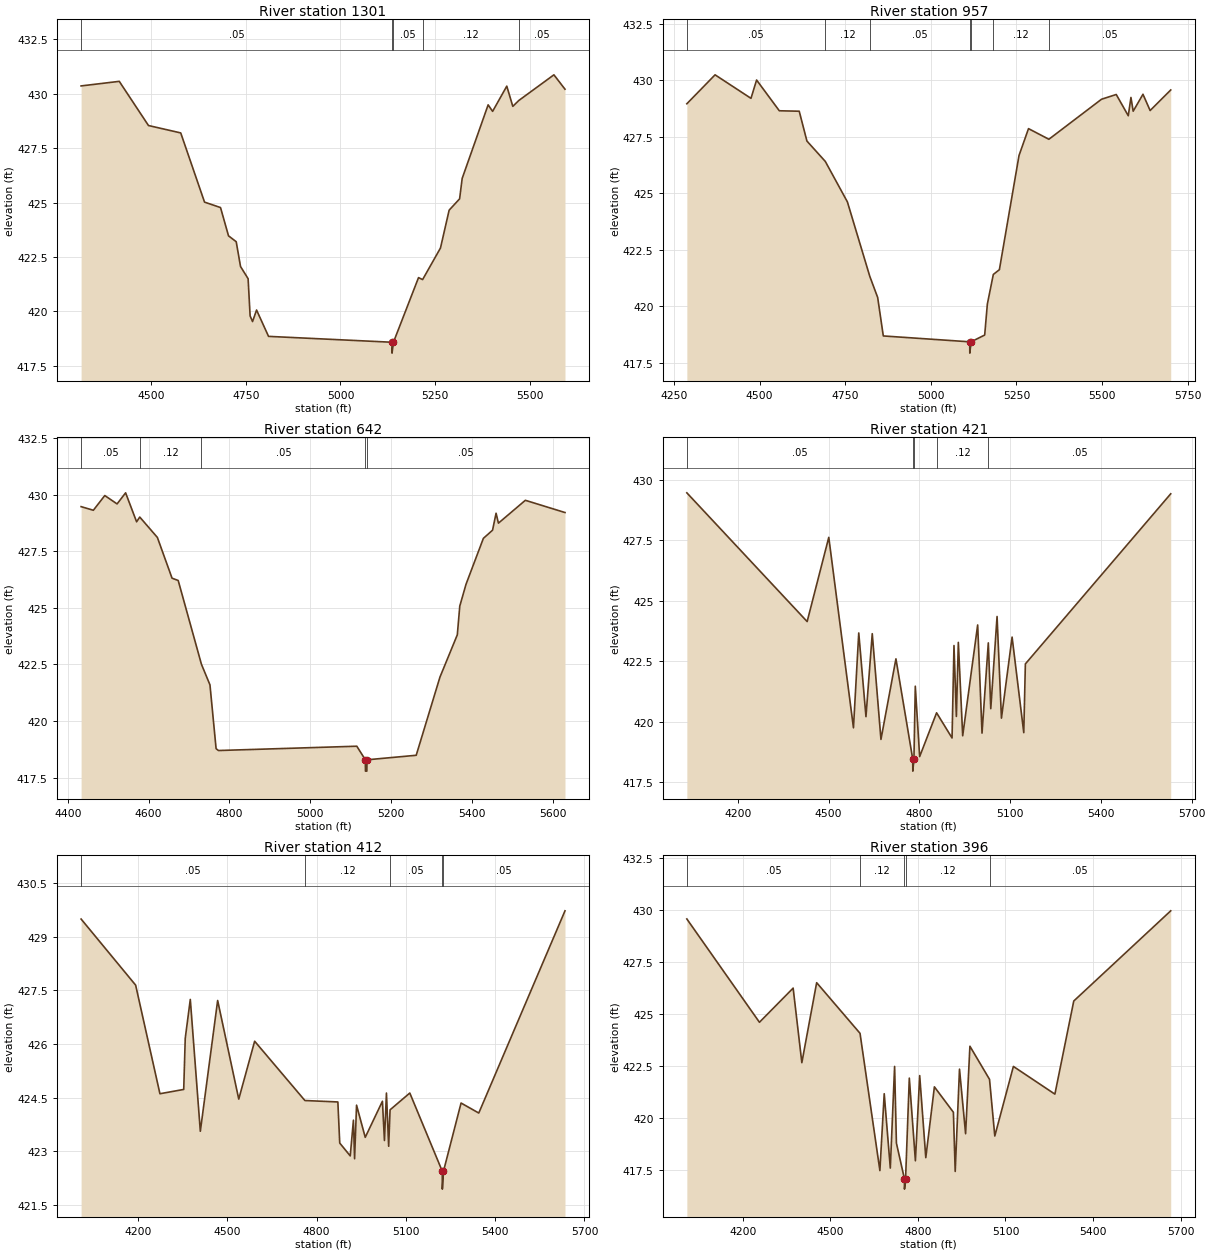
Type RM Length L Ch R = 1,1301,344,344,344
BEGIN DESCRIPTION:
Mapping XS d142eb9f
END DESCRIPTION:
XS GIS Cut Line= 3
      2644824.38      6917512.95      2644175.11      6917733.42
      2643659.35      6918022.45
#Sta/Elev= 30
  4315.6  430.36  4416.3  430.57  4493.4  428.54  4578.5  428.20  4641.3  425.02
  4683.5  424.77  4704.6  423.47  4724.9  423.20  4736.3  422.06  4756.3  421.50
  4761.6  419.79  4768.0  419.53  4778.6  420.06  4810.2  418.85  5135.8  418.58
  5136.1  418.08  5139.8  418.58  5206.0  421.55  5216.8  421.46  5263.9  422.91
  5286.8  424.65  5314.4  425.17  5321.2  426.11  5389.7  429.49  5401.5  429.19
  5438.9  430.35  5454.8  429.42  5470.6  429.69  5563.3  430.87  5592.5  430.21
#Mann=5,-1,0
  4315.6    0.05       0  5135.8    0.03       0  5139.8    0.05       0
  5216.8    0.12       0  5470.6    0.05       0
Bank Sta=5135.8,5139.8
Exp/Cntr=0.3,0.1

Type RM Length L Ch R = 1,957,315,315,315
BEGIN DESCRIPTION:
Mapping XS 6e25a9f8
END DESCRIPTION:
XS GIS Cut Line= 3
      2644716.76      6917089.33      2644081.36      6917420.92
      2643547.28      6917866.56
#Sta/Elev= 30
  4287.9  428.95  4370.3  430.23  4475.1  429.19  4491.5  430.00  4557.8  428.64
  4615.9  428.62  4638.4  427.30  4692.0  426.40  4756.5  424.61  4821.8  421.32
  4844.9  420.38  4861.3  418.68  5113.5  418.42  5113.8  417.92  5117.5  418.42
  5157.2  418.72  5165.0  420.09  5182.4  421.40  5200.1  421.61  5257.4  426.66
  5285.1  427.85  5344.6  427.38  5498.2  429.15  5541.2  429.36  5576.3  428.42
  5584.1  429.23  5590.6  428.62  5619.2  429.37  5640.1  428.65  5700.2  429.56
#Mann=7,-1,0
  4287.9    0.05       0  4692.0    0.12       0  4821.8    0.05       0
  5113.5    0.03       0  5117.5    0.05       0  5182.4    0.12       0
  5344.6    0.05       0
Bank Sta=5113.5,5117.5
Exp/Cntr=0.3,0.1

Type RM Length L Ch R = 1,642,221,221,221
BEGIN DESCRIPTION:
Mapping XS ba1fd810
END DESCRIPTION:
XS GIS Cut Line= 3
      2644501.49      6916815.02      2644024.07      6917122.31
      2643706.37      6917665.69
#Sta/Elev= 30
  4433.2  429.47  4463.5  429.31  4491.8  429.96  4522.2  429.59  4543.3  430.08
  4570.5  428.80  4578.3  429.01  4621.9  428.11  4658.2  426.31  4673.4  426.21
  4730.9  422.51  4752.0  421.60  4767.2  418.78  4773.1  418.70  5115.3  418.89
  5136.5  418.29  5136.7  417.79  5140.2  417.79  5140.5  418.29  5262.3  418.49
  5321.0  421.94  5364.0  423.81  5370.1  425.08  5385.5  426.04  5428.5  428.07
  5451.2  428.43  5459.9  429.18  5465.7  428.74  5532.3  429.75  5630.4  429.21
#Mann=5,-1,0
  4433.2    0.05       0  4578.3    0.12       0  4730.9    0.05       0
  5136.5    0.03       0  5140.5    0.05       0
Bank Sta=5136.5,5140.5
Exp/Cntr=0.3,0.1

Type RM Length L Ch R = 1,421,9,9,9
BEGIN DESCRIPTION:
Mapping XS 4c3b6f09
END DESCRIPTION:
XS GIS Cut Line= 6
      2644685.50      6916537.24      2644126.50      6916651.82
      2643876.50      6916960.85      2643798.37      6917059.81
      2643770.60      6917137.93      2643716.92      6917556.99
#Sta/Elev= 30
  4031.2  429.46  4428.9  424.14  4500.4  427.62  4582.0  419.75  4599.5  423.67
  4623.3  420.21  4644.1  423.64  4672.9  419.27  4722.4  422.60  4777.9  418.46
  4778.2  417.96  4781.9  418.46  4786.4  421.47  4800.8  418.56  4856.8  420.37
  4907.9  419.33  4914.3  423.15  4922.2  420.22  4928.7  423.28  4943.1  419.42
  4992.6  424.00  5007.0  419.53  5027.8  423.26  5035.9  420.54  5056.7  424.35
  5071.2  420.15  5106.4  423.50  5145.0  419.55  5150.3  422.39  5630.8  429.42
#Mann=5,-1,0
  4031.2    0.05       0  4777.9    0.07       0  4781.9    0.05       0
  4856.8    0.12       0  5027.8    0.05       0
Bank Sta=4777.9,4781.9
Exp/Cntr=0.3,0.1

Type RM Length L Ch R = 1,412,16,16,16
BEGIN DESCRIPTION:
Mapping XS 4e3ff989
END DESCRIPTION:
XS GIS Cut Line= 6
      2644685.53      6916526.82      2644189.00      6916627.52
      2644112.61      6916627.52      2643867.82      6916957.38
      2643775.80      6917059.81      2643703.13      6917547.69
#Sta/Elev= 30
  4009.1  429.50  4192.3  427.65  4273.9  424.61  4353.8  424.73  4358.9  426.16
  4375.9  427.25  4409.6  423.56  4467.8  427.22  4538.7  424.46  4592.1  426.08
  4760.9  424.42  4871.6  424.38  4877.9  423.23  4913.2  422.87  4923.9  423.87
  4927.8  422.79  4934.4  424.29  4963.6  423.39  5021.3  424.40  5028.1  423.30
  5034.8  424.63  5042.3  423.14  5047.0  424.16  5113.3  424.63  5222.4  422.44
  5222.6  421.94  5226.4  422.44  5285.5  424.35  5345.0  424.07  5634.6  429.73
#Mann=5,-1,0
  4009.1    0.05       0  4760.9    0.12       0  5047.0    0.05       0
  5222.4    0.07       0  5226.4    0.05       0
Bank Sta=5222.4,5226.4
Exp/Cntr=0.3,0.1

Type RM Length L Ch R = 1,396,249,249,249
BEGIN DESCRIPTION:
Mapping XS 3f9a4265
END DESCRIPTION:
XS GIS Cut Line= 6
      2644673.37      6916519.88      2644171.64      6916613.63
      2644091.78      6916617.10      2643857.40      6916945.22
      2643744.55      6917042.45      2643687.26      6917554.60
#Sta/Elev= 30
  4008.1  429.55  4256.9  424.59  4372.4  426.23  4402.2  422.65  4453.0  426.49
  4601.6  424.06  4669.7  417.47  4684.5  421.16  4705.4  417.59  4720.1  422.47
  4726.3  418.79  4753.7  417.08  4754.0  416.58  4757.7  417.08  4770.5  421.91
  4791.4  417.94  4806.1  422.03  4827.0  418.09  4856.5  421.49  4921.6  420.27
  4927.8  417.43  4942.5  422.34  4963.4  419.24  4978.2  423.44  5045.4  421.85
  5063.5  419.13  5127.2  422.47  5269.4  421.14  5334.1  425.61  5666.4  429.94
#Mann=5,-1,0
  4008.1    0.05       0  4601.6    0.12       0  4753.7    0.07       0
  4757.7    0.12       0  5045.4    0.05       0
Bank Sta=4753.7,4757.7
Exp/Cntr=0.3,0.1

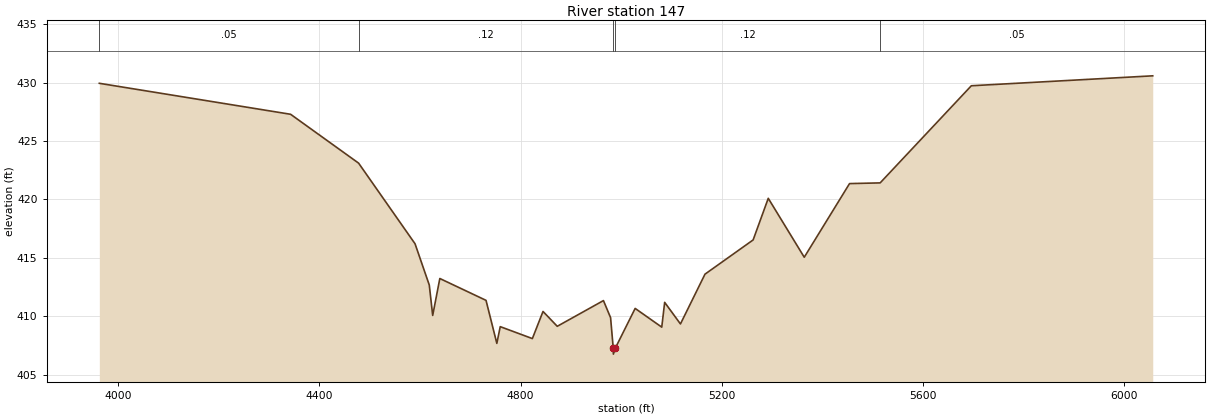
Type RM Length L Ch R = 1,147,0,0,0
BEGIN DESCRIPTION:
Mapping XS 27524759
END DESCRIPTION:
XS GIS Cut Line= 5
      2644666.46      6916420.92      2644072.68      6916429.60
      2643735.87      6916740.36      2643489.35      6917162.24
      2643617.81      6917702.13
#Sta/Elev= 30
  3962.0  429.94  4342.5  427.29  4477.8  423.11  4590.1  416.21  4618.4  412.68
  4625.2  410.08  4639.4  413.24  4731.3  411.37  4752.8  407.69  4759.6  409.12
  4823.5  408.10  4844.7  410.42  4873.0  409.15  4964.9  411.35  4979.1  409.89
  4984.4  407.27  4984.7  406.77  4988.4  407.27  5028.0  410.68  5080.9  409.08
  5086.7  411.20  5118.1  409.35  5166.9  413.61  5262.7  416.54  5292.8  420.10
  5364.4  415.06  5454.5  421.36  5515.4  421.42  5696.8  429.73  6057.7  430.58
#Mann=5,-1,0
  3962.0    0.05       0  4477.8    0.12       0  4984.4    0.07       0
  4988.4    0.12       0  5515.4    0.05       0
Bank Sta=4984.4,4988.4
Exp/Cntr=0.3,0.1

Chan Stop Cuts=-1