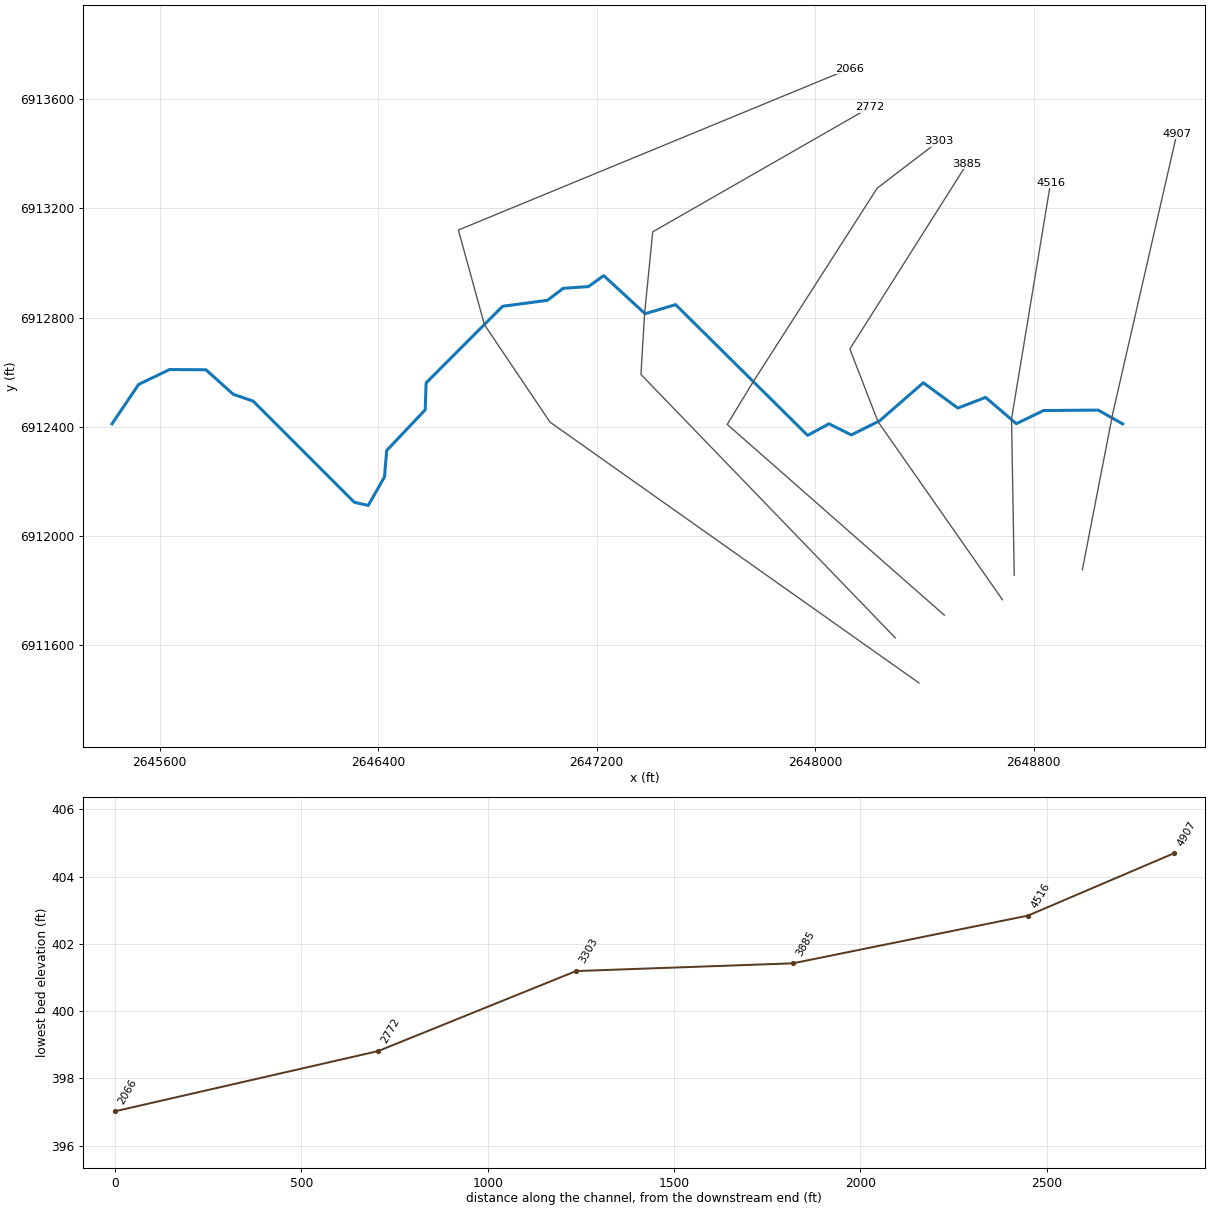
--- Kings Creek Trib 16.prj (project) ---

Proj Title=Kings Creek Trib 16 Base Level Engineering
Current Plan=p01
Default Exp/Contr=0.3,0.1
English Units
Geom File=g01
Flow File=f01
Plan File=p01
Y Axis Title=Elevation
X Axis Title(PF)=Main Channel Distance
X Axis Title(XS)=Station
BEGIN DESCRIPTION:
Kings Creek Trib 16
END DESCRIPTION:
DSS Export Rating Curves= 0
DSS Export Rating Curve Sorted= 0
DSS Export Volume Flow Curves= 0
DXF OffsetX= 0
DXF OffsetY= 0
DXF ScaleX= 1
DXF ScaleY= 10

--- Kings Creek Trib 16.p01 (plan) ---

Plan Title=Multiple Run
Short Identifier=Multiple
Geom File=g01
Flow File=f01
Subcritical Flow
K Sum by GR= 0
Std Step Tol= 0.01
Critical Tol= 0.01
Num of Std Step Trials= 20
Max Error Tol= 0.3
Flow Tol Ratio= 0.001
Split Flow NTrial= 30
Split Flow Tol= 0.02
Split Flow Ratio= 0.02
Log Output Level= 0
Friction Slope Method= 1
Unsteady Friction Slope Method= 2
Unsteady Bridges Friction Slope Method= 1
Parabolic Critical Depth
Global Vel Dist=  1 , 1 , 1
Global Log Level= 0
CheckData=True
Encroach Param= -1, 0, 0, 0
BEGIN DESCRIPTION:
Multiple Run
END DESCRIPTION:

--- Kings Creek Trib 16.f01 (steady flow) ---

Flow Title=Multiple
Number of Profiles=7
Profile Names=10-year,25-year,50-year,1pct_min,100-year,1pct_plu,500-year
River Rch & RM= Kings Creek Trib,Reach-1,4907
     394     516     612     360     719    1435     992
River Rch & RM= Kings Creek Trib,Reach-1,3303
     816    1118    1366     827    1650    3293    2409
Boundary for River Rch & Prof#=Kings Creek Trib,Reach-1,1
Up Type=0
Dn Type=3
Dn Slope=0.005
Boundary for River Rch & Prof#=Kings Creek Trib,Reach-1,2
Up Type=0
Dn Type=3
Dn Slope=0.005
Boundary for River Rch & Prof#=Kings Creek Trib,Reach-1,3
Up Type=0
Dn Type=3
Dn Slope=0.005
Boundary for River Rch & Prof#=Kings Creek Trib,Reach-1,4
Up Type=0
Dn Type=3
Dn Slope=0.005
Boundary for River Rch & Prof#=Kings Creek Trib,Reach-1,5
Up Type=0
Dn Type=3
Dn Slope=0.005
Boundary for River Rch & Prof#=Kings Creek Trib,Reach-1,6
Up Type=0
Dn Type=3
Dn Slope=0.005
Boundary for River Rch & Prof#=Kings Creek Trib,Reach-1,7
Up Type=0
Dn Type=3
Dn Slope=0.005

--- Kings Creek Trib 16.g01 (geometry) ---

Geom Title=Existing Conditions
Program Version=4.10

River Reach=Kings Creek Trib,Reach-1
Reach XY= 30
        2649126.        6912411.      2649036.17      6912461.42
       2648836.5      6912459.76      2648736.62      6912411.61
      2648624.35      6912507.83       2648522.6      6912468.84
      2648396.16      6912561.47      2648235.68      6912421.75
      2648132.61      6912370.43        2648051.      6912411.22
      2647972.59      6912368.82      2647489.38      6912847.46
      2647377.65      6912814.16       2647226.1      6912953.69
      2647170.11      6912913.56       2647077.6      6912907.15
      2647020.06      6912863.27      2646855.84      6912841.39
        2646576.        6912561.      2646572.62       6912462.4
      2646431.52      6912313.43      2646423.68      6912216.94
      2646363.99      6912112.12      2646313.02      6912124.01
      2645942.67      6912494.35      2645869.96      6912519.18
      2645770.14      6912608.95       2645636.5      6912609.81
      2645523.45      6912555.28        2645426.        6912411.

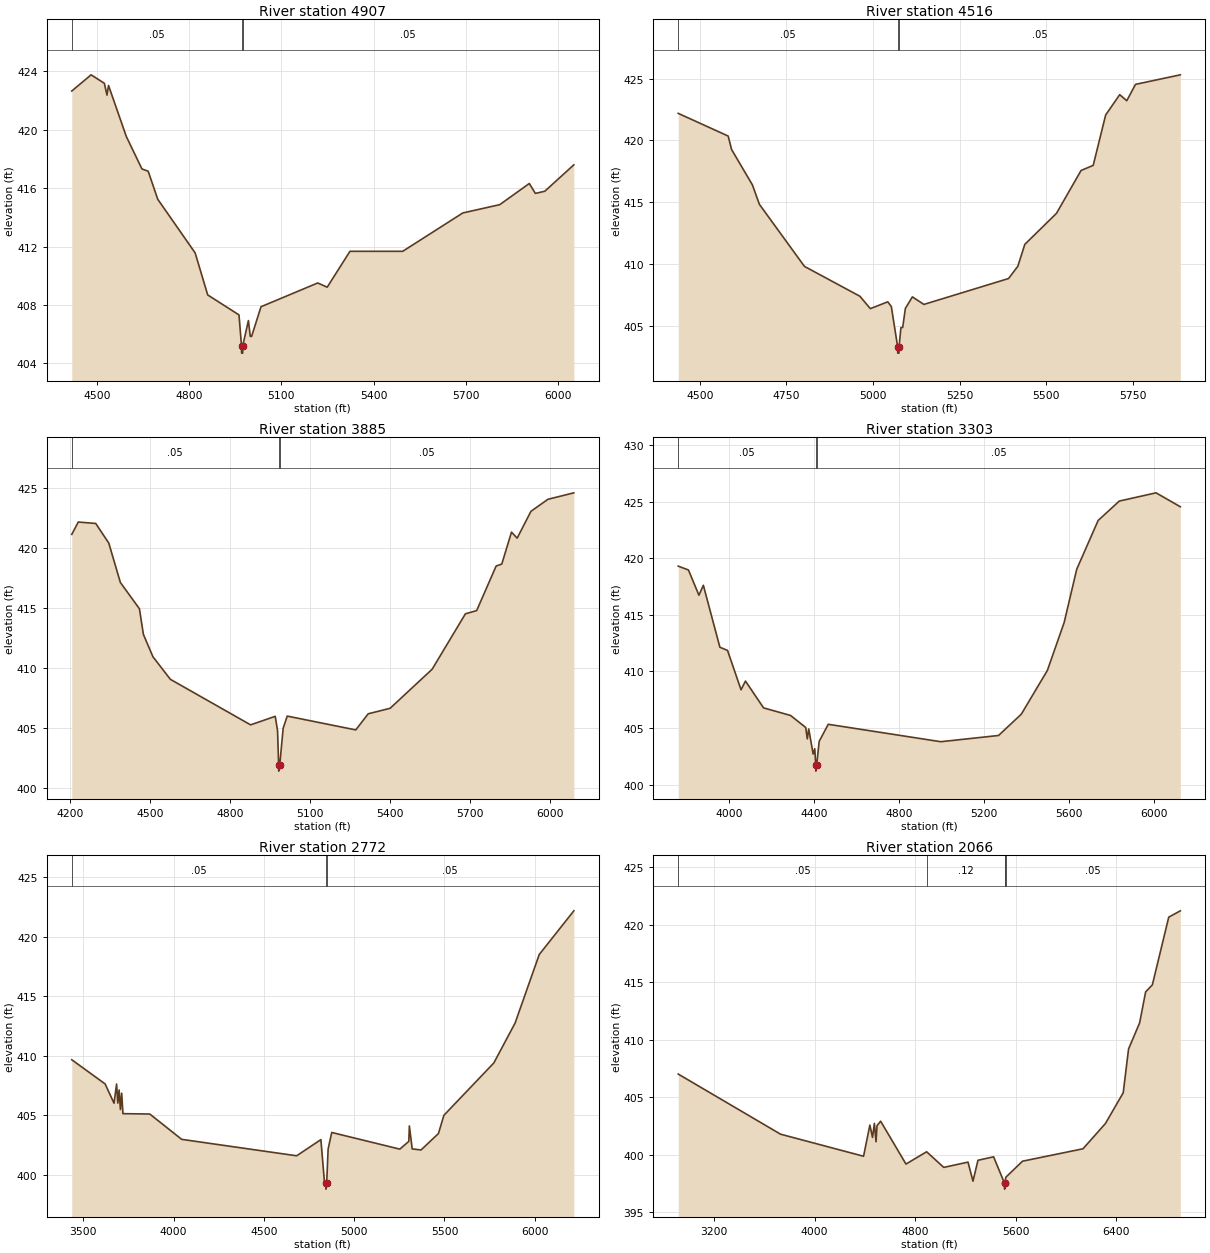
Type RM Length L Ch R = 1 ,4907    ,391,391,391
BEGIN DESCRIPTION:
Kings Creek Trib 16 9.0
END DESCRIPTION:
XS GIS Cut Line= 3
      2648978.48      6911876.97      2649089.51      6912448.08
       2649324.3      6913473.03
#Sta/Elev= 30
  4418.2  422.66  4481.1  423.77  4524.2  423.19  4532.7  422.38  4537.8  423.04
  4595.5  419.55  4646.4  417.32  4666.8  417.16  4697.9  415.24  4819.6  411.56
  4860.4  408.68  4962.2  407.31  4970.4  405.19  4970.7  404.69  4974.2  404.69
  4974.4  405.19  4992.8  406.92  4998.9  405.84  5003.3  405.84  5033.8  407.87
  5218.4   409.5  5249.2  409.21  5323.2  411.67  5494.8  411.67  5690.3   414.3
  5810.6  414.87  5906.6  416.32  5926.3  415.64  5957.1  415.79  6051.5   417.6
#Mann= 3 ,-1 , 0
  4418.2     .05       0  4970.4     .03       0  4974.4     .05       0
Bank Sta=4970.4,4974.4
XS Rating Curve= 0 ,0
Exp/Cntr=0.3,0.1

Type RM Length L Ch R = 1 ,4516    ,631,631,631
BEGIN DESCRIPTION:
Mapping XS 1fade23f
END DESCRIPTION:
XS GIS Cut Line= 3
       2648729.1      6911856.98      2648719.12      6912428.95
       2648862.1      6913293.45
#Sta/Elev= 30
  4437.9  422.19  4581.9  420.36  4591.9  419.27    4652  416.41    4672  414.85
    4802  409.84    4962  407.43    4992  406.43  5042.4  406.98  5052.6   406.6
  5070.9  403.34  5071.1  402.84  5074.6  402.84  5074.9  403.34  5080.3   404.9
  5085.4  404.91  5093.1  406.45  5113.4  407.38  5146.5  406.77  5390.7  408.86
  5417.5  409.85  5437.7  411.62    5529  414.12  5599.9  417.58  5634.9  417.99
  5670.9  422.06  5711.4   423.7  5731.7  423.21    5757  424.53  5886.2   425.3
#Mann= 3 ,-1 , 0
  4437.9     .05       0  5070.9     .07       0  5074.9     .05       0
Bank Sta=5070.9,5074.9
XS Rating Curve= 0 ,0
Exp/Cntr=0.3,0.1

Type RM Length L Ch R = 1 ,3885    ,582,582,582
BEGIN DESCRIPTION:
Mapping XS 73b2a3e4
END DESCRIPTION:
XS GIS Cut Line= 4
      2648685.88      6911767.22      2648230.32      6912418.97
      2648127.24      6912684.99      2648556.16      6913363.28
#Sta/Elev= 30
  4205.6  421.12    4230  422.15  4295.5  422.03  4344.4   420.4  4387.9  417.12
  4459.4  414.93  4474.2   412.8    4510  410.94  4575.4  409.06  4876.3  405.27
  4968.7  405.98  4977.4  404.78  4981.5  401.92  4981.8  401.42  4985.5  401.92
  4998.4  404.99  5013.7     406  5270.7  404.85  5317.3  406.19  5399.6  406.65
  5557.2   409.9  5681.9  414.51  5724.2  414.78  5797.2  418.49  5818.3  418.65
  5854.8  421.31    5876  420.81  5927.7  423.04  5991.3  424.04  6088.6  424.58
#Mann= 3 ,-1 , 0
  4205.6     .05       0  4981.5     .04       0  4985.5     .05       0
Bank Sta=4981.5,4985.5
XS Rating Curve= 0 ,0
Exp/Cntr=0.3,0.1

Type RM Length L Ch R = 1 ,3303    ,531,531,531
BEGIN DESCRIPTION:
Mapping XS be775da5
END DESCRIPTION:
XS GIS Cut Line= 5
      2648473.09      6911710.68      2647678.34        6912409.
      2647771.45      6912561.95        2648227.      6913273.54
      2648451.78      6913445.43
#Sta/Elev= 30
  3760.4  419.31  3808.5  418.97  3857.9  416.74  3878.7  417.62  3956.6  412.14
  3992.6  411.86  4056.2  408.38  4077.1  409.15  4162.4  406.78  4289.6  406.11
  4360.8  405.05  4368.3  404.04    4375  404.92  4395.9   402.7  4403.5  403.17
  4408.1  401.69  4408.4  401.19  4412.1  401.69  4424.3  403.82    4467  405.33
    4997  403.79  5269.1  404.34  5376.2  406.22  5499.1  410.09  5578.1  414.32
  5637.5  419.04  5738.4  423.35  5837.9  425.06    6011  425.79  6125.3  424.56
#Mann= 3 ,-1 , 0
  3760.4     .05       0  4408.1     .04       0  4412.1     .05       0
Bank Sta=4408.1,4412.1
XS Rating Curve= 0 ,0
Exp/Cntr=0.3,0.1

Type RM Length L Ch R = 1 ,2772    ,706,706,706
BEGIN DESCRIPTION:
Mapping XS 56fc2e23
END DESCRIPTION:
XS GIS Cut Line= 5
      2648293.49      6911627.59      2647362.45      6912591.88
      2647375.75      6912814.67      2647405.68      6913113.93
      2648200.43       6913569.5
#Sta/Elev= 30
    3436  409.68  3620.6  407.65    3670  406.03  3684.2  407.64  3691.1  406.04
  3698.3  407.14  3705.3   405.5  3712.5  406.87  3719.4  405.15  3868.1  405.12
  4044.8  402.99  4681.3  401.61  4815.6  402.97  4835.6  399.35  4843.6  399.31
  4843.9  398.81  4847.6  399.31  4855.7  402.18  4875.7  403.57  5252.7  402.17
  5302.4  402.82  5305.5  404.12  5321.3  402.19  5370.2   402.1  5466.6  403.48
  5496.7  405.01  5773.3  409.41    5891  412.76  6024.8  418.52  6216.4  422.19
#Mann= 3 ,-1 , 0
    3436     .05       0  4843.6     .04       0  4847.6     .05       0
Bank Sta=4843.6,4847.6
XS Rating Curve= 0 ,0
Exp/Cntr=0.3,0.1

Type RM Length L Ch R = 1 ,2066    ,0,0,0
BEGIN DESCRIPTION:
Kings Creek Trib 16 5.0
END DESCRIPTION:
XS GIS Cut Line= 5
      2648380.29      6911462.46      2647029.44      6912417.43
      2646789.32      6912774.36       2646694.1      6913120.58
      2648125.97      6913710.99
#Sta/Elev= 30
  2915.5  407.03    3729   401.8  4389.2  399.88  4439.3  402.59  4460.5  401.52
  4475.3  402.74  4488.3  401.14  4496.2  402.54    4525  402.93  4726.5   399.2
  4890.7  400.27  5026.9  398.91  5219.7  399.37  5259.3  397.71  5298.9  399.53
  5423.2  399.83  5510.6  397.52  5510.8  397.02  5514.6  397.52  5520.1  398.05
  5653.2  399.45  6134.3  400.53  6312.6  402.73  6453.9   405.4  6496.4  409.21
  6584.4  411.48  6632.3  414.18  6685.6  414.79    6816  420.68  6907.9  421.23
#Mann= 5 ,-1 , 0
  2915.5     .05       0  4890.7     .12       0  5510.6     .07       0
  5514.6     .12       0  5520.1     .05       0
Bank Sta=5510.6,5514.6
XS Rating Curve= 0 ,0
Exp/Cntr=0.3,0.1

Chan Stop Cuts=-1
Use User Specified Reach Order=0
Composite Channel Slope=5