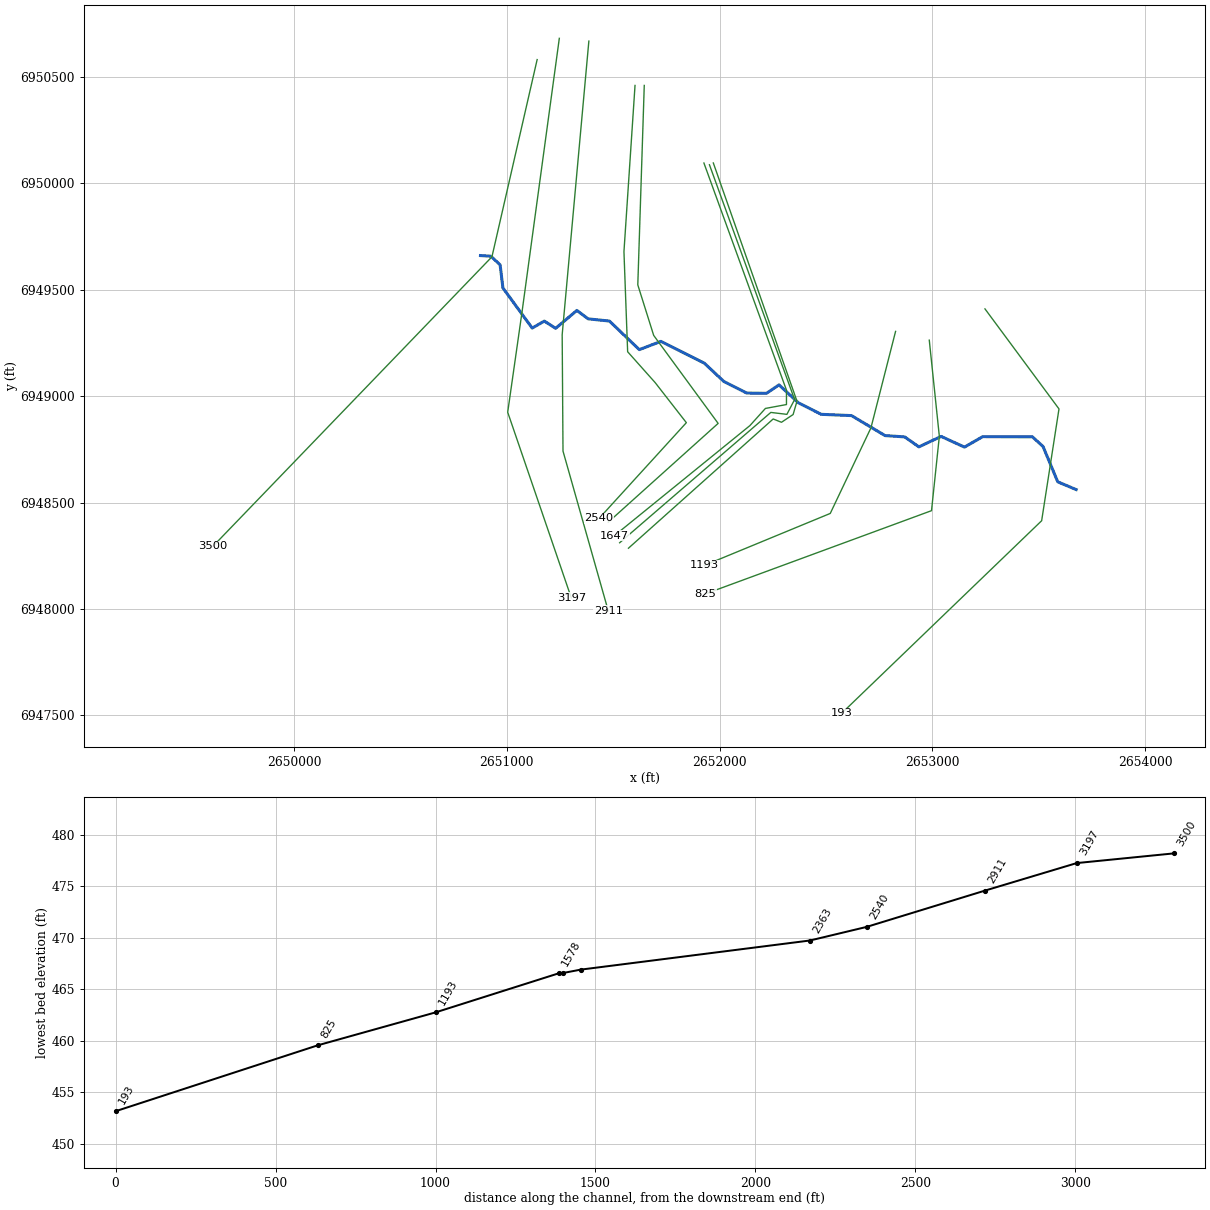
--- Kings Creek Trib 1_1.prj (project) ---

Proj Title=Kings Creek Trib 1_1 Base Level Engineering
Current Plan=p01
Default Exp/Contr=0.3,0.1
English Units
Geom File=g01
Flow File=f01
Plan File=p01
Y Axis Title=Elevation
X Axis Title(PF)=Main Channel Distance
X Axis Title(XS)=Station
BEGIN DESCRIPTION:
Kings Creek Trib 1_1
END DESCRIPTION:
DSS Export Rating Curves= 0
DSS Export Rating Curve Sorted= 0
DSS Export Volume Flow Curves= 0
DXF OffsetX= 0
DXF OffsetY= 0
DXF ScaleX= 1
DXF ScaleY= 10

--- Kings Creek Trib 1_1.p01 (plan) ---

Plan Title=Multiple Run
Short Identifier=Multiple
Geom File=g01
Flow File=f01
Subcritical Flow
K Sum by GR= 0
Std Step Tol= 0.01
Critical Tol= 0.01
Num of Std Step Trials= 20
Max Error Tol= 0.3
Flow Tol Ratio= 0.001
Split Flow NTrial= 30
Split Flow Tol= 0.02
Split Flow Ratio= 0.02
Log Output Level= 0
Friction Slope Method= 1
Unsteady Friction Slope Method= 2
Unsteady Bridges Friction Slope Method= 1
Parabolic Critical Depth
Global Vel Dist=  1 , 1 , 1
Global Log Level= 0
CheckData=True
Encroach Param= -1, 0, 0, 0
BEGIN DESCRIPTION:
Multiple Run
END DESCRIPTION:

--- Kings Creek Trib 1_1.f01 (steady flow) ---

Flow Title=Multiple
Number of Profiles=7
Profile Names=10-year,25-year,50-year,1pct_min,100-year,1pct_plu,500-year
River Rch & RM= Kings Creek Trib,Reach-1,3500
     320     413     485     283     566    1128     767
Boundary for River Rch & Prof#=Kings Creek Trib,Reach-1,1
Up Type=0
Dn Type=3
Dn Slope=0.005
Boundary for River Rch & Prof#=Kings Creek Trib,Reach-1,2
Up Type=0
Dn Type=3
Dn Slope=0.005
Boundary for River Rch & Prof#=Kings Creek Trib,Reach-1,3
Up Type=0
Dn Type=3
Dn Slope=0.005
Boundary for River Rch & Prof#=Kings Creek Trib,Reach-1,4
Up Type=0
Dn Type=3
Dn Slope=0.005
Boundary for River Rch & Prof#=Kings Creek Trib,Reach-1,5
Up Type=0
Dn Type=3
Dn Slope=0.005
Boundary for River Rch & Prof#=Kings Creek Trib,Reach-1,6
Up Type=0
Dn Type=3
Dn Slope=0.005
Boundary for River Rch & Prof#=Kings Creek Trib,Reach-1,7
Up Type=0
Dn Type=3
Dn Slope=0.005

--- Kings Creek Trib 1_1.g01 (geometry) ---

Geom Title=Existing Conditions
Program Version=4.10

River Reach=Kings Creek Trib,Reach-1
Reach XY= 30
        2650876.        6949661.      2650925.01      6949657.88
      2650968.36      6949617.44      2650981.54      6949508.58
      2651119.05      6949320.17      2651175.99      6949352.94
      2651229.33      6949319.01      2651329.22      6949403.11
      2651381.89      6949363.56      2651482.17      6949353.14
      2651622.59      6949218.82      2651724.26      6949257.63
      2651928.29      6949155.15      2652019.95      6949069.16
      2652127.59      6949014.68      2652220.11      6949013.37
      2652279.41      6949053.19      2652369.94      6948969.18
      2652477.56      6948914.76      2652620.07      6948908.75
      2652777.58      6948814.83      2652870.03      6948808.62
      2652936.69      6948761.77      2653041.39      6948810.89
        2653151.      6948760.61       2653236.5      6948809.76
      2653470.33      6948809.02      2653520.29      6948763.58
      2653589.37      6948597.45        2653676.        6948561.

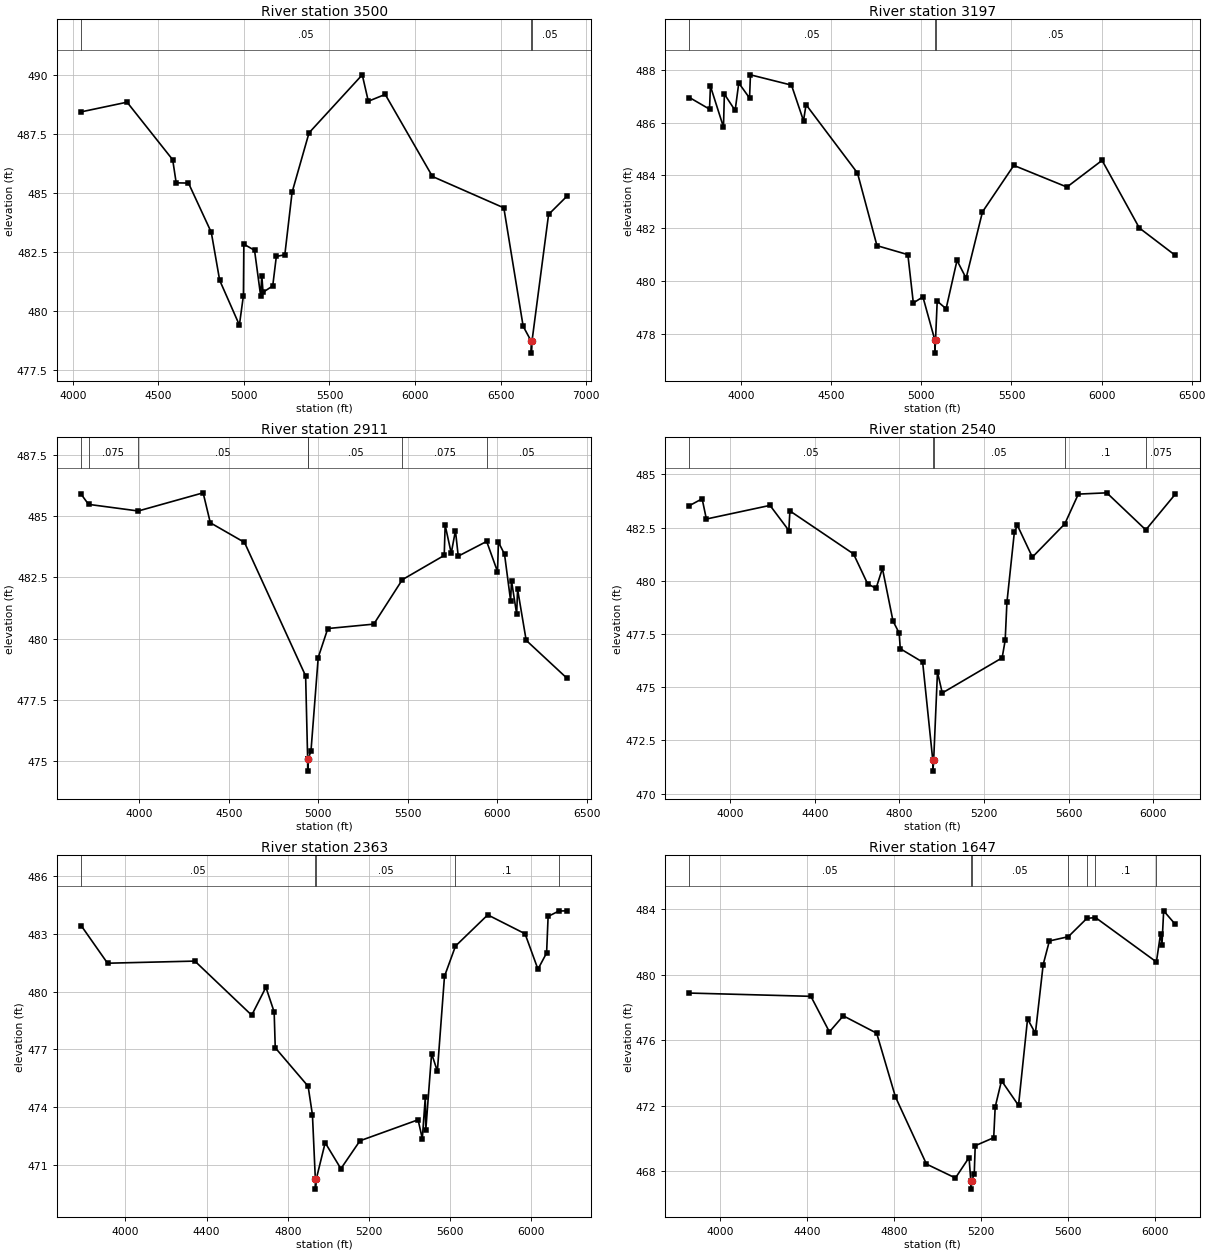
Type RM Length L Ch R = 1 ,3500    ,303,303,303
BEGIN DESCRIPTION:
Kings Creek Trib 1_1 7.0
END DESCRIPTION:
XS GIS Cut Line= 3
      2651142.41      6950582.18      2650929.94      6949655.22
      2649618.99      6948294.89
#Sta/Elev= 30
    4049  488.44    4317  488.85  4583.7  486.41  4604.2  485.43    4676  485.42
  4809.4  483.33  4858.3   481.3  4973.6   479.4  4997.2  480.65  4999.6  482.83
  5062.2  482.57  5097.7  480.65  5104.7  481.49  5111.9  480.79  5168.5  481.06
  5189.6  482.31  5239.2  482.38  5281.7  485.03  5380.7  487.55  5691.8  490.01
  5727.3  488.89    5826  489.18  6102.1   485.7  6519.4  484.37  6632.3  479.35
  6679.9  478.71  6680.2  478.21  6683.9  478.71    6781  484.09  6889.2  484.87
#Mann= 3 ,-1 , 0
    4049     .05       0  6679.9     .05       0  6683.9     .05       0
Bank Sta=6679.9,6683.9
XS Rating Curve= 0 ,0
Exp/Cntr=0.3,0.1

Type RM Length L Ch R = 1 ,3197    ,286,286,286
BEGIN DESCRIPTION:
Mapping XS 9fd11caa
END DESCRIPTION:
XS GIS Cut Line= 4
      2651246.59      6950682.05      2651072.01      6949400.61
      2651003.99      6948924.59        2651303.      6948051.83
#Sta/Elev= 30
  3712.9  486.95  3824.1  486.51  3829.2  487.38  3901.6  485.83  3906.6  487.08
  3966.3  486.46  3986.5   487.5  4046.3  486.93  4051.3  487.81  4279.1  487.42
  4345.8  486.07  4359.9  486.68  4645.4  484.09  4753.5  481.34    4925     481
  4955.3  479.17  5008.5   479.4  5074.5  477.77  5074.7  477.27  5078.5  477.77
  5087.8  479.24  5137.1  478.95  5197.7  480.78  5248.2  480.11  5339.1  482.62
    5513  484.38  5807.9  483.56  6002.9  484.57  6209.6  482.01  6409.6  480.97
#Mann= 3 ,-1 , 0
  3712.9     .05       0  5074.5     .03       0  5078.5     .05       0
Bank Sta=5074.5,5078.5
XS Rating Curve= 0 ,0
Exp/Cntr=0.3,0.1

Type RM Length L Ch R = 1 ,2911    ,371,371,371
BEGIN DESCRIPTION:
Kings Creek Trib 1_1 6.0
END DESCRIPTION:
XS GIS Cut Line= 4
      2651385.47      6950668.97      2651260.06      6949289.18
      2651263.94      6948741.93      2651476.61       6947991.1
#Sta/Elev= 30
  3675.8  485.88  3716.6  485.47  3994.2   485.2  4356.6  485.94  4396.7  484.72
  4587.5  483.92  4928.9  478.48  4940.2   475.1  4940.5   474.6  4944.2   475.1
    4959  475.44  4999.2  479.23  5052.7  480.41  5309.5  480.59  5468.8   482.4
  5702.8  483.39    5708  484.62    5742  483.48  5765.4   484.4  5781.1  483.36
  5939.8  483.96  6000.3  482.73  6005.5  483.93  6039.5  483.44  6073.4  481.55
  6078.6  482.35  6107.3     481  6112.5  482.01  6160.4  479.93  6388.9  478.38
#Mann= 7 ,-1 , 0
  3675.8     .05       0  3716.6    .075       0  3994.2     .05       0
  4940.2     .05       0  4944.2     .05       0  5468.8    .075       0
  5939.8     .05       0
Bank Sta=4940.2,4944.2
XS Rating Curve= 0 ,0
Exp/Cntr=0.3,0.1

Type RM Length L Ch R = 1 ,2540    ,177,177,177
BEGIN DESCRIPTION:
Mapping XS c0fe9cc0
END DESCRIPTION:
XS GIS Cut Line= 6
      2651602.48      6950460.66       2651550.4      6949679.43
      2651567.79      6949208.88       2651696.7      6949064.35
      2651843.76       6948875.5      2651433.65      6948425.57
#Sta/Elev= 30
    3808  483.53  3867.8  483.85  3887.8   482.9  4188.5  483.54  4277.5  482.36
  4282.5  483.28  4583.2  481.26  4649.5  479.86  4689.5  479.64  4719.6  480.58
  4769.6  478.11  4798.9  477.54  4803.9  476.81  4909.7  476.18  4957.7  471.56
    4958  471.06  4961.7  471.56  4979.7  475.71  5002.4  474.73  5285.2  476.38
  5299.6   477.2  5307.8  478.98  5343.1  482.29  5357.5   482.6  5428.1  481.11
  5581.2  482.67  5645.3  484.07  5779.7  484.13    5964  482.39  6103.7  484.07
#Mann= 5 ,-1 , 0
    3808     .05       0  4957.7     .04       0  4961.7     .05       0
  5581.2      .1       0    5964    .075       0
Bank Sta=4957.7,4961.7
XS Rating Curve= 0 ,0
Exp/Cntr=0.3,0.1

Type RM Length L Ch R = 1 ,2363    ,716,716,716
BEGIN DESCRIPTION:
Mapping XS 9107ef15
END DESCRIPTION:
XS GIS Cut Line= 5
      2651645.89      6950460.67      2651615.51      6949523.18
      2651690.19       6949285.7      2651993.11      6948872.14
      2651476.65      6948407.76
#Sta/Elev= 30
  3782.5  483.42  3912.2  481.47  4342.5  481.58  4622.6  478.77  4692.6  480.22
  4733.2  478.94  4738.6  477.08  4900.6  475.08  4921.9  473.59  4936.2  470.24
  4936.5  469.74  4940.2  470.24  4984.6  472.15    5062   470.8    5156  472.25
  5442.4  473.34  5463.2  472.36  5477.9  474.51  5480.3   472.8    5509  476.78
  5537.4  475.86  5572.5  480.79  5626.7  482.36  5785.6  483.98  5969.4     483
    6033  481.16  6075.6     482  6083.1   483.9  6136.1  484.18  6176.6  484.19
#Mann= 5 ,-1 , 0
  3782.5     .05       0  4936.2     .04       0  4940.2     .05       0
  5626.7      .1       0  6136.1    .075       0
Bank Sta=4936.2,4940.2
XS Rating Curve= 0 ,0
Exp/Cntr=0.3,0.1

Type RM Length L Ch R = 1 ,1647    ,54,54,54
BEGIN DESCRIPTION:
Mapping XS 5b9fc54f
END DESCRIPTION:
XS GIS Cut Line= 6
      2651926.28      6950096.06      2652314.29      6949028.39
      2652314.29      6948960.68      2652215.33      6948942.45
      2652142.42      6948861.72      2651505.98      6948344.77
#Sta/Elev= 30
  3858.9  478.88  4417.7  478.68  4502.9  476.51  4566.7  477.49  4720.4  476.43
  4806.8  472.54  4949.5  468.44  5082.8  467.59  5145.6  468.84  5153.6  467.41
  5153.9  466.91  5157.6  467.41  5169.5  467.85  5173.9  469.56    5259  470.05
  5265.8  471.92  5294.9  473.53  5373.2  472.02  5414.8   477.3  5450.8  476.42
  5486.7  480.62  5515.2  482.06  5602.3  482.32  5687.8  483.44  5727.4  483.49
  6007.7  480.78  6026.9   482.5  6033.3  481.83  6041.2   483.9    6095  483.07
#Mann= 7 ,-1 , 0
  3858.9     .05       0  5153.6     .03       0  5157.6     .05       0
  5602.3      .1       0  5687.8     .05       0  5727.4      .1       0
  6007.7     .05       0
Bank Sta=5153.6,5157.6
XS Rating Curve= 0 ,0
Exp/Cntr=0.3,0.1

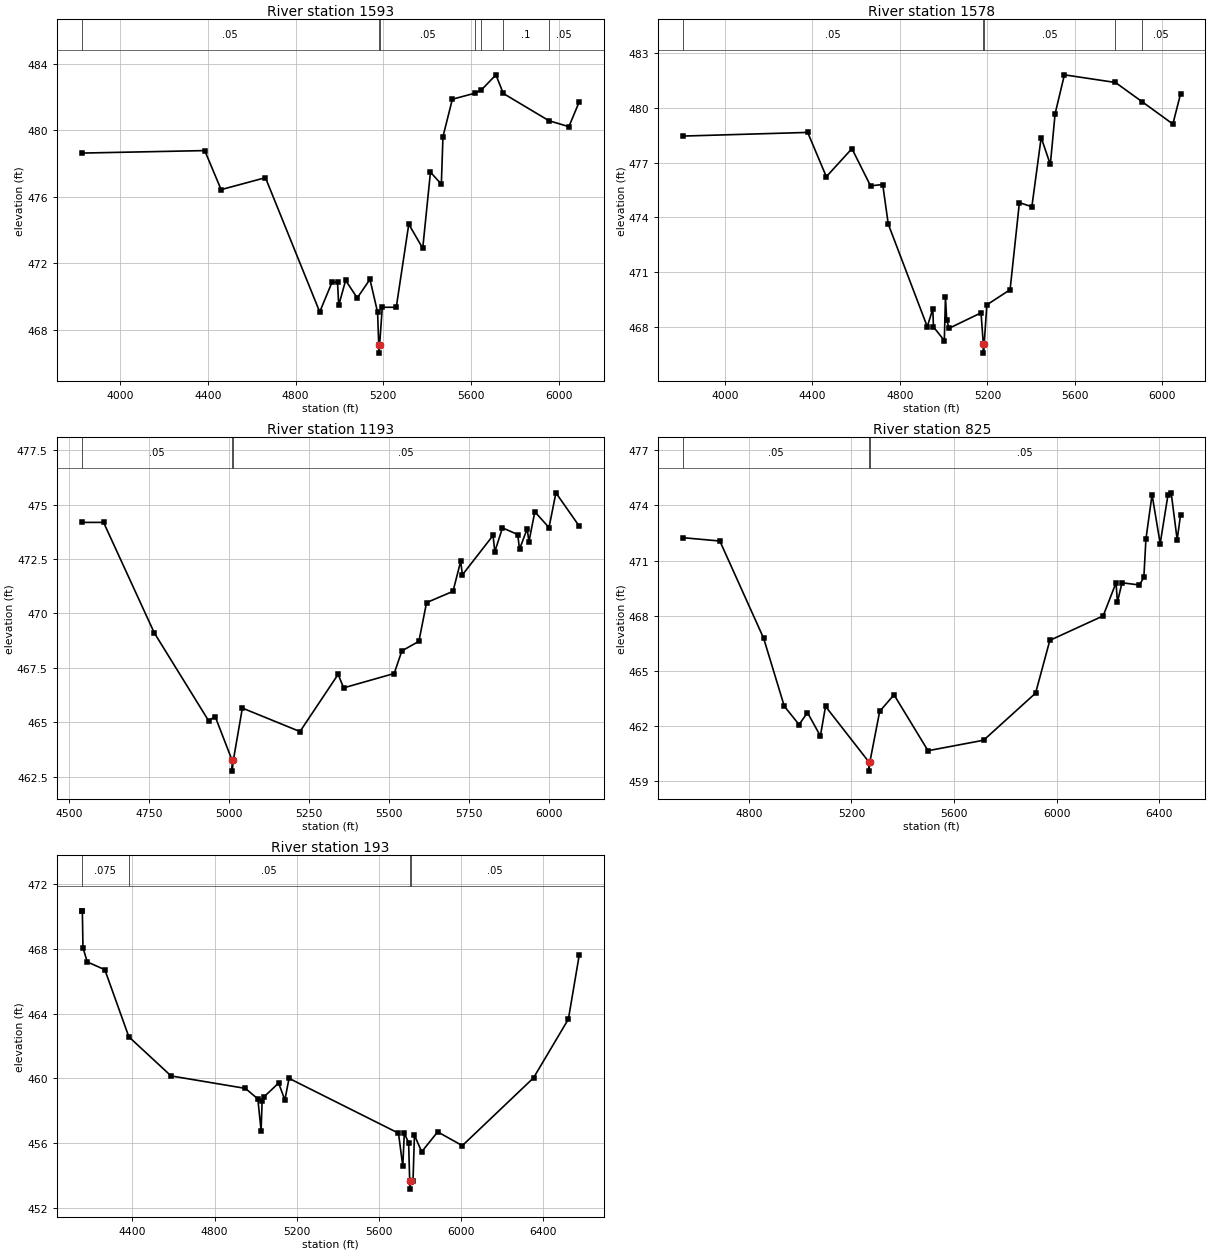
Type RM Length L Ch R = 1 ,1593    ,15,15,15
BEGIN DESCRIPTION:
Kings Creek Trib 1_1 3.0
END DESCRIPTION:
XS GIS Cut Line= 5
       2651952.3      6950087.79      2652352.53      6948984.12
      2652316.24      6948914.58      2652240.72       6948923.7
      2651530.26      6948311.11
#Sta/Elev= 30
    3826  478.63  4386.4  478.78  4460.8  476.43  4662.9  477.15  4910.2  469.07
  4966.1  470.85  4991.4  470.85  4996.7  469.46  5028.3  470.97  5081.1  469.91
  5139.1  471.03  5173.9  469.05  5179.1  467.09  5179.3  466.59  5183.1  467.09
  5195.3  469.35    5259  469.35    5316  474.35  5379.6   472.9  5414.8  477.48
  5464.4  476.76  5471.8  479.62  5514.6  481.87  5618.5  482.24  5646.2  482.42
  5713.1  483.34  5746.6  482.22  5954.5  480.58  6045.6  480.22  6092.6  481.71
#Mann= 7 ,-1 , 0
    3826     .05       0  5179.1     .06       0  5183.1     .05       0
  5618.5      .1       0  5646.2     .05       0  5746.6      .1       0
  5954.5     .05       0
Bank Sta=5179.1,5183.1
XS Rating Curve= 0 ,0
Exp/Cntr=0.3,0.1

Type RM Length L Ch R = 1 ,1578    ,385,385,385
BEGIN DESCRIPTION:
Mapping XS 35e335d1
END DESCRIPTION:
XS GIS Cut Line= 6
      2651970.52      6950096.14      2652363.77       6948976.3
      2652345.54       6948913.8      2652290.85      6948877.34
      2652251.79      6948892.97      2651571.63       6948285.5
#Sta/Elev= 30
  3809.3  478.46  4378.6  478.66  4463.8  476.23  4580.8  477.77  4665.9  475.73
  4721.6   475.8  4746.9  473.63  4925.2     468  4950.5  468.98  4953.4  467.99
  5003.1  467.24  5008.3  469.64  5013.9  468.39  5024.3  467.91  5170.9  468.76
  5181.3  467.05  5181.6  466.55  5185.3  467.05  5197.5   469.2  5303.7  470.03
  5346.3  474.81  5403.2  474.58  5445.8  478.38  5487.6   476.9  5509.4  479.68
    5552  481.82  5785.2   481.4  5906.5  480.35  6047.7  479.12  6082.8  480.77
#Mann= 5 ,-1 , 0
  3809.3     .05       0  5181.3     .03       0  5185.3     .05       0
  5785.2      .1       0  5906.5     .05       0
Bank Sta=5181.3,5185.3
XS Rating Curve= 0 ,0
Exp/Cntr=0.3,0.1

Type RM Length L Ch R = 1 ,1193    ,368,368,368
BEGIN DESCRIPTION:
Kings Creek Trib 1_1 2.0
END DESCRIPTION:
XS GIS Cut Line= 4
      2652827.16      6949304.52      2652711.37       6948851.1
      2652520.15      6948448.92      2651928.84      6948204.85
#Sta/Elev= 30
  4540.8  474.19  4608.8  474.19  4767.1  469.11  4936.6  465.07  4957.3  465.26
    5010  463.25  5010.3  462.75    5014  463.25  5042.1  465.65    5222  464.57
  5341.1   467.2  5358.3  466.58  5516.1  467.24  5540.1  468.28  5593.3  468.72
  5617.2   470.5  5699.8  471.02  5723.7   472.4  5729.2  471.78  5824.8  473.59
  5830.3  472.84  5854.2  473.94    5902  473.63  5907.4  472.95  5931.4   473.9
  5936.8   473.3  5955.3  474.68  5999.5  473.95  6021.1  475.55  6093.8  474.02
#Mann= 3 ,-1 , 0
  4540.8     .05       0    5010     .03       0    5014     .05       0
Bank Sta=5010,5014
XS Rating Curve= 0 ,0
Exp/Cntr=0.3,0.1

Type RM Length L Ch R = 1 ,825     ,632,632,632
BEGIN DESCRIPTION:
Mapping XS 9adec370
END DESCRIPTION:
XS GIS Cut Line= 4
      2652985.56      6949263.39      2653032.86      6948811.41
      2652996.07      6948461.89      2651931.71      6948070.31
#Sta/Elev= 30
  4543.4  472.24  4686.6  472.06  4857.5  466.77  4937.9  463.08  4995.5  462.08
  5028.4  462.73  5078.7  461.46  5098.8  463.07  5267.8  460.05    5268  459.55
  5271.8  460.05    5310   462.8  5365.9   463.7  5498.5  460.66  5715.4  461.23
    5918  463.79  5973.6  466.66  6181.6  467.99  6231.8  469.79  6237.2  468.74
  6255.1  469.79  6323.2  469.67  6340.3  470.09  6348.4  472.17  6372.3  474.58
    6404  471.92  6434.4  474.57  6446.9  474.68  6470.2  472.13  6483.4  473.48
#Mann= 3 ,-1 , 0
  4543.4     .05       0  5267.8     .04       0  5271.8     .05       0
Bank Sta=5267.8,5271.8
XS Rating Curve= 0 ,0
Exp/Cntr=0.3,0.1

Type RM Length L Ch R = 1 ,193     ,0,0,0
BEGIN DESCRIPTION:
Kings Creek Trib 1_1 1.0
END DESCRIPTION:
XS GIS Cut Line= 4
      2653247.33      6949410.41      2653595.25      6948940.18
      2653513.78      6948414.59      2652573.36       6947509.1
#Sta/Elev= 30
  4153.4  470.35  4156.1  470.35  4159.2  468.07  4180.1  467.19  4265.6  466.71
  4382.5  462.56  4588.1  460.14    4950  459.37  5010.7  458.72  5026.6  456.76
  5031.6  458.58  5041.1  458.85  5111.9   459.7  5142.3  458.65  5162.7  459.99
  5695.6   456.6  5716.7  454.55  5723.9   456.6    5745  456.01  5750.2  453.64
  5750.5  453.14  5754.2  453.64  5766.4  453.65  5773.3  456.48  5808.6  455.45
  5886.5  456.68  6006.6  455.83  6353.2  460.02    6523  463.65  6575.7   467.6
#Mann= 4 ,-1 , 0
  4153.4    .075       0  4382.5     .05       0  5750.2     .04       0
  5754.2     .05       0
Bank Sta=5750.2,5754.2
XS Rating Curve= 0 ,0
Exp/Cntr=0.3,0.1

Chan Stop Cuts=-1
Use User Specified Reach Order=0
Composite Channel Slope=5