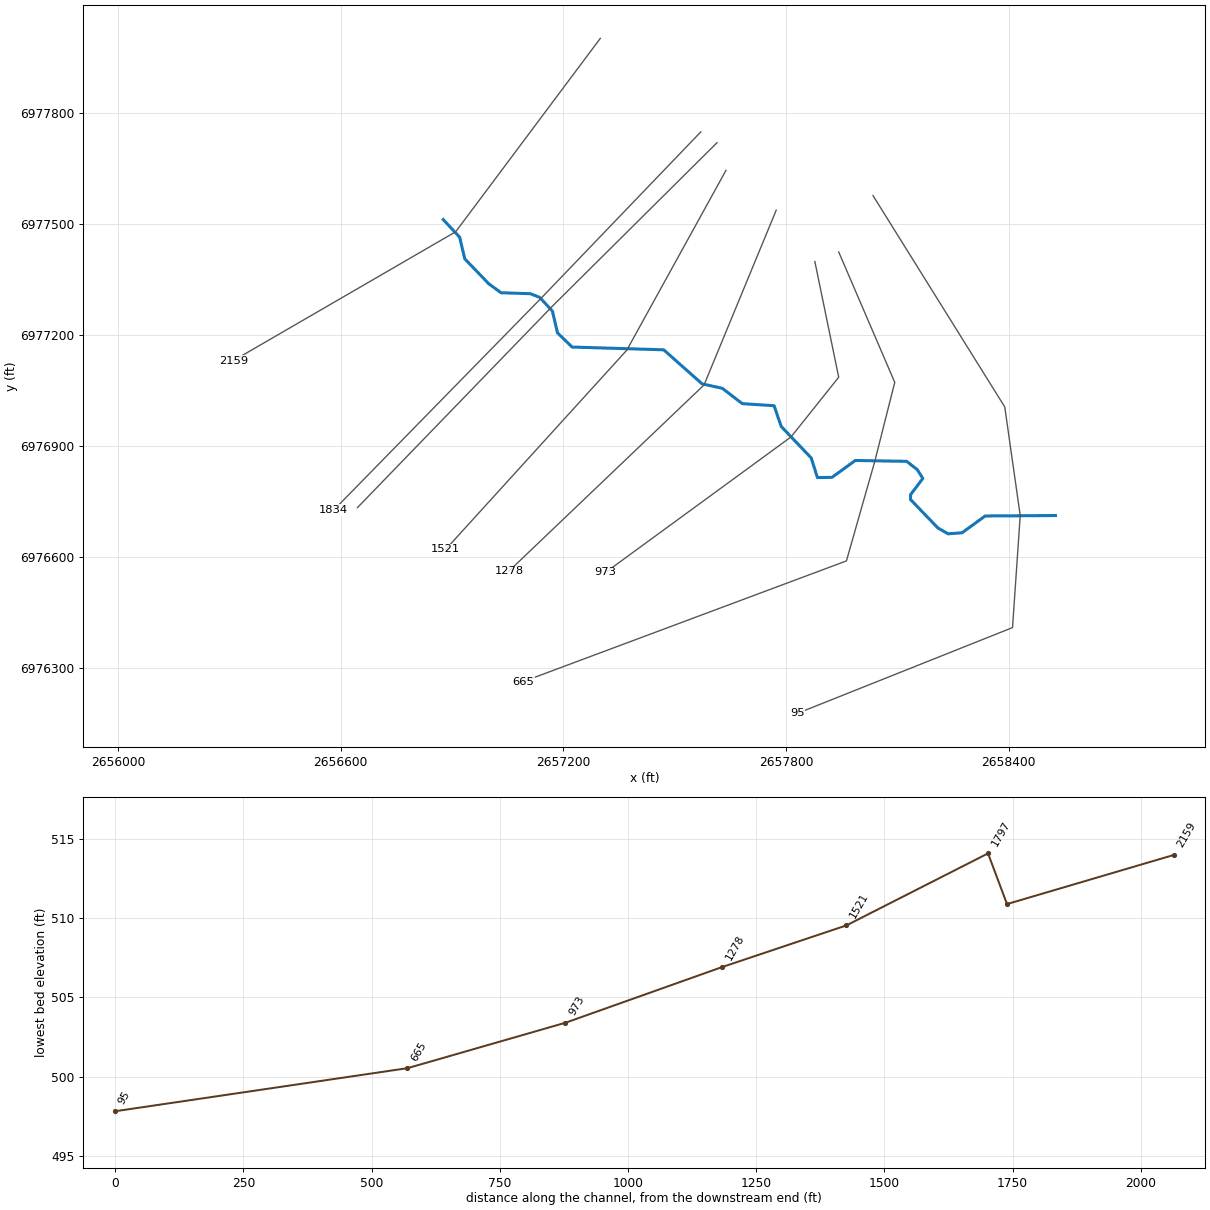
--- Kings Creek Trib 3.prj (project) ---

Proj Title=Kings Creek Trib 3 Base Level Engineering
Current Plan=p01
Default Exp/Contr=0.3,0.1
English Units
Geom File=g01
Flow File=f01
Plan File=p01
BEGIN DESCRIPTION:
Kings Creek Trib 3
END DESCRIPTION:

--- Kings Creek Trib 3.p01 (plan) ---

Plan Title=Multiple Run
Short Identifier=Multiple
Geom File=g01
Flow File=f01
Subcritical Flow
K Sum by GR= 0
Std Step Tol= 0.01
Critical Tol= 0.01
Num of Std Step Trials= 20
Max Error Tol= 0.3
Flow Tol Ratio= 0.001
Split Flow NTrial= 30
Split Flow Tol= 0.02
Split Flow Ratio= 0.02
Log Output Level= 0
Friction Slope Method= 1
Unsteady Friction Slope Method= 2
Unsteady Bridges Friction Slope Method= 1
Parabolic Critical Depth
Global Vel Dist=  1 , 1 , 1
Global Log Level= 0
CheckData=True
Encroach Param= -1, 0, 0, 0
BEGIN DESCRIPTION:
Multiple Run
END DESCRIPTION:

--- Kings Creek Trib 3.f01 (steady flow) ---

Flow Title=Multiple
Number of Profiles=7
Profile Names=10-year,25-year,50-year,1pct_min,100-year,1pct_plu,500-year
River Rch & RM= Kings Creek Trib,Reach-1,2159
     509     677     811     483     964    1922    1358
Boundary for River Rch & Prof#=Kings Creek Trib,Reach-1,1
Up Type=0
Dn Type=3
Dn Slope=0.005
Boundary for River Rch & Prof#=Kings Creek Trib,Reach-1,2
Up Type=0
Dn Type=3
Dn Slope=0.005
Boundary for River Rch & Prof#=Kings Creek Trib,Reach-1,3
Up Type=0
Dn Type=3
Dn Slope=0.005
Boundary for River Rch & Prof#=Kings Creek Trib,Reach-1,4
Up Type=0
Dn Type=3
Dn Slope=0.005
Boundary for River Rch & Prof#=Kings Creek Trib,Reach-1,5
Up Type=0
Dn Type=3
Dn Slope=0.005
Boundary for River Rch & Prof#=Kings Creek Trib,Reach-1,6
Up Type=0
Dn Type=3
Dn Slope=0.005
Boundary for River Rch & Prof#=Kings Creek Trib,Reach-1,7
Up Type=0
Dn Type=3
Dn Slope=0.005

--- Kings Creek Trib 3.g01 (geometry) ---

Geom Title=Existing Conditions

River Reach=Kings Creek Trib,Reach-1
Reach XY= 30
      2656876.00      6977511.00      2656920.29      6977463.35
      2656934.05      6977404.89      2656999.07      6977337.15
      2657031.89      6977313.15      2657110.91      6977310.53
      2657136.10      6977300.61      2657170.25      6977263.55
      2657184.03      6977204.64      2657223.30      6977166.36
      2657470.14      6977158.94      2657573.71      6977066.85
      2657628.17      6977054.86      2657682.05      6977013.37
      2657767.66      6977007.84      2657786.92      6976951.63
      2657867.70      6976866.64      2657884.48      6976813.63
      2657923.89      6976814.19      2657986.48      6976859.77
      2658125.00      6976857.47      2658153.69      6976834.84
      2658168.54      6976811.25      2658135.62      6976767.68
      2658135.30      6976754.32      2658209.25      6976677.22
      2658236.61      6976661.60      2658274.25      6976664.34
      2658336.49      6976709.77      2658526.00      6976711.00

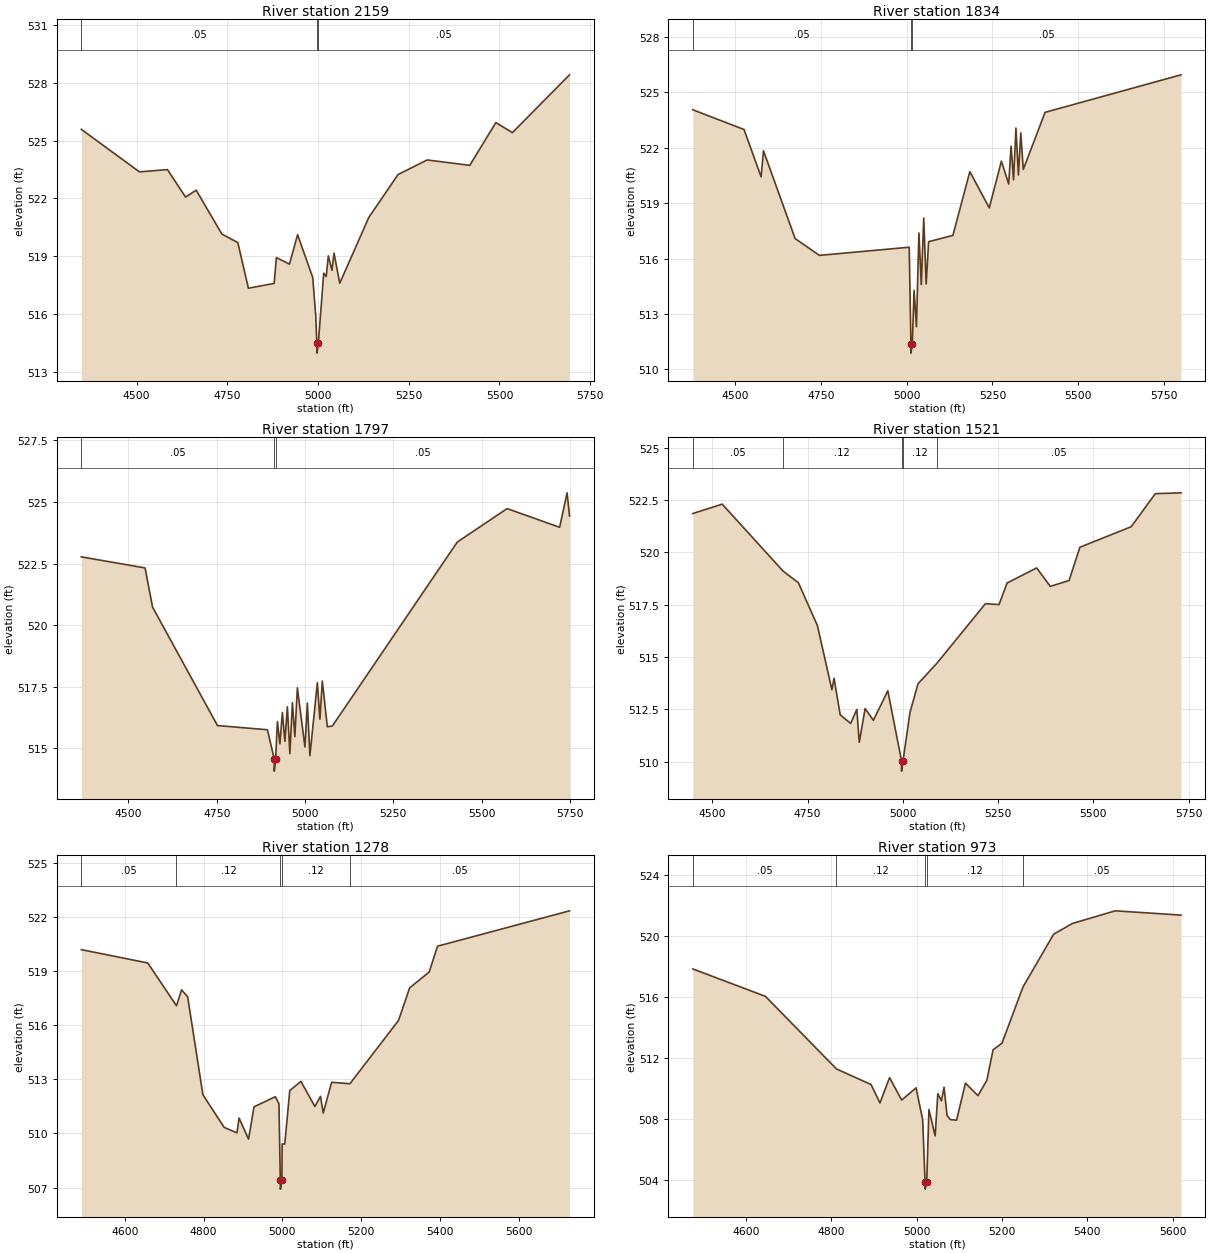
Type RM Length L Ch R = 1,2159,325,325,325
BEGIN DESCRIPTION:
Kings Creek Trib 3 4.0
END DESCRIPTION:
XS GIS Cut Line= 3
      2657299.42      6978000.79      2656909.58      6977477.92
      2656310.46      6977129.63
#Sta/Elev= 30
  4347.8  525.59  4508.0  523.38  4585.1  523.50  4635.1  522.07  4664.3  522.43
  4735.2  520.15  4779.0  519.71  4808.2  517.34  4879.1  517.59  4885.3  518.93
  4921.3  518.59  4943.7  520.12  4985.4  517.90  4993.8  515.90  4996.8  514.47
  4997.1  513.97  5000.8  514.47  5015.7  518.12  5022.6  517.95  5028.4  519.02
  5038.3  518.27  5044.1  519.16  5059.9  517.60  5140.1  521.02  5220.4  523.24
  5300.7  524.00  5418.2  523.72  5490.0  525.94  5535.7  525.42  5693.0  528.42
#Mann=3,-1,0
  4347.8    0.05       0  4996.8    0.04       0  5000.8    0.05       0
Bank Sta=4996.8,5000.8
Exp/Cntr=0.3,0.1

Type RM Length L Ch R = 1,1834,37,37,37
BEGIN DESCRIPTION:
Mapping XS 3aeaaabd
END DESCRIPTION:
XS GIS Cut Line= 3
      2657570.28      6977748.04      2657143.19      6977301.85
      2656581.13      6976725.91
#Sta/Elev= 30
  4376.9  524.05  4526.2  522.98  4575.9  520.42  4582.8  521.83  4675.0  517.08
  4745.8  516.17  5007.4  516.61  5012.4  511.38  5012.6  510.88  5016.4  511.38
  5021.5  514.28  5028.5  512.31  5035.7  517.38  5042.6  514.59  5049.8  518.19
  5056.8  514.62  5063.9  516.91  5134.7  517.25  5184.1  520.70  5240.7  518.74
  5276.0  521.27  5297.3  520.03  5304.2  522.08  5311.4  520.26  5318.4  523.06
  5325.6  520.52  5332.5  522.80  5339.7  520.82  5403.3  523.91  5799.3  525.94
#Mann=3,-1,0
  4376.9    0.05       0  5012.4    0.03       0  5016.4    0.05       0
Bank Sta=5012.4,5016.4
Exp/Cntr=0.3,0.1

Type RM Length L Ch R = 1,1797,276,276,276
BEGIN DESCRIPTION:
Mapping XS b3d2cecd
END DESCRIPTION:
XS GIS Cut Line= 3
      2657613.70      6977718.55      2657169.23      6977275.81
      2656644.89      6976732.38
#Sta/Elev= 30
  4366.6  522.77  4547.1  522.32  4568.3  520.73  4752.2  515.92  4893.6  515.75
  4912.8  514.57  4913.0  514.07  4916.8  514.57  4921.9  516.08  4928.9  515.18
  4936.0  516.45  4943.1  515.28  4950.1  516.68  4957.2  514.78  4964.3  516.85
  4971.3  515.47  4978.4  517.45  4999.9  515.05  5006.7  516.83  5013.9  514.70
  5035.0  517.66  5042.2  516.18  5049.1  517.73  5063.3  515.87  5077.4  515.90
  5431.2  523.37  5572.4  524.73  5721.1  523.97  5742.2  525.37  5749.1  524.43
#Mann=3,-1,0
  4366.6    0.05       0  4912.8    0.03       0  4916.8    0.05       0
Bank Sta=4912.8,4916.8
Exp/Cntr=0.3,0.1

Type RM Length L Ch R = 1,1521,243,243,243
BEGIN DESCRIPTION:
Mapping XS cfe1a401
END DESCRIPTION:
XS GIS Cut Line= 3
      2657637.98      6977643.86      2657370.62      6977157.75
      2656882.75      6976619.54
#Sta/Elev= 30
  4449.0  521.85  4526.1  522.30  4685.9  519.10  4726.2  518.54  4776.1  516.49
  4814.0  513.43  4819.7  513.98  4835.8  512.23  4863.3  511.82  4879.4  512.49
  4885.9  510.92  4901.2  512.53  4922.9  511.97  4960.8  513.38  4996.7  510.04
  4996.9  509.54  5000.7  510.04  5018.9  512.34  5039.9  513.71  5090.2  514.71
  5216.9  517.54  5252.7  517.50  5273.7  518.53  5351.4  519.25  5387.2  518.37
  5436.5  518.65  5464.9  520.24  5599.4  521.22  5662.9  522.80  5730.2  522.84
#Mann=5,-1,0
  4449.0    0.05       0  4685.9    0.12       0  4996.7    0.07       0
  5000.7    0.12       0  5090.2    0.05       0
Bank Sta=4996.7,5000.7
Exp/Cntr=0.3,0.1

Type RM Length L Ch R = 1,1278,305,305,305
BEGIN DESCRIPTION:
Mapping XS cac8167c
END DESCRIPTION:
XS GIS Cut Line= 3
      2657773.40      6977536.23      2657578.95      6977064.00
      2657052.94      6976560.56
#Sta/Elev= 30
  4489.8  520.18  4658.4  519.44  4731.3  517.07  4744.2  517.95  4759.6  517.57
  4798.3  512.14  4852.3  510.33  4884.7  510.03  4890.1  510.85  4914.1  509.68
  4928.0  511.47  4982.1  512.03  4991.3  511.64  4994.7  507.41  4995.0  506.91
  4998.7  507.41  4999.4  509.41  5006.0  509.41  5018.7  512.37  5047.0  512.88
  5082.5  511.49  5096.7  512.05  5103.6  511.13  5125.0  512.83  5171.4  512.75
  5294.8  516.26  5322.9  518.06  5372.5  518.94  5393.6  520.37  5728.6  522.33
#Mann=5,-1,0
  4489.8    0.05       0  4731.3    0.12       0  4994.7    0.07       0
  4998.7    0.12       0  5171.4    0.05       0
Bank Sta=4994.7,4998.7
Exp/Cntr=0.3,0.1

Type RM Length L Ch R = 1,973,308,308,308
BEGIN DESCRIPTION:
Mapping XS 44ae9b27
END DESCRIPTION:
XS GIS Cut Line= 4
      2657877.57      6977397.31      2657941.80      6977084.83
      2657813.32      6976923.38      2657313.30      6976557.04
#Sta/Elev= 30
  4474.7  517.85  4645.2  516.05  4811.7  511.29  4892.9  510.27  4913.7  509.06
  4936.2  510.72  4964.7  509.25  4998.4  510.05  5013.9  507.97  5019.5  503.91
  5019.8  503.41  5023.5  503.91  5028.6  508.63  5043.2  506.90  5049.4  509.67
  5057.9  509.20  5064.1  510.09  5071.1  508.24  5078.8  507.97  5093.4  507.93
  5114.3  510.36  5143.6  509.54  5164.4  510.54  5179.1  512.55  5200.0  512.98
  5249.1  516.66  5321.2  520.13  5365.1  520.83  5465.5  521.66  5619.9  521.38
#Mann=5,-1,0
  4474.7    0.05       0  4811.7    0.12       0  5019.5    0.07       0
  5023.5    0.12       0  5249.1    0.05       0
Bank Sta=5019.5,5023.5
Exp/Cntr=0.3,0.1

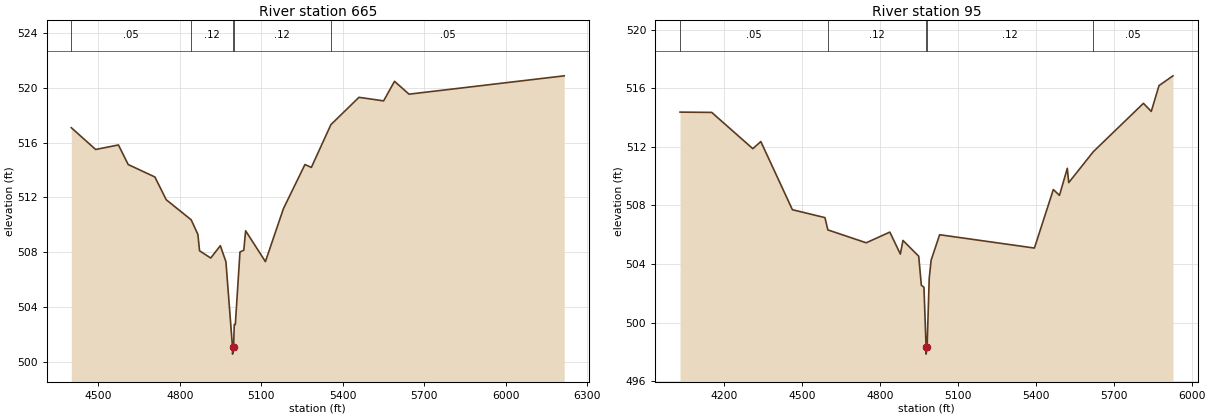
Type RM Length L Ch R = 1,665,570,570,570
BEGIN DESCRIPTION:
Mapping XS 596d0d2a
END DESCRIPTION:
XS GIS Cut Line= 5
      2657941.80      6977423.37      2658092.84      6977070.95
      2658039.02      6976857.40      2657962.63      6976588.31
      2657091.12      6976261.92
#Sta/Elev= 30
  4400.5  517.09  4490.1  515.50  4573.9  515.83  4609.8  514.40  4708.1  513.49
  4749.8  511.83  4841.7  510.36  4866.4  509.29  4872.4  508.10  4913.5  507.57
  4948.9  508.47  4969.5  507.30  4993.7  501.05  4993.9  500.55  4997.7  501.05
  5000.1  502.71  5004.1  502.71  5021.2  508.01  5035.2  508.14  5042.0  509.56
  5114.8  507.31  5181.2  511.18  5260.3  514.40  5283.9  514.19  5355.7  517.31
  5459.0  519.31  5549.8  519.05  5589.9  520.48  5643.3  519.54  6214.5  520.88
#Mann=5,-1,0
  4400.5    0.05       0  4841.7    0.12       0  4993.7    0.07       0
  4997.7    0.12       0  5355.7    0.05       0
Bank Sta=4993.7,4997.7
Exp/Cntr=0.3,0.1

Type RM Length L Ch R = 1,95,0,0,0
BEGIN DESCRIPTION:
Kings Creek Trib 3 2.0
END DESCRIPTION:
XS GIS Cut Line= 5
      2658034.27      6977575.68      2658389.28      6977004.54
      2658430.97      6976711.07      2658410.22      6976408.10
      2657830.44      6976176.23
#Sta/Elev= 30
  4031.1  514.38  4153.0  514.36  4311.2  511.88  4341.9  512.37  4463.5  507.71
  4588.7  507.17  4599.9  506.33  4747.6  505.45  4838.5  506.18  4878.9  504.68
  4889.0  505.61  4949.6  504.53  4959.7  502.55  4969.8  502.41  4977.9  498.34
  4978.1  497.84  4981.9  498.34  4990.0  503.02  4997.5  504.27  5030.1  506.00
  5394.9  505.09  5467.7  509.09  5491.3  508.69  5521.5  510.54  5526.9  509.56
  5621.8  511.68  5814.4  514.98  5844.6  514.43  5874.3  516.19  5928.1  516.86
#Mann=5,-1,0
  4031.1    0.05       0  4599.9    0.12       0  4977.9    0.07       0
  4981.9    0.12       0  5621.8    0.05       0
Bank Sta=4977.9,4981.9
Exp/Cntr=0.3,0.1

Chan Stop Cuts=-1