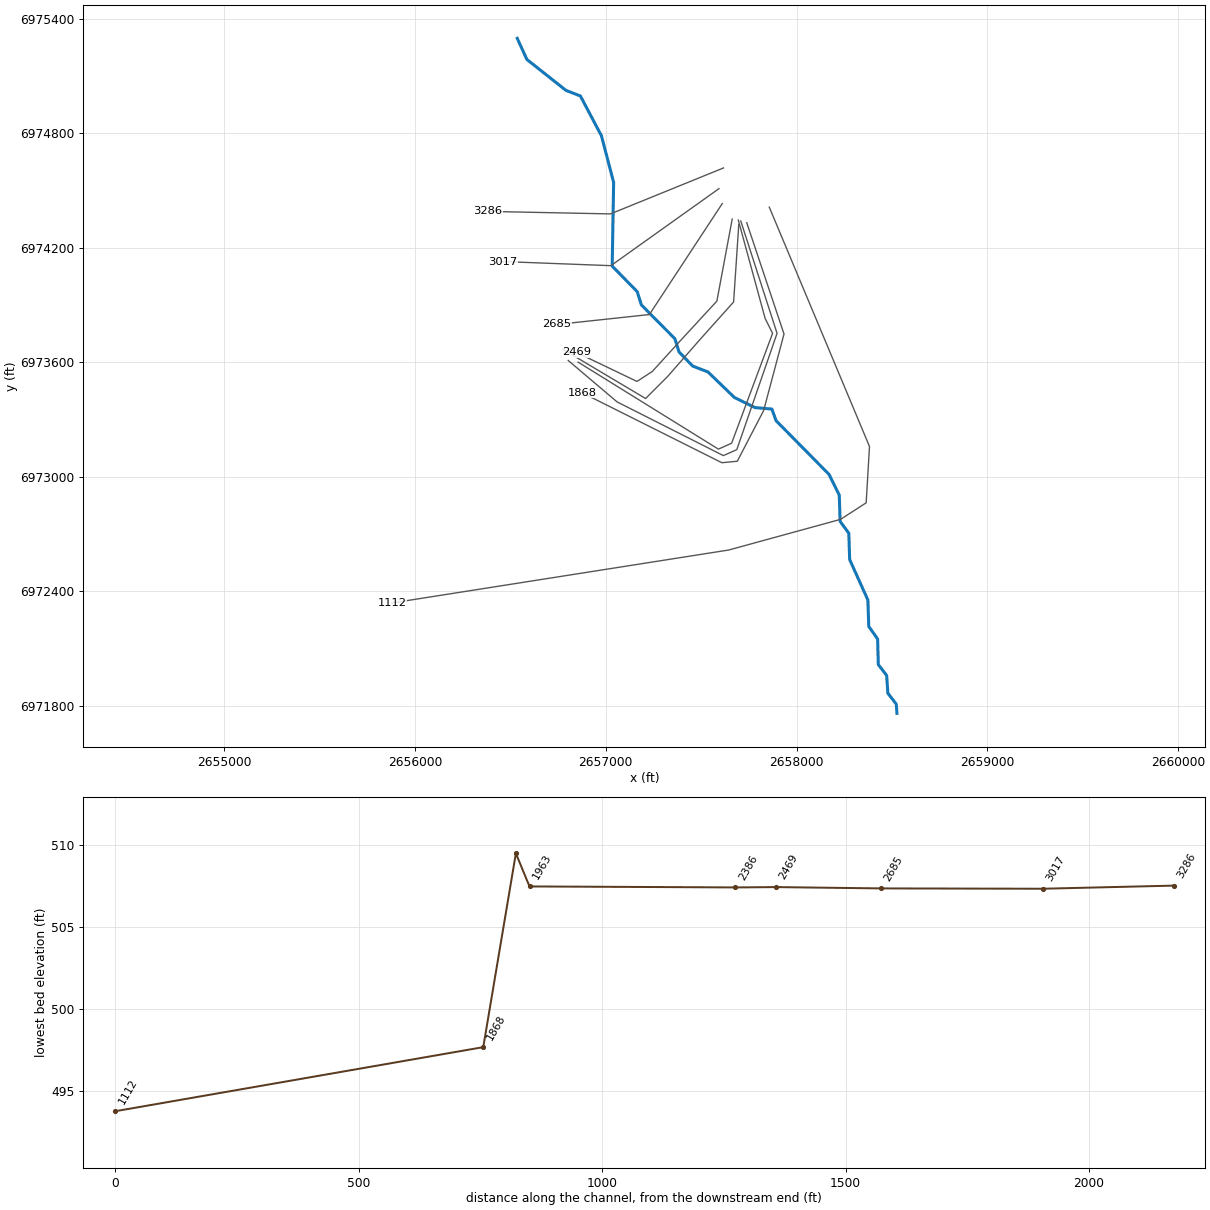
--- Kings Creek Trib 4.prj (project) ---

Proj Title=Kings Creek Trib 4 Base Level Engineering
Current Plan=p01
Default Exp/Contr=0.3,0.1
English Units
Geom File=g01
Flow File=f01
Plan File=p01
BEGIN DESCRIPTION:
Kings Creek Trib 4
END DESCRIPTION:

--- Kings Creek Trib 4.p01 (plan) ---

Plan Title=Multiple Run
Short Identifier=Multiple
Geom File=g01
Flow File=f01
Subcritical Flow
K Sum by GR= 0
Std Step Tol= 0.01
Critical Tol= 0.01
Num of Std Step Trials= 20
Max Error Tol= 0.3
Flow Tol Ratio= 0.001
Split Flow NTrial= 30
Split Flow Tol= 0.02
Split Flow Ratio= 0.02
Log Output Level= 0
Friction Slope Method= 1
Unsteady Friction Slope Method= 2
Unsteady Bridges Friction Slope Method= 1
Parabolic Critical Depth
Global Vel Dist=  1 , 1 , 1
Global Log Level= 0
CheckData=True
Encroach Param= -1, 0, 0, 0
BEGIN DESCRIPTION:
Multiple Run
END DESCRIPTION:

--- Kings Creek Trib 4.f01 (steady flow) ---

Flow Title=Multiple
Number of Profiles=7
Profile Names=10-year,25-year,50-year,1pct_min,100-year,1pct_plu,500-year
River Rch & RM= Kings Creek Trib,Reach-1,3286
     429     562     667     393     785    1566    1085
River Rch & RM= Kings Creek Trib,Reach-1,1112
     438     574     682     402     803    1602    1111
Boundary for River Rch & Prof#=Kings Creek Trib,Reach-1,1
Up Type=0
Dn Type=3
Dn Slope=0.005
Boundary for River Rch & Prof#=Kings Creek Trib,Reach-1,2
Up Type=0
Dn Type=3
Dn Slope=0.005
Boundary for River Rch & Prof#=Kings Creek Trib,Reach-1,3
Up Type=0
Dn Type=3
Dn Slope=0.005
Boundary for River Rch & Prof#=Kings Creek Trib,Reach-1,4
Up Type=0
Dn Type=3
Dn Slope=0.005
Boundary for River Rch & Prof#=Kings Creek Trib,Reach-1,5
Up Type=0
Dn Type=3
Dn Slope=0.005
Boundary for River Rch & Prof#=Kings Creek Trib,Reach-1,6
Up Type=0
Dn Type=3
Dn Slope=0.005
Boundary for River Rch & Prof#=Kings Creek Trib,Reach-1,7
Up Type=0
Dn Type=3
Dn Slope=0.005

--- Kings Creek Trib 4.g01 (geometry) ---

Geom Title=Existing Conditions

River Reach=Kings Creek Trib,Reach-1
Reach XY= 30
      2656536.21      6975298.38      2656586.73      6975187.76
      2656791.71      6975025.46      2656867.20      6974996.43
      2656977.53      6974787.38      2657041.40      6974543.50
      2657033.81      6974104.81      2657165.22      6973970.68
      2657186.78      6973901.32      2657362.37      6973724.21
      2657384.15      6973654.93      2657455.87      6973580.77
      2657535.68      6973550.22      2657673.70      6973416.83
      2657782.05      6973363.37      2657870.53      6973355.74
      2657892.74      6973294.55      2658170.17      6973013.30
      2658223.75      6972905.07      2658228.27      6972766.94
      2658273.73      6972705.06      2658278.27      6972566.94
      2658373.73      6972355.06      2658378.27      6972216.94
      2658424.77      6972150.49      2658428.27      6972016.94
      2658472.15      6971959.40      2658478.23      6971866.92
      2658522.36      6971809.49      2658526.00      6971761.00

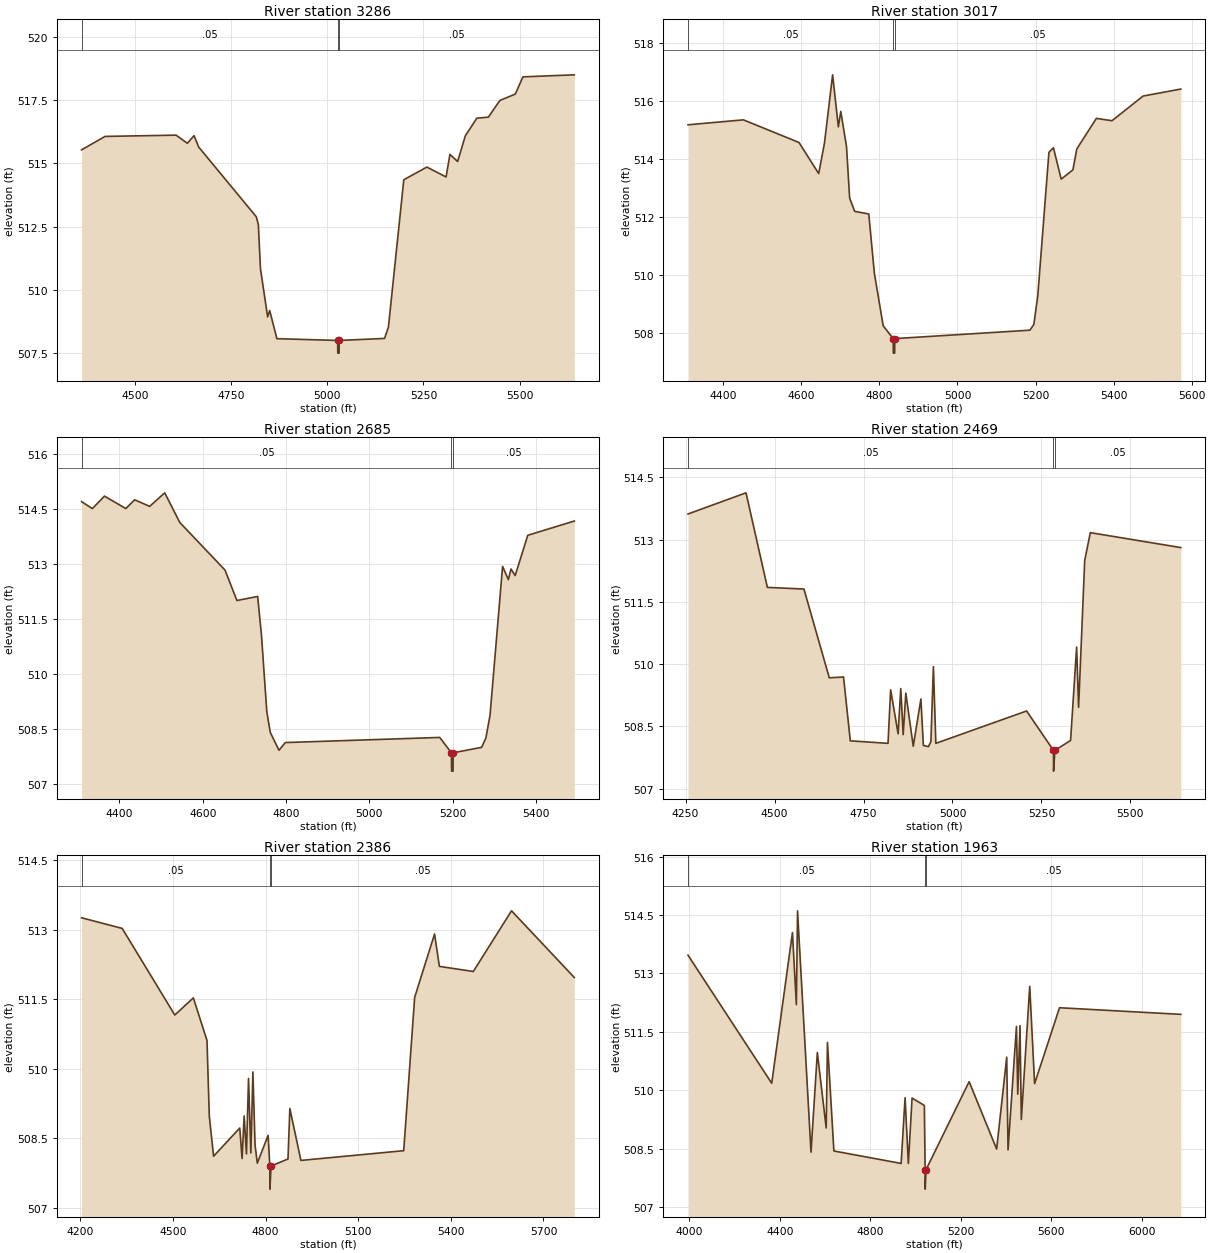
Type RM Length L Ch R = 1,3286,269,269,269
BEGIN DESCRIPTION:
Mapping XS 93f3b13e
END DESCRIPTION:
XS GIS Cut Line= 3
      2657617.22      6974619.24      2657024.82      6974378.37
      2656382.45      6974391.39
#Sta/Elev= 30
  4360.5  515.53  4421.7  516.06  4606.4  516.11  4635.8  515.79  4653.3  516.09
  4665.3  515.64  4815.1  512.89  4820.5  512.58  4826.0  510.84  4844.6  508.94
  4850.0  509.19  4868.7  508.08  5026.8  508.01  5027.1  507.51  5030.6  507.51
  5030.8  508.01  5148.8  508.09  5158.9  508.54  5198.9  514.35  5258.9  514.85
  5308.9  514.46  5318.9  515.35  5338.9  515.07  5358.9  516.08  5388.9  516.78
  5418.9  516.82  5448.9  517.48  5488.9  517.73  5508.9  518.41  5642.5  518.49
#Mann=3,-1,0
  4360.5    0.05       0  5026.8    0.03       0  5030.8    0.05       0
Bank Sta=5026.8,5030.8
Exp/Cntr=0.3,0.1

Type RM Length L Ch R = 1,3017,332,332,332
BEGIN DESCRIPTION:
Mapping XS f3d7df63
END DESCRIPTION:
XS GIS Cut Line= 3
      2657593.39      6974510.75      2657026.99      6974107.10
      2656459.71      6974128.76
#Sta/Elev= 30
  4309.2  515.18  4451.2  515.35  4593.8  514.57  4644.2  513.50  4659.0  514.55
  4679.9  516.90  4694.6  515.11  4700.8  515.64  4715.5  514.43  4723.5  512.66
  4736.4  512.20  4772.6  512.11  4786.8  510.08  4809.5  508.26  4835.2  507.82
  4835.5  507.32  4839.0  507.32  4839.2  507.82  5185.8  508.11  5195.8  508.31
  5205.8  509.29  5234.4  514.23  5245.9  514.39  5265.9  513.31  5295.9  513.63
  5305.9  514.35  5356.0  515.40  5396.0  515.32  5476.0  516.17  5572.4  516.41
#Mann=3,-1,0
  4309.2    0.05       0  4835.2    0.03       0  4839.2    0.05       0
Bank Sta=4835.2,4839.2
Exp/Cntr=0.3,0.1

Type RM Length L Ch R = 1,2685,216,216,216
BEGIN DESCRIPTION:
Mapping XS c8d92121
END DESCRIPTION:
XS GIS Cut Line= 3
      2657610.75      6974432.62      2657228.81      6973851.03
      2656744.90      6973798.95
#Sta/Elev= 30
  4309.2  514.70  4335.1  514.51  4364.2  514.85  4415.4  514.51  4436.5  514.75
  4472.7  514.57  4508.8  514.94  4545.0  514.13  4653.5  512.83  4682.0  512.00
  4731.8  512.11  4740.9  511.06  4753.8  508.96  4762.0  508.40  4783.0  507.91
  4798.1  508.12  5168.7  508.26  5196.9  507.84  5197.2  507.34  5200.7  507.34
  5200.9  507.84  5269.3  507.99  5279.4  508.24  5289.4  508.86  5319.6  512.93
  5333.5  512.57  5339.7  512.86  5349.8  512.68  5380.0  513.78  5491.7  514.17
#Mann=3,-1,0
  4309.2    0.05       0  5196.9    0.03       0  5200.9    0.05       0
Bank Sta=5196.9,5200.9
Exp/Cntr=0.3,0.1

Type RM Length L Ch R = 1,2469,83,83,83
BEGIN DESCRIPTION:
Mapping XS 7a799cd7
END DESCRIPTION:
XS GIS Cut Line= 6
      2657662.70      6974351.22      2657582.40      6973921.51
      2657378.41      6973700.16      2657243.86      6973552.59
      2657163.57      6973500.51      2656846.76      6973652.40
#Sta/Elev= 30
  4256.8  513.62  4419.8  514.13  4479.8  511.85  4582.6  511.81  4653.8  509.67
  4693.9  509.69  4712.9  508.15  4818.9  508.09  4826.3  509.38  4847.3  508.32
  4854.7  509.41  4861.5  508.30  4868.9  509.30  4889.8  508.02  4911.4  509.16
  4918.2  508.04  4932.4  508.01  4939.4  508.13  4946.5  509.94  4953.3  508.09
  5208.4  508.87  5283.9  507.92  5284.2  507.42  5287.9  507.92  5332.0  508.16
  5349.0  510.41  5354.5  508.96  5371.7  512.50  5387.5  513.17  5641.7  512.81
#Mann=3,-1,0
  4256.8    0.05       0  5283.9    0.03       0  5287.9    0.05       0
Bank Sta=5283.9,5287.9
Exp/Cntr=0.3,0.1

Type RM Length L Ch R = 1,2386,423,423,423
BEGIN DESCRIPTION:
Mapping XS dbdd93b3
END DESCRIPTION:
XS GIS Cut Line= 6
      2657697.13      6974322.39      2657670.08      6973916.85
      2657490.96      6973716.91      2657323.86      6973525.94
      2657208.85      6973410.92      2656774.85      6973669.15
#Sta/Elev= 30
  4203.6  513.26  4335.3  513.03  4505.7  511.16  4565.8  511.53  4610.0  510.61
  4617.4  508.98  4631.3  508.11  4716.1  508.72  4723.6  508.06  4730.3  508.98
  4737.8  508.16  4744.5  509.79  4752.0  508.18  4758.7  509.93  4765.6  508.36
  4772.9  507.96  4808.0  508.56  4813.5  507.90  4813.8  507.40  4817.5  507.90
  4872.3  508.05  4878.4  509.14  4914.2  508.02  5247.3  508.23  5282.7  511.54
  5347.2  512.91  5362.8  512.21  5472.7  512.10  5596.5  513.41  5799.9  511.97
#Mann=3,-1,0
  4203.6    0.05       0  4813.5    0.03       0  4817.5    0.05       0
Bank Sta=4813.5,4817.5
Exp/Cntr=0.3,0.1

Type RM Length L Ch R = 1,1963,28,28,28
BEGIN DESCRIPTION:
Mapping XS 9e730523
END DESCRIPTION:
XS GIS Cut Line= 6
      2657694.61      6974346.16      2657835.24      6973830.54
      2657874.30      6973752.42      2657659.66      6973176.83
      2657590.44      6973145.65      2656855.52      6973601.48
#Sta/Elev= 30
  3994.4  513.47  4364.2  510.18  4455.8  514.05  4473.1  512.20  4478.2  514.61
  4537.8  508.41  4565.8  510.97  4604.9  509.03  4610.5  511.23  4638.9  508.44
  4936.0  508.12  4953.4  509.81  4967.9  508.12  4984.3  509.80  5038.6  509.61
  5042.0  507.96  5042.3  507.46  5046.0  507.96  5236.4  510.22  5358.0  508.49
  5402.5  510.85  5408.3  508.47  5445.5  511.64  5451.3  509.90  5461.2  511.66
  5467.0  509.25  5504.2  512.67  5525.7  510.17  5635.8  512.12  6171.5  511.95
#Mann=3,-1,0
  3994.4    0.05       0  5042.0    0.03       0  5046.0    0.05       0
Bank Sta=5042,5046
Exp/Cntr=0.3,0.1

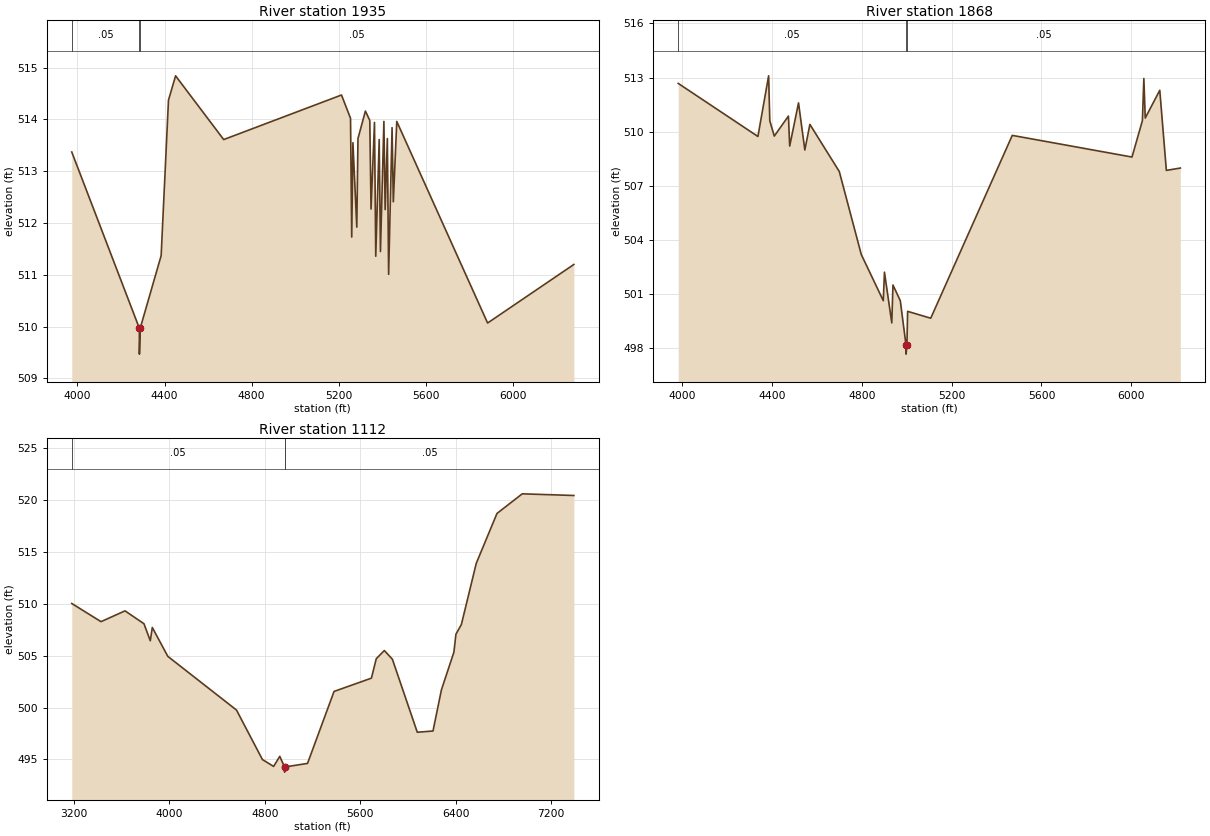
Type RM Length L Ch R = 1,1935,67,67,67
BEGIN DESCRIPTION:
Mapping XS 57b1bb62
END DESCRIPTION:
XS GIS Cut Line= 6
      2657707.62      6974341.00      2657897.74      6973752.42
      2657686.80      6973143.04      2657616.49      6973111.79
      2657059.54      6973393.13      2656803.45      6973610.15
#Sta/Elev= 30
  3974.1  513.37  4284.3  509.97  4284.6  509.47  4288.3  509.97  4384.4  511.37
  4418.1  514.37  4450.7  514.84  4671.6  513.61  5212.4  514.47  5253.8  514.02
  5259.3  511.73  5264.8  513.55  5282.6  511.92  5288.0  513.63  5322.1  514.16
  5342.2  513.98  5348.0  512.27  5363.8  513.94  5369.6  511.36  5385.4  513.61
  5391.2  511.45  5407.0  513.96  5412.8  512.26  5422.9  513.63  5428.7  511.01
  5444.5  513.84  5450.3  512.41  5466.1  513.96  5883.1  510.07  6279.0  511.20
#Mann=3,-1,0
  3974.1    0.05       0  4284.3    0.03       0  4288.3    0.05       0
Bank Sta=4284.3,4288.3
Exp/Cntr=0.3,0.1

Type RM Length L Ch R = 1,1868,756,756,756
BEGIN DESCRIPTION:
Mapping XS a5057745
END DESCRIPTION:
XS GIS Cut Line= 6
      2657738.89      6974332.23      2657934.19      6973748.94
      2657827.42      6973347.90      2657689.40      6973082.28
      2657608.67      6973074.46      2656877.67      6973440.45
#Sta/Elev= 30
  3981.1  512.68  4336.3  509.74  4384.0  513.10  4389.2  510.61  4409.2  509.76
  4472.3  510.87  4477.9  509.21  4517.3  511.60  4545.4  508.99  4567.9  510.41
  4698.9  507.80  4797.0  503.20  4895.1  500.64  4900.3  502.22  4933.0  499.41
  4938.2  501.51  4970.9  500.64  4996.4  498.18  4996.6  497.68  5000.4  498.18
  5003.6  500.05  5106.6  499.67  5470.0  509.80  6003.7  508.60  6050.1  510.62
  6056.5  512.95  6062.7  510.76  6127.5  512.30  6156.8  507.86  6219.0  507.99
#Mann=3,-1,0
  3981.1    0.05       0  4996.4    0.03       0  5000.4    0.05       0
Bank Sta=4996.4,5000.4
Exp/Cntr=0.3,0.1

Type RM Length L Ch R = 1,1112,0,0,0
BEGIN DESCRIPTION:
Mapping XS e1c7a33a
END DESCRIPTION:
XS GIS Cut Line= 6
      2657856.95      6974413.83      2658382.11      6973159.53
      2658364.75      6972864.40      2658230.20      6972777.59
      2657644.26      6972617.00      2655879.36      6972339.47
#Sta/Elev= 30
  3180.6  510.02  3425.9  508.27  3627.0  509.31  3786.0  508.07  3839.0  506.43
  3855.8  507.71  3985.9  504.93  4561.6  499.76  4779.3  494.99  4873.1  494.33
  4924.6  495.30  4964.8  494.28  4965.1  493.78  4968.8  494.28  5157.4  494.62
  5379.7  501.55  5693.1  502.83  5733.6  504.70  5801.3  505.49  5868.9  504.65
  6077.7  497.62  6209.3  497.74  6280.2  501.71  6384.6  505.33  6401.7  507.06
  6447.1  507.99  6572.2  513.89  6745.8  518.69  6957.7  520.58  7390.3  520.42
#Mann=3,-1,0
  3180.6    0.05       0  4964.8    0.04       0  4968.8    0.05       0
Bank Sta=4964.8,4968.8
Exp/Cntr=0.3,0.1

Chan Stop Cuts=-1