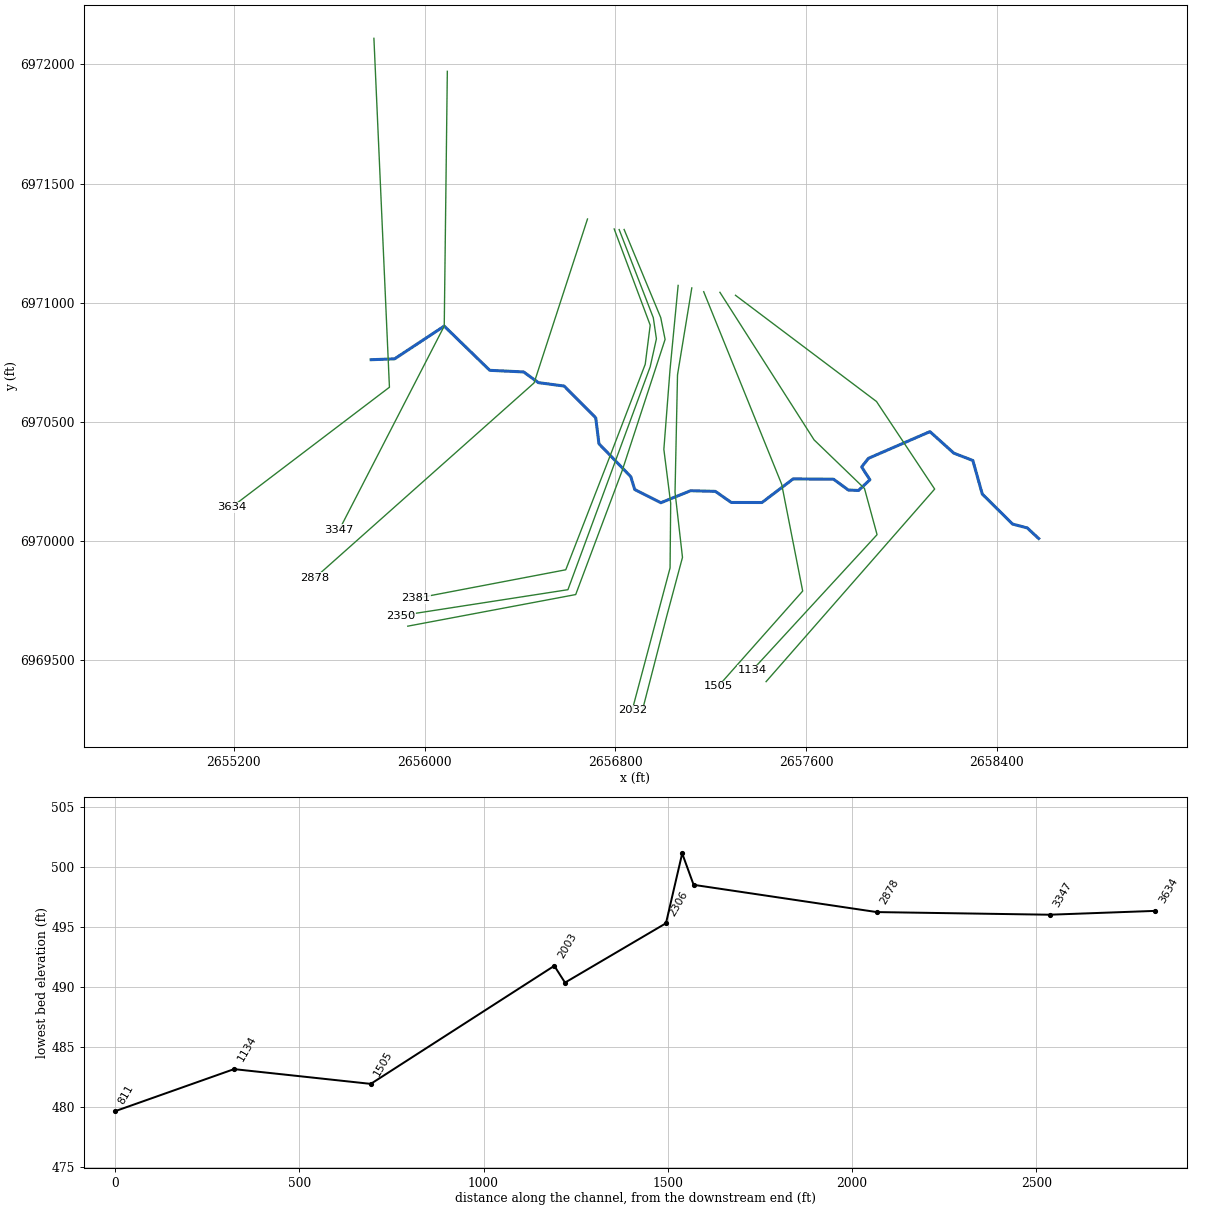
--- Kings Creek Trib 5.prj (project) ---

Proj Title=Kings Creek Trib 5 Base Level Engineering
Current Plan=p01
Default Exp/Contr=0.3,0.1
English Units
Geom File=g01
Flow File=f01
Plan File=p01
BEGIN DESCRIPTION:
Kings Creek Trib 5
END DESCRIPTION:

--- Kings Creek Trib 5.p01 (plan) ---

Plan Title=Multiple Run
Short Identifier=Multiple
Geom File=g01
Flow File=f01
Subcritical Flow
K Sum by GR= 0
Std Step Tol= 0.01
Critical Tol= 0.01
Num of Std Step Trials= 20
Max Error Tol= 0.3
Flow Tol Ratio= 0.001
Split Flow NTrial= 30
Split Flow Tol= 0.02
Split Flow Ratio= 0.02
Log Output Level= 0
Friction Slope Method= 1
Unsteady Friction Slope Method= 2
Unsteady Bridges Friction Slope Method= 1
Parabolic Critical Depth
Global Vel Dist=  1 , 1 , 1
Global Log Level= 0
CheckData=True
Encroach Param= -1, 0, 0, 0
BEGIN DESCRIPTION:
Multiple Run
END DESCRIPTION:

--- Kings Creek Trib 5.f01 (steady flow) ---

Flow Title=Multiple
Number of Profiles=7
Profile Names=10-year,25-year,50-year,1pct_min,100-year,1pct_plu,500-year
River Rch & RM= Kings Creek Trib,Reach-1,3634
     521     692     830     494     986    1967    1390
River Rch & RM= Kings Creek Trib,Reach-1,2306
     541     719     862     513    1024    2043    1442
Boundary for River Rch & Prof#=Kings Creek Trib,Reach-1,1
Up Type=0
Dn Type=3
Dn Slope=0.005
Boundary for River Rch & Prof#=Kings Creek Trib,Reach-1,2
Up Type=0
Dn Type=3
Dn Slope=0.005
Boundary for River Rch & Prof#=Kings Creek Trib,Reach-1,3
Up Type=0
Dn Type=3
Dn Slope=0.005
Boundary for River Rch & Prof#=Kings Creek Trib,Reach-1,4
Up Type=0
Dn Type=3
Dn Slope=0.005
Boundary for River Rch & Prof#=Kings Creek Trib,Reach-1,5
Up Type=0
Dn Type=3
Dn Slope=0.005
Boundary for River Rch & Prof#=Kings Creek Trib,Reach-1,6
Up Type=0
Dn Type=3
Dn Slope=0.005
Boundary for River Rch & Prof#=Kings Creek Trib,Reach-1,7
Up Type=0
Dn Type=3
Dn Slope=0.005

--- Kings Creek Trib 5.g01 (geometry) ---

Geom Title=Existing Conditions

River Reach=Kings Creek Trib,Reach-1
Reach XY= 30
      2655776.00      6970761.00      2655874.50      6970764.63
      2656082.67      6970902.04      2656273.55      6970716.47
      2656415.49      6970709.77      2656477.60      6970664.86
      2656585.79      6970650.48      2656718.14      6970517.17
      2656731.52      6970408.57      2656865.11      6970270.41
      2656881.61      6970216.59      2656991.37      6970161.07
      2657115.83      6970211.50      2657220.06      6970208.75
      2657286.51      6970162.21      2657415.56      6970162.04
      2657545.99      6970261.04      2657715.50      6970259.76
      2657777.81      6970214.34      2657820.36      6970212.62
      2657868.10      6970257.35      2657833.48      6970311.20
      2657862.00      6970347.38      2658119.96      6970459.38
      2658219.98      6970369.19      2658299.95      6970338.19
      2658339.40      6970197.70      2658466.29      6970071.70
      2658528.35      6970055.29      2658576.00      6970011.00

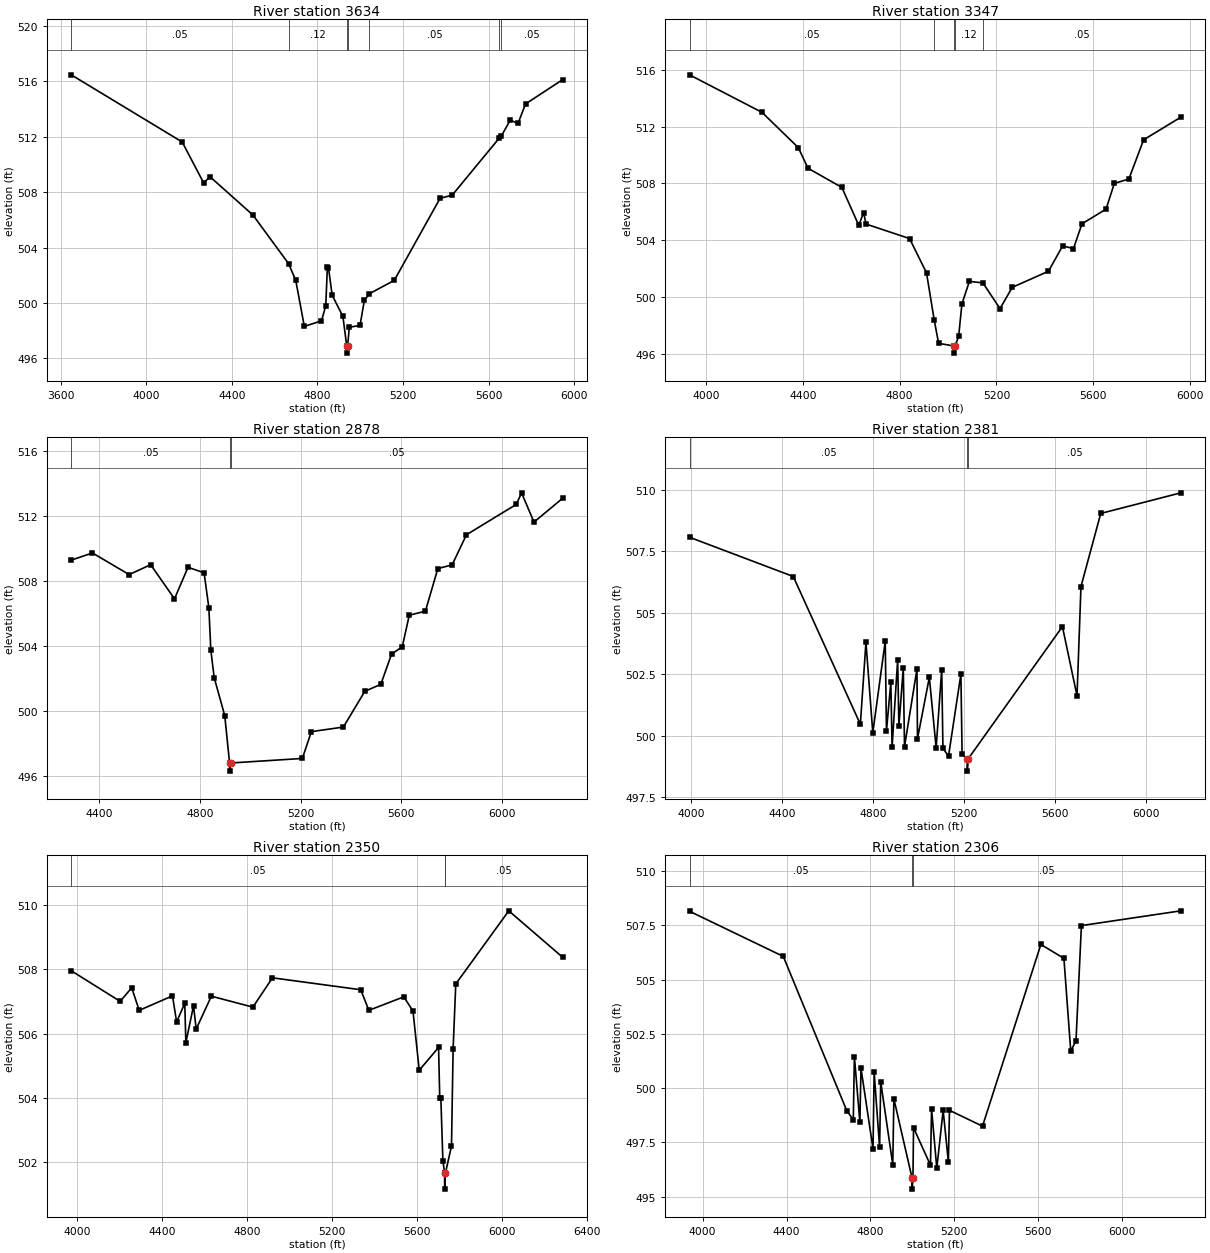
Type RM Length L Ch R = 1,3634,287,287,287
BEGIN DESCRIPTION:
Kings Creek Trib 5 7.0
END DESCRIPTION:
XS GIS Cut Line= 3
      2655787.70      6972109.00      2655852.80      6970645.50
      2655191.34      6970142.89
#Sta/Elev= 30
  3650.1  516.47  4168.6  511.62  4268.7  508.67  4298.7  509.11  4498.9  506.35
  4665.6  502.84  4699.1  501.63  4739.2  498.31  4819.3  498.71  4839.3  499.79
  4846.9  502.59  4851.9  502.55  4869.3  500.56  4919.4  499.03  4937.4  496.88
  4937.6  496.38  4941.4  496.88  4949.4  498.25  4999.4  498.38  5019.5  500.18
  5043.1  500.67  5159.4  501.63  5373.6  507.56  5429.8  507.78  5650.9  511.92
  5660.3  512.07  5701.3  513.20  5737.5  512.96  5772.9  514.37  5945.8  516.12
#Mann=7,-1,0
  3650.1    0.05       0  4665.6    0.12       0  4937.4    0.07       0
  4941.4    0.12       0  5043.1    0.05       0  5650.9    0.12       0
  5660.3    0.05       0
Bank Sta=4937.4,4941.4
Exp/Cntr=0.3,0.1

Type RM Length L Ch R = 1,3347,469,469,469
BEGIN DESCRIPTION:
Kings Creek Trib 5 6.0
END DESCRIPTION:
XS GIS Cut Line= 3
      2656095.64      6971970.66      2656082.67      6970902.04
      2655641.86      6970046.53
#Sta/Elev= 30
  3931.3  515.64  4231.0  513.00  4381.0  510.52  4421.0  509.07  4561.0  507.72
  4631.0  505.05  4651.0  505.95  4661.0  505.14  4841.0  504.12  4911.0  501.71
  4943.0  498.38  4961.0  496.75  5025.4  496.56  5025.6  496.06  5029.4  496.56
  5043.9  497.25  5057.4  499.52  5088.3  501.11  5144.2  501.00  5214.9  499.19
  5265.6  500.69  5415.1  501.82  5473.6  503.60  5518.6  503.42  5553.7  505.16
  5653.3  506.19  5687.4  508.00  5747.6  508.31  5808.5  511.07  5962.4  512.66
#Mann=5,-1,0
  3931.3    0.05       0  4943.0    0.12       0  5025.4    0.07       0
  5029.4    0.12       0  5144.2    0.05       0
Bank Sta=5025.4,5029.4
Exp/Cntr=0.3,0.1

Type RM Length L Ch R = 1,2878,497,497,497
BEGIN DESCRIPTION:
Mapping XS 8741dc4e
END DESCRIPTION:
XS GIS Cut Line= 3
      2656683.53      6971351.22      2656459.57      6970663.72
      2655540.66      6969846.34
#Sta/Elev= 30
  4288.4  509.26  4372.8  509.70  4518.7  508.37  4604.1  508.98  4698.8  506.88
  4752.6  508.82  4816.4  508.48  4835.5  506.32  4843.1  503.74  4856.6  502.03
  4898.6  499.69  4917.7  496.78  4917.9  496.28  4921.7  496.78  5207.0  497.06
  5242.9  498.71  5370.0  498.99  5455.3  501.19  5518.9  501.62  5561.5  503.48
  5604.2  503.93  5631.9  505.87  5696.1  506.12  5745.5  508.74  5802.3  508.97
  5859.2  510.82  6057.4  512.69  6078.3  513.40  6127.6  511.60  6241.3  513.06
#Mann=3,-1,0
  4288.4    0.05       0  4917.7    0.03       0  4921.7    0.05       0
Bank Sta=4917.7,4921.7
Exp/Cntr=0.3,0.1

Type RM Length L Ch R = 1,2381,31,31,31
BEGIN DESCRIPTION:
Mapping XS 0c4c37f1
END DESCRIPTION:
XS GIS Cut Line= 6
      2656795.52      6971309.55      2656946.55      6970905.91
      2656925.72      6970741.85      2656779.89      6970361.64
      2656592.39      6969879.87      2655964.75      6969760.07
#Sta/Elev= 30
  3992.7  508.08  4448.8  506.48  4743.6  500.46  4768.2  503.80  4798.3  500.11
  4853.0  503.85  4858.3  500.18  4877.6  502.17  4883.0  499.53  4907.6  503.08
  4913.0  500.39  4932.3  502.75  4937.7  499.55  4992.4  502.71  4994.7  499.87
  5046.8  502.37  5076.7  499.50  5101.2  502.68  5106.6  499.48  5131.1  499.16
  5185.5  502.50  5190.8  499.23  5213.4  499.05  5213.6  498.55  5217.4  499.05
  5631.7  504.44  5695.9  501.62  5713.2  506.07  5800.1  509.05  6152.2  509.89
#Mann=3,-1,0
  3992.7    0.05       0  5213.4    0.03       0  5217.4    0.05       0
Bank Sta=5213.4,5217.4
Exp/Cntr=0.3,0.1

Type RM Length L Ch R = 1,2350,44,44,44
BEGIN DESCRIPTION:
Mapping XS b26294cb
END DESCRIPTION:
XS GIS Cut Line= 6
      2656816.36      6971306.92      2656959.57      6970937.16
      2656972.60      6970848.62      2656946.55      6970731.43
      2656601.46      6969796.35      2655899.04      6969687.47
#Sta/Elev= 30
  3972.6  507.95  4202.9  507.00  4257.4  507.42  4292.7  506.72  4449.4  507.17
  4468.8  506.36  4507.2  506.94  4512.3  505.72  4548.4  506.86  4561.0  506.14
  4632.4  507.16  4827.9  506.82  4920.2  507.73  5335.9  507.36  5374.0  506.72
  5538.5  507.14  5581.8  506.70  5611.3  504.86  5702.3  505.57  5707.8  503.99
  5712.9  504.01  5722.6  502.05  5730.7  501.67  5731.0  501.17  5734.7  501.67
  5763.1  502.51  5770.8  505.53  5783.3  507.54  6032.9  509.81  6286.2  508.37
#Mann=3,-1,0
  3972.6    0.05       0  5730.7    0.03       0  5734.7    0.05       0
Bank Sta=5730.7,5734.7
Exp/Cntr=0.3,0.1

Type RM Length L Ch R = 1,2306,274,274,274
BEGIN DESCRIPTION:
Mapping XS 19d02259
END DESCRIPTION:
XS GIS Cut Line= 6
      2656837.17      6971307.19      2656990.82      6970937.38
      2657009.05      6970846.23      2656829.37      6970296.75
      2656634.05      6969775.92      2655929.66      6969643.36
#Sta/Elev= 30
  3937.1  508.15  4384.6  506.07  4687.3  498.97  4718.7  498.54  4724.0  501.45
  4750.1  498.43  4755.4  500.92  4812.9  497.20  4818.2  500.74  4844.3  497.27
  4849.6  500.29  4907.1  496.48  4912.4  499.51  4999.4  495.85  4999.6  495.35
  5003.4  495.85  5006.2  498.18  5087.0  496.45  5092.3  499.03  5117.2  496.31
  5147.5  498.98  5172.4  496.60  5177.7  498.98  5335.3  498.25  5613.8  506.62
  5723.8  505.98  5756.4  501.71  5781.4  502.18  5807.3  507.49  6281.8  508.17
#Mann=3,-1,0
  3937.1    0.05       0  4999.4    0.04       0  5003.4    0.05       0
Bank Sta=4999.4,5003.4
Exp/Cntr=0.3,0.1

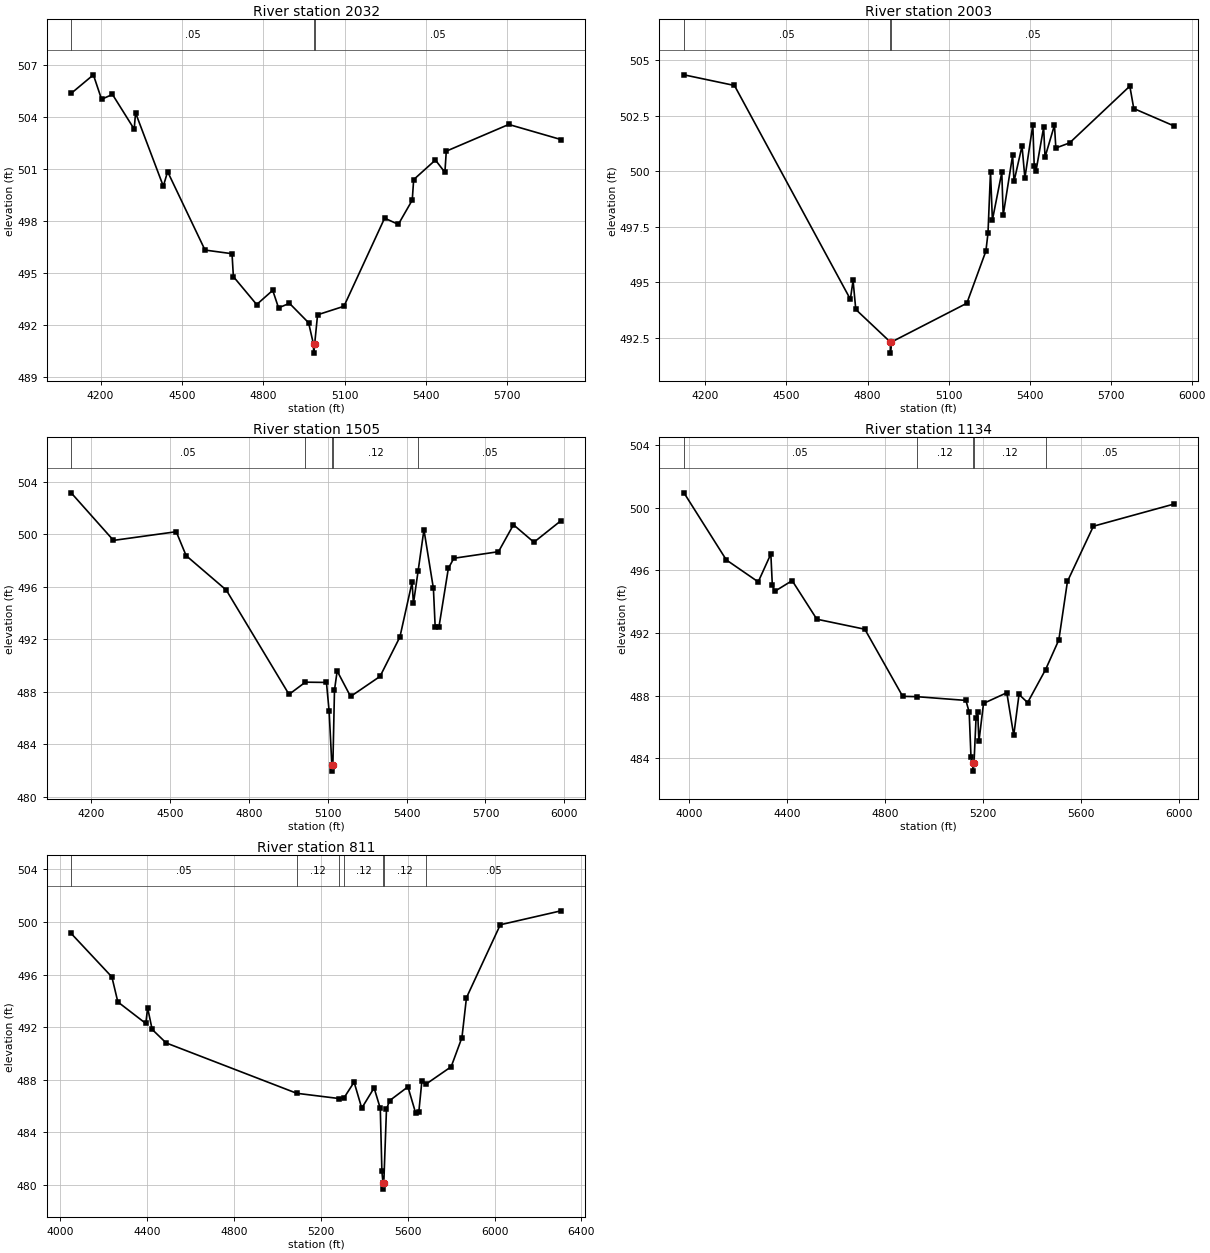
Type RM Length L Ch R = 1,2032,29,29,29
BEGIN DESCRIPTION:
Mapping XS fdb4c8e4
END DESCRIPTION:
XS GIS Cut Line= 6
      2657063.74      6971072.61      2657029.89      6970721.02
      2657003.85      6970385.08      2657032.49      6970158.52
      2657029.89      6969887.68      2656871.04      6969291.36
#Sta/Elev= 30
  4091.4  505.37  4173.4  506.44  4203.5  505.03  4243.7  505.31  4323.9  503.31
  4328.9  504.25  4431.3  500.02  4447.1  500.86  4585.1  496.34  4684.7  496.13
  4689.7  494.81  4775.6  493.20  4834.8  494.02  4856.2  493.01  4896.6  493.27
  4967.1  492.15  4985.3  490.90  4985.5  490.40  4989.3  490.90  5000.2  492.61
  5097.5  493.10  5247.5  498.18  5298.0  497.82  5349.4  499.22  5354.6  500.40
  5434.8  501.53  5469.8  500.82  5474.9  502.04  5705.3  503.58  5897.9  502.71
#Mann=3,-1,0
  4091.4    0.05       0  4985.3    0.03       0  4989.3    0.05       0
Bank Sta=4985.3,4989.3
Exp/Cntr=0.3,0.1

Type RM Length L Ch R = 1,2003,498,498,498
BEGIN DESCRIPTION:
Mapping XS 7b75932b
END DESCRIPTION:
XS GIS Cut Line= 6
      2657121.02      6971062.11      2657061.14      6970697.58
      2657050.72      6970205.39      2657081.97      6969931.95
      2657014.26      6969679.35      2656910.58      6969277.57
#Sta/Elev= 30
  4120.4  504.35  4307.3  503.87  4736.5  494.23  4746.5  495.08  4756.5  493.77
  4884.5  492.30  4884.7  491.80  4888.5  492.30  5167.7  494.05  5238.2  496.40
  5246.0  497.21  5255.3  499.98  5262.3  497.80  5297.1  499.95  5302.3  498.02
  5337.2  500.72  5342.3  499.54  5372.0  501.14  5382.6  499.70  5412.0  502.09
  5417.2  500.22  5424.0  500.03  5452.0  501.98  5457.2  500.64  5492.1  502.08
  5497.2  501.05  5548.1  501.28  5771.1  503.84  5785.7  502.83  5933.8  502.05
#Mann=3,-1,0
  4120.4    0.05       0  4884.5    0.03       0  4888.5    0.05       0
Bank Sta=4884.5,4888.5
Exp/Cntr=0.3,0.1

Type RM Length L Ch R = 1,1505,371,371,371
BEGIN DESCRIPTION:
Mapping XS de42fe58
END DESCRIPTION:
XS GIS Cut Line= 4
      2657170.98      6971046.26      2657498.09      6970238.54
      2657586.16      6969790.63      2657231.35      6969390.52
#Sta/Elev= 30
  4124.4  503.14  4285.4  499.52  4524.0  500.18  4561.6  498.36  4714.3  495.74
  4952.9  487.80  5015.1  488.73  5095.2  488.71  5105.4  486.53  5115.7  482.46
  5115.9  481.96  5119.7  482.46  5125.8  488.13  5136.0  489.58  5187.0  487.64
  5299.1  489.17  5374.6  492.17  5420.9  496.34  5426.0  494.72  5443.6  497.16
  5466.0  500.33  5502.0  495.86  5508.7  492.94  5522.9  492.91  5558.8  497.39
  5579.7  498.16  5749.5  498.66  5806.4  500.71  5884.2  499.38  5987.1  501.02
#Mann=5,-1,0
  4124.4    0.05       0  5015.1    0.12       0  5115.7    0.05       0
  5119.7    0.12       0  5443.6    0.05       0
Bank Sta=5115.7,5119.7
Exp/Cntr=0.3,0.1

Type RM Length L Ch R = 1,1134,323,323,323
BEGIN DESCRIPTION:
Mapping XS 54bb0c2c
END DESCRIPTION:
XS GIS Cut Line= 5
      2657238.93      6971043.74      2657633.97      6970424.75
      2657845.35      6970220.92      2657898.19      6970027.16
      2657374.77      6969458.45
#Sta/Elev= 30
  3978.0  500.94  4151.2  496.66  4281.5  495.26  4333.1  497.04  4339.1  495.07
  4348.3  494.65  4420.2  495.34  4521.0  492.88  4717.2  492.24  4871.9  487.96
  4928.5  487.94  5130.3  487.70  5143.6  486.95  5151.0  484.08  5159.3  483.69
  5159.6  483.19  5163.3  483.69  5171.7  486.59  5178.2  486.99  5183.4  485.08
  5202.2  487.51  5297.4  488.19  5325.7  485.47  5347.3  488.08  5382.4  487.56
  5455.9  489.67  5510.0  491.56  5545.2  495.29  5651.2  498.81  5979.7  500.22
#Mann=5,-1,0
  3978.0    0.05       0  4928.5    0.12       0  5159.3    0.07       0
  5163.3    0.12       0  5455.9    0.05       0
Bank Sta=5159.3,5163.3
Exp/Cntr=0.3,0.1

Type RM Length L Ch R = 1,811,0,0,0
BEGIN DESCRIPTION:
Mapping XS 3375204d
END DESCRIPTION:
XS GIS Cut Line= 4
      2657304.33      6971031.18      2657895.67      6970585.79
      2658139.76      6970218.41      2657432.67      6969410.66
#Sta/Elev= 30
  4051.1  499.13  4238.6  495.82  4266.0  493.92  4394.8  492.28  4403.1  493.47
  4423.9  491.83  4488.5  490.80  5089.6  486.97  5285.0  486.57  5307.8  486.64
  5353.7  487.82  5388.8  485.84  5445.7  487.38  5474.2  485.82  5481.6  481.03
  5486.4  480.18  5486.7  479.68  5490.4  480.18  5502.7  485.75  5516.9  486.41
  5601.4  487.46  5637.5  485.44  5651.7  485.57  5665.9  487.94  5684.0  487.66
  5800.5  488.99  5850.1  491.21  5870.9  494.24  6026.6  499.79  6306.0  500.85
#Mann=7,-1,0
  4051.1    0.05       0  5089.6    0.12       0  5285.0    0.05       0
  5307.8    0.12       0  5486.4    0.05       0  5490.4    0.12       0
  5684.0    0.05       0
Bank Sta=5486.4,5490.4
Exp/Cntr=0.3,0.1

Chan Stop Cuts=-1