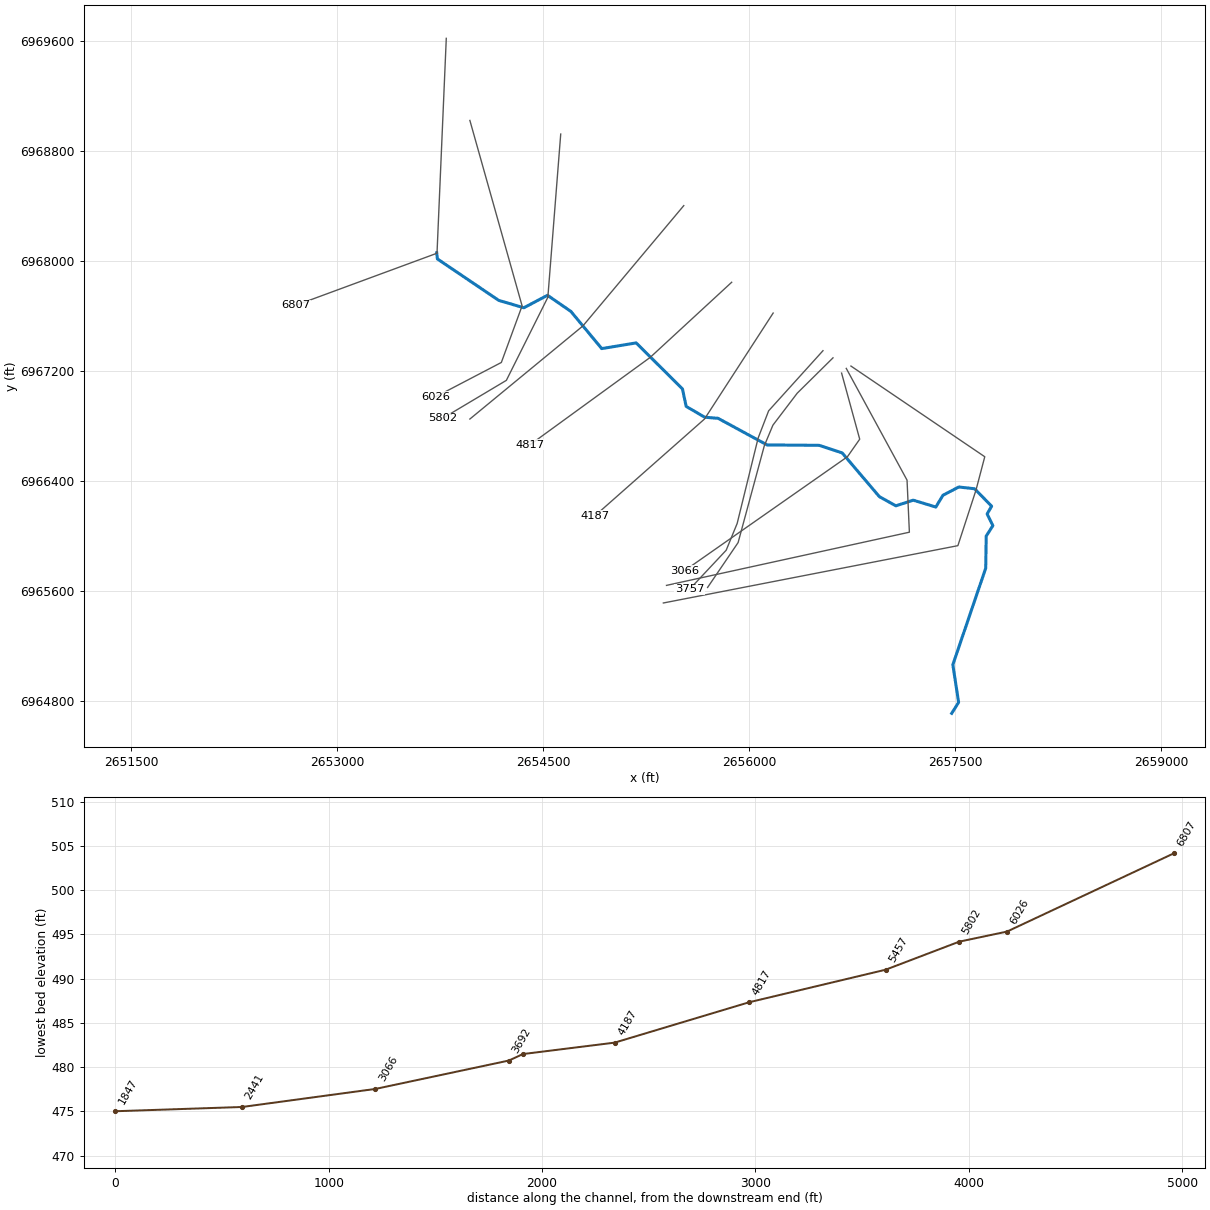
--- Kings Creek Trib 6.prj (project) ---

Proj Title=Kings Creek Trib 6 Base Level Engineering
Current Plan=p01
Default Exp/Contr=0.3,0.1
English Units
Geom File=g01
Flow File=f01
Plan File=p01
BEGIN DESCRIPTION:
Kings Creek Trib 6
END DESCRIPTION:

--- Kings Creek Trib 6.p01 (plan) ---

Plan Title=Multiple Run
Short Identifier=Multiple
Geom File=g01
Flow File=f01
Subcritical Flow
K Sum by GR= 0
Std Step Tol= 0.01
Critical Tol= 0.01
Num of Std Step Trials= 20
Max Error Tol= 0.3
Flow Tol Ratio= 0.001
Split Flow NTrial= 30
Split Flow Tol= 0.02
Split Flow Ratio= 0.02
Log Output Level= 0
Friction Slope Method= 1
Unsteady Friction Slope Method= 2
Unsteady Bridges Friction Slope Method= 1
Parabolic Critical Depth
Global Vel Dist=  1 , 1 , 1
Global Log Level= 0
CheckData=True
Encroach Param= -1, 0, 0, 0
BEGIN DESCRIPTION:
Multiple Run
END DESCRIPTION:

--- Kings Creek Trib 6.f01 (steady flow) ---

Flow Title=Multiple
Number of Profiles=7
Profile Names=10-year,25-year,50-year,1pct_min,100-year,1pct_plu,500-year
River Rch & RM= Kings Creek Trib,Reach-1,6807
     403     529     628     371     740    1476    1025
River Rch & RM= Kings Creek Trib,Reach-1,4187
     502     667     799     476     950    1895    1339
River Rch & RM= Kings Creek Trib,Reach-1,3692
     670     905    1097     659    1315    2624    1890
Boundary for River Rch & Prof#=Kings Creek Trib,Reach-1,1
Up Type=0
Dn Type=3
Dn Slope=0.005
Boundary for River Rch & Prof#=Kings Creek Trib,Reach-1,2
Up Type=0
Dn Type=3
Dn Slope=0.005
Boundary for River Rch & Prof#=Kings Creek Trib,Reach-1,3
Up Type=0
Dn Type=3
Dn Slope=0.005
Boundary for River Rch & Prof#=Kings Creek Trib,Reach-1,4
Up Type=0
Dn Type=3
Dn Slope=0.005
Boundary for River Rch & Prof#=Kings Creek Trib,Reach-1,5
Up Type=0
Dn Type=3
Dn Slope=0.005
Boundary for River Rch & Prof#=Kings Creek Trib,Reach-1,6
Up Type=0
Dn Type=3
Dn Slope=0.005
Boundary for River Rch & Prof#=Kings Creek Trib,Reach-1,7
Up Type=0
Dn Type=3
Dn Slope=0.005

--- Kings Creek Trib 6.g01 (geometry) ---

Geom Title=Existing Conditions

River Reach=Kings Creek Trib,Reach-1
Reach XY= 30
      2653726.00      6968061.00      2653730.92      6968016.32
      2654177.58      6967714.82      2654360.61      6967661.08
      2654532.72      6967751.87      2654702.82      6967634.71
      2654927.62      6967364.12      2655178.45      6967405.55
      2655515.48      6967070.78      2655542.30      6966943.87
      2655677.58      6966864.82      2655774.42      6966857.17
      2656131.93      6966663.24      2656510.78      6966660.48
      2656678.44      6966605.48      2656949.18      6966287.29
      2657069.38      6966220.41      2657196.04      6966261.58
      2657360.10      6966211.54      2657412.46      6966297.45
      2657527.58      6966357.33      2657642.76      6966344.60
      2657766.70      6966217.67      2657733.84      6966161.09
      2657775.85      6966076.42      2657727.24      6966000.50
      2657723.74      6965766.94      2657484.27      6965064.22
      2657526.39      6964790.87      2657476.00      6964711.00

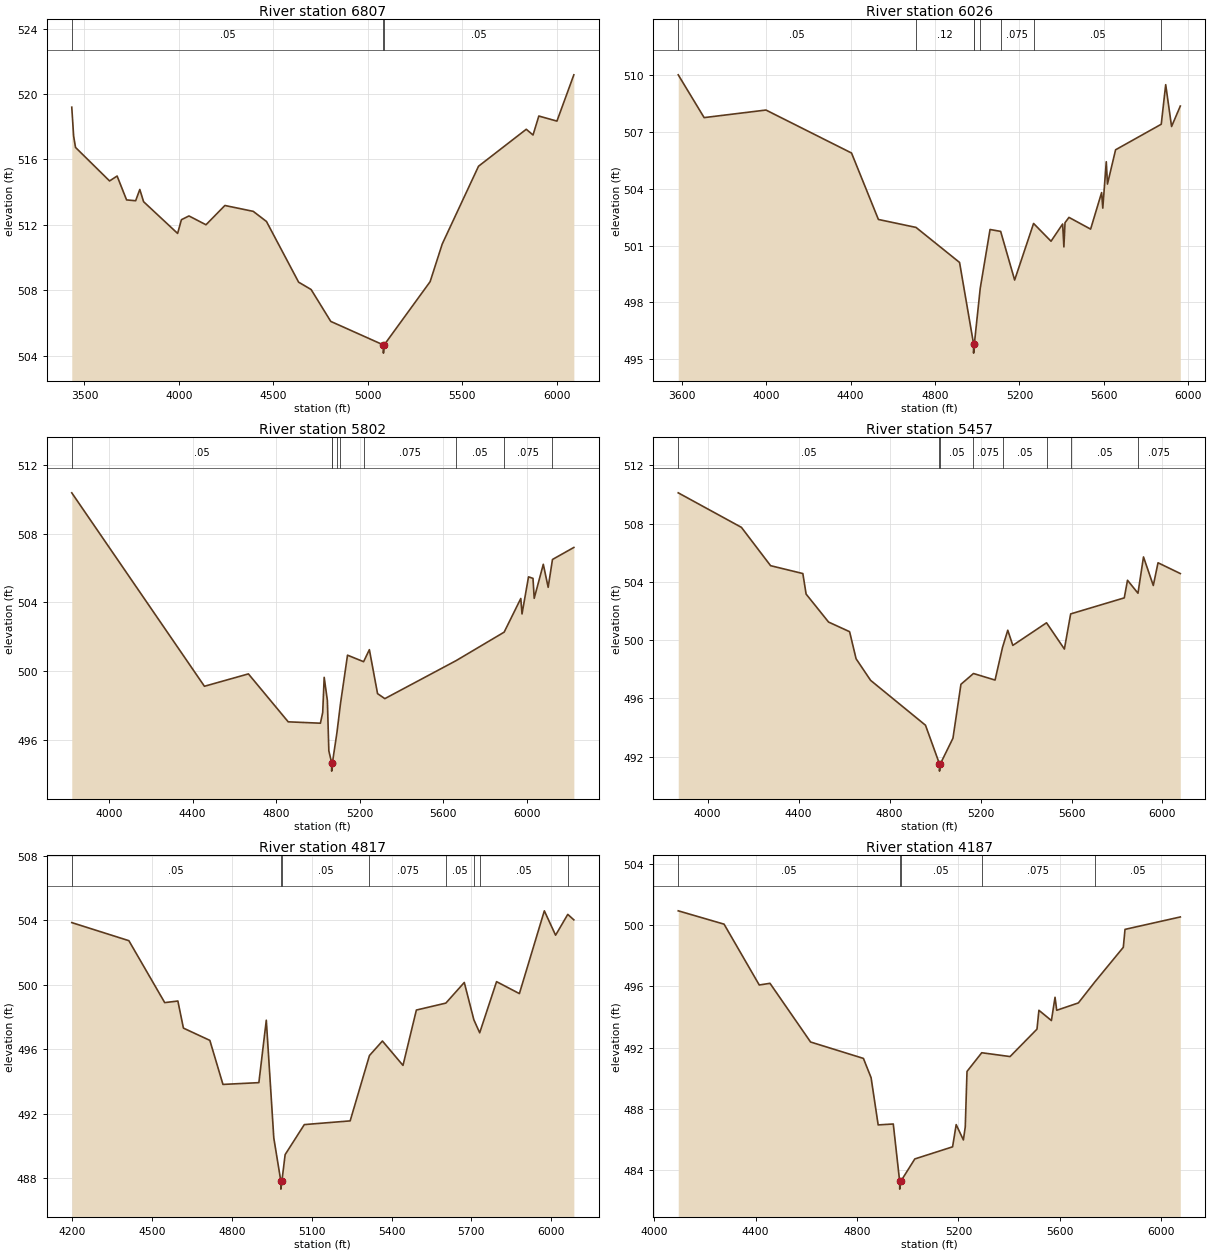
Type RM Length L Ch R = 1,6807,781,781,781
BEGIN DESCRIPTION:
Kings Creek Trib 6 13.0
END DESCRIPTION:
XS GIS Cut Line= 3
      2653795.72      6969620.91      2653728.22      6968057.87
      2652702.00      6967679.93
#Sta/Elev= 30
  3433.0  519.19  3442.9  517.42  3452.9  516.73  3633.1  514.68  3673.1  514.98
  3723.2  513.52  3771.2  513.47  3793.2  514.16  3813.3  513.41  3993.4  511.47
  4013.5  512.31  4053.5  512.54  4143.6  512.00  4243.7  513.18  4393.8  512.82
  4463.9  512.20  4634.0  508.49  4700.2  508.04  4804.2  506.09  5082.8  504.65
  5083.0  504.15  5086.8  504.65  5330.2  508.52  5394.2  510.82  5586.5  515.58
  5839.2  517.84  5875.0  517.49  5905.7  518.65  6001.6  518.34  6091.1  521.17
#Mann=3,-1,0
  3433.0    0.05       0  5082.8    0.04       0  5086.8    0.05       0
Bank Sta=5082.8,5086.8
Exp/Cntr=0.3,0.1

Type RM Length L Ch R = 1,6026,224,224,224
BEGIN DESCRIPTION:
Mapping XS beda3161
END DESCRIPTION:
XS GIS Cut Line= 4
      2653967.60      6969023.63      2654347.80      6967674.71
      2654196.76      6967263.25      2653719.32      6967014.15
#Sta/Elev= 30
  3583.9  510.02  3706.6  507.76  3999.5  508.16  4404.8  505.89  4532.1  502.38
  4710.3  501.96  4916.5  500.11  4982.7  495.82  4983.0  495.32  4986.7  495.82
  5014.4  498.74  5060.9  501.85  5111.2  501.75  5177.5  499.18  5267.1  502.17
  5349.8  501.23  5404.8  502.14  5410.7  500.93  5416.1  502.21  5434.8  502.49
  5537.3  501.87  5589.4  503.80  5595.0  502.98  5611.5  505.43  5617.1  504.25
  5655.6  506.06  5871.9  507.41  5893.0  509.50  5920.8  507.29  5962.2  508.37
#Mann=8,-1,0
  3583.9    0.05       0  4710.3    0.12       0  4982.7    0.07       0
  4986.7    0.12       0  5014.4    0.05       0  5111.2   0.075       0
  5267.1    0.05       0  5871.9   0.075       0
Bank Sta=4982.7,4986.7
Exp/Cntr=0.3,0.1

Type RM Length L Ch R = 1,5802,345,345,345
BEGIN DESCRIPTION:
Mapping XS b48aa026
END DESCRIPTION:
XS GIS Cut Line= 4
      2654629.05      6968924.66      2654535.30      6967737.21
      2654233.22      6967133.04      2653770.31      6966857.38
#Sta/Elev= 30
  3821.4  510.38  4457.0  499.12  4667.7  499.84  4858.3  497.05  5012.6  496.97
  5023.6  497.59  5030.7  499.64  5046.0  498.29  5053.0  495.36  5066.3  494.68
  5066.6  494.18  5070.3  494.68  5091.8  496.42  5108.8  498.11  5142.5  500.93
  5219.5  500.55  5247.2  501.25  5286.4  498.69  5321.4  498.40  5662.5  500.61
  5892.9  502.27  5972.7  504.23  5978.5  503.33  6009.7  505.49  6031.1  505.40
  6036.9  504.24  6080.5  506.22  6103.8  504.88  6124.4  506.50  6226.8  507.20
#Mann=9,-1,0
  3821.4    0.05       0  5066.3    0.03       0  5070.3    0.05       0
  5091.8    0.12       0  5108.8    0.05       0  5219.5   0.075       0
  5662.5    0.05       0  5892.9   0.075       0  6124.4    0.05       0
Bank Sta=5066.3,5070.3
Exp/Cntr=0.3,0.1

Type RM Length L Ch R = 1,5457,640,640,640
BEGIN DESCRIPTION:
Mapping XS 74356e16
END DESCRIPTION:
XS GIS Cut Line= 3
      2655524.91      6968403.90      2654790.51      6967528.87
      2653967.62      6966851.81
#Sta/Elev= 30
  3870.5  510.11  4148.4  507.74  4276.7  505.11  4418.5  504.57  4432.9  503.16
  4531.7  501.24  4624.1  500.58  4652.7  498.72  4716.5  497.24  4957.9  494.16
  5019.3  491.51  5019.5  491.01  5023.3  491.51  5078.7  493.27  5113.8  496.97
  5168.9  497.71  5263.8  497.26  5296.6  499.50  5319.7  500.68  5341.9  499.64
  5490.2  501.19  5568.7  499.39  5596.3  501.80  5832.0  502.90  5846.3  504.11
  5892.3  503.22  5916.6  505.71  5959.7  503.75  5980.5  505.31  6078.5  504.57
#Mann=8,-1,0
  3870.5    0.05       0  5019.3    0.05       0  5023.3    0.05       0
  5168.9   0.075       0  5296.6    0.05       0  5490.2   0.075       0
  5596.3    0.05       0  5892.3   0.075       0
Bank Sta=5019.3,5023.3
Exp/Cntr=0.3,0.1

Type RM Length L Ch R = 1,4817,630,630,630
BEGIN DESCRIPTION:
Mapping XS a3b830e7
END DESCRIPTION:
XS GIS Cut Line= 3
      2655873.85      6967846.58      2655280.09      6967299.71
      2654406.23      6966665.12
#Sta/Elev= 30
  4197.9  503.85  4412.5  502.73  4547.3  498.89  4596.7  498.99  4617.6  497.31
  4716.9  496.55  4766.2  493.82  4901.2  493.93  4929.1  497.80  4957.3  490.50
  4983.7  487.83  4983.9  487.33  4987.7  487.83  4999.9  489.47  5072.0  491.33
  5244.3  491.56  5316.8  495.61  5365.6  496.51  5442.9  495.00  5493.2  498.43
  5604.0  498.86  5673.3  500.14  5709.2  497.83  5731.2  497.02  5794.6  500.19
  5880.4  499.45  5974.2  504.58  6016.5  503.07  6062.3  504.36  6085.1  504.02
#Mann=8,-1,0
  4197.9    0.05       0  4983.7    0.03       0  4987.7    0.05       0
  5316.8   0.075       0  5604.0    0.05       0  5709.2   0.075       0
  5731.2    0.05       0  6062.3   0.075       0
Bank Sta=4983.7,4987.7
Exp/Cntr=0.3,0.1

Type RM Length L Ch R = 1,4187,430,430,430
BEGIN DESCRIPTION:
Mapping XS 49fe3451
END DESCRIPTION:
XS GIS Cut Line= 3
      2656175.94      6967622.64      2655675.93      6966851.79
      2654879.99      6966149.49
#Sta/Elev= 30
  4094.6  500.93  4275.4  500.06  4414.2  496.09  4456.5  496.20  4616.6  492.37
  4825.0  491.30  4855.3  490.04  4883.2  486.96  4942.8  487.02  4968.0  483.27
  4968.2  482.77  4972.0  483.27  5027.7  484.74  5176.7  485.53  5190.9  486.98
  5219.3  485.98  5226.7  486.83  5233.6  490.45  5291.7  491.67  5403.4  491.42
  5509.6  493.21  5517.2  494.44  5566.5  493.77  5580.8  495.29  5587.4  494.44
  5672.8  494.92  5737.8  496.29  5850.1  498.55  5856.8  499.72  6074.9  500.53
#Mann=5,-1,0
  4094.6    0.05       0  4968.0    0.03       0  4972.0    0.05       0
  5291.7   0.075       0  5737.8    0.05       0
Bank Sta=4968,4972
Exp/Cntr=0.3,0.1

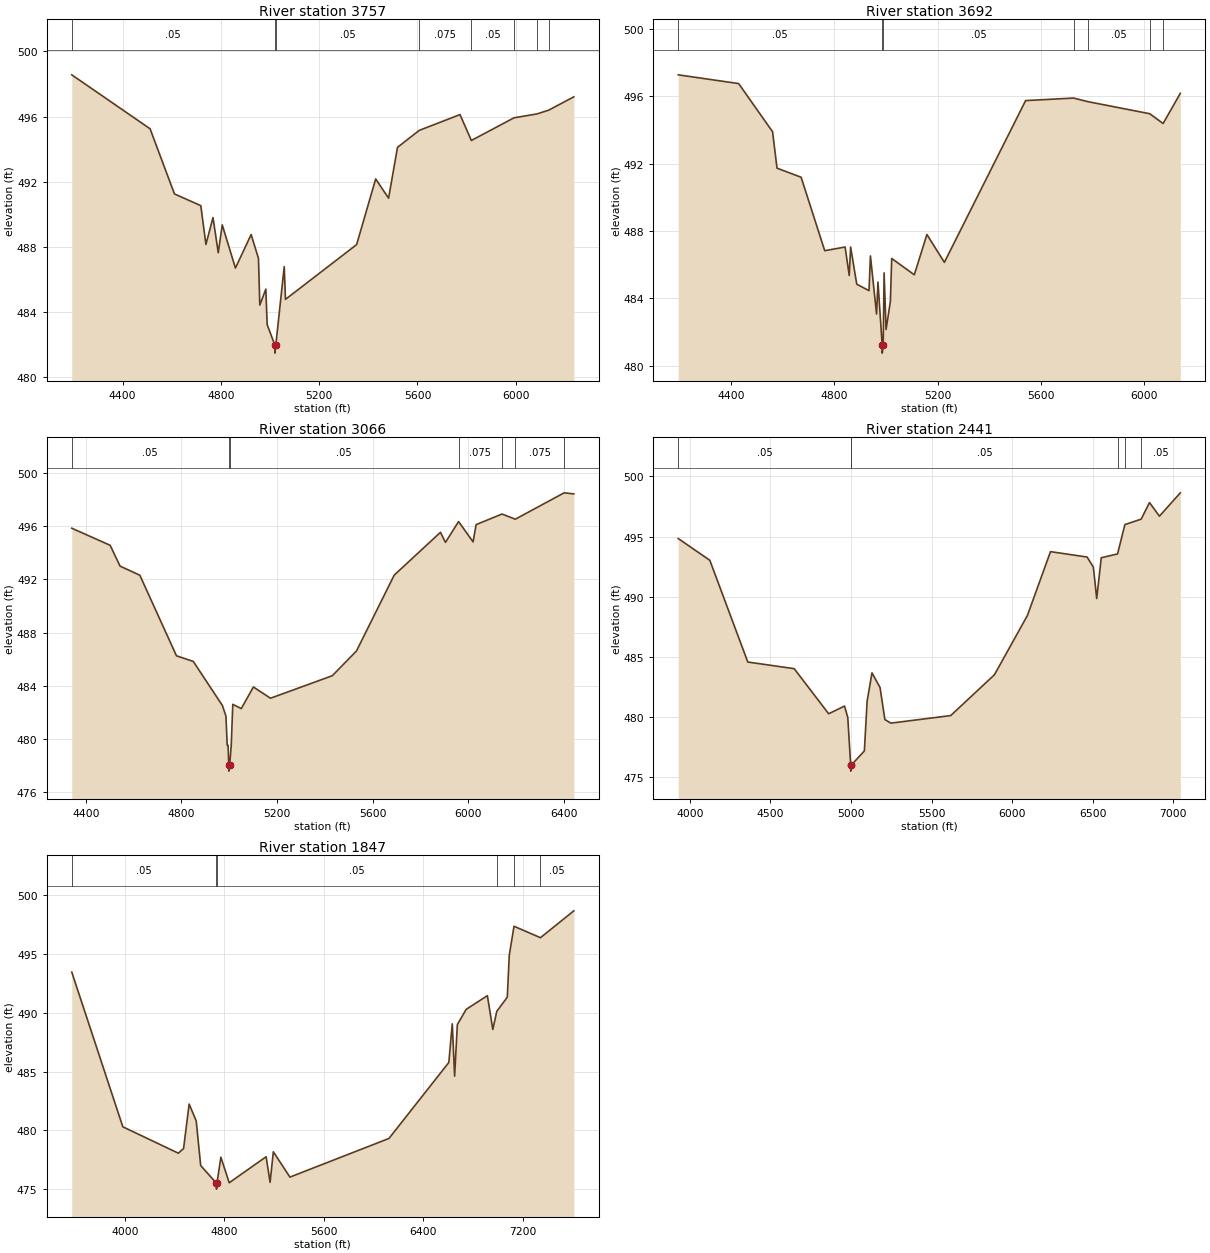
Type RM Length L Ch R = 1,3757,65,65,65
BEGIN DESCRIPTION:
Mapping XS 868db154
END DESCRIPTION:
XS GIS Cut Line= 6
      2656538.77      6967348.89      2656142.94      6966911.40
      2656066.55      6966713.48      2655913.77      6966091.95
      2655833.91      6965897.51      2655566.54      6965612.78
#Sta/Elev= 30
  4192.8  498.56  4511.5  495.25  4610.9  491.25  4718.1  490.53  4738.9  488.15
  4767.7  489.80  4789.1  487.64  4805.4  489.35  4859.0  486.70  4922.9  488.76
  4952.8  487.29  4958.2  484.43  4982.8  485.41  4988.1  483.23  5019.4  481.98
  5019.6  481.48  5023.4  481.98  5057.6  486.79  5062.7  484.78  5352.3  488.14
  5429.9  492.17  5482.4  490.99  5518.7  494.11  5607.2  495.15  5773.2  496.12
  5819.3  494.53  5992.7  495.92  6086.3  496.16  6133.8  496.39  6236.5  497.21
#Mann=8,-1,0
  4192.8    0.05       0  5019.4    0.03       0  5023.4    0.05       0
  5607.2   0.075       0  5819.3    0.05       0  5992.7   0.075       0
  6086.3     0.1       0  6133.8    0.05       0
Bank Sta=5019.4,5023.4
Exp/Cntr=0.3,0.1

Type RM Length L Ch R = 1,3692,626,626,626
BEGIN DESCRIPTION:
Mapping XS f926b353
END DESCRIPTION:
XS GIS Cut Line= 6
      2656611.65      6967296.78      2656351.27      6967039.87
      2656174.19      6966807.23      2656111.69      6966657.92
      2655920.72      6965953.06      2655698.48      6965626.65
#Sta/Elev= 30
  4194.3  497.27  4428.6  496.75  4560.1  493.89  4577.3  491.73  4670.8  491.19
  4762.3  486.83  4841.3  487.05  4857.3  485.36  4862.7  487.05  4886.5  484.84
  4934.0  484.46  4939.5  486.52  4963.3  483.07  4968.7  484.97  4985.0  481.25
  4985.3  480.75  4989.0  481.25  4992.5  485.51  5000.1  482.15  5016.9  483.82
  5022.0  486.37  5109.6  485.40  5158.5  487.79  5226.2  486.14  5541.2  495.74
  5727.4  495.89  5781.9  495.68  6022.6  494.96  6074.3  494.38  6141.0  496.17
#Mann=7,-1,0
  4194.3    0.05       0  4985.0    0.03       0  4989.0    0.05       0
  5727.4   0.075       0  5781.9    0.05       0  6022.6   0.075       0
  6074.3     0.1       0
Bank Sta=4985,4989
Exp/Cntr=0.3,0.1

Type RM Length L Ch R = 1,3066,625,625,625
BEGIN DESCRIPTION:
Mapping XS dbe0a53b
END DESCRIPTION:
XS GIS Cut Line= 4
      2656674.23      6967185.97      2656806.14      6966705.14
      2656716.78      6966577.48      2655530.28      6965748.21
#Sta/Elev= 30
  4340.9  495.87  4501.6  494.58  4543.1  493.01  4626.0  492.32  4779.3  486.24
  4849.6  485.82  4971.6  482.49  4986.4  481.69  4991.6  479.49  4995.3  479.49
  4998.1  478.04  4998.4  477.54  5002.1  478.04  5008.5  479.48  5015.0  482.58
  5050.7  482.26  5101.3  483.89  5172.8  483.04  5431.8  484.74  5533.0  486.61
  5690.9  492.33  5884.5  495.56  5905.4  494.80  5960.3  496.37  6021.1  494.84
  6033.6  496.14  6142.1  496.94  6197.9  496.55  6402.3  498.54  6442.9  498.46
#Mann=7,-1,0
  4340.9    0.05       0  4998.1    0.04       0  5002.1    0.05       0
  5960.3   0.075       0  6142.1    0.05       0  6197.9   0.075       0
  6402.3    0.05       0
Bank Sta=4998.1,5002.1
Exp/Cntr=0.3,0.1

Type RM Length L Ch R = 1,2441,594,594,594
BEGIN DESCRIPTION:
Mapping XS 75cb56de
END DESCRIPTION:
XS GIS Cut Line= 4
      2656708.27      6967220.01      2657150.81      6966407.28
      2657167.83      6966028.56      2655399.35      6965641.71
#Sta/Elev= 30
  3928.7  494.84  4124.7  493.03  4360.3  484.57  4648.0  484.02  4861.9  480.27
  4960.5  480.91  4980.5  479.96  4998.5  476.00  4998.8  475.50  5002.5  476.00
  5083.4  477.18  5100.6  481.32  5130.7  483.67  5180.7  482.45  5210.7  479.79
  5247.8  479.49  5619.2  480.12  5890.2  483.51  6094.9  488.44  6238.2  493.75
  6465.2  493.30  6504.0  492.47  6524.9  489.85  6553.0  493.24  6654.2  493.56
  6699.7  496.00  6800.5  496.45  6852.4  497.83  6913.9  496.70  7043.5  498.64
#Mann=6,-1,0
  3928.7    0.05       0  4998.5    0.04       0  5002.5    0.05       0
  6654.2   0.075       0  6699.7     0.1       0  6800.5    0.05       0
Bank Sta=4998.5,5002.5
Exp/Cntr=0.3,0.1

Type RM Length L Ch R = 1,1847,0,0,0
BEGIN DESCRIPTION:
Kings Creek Trib 6 6.0
END DESCRIPTION:
XS GIS Cut Line= 5
      2656742.28      6967237.06      2657716.75      6966577.48
      2657652.87      6966334.85      2657521.01      6965930.69
      2655376.40      6965513.69
#Sta/Elev= 30
  3572.4  493.44  3983.0  480.31  4429.4  478.07  4471.4  478.46  4516.3  482.24
  4573.2  480.81  4609.2  477.02  4736.0  475.52  4736.3  475.02  4740.0  475.52
  4771.5  477.73  4838.5  475.56  5135.3  477.77  5167.2  475.60  5193.4  478.19
  5326.7  476.04  6123.0  479.32  6604.6  485.77  6632.3  489.05  6651.2  484.61
  6673.1  488.99  6744.4  490.28  6914.6  491.44  6958.3  488.57  6990.2  490.11
  7074.7  491.31  7090.8  494.88  7128.8  497.33  7341.5  496.36  7609.9  498.64
#Mann=6,-1,0
  3572.4    0.05       0  4736.0    0.04       0  4740.0    0.05       0
  6990.2   0.075       0  7128.8     0.1       0  7341.5    0.05       0
Bank Sta=4736,4740
Exp/Cntr=0.3,0.1

Chan Stop Cuts=-1