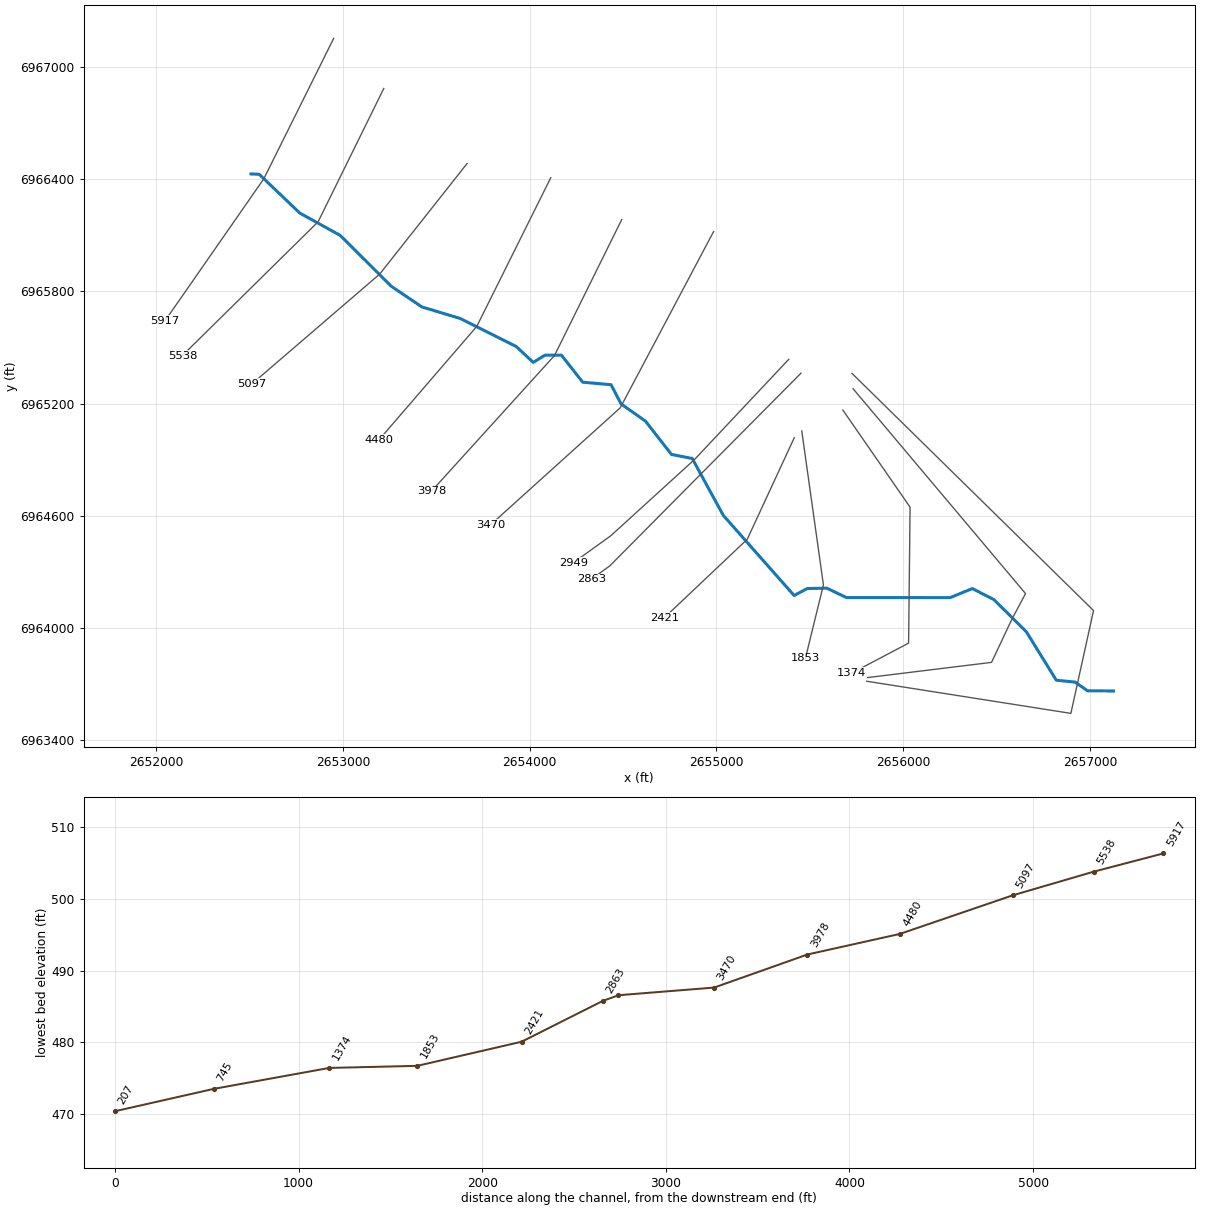
--- Kings Creek Trib 7.prj (project) ---

Proj Title=Kings Creek Trib 7 Base Level Engineering
Current Plan=p01
Default Exp/Contr=0.3,0.1
English Units
Geom File=g01
Flow File=f01
Plan File=p01
Y Axis Title=Elevation
X Axis Title(PF)=Main Channel Distance
X Axis Title(XS)=Station
BEGIN DESCRIPTION:
Kings Creek Trib 7
END DESCRIPTION:
DSS Export Rating Curves= 0
DSS Export Rating Curve Sorted= 0
DSS Export Volume Flow Curves= 0
DXF OffsetX= 0
DXF OffsetY= 0
DXF ScaleX= 1
DXF ScaleY= 10

--- Kings Creek Trib 7.p01 (plan) ---

Plan Title=Multiple Run
Short Identifier=Multiple
Geom File=g01
Flow File=f01
Subcritical Flow
K Sum by GR= 0
Std Step Tol= 0.01
Critical Tol= 0.01
Num of Std Step Trials= 20
Max Error Tol= 0.3
Flow Tol Ratio= 0.001
Split Flow NTrial= 30
Split Flow Tol= 0.02
Split Flow Ratio= 0.02
Log Output Level= 0
Friction Slope Method= 1
Unsteady Friction Slope Method= 2
Unsteady Bridges Friction Slope Method= 1
Parabolic Critical Depth
Global Vel Dist=  1 , 1 , 1
Global Log Level= 0
CheckData=True
Encroach Param= -1, 0, 0, 0
BEGIN DESCRIPTION:
Multiple Run
END DESCRIPTION:

--- Kings Creek Trib 7.f01 (steady flow) ---

Flow Title=Multiple
Number of Profiles=7
Profile Names=10-year,25-year,50-year,1pct_min,100-year,1pct_plu,500-year
River Rch & RM= Kings Creek Trib,Reach-1,5917
     376     491     582     343     684    1365     944
River Rch & RM= Kings Creek Trib,Reach-1,2949
     385     503     596     351     701    1398     967
River Rch & RM= Kings Creek Trib,Reach-1,2863
     446     589     702     416     830    1656    1158
River Rch & RM= Kings Creek Trib,Reach-1,207
    2389    3399    4262    2637    5262   10498    8026
Boundary for River Rch & Prof#=Kings Creek Trib,Reach-1,1
Up Type=0
Dn Type=3
Dn Slope=0.005
Boundary for River Rch & Prof#=Kings Creek Trib,Reach-1,2
Up Type=0
Dn Type=3
Dn Slope=0.005
Boundary for River Rch & Prof#=Kings Creek Trib,Reach-1,3
Up Type=0
Dn Type=3
Dn Slope=0.005
Boundary for River Rch & Prof#=Kings Creek Trib,Reach-1,4
Up Type=0
Dn Type=3
Dn Slope=0.005
Boundary for River Rch & Prof#=Kings Creek Trib,Reach-1,5
Up Type=0
Dn Type=3
Dn Slope=0.005
Boundary for River Rch & Prof#=Kings Creek Trib,Reach-1,6
Up Type=0
Dn Type=3
Dn Slope=0.005
Boundary for River Rch & Prof#=Kings Creek Trib,Reach-1,7
Up Type=0
Dn Type=3
Dn Slope=0.005

--- Kings Creek Trib 7.g01 (geometry) ---

Geom Title=Existing Conditions
Program Version=4.10

River Reach=Kings Creek Trib,Reach-1
Reach XY= 30
      2652508.74      6966428.99      2652552.48      6966427.04
        2652770.      6966219.28      2652985.68      6966100.22
      2653259.33      6965827.65      2653423.71      6965716.84
      2653628.32      6965655.23       2653928.3      6965505.14
      2654019.27      6965420.15      2654081.89      6965458.63
      2654170.12      6965459.04      2654284.31      6965314.08
      2654436.12      6965300.65      2654489.63      6965197.78
      2654620.38      6965105.38      2654759.27      6964927.47
      2654870.53      6964905.74      2655036.76      6964601.32
      2655415.94       6964172.1      2655486.44      6964209.62
      2655591.16      6964211.47      2655696.03      6964161.07
      2656251.09      6964160.81      2656369.89       6964209.2
      2656485.68      6964150.24      2656659.35      6963977.67
      2656819.55      6963718.74      2656920.02      6963708.64
      2656986.48      6963662.17        2657126.        6963661.

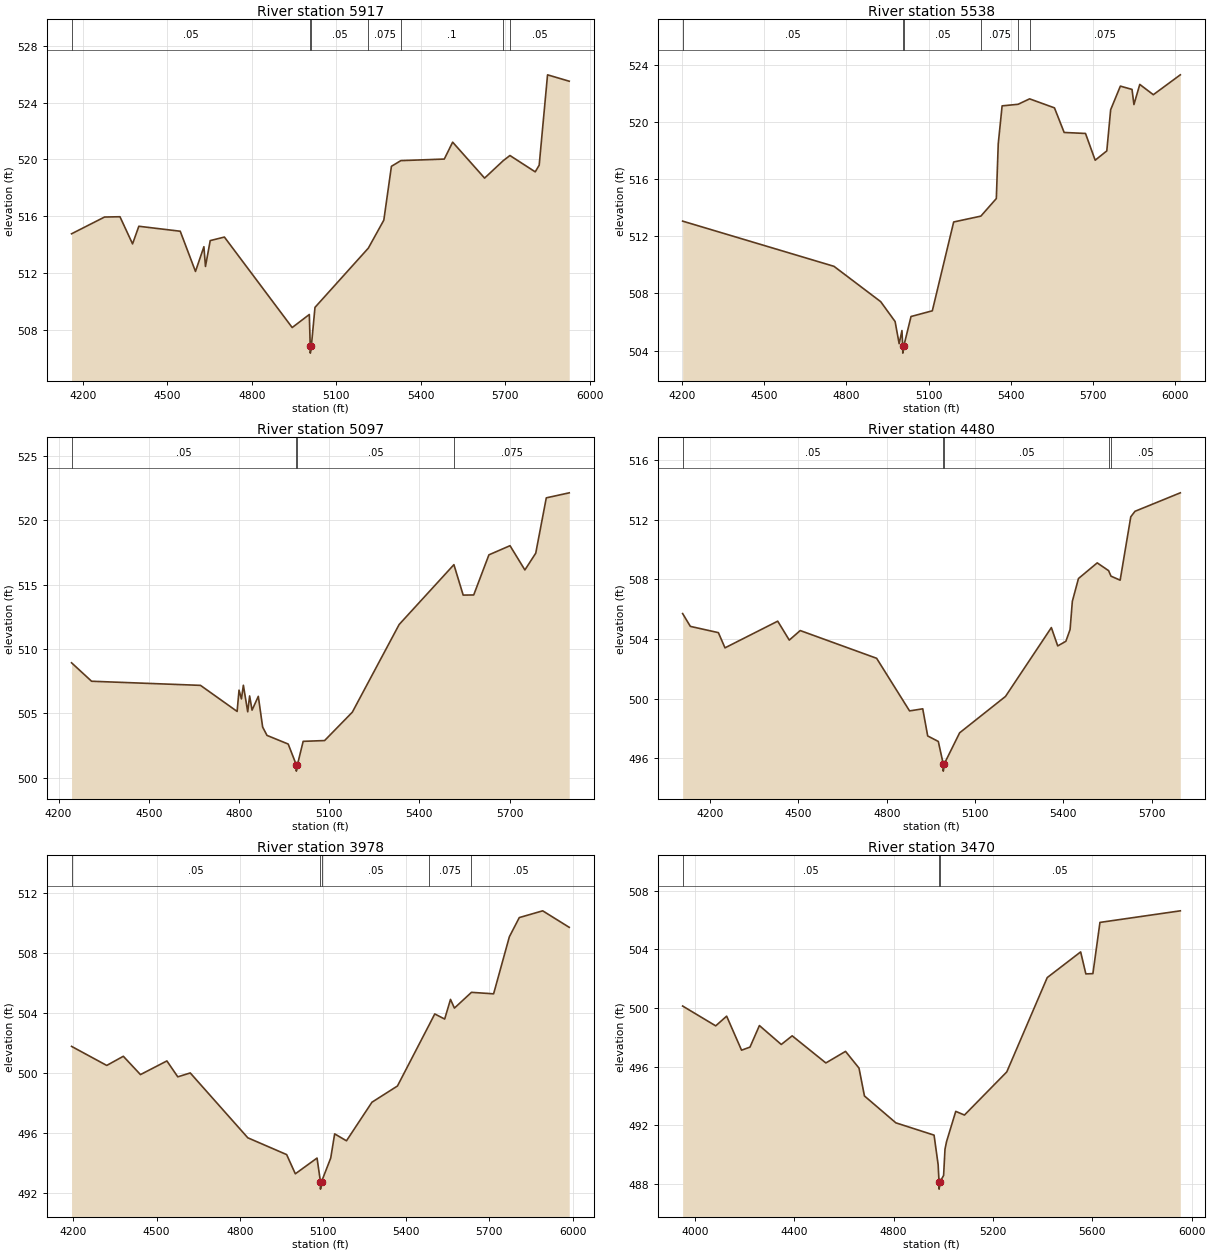
Type RM Length L Ch R = 1 ,5917    ,379,379,379
BEGIN DESCRIPTION:
Kings Creek Trib 7 11.0
END DESCRIPTION:
XS GIS Cut Line= 3
      2652951.25      6967154.89        2652577.      6966402.87
      2652047.61       6965641.9
#Sta/Elev= 30
    4160  514.77  4277.2  515.95  4331.9  515.97  4376.6  514.06  4398.9   515.3
  4545.9  514.95    4600  512.12  4629.9  513.86  4635.5  512.47  4652.3  514.29
  4702.7  514.54  4943.4  508.17  5004.2  509.09  5007.4  506.87  5007.7  506.37
  5011.4  506.87  5024.3  509.59  5213.7  513.76  5268.7  515.73  5295.7  519.52
  5329.1  519.92  5483.4  520.03  5513.1  521.22  5626.5  518.69  5692.8  519.92
  5716.5  520.28  5806.3  519.13  5820.3   519.6    5850  525.96    5927  525.51
#Mann= 7 ,-1 , 0
    4160     .05       0  5007.4     .03       0  5011.4     .05       0
  5213.7    .075       0  5329.1      .1       0  5692.8    .075       0
  5716.5     .05       0
Bank Sta=5007.4,5011.4
XS Rating Curve= 0 ,0
Exp/Cntr=0.3,0.1

Type RM Length L Ch R = 1 ,5538    ,441,441,441
BEGIN DESCRIPTION:
Mapping XS 7f2ab775
END DESCRIPTION:
XS GIS Cut Line= 3
      2653219.24      6966886.26      2652867.68      6966172.74
      2652141.13       6965456.6
#Sta/Elev= 30
  4202.3  513.06  4754.4   509.9  4924.8  507.43  4977.4  506.04  4992.2  504.49
  5002.4  505.41  5005.2  504.33  5005.5  503.83  5009.2  504.33  5035.5  506.39
  5113.2  506.79  5191.1     513  5290.3  513.41  5346.7  514.64  5353.7  518.47
  5367.8  521.12  5426.2  521.23  5468.1  521.61  5558.8  520.98  5594.1  519.26
    5672  519.19  5707.3  517.32  5749.7  517.97  5763.8  520.85  5799.2   522.5
  5841.7  522.27  5848.7  521.21    5870  522.62  5919.4   521.9  6017.9  523.29
#Mann= 6 ,-1 , 0
  4202.3     .05       0  5005.2     .03       0  5009.2     .05       0
  5290.3    .075       0  5426.2      .1       0  5468.1    .075       0
Bank Sta=5005.2,5009.2
XS Rating Curve= 0 ,0
Exp/Cntr=0.3,0.1

Type RM Length L Ch R = 1 ,5097    ,617,617,617
BEGIN DESCRIPTION:
Mapping XS c53ceeaf
END DESCRIPTION:
XS GIS Cut Line= 3
      2653665.23      6966484.61      2653197.35      6965892.76
      2652514.14      6965305.44
#Sta/Elev= 30
  4243.3  508.93  4309.9   507.5  4672.2  507.18    4794  505.16  4800.4  506.81
  4808.4  506.13  4814.8  507.19  4829.3  505.13  4835.6  506.36  4843.7  505.26
  4864.5  506.33  4878.9  503.95  4893.4   503.3  4963.9  502.63  4990.7  501.03
    4991  500.53  4994.7  501.03  5013.7  502.84    5085   502.9  5177.2   505.1
    5333   511.9  5515.1  516.54  5545.9  514.18    5581  514.19  5631.5   517.3
  5701.7  518.01  5751.2  516.13  5787.3  517.43  5822.4  521.72  5898.7  522.11
#Mann= 4 ,-1 , 0
  4243.3     .05       0  4990.7     .03       0  4994.7     .05       0
  5515.1    .075       0
Bank Sta=4990.7,4994.7
XS Rating Curve= 0 ,0
Exp/Cntr=0.3,0.1

Type RM Length L Ch R = 1 ,4480    ,502,502,502
BEGIN DESCRIPTION:
Mapping XS cb476c29
END DESCRIPTION:
XS GIS Cut Line= 3
      2654113.18      6966408.68      2653717.24      6965612.81
       2653193.8      6965005.47
#Sta/Elev= 30
  4106.7   505.7    4133  504.84  4228.2  504.42  4250.6   503.4  4429.7  505.19
    4469  503.92  4506.2  504.56  4765.7   502.7  4877.6  499.17  4922.4  499.31
  4939.2  497.49  4975.3  497.12  4991.8  495.63  4992.1  495.13  4995.8  495.63
  5047.7   497.7  5203.5  500.14  5359.3  504.76  5380.9  503.53  5408.6  503.84
  5422.9  504.63  5430.6  506.52  5451.4  508.05  5515.1   509.1  5553.7  508.58
  5561.9  508.21    5593  507.94  5629.1  512.19  5643.4  512.56  5797.4   513.8
#Mann= 5 ,-1 , 0
  4106.7     .05       0  4991.8     .03       0  4995.8     .05       0
  5553.7    .075       0  5561.9     .05       0
Bank Sta=4991.8,4995.8
XS Rating Curve= 0 ,0
Exp/Cntr=0.3,0.1

Type RM Length L Ch R = 1 ,3978    ,508,508,508
BEGIN DESCRIPTION:
Mapping XS 06de5851
END DESCRIPTION:
XS GIS Cut Line= 3
      2654493.11      6966184.74      2654133.16      6965456.85
      2653473.27      6964728.97
#Sta/Elev= 30
  4193.5  501.78  4320.4  500.51  4380.2  501.12    4442   499.9  4537.3  500.81
  4576.6  499.75  4621.5  500.01    4829  495.69  4969.1  494.57  5000.4  493.29
  5078.7  494.34  5090.9  492.77  5091.1  492.27  5094.9  492.77    5128  494.34
  5142.2  495.95  5184.8  495.49  5276.7  498.06  5368.6  499.14  5483.7  503.24
  5503.1  503.94  5538.9   503.6  5559.9  504.91    5574  504.33  5635.5  505.38
  5715.3  505.28  5772.1  509.08  5807.9  510.36  5892.3  510.81    5988  509.71
#Mann= 5 ,-1 , 0
  4193.5     .05       0  5090.9     .03       0  5094.9     .05       0
  5483.7    .075       0  5635.5     .05       0
Bank Sta=5090.9,5094.9
XS Rating Curve= 0 ,0
Exp/Cntr=0.3,0.1

Type RM Length L Ch R = 1 ,3470    ,521,521,521
BEGIN DESCRIPTION:
Mapping XS 803b889a
END DESCRIPTION:
XS GIS Cut Line= 3
      2654984.97      6966120.69      2654485.08       6965176.9
      2653790.08       6964549.8
#Sta/Elev= 30
  3950.4  500.14  4083.6  498.79  4127.6  499.45  4187.7  497.13  4221.6  497.34
  4259.6  498.81  4347.6  497.52  4391.6  498.11  4527.2  496.26  4606.4  497.05
  4660.6  495.91  4682.6  494.01  4808.9  492.18  4962.9  491.34  4979.3  489.33
  4982.9  488.16  4983.2  487.66  4986.9  488.16  5001.3  488.59  5006.9  490.38
  5013.2   490.9  5050.2  492.96  5085.3  492.71  5255.7  495.65  5418.6  502.08
  5553.2  503.83  5574.1  502.33  5602.5  502.35  5630.9  505.84  5954.5  506.63
#Mann= 3 ,-1 , 0
  3950.4     .05       0  4982.9     .03       0  4986.9     .05       0
Bank Sta=4982.9,4986.9
XS Rating Curve= 0 ,0
Exp/Cntr=0.3,0.1

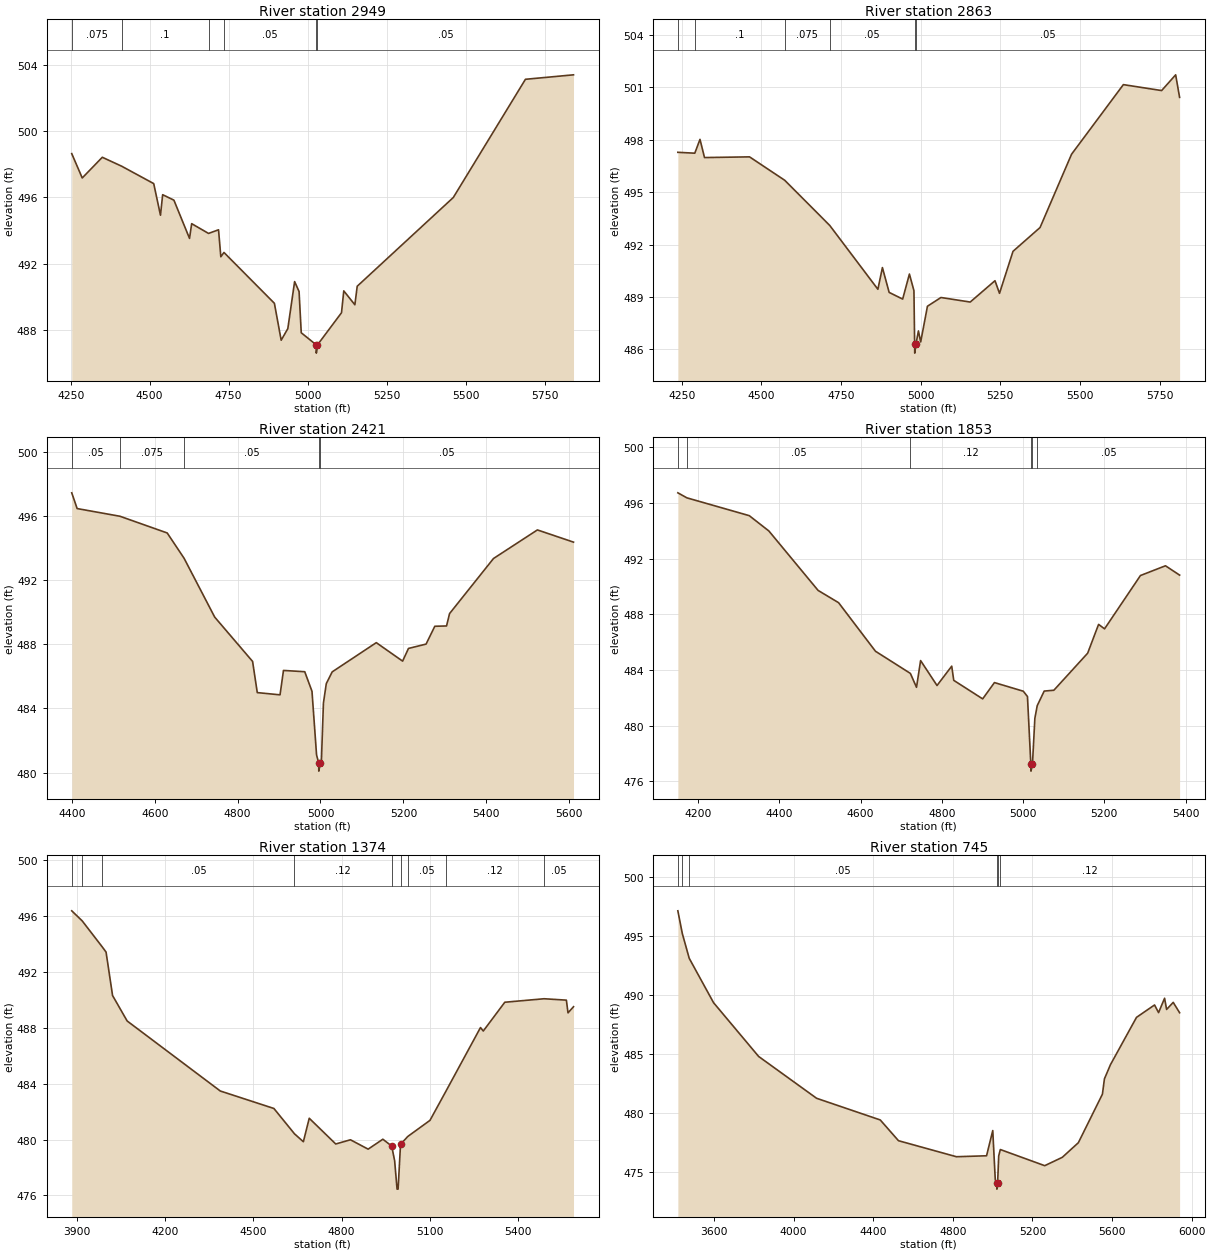
Type RM Length L Ch R = 1 ,2949    ,86,86,86
BEGIN DESCRIPTION:
Mapping XS 5f9a776f
END DESCRIPTION:
XS GIS Cut Line= 4
      2655387.21      6965436.53      2654883.28       6964900.6
      2654435.37      6964492.68      2654235.37      6964348.69
#Sta/Elev= 30
  4253.5  498.64  4286.7  497.17  4350.2  498.42  4411.5  497.88  4512.9  496.83
  4534.3  494.92  4541.2  496.16  4576.8  495.83  4626.2  493.52    4633  494.41
  4686.4  493.82    4718  494.04  4725.3  492.41  4735.2  492.67  4894.8   489.6
  4916.3  487.37  4937.3  488.07  4958.8  490.91  4972.9  490.31  4979.8  487.82
  5027.2  487.09  5027.5  486.59  5031.2  487.09  5107.2  489.03  5114.4  490.35
  5149.5  489.51  5156.9  490.63    5461  495.99  5689.3  503.13  5841.4   503.4
#Mann= 6 ,-1 , 0
  4253.5    .075       0  4411.5      .1       0  4686.4    .075       0
  4735.2     .05       0  5027.2     .05       0  5031.2     .05       0
Bank Sta=5027.2,5031.2
XS Rating Curve= 0 ,0
Exp/Cntr=0.3,0.1

Type RM Length L Ch R = 1 ,2863    ,442,442,442
BEGIN DESCRIPTION:
Mapping XS 5d16fd23
END DESCRIPTION:
XS GIS Cut Line= 4
      2655452.86      6965362.44      2654924.97      6964830.56
      2654429.07      6964330.66      2654330.08      6964259.38
#Sta/Elev= 30
  4237.4  497.27  4290.6  497.22  4306.9  498.01  4321.1  496.97  4462.5  497.01
  4573.1  495.67  4714.3  493.09  4865.5  489.44  4879.7  490.68  4900.9  489.26
  4943.3  488.88  4964.5  490.31  4978.7  489.36  4980.9  486.29  4981.2  485.79
  4984.9  486.29  4992.8  487.06  4999.9  486.43  5021.1  488.47  5063.5  488.97
  5155.4  488.71  5233.2  489.93  5247.4  489.21  5289.8  491.61  5374.7  492.97
  5473.6  497.16  5636.3  501.14  5756.4   500.8  5800.5   501.7  5812.9  500.41
#Mann= 6 ,-1 , 0
  4237.4    .075       0  4290.6      .1       0  4573.1    .075       0
  4714.3     .05       0  4980.9     .05       0  4984.9     .05       0
Bank Sta=4980.9,4984.9
XS Rating Curve= 0 ,0
Exp/Cntr=0.3,0.1

Type RM Length L Ch R = 1 ,2421    ,568,568,568
BEGIN DESCRIPTION:
Mapping XS 63439a30
END DESCRIPTION:
XS GIS Cut Line= 3
      2655416.89      6965016.93      2655164.95      6964473.05
        2654721.       6964053.1
#Sta/Elev= 30
  4399.9  497.43  4412.9  496.45  4516.3  495.97  4630.2  494.93  4670.8  493.36
  4744.8  489.69  4836.2  486.93  4847.5  484.99  4902.4  484.85  4910.7  486.37
    4962  486.29  4979.5  485.07  4990.5  481.11  4995.7   480.6  4995.9   480.1
  4999.7   480.6    5002   480.6  5007.1  484.34    5014  485.55  5028.2  486.28
  5134.6   488.1  5198.1  486.95  5212.3  487.74  5254.7  488.01  5275.8  489.12
  5304.1  489.14  5311.4  489.91  5417.4  493.34  5523.3  495.12  5610.4  494.36
#Mann= 5 ,-1 , 0
  4399.9     .05       0  4516.3    .075       0  4670.8     .05       0
  4995.7     .04       0  4999.7     .05       0
Bank Sta=4995.7,4999.7
XS Rating Curve= 0 ,0
Exp/Cntr=0.3,0.1

Type RM Length L Ch R = 1 ,1853    ,479,479,479
BEGIN DESCRIPTION:
Mapping XS 0f6e3af2
END DESCRIPTION:
XS GIS Cut Line= 3
      2655456.89      6965052.88      2655572.86       6964229.1
      2655476.88      6963837.18
#Sta/Elev= 30
  4149.9  496.73  4172.1  496.37  4325.7  495.09    4374  493.99  4495.2  489.72
  4545.6  488.84  4636.5  485.35  4722.4  483.76  4737.5  482.76  4747.6  484.68
    4788  482.89  4824.2  484.28  4829.2  483.26  4900.4  481.93  4929.4   483.1
  5000.4  482.48  5010.7   482.1    5019  477.24  5019.3  476.74    5023  477.24
  5028.9  480.53  5034.7  481.44  5051.9  482.49  5075.7  482.55  5158.9  485.21
  5185.8  487.28  5200.5  486.96  5288.9  490.79  5350.5  491.49  5385.3  490.82
#Mann= 6 ,-1 , 0
  4149.9    .075       0  4172.1     .05       0  4722.4     .12       0
    5019     .07       0    5023     .12       0  5034.7     .05       0
Bank Sta=5019,5023
XS Rating Curve= 0 ,0
Exp/Cntr=0.3,0.1

Type RM Length L Ch R = 1 ,1374    ,629,629,629
BEGIN DESCRIPTION:
Mapping XS 16912192
END DESCRIPTION:
XS GIS Cut Line= 4
      2655676.83      6965164.92      2656036.77      6964645.01
      2656028.77      6963917.16      2655724.83      6963757.19
#Sta/Elev= 30
  3883.6  496.36  3919.1  495.64  3987.1  493.78  4000.1  493.41  4022.2   490.3
  4071.7  488.48    4388  483.47    4570  482.22  4639.8  480.41    4670  479.84
    4690  481.52    4780  479.68    4830  479.98    4890  479.31    4940  480.02
    4970  479.53    4980  478.48  4988.2  476.45  4991.7  476.45    5000  479.66
  5024.8  480.22    5100  481.37  5153.5  483.43  5271.5  488.01  5280.9  487.76
    5354  489.82  5487.5  490.07  5563.1  489.97  5568.7  489.06  5587.3   489.5
#Mann= 9 ,-1 , 0
  3883.6      .1       0  3919.1    .075       0  3987.1     .05       0
  4639.8     .12       0    4970     .03       0    5000     .12       0
  5024.8     .05       0  5153.5     .12       0  5487.5     .05       0
Bank Sta=4970,5000
XS Rating Curve= 0 ,0
Exp/Cntr=0.3,0.1

Type RM Length L Ch R = 1 ,745     ,538,538,538
BEGIN DESCRIPTION:
Mapping XS 8e2c6e33
END DESCRIPTION:
XS GIS Cut Line= 5
      2655731.74      6965278.99      2656654.82      6964182.56
      2656581.15      6964043.88      2656472.81       6963814.2
      2655801.08      6963731.86
#Sta/Elev= 30
  3418.6  497.15    3441  495.22  3475.7  493.12  3598.1  489.35  3824.5  484.79
  4115.7  481.24  4435.6   479.4  4527.1  477.64  4818.1  476.28  4969.6  476.36
  5000.8   478.5  5013.4  474.33  5021.1  474.03  5021.4  473.53  5025.1  474.03
  5030.7  476.35  5038.8  476.89  5261.9  475.52  5350.3  476.23  5430.9  477.47
  5551.8  481.59  5561.9  482.89  5592.1  484.09  5723.1  488.11  5813.7  489.16
  5833.9  488.51  5864.1  489.73  5874.2  488.78  5907.5  489.38  5939.6   488.5
#Mann= 6 ,-1 , 0
  3418.6      .1       0    3441    .075       0  3475.7     .05       0
  5021.1      .1       0  5025.1     .05       0  5038.8     .12       0
Bank Sta=5021.1,5025.1
XS Rating Curve= 0 ,0
Exp/Cntr=0.3,0.1

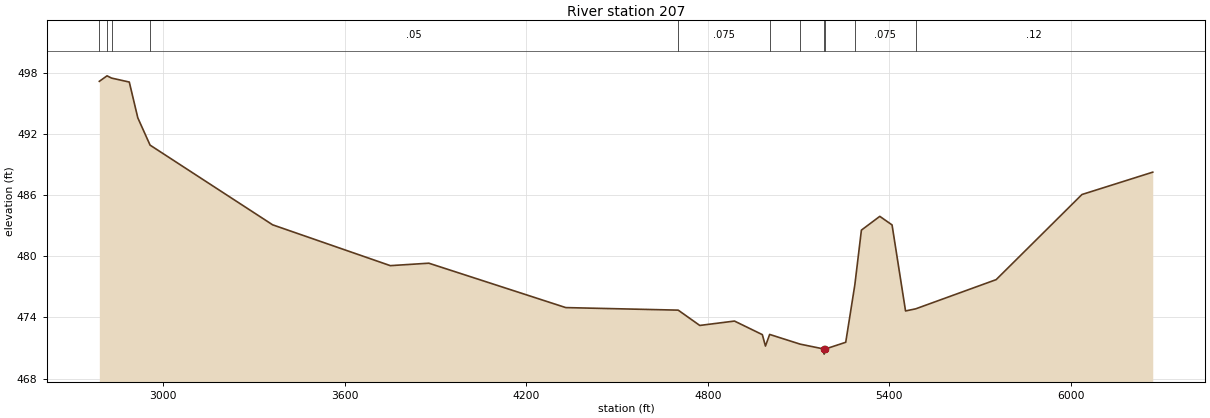
Type RM Length L Ch R = 1 ,207     ,0,0,0
BEGIN DESCRIPTION:
Kings Creek Trib 7 2.0
END DESCRIPTION:
XS GIS Cut Line= 4
      2655725.99      6965361.01      2657018.84      6964091.55
       2656897.5      6963541.18      2655804.84       6963713.2
#Sta/Elev= 30
  2789.3  497.14  2814.8  497.68  2829.5  497.46  2888.3  497.07  2916.5  493.56
    2957  490.89  3362.1  483.08    3751  479.08  3878.3  479.32  4330.9  474.97
  4702.5  474.72  4773.8  473.22  4888.5  473.65  4980.6  472.32  4990.9   471.2
  5004.7  472.34  5105.4  471.39  5184.5  470.91  5184.8  470.41  5188.5  470.91
  5256.2  471.57  5286.3   477.2    5308  482.56  5368.8  483.91  5409.3  483.07
  5453.9  474.64  5487.6  474.85  5753.4  477.71  6036.9  486.05  6270.9  488.24
#Mann= 11 ,-1 , 0
  2789.3    .075       0  2814.8      .1       0  2829.5    .075       0
    2957     .05       0  4702.5    .075       0  5004.7     .12       0
  5105.4     .05       0  5184.5      .1       0  5188.5     .05       0
  5286.3    .075       0  5487.6     .12       0
Bank Sta=5184.5,5188.5
XS Rating Curve= 0 ,0
Exp/Cntr=0.3,0.1

Chan Stop Cuts=-1
Use User Specified Reach Order=0
Composite Channel Slope=5