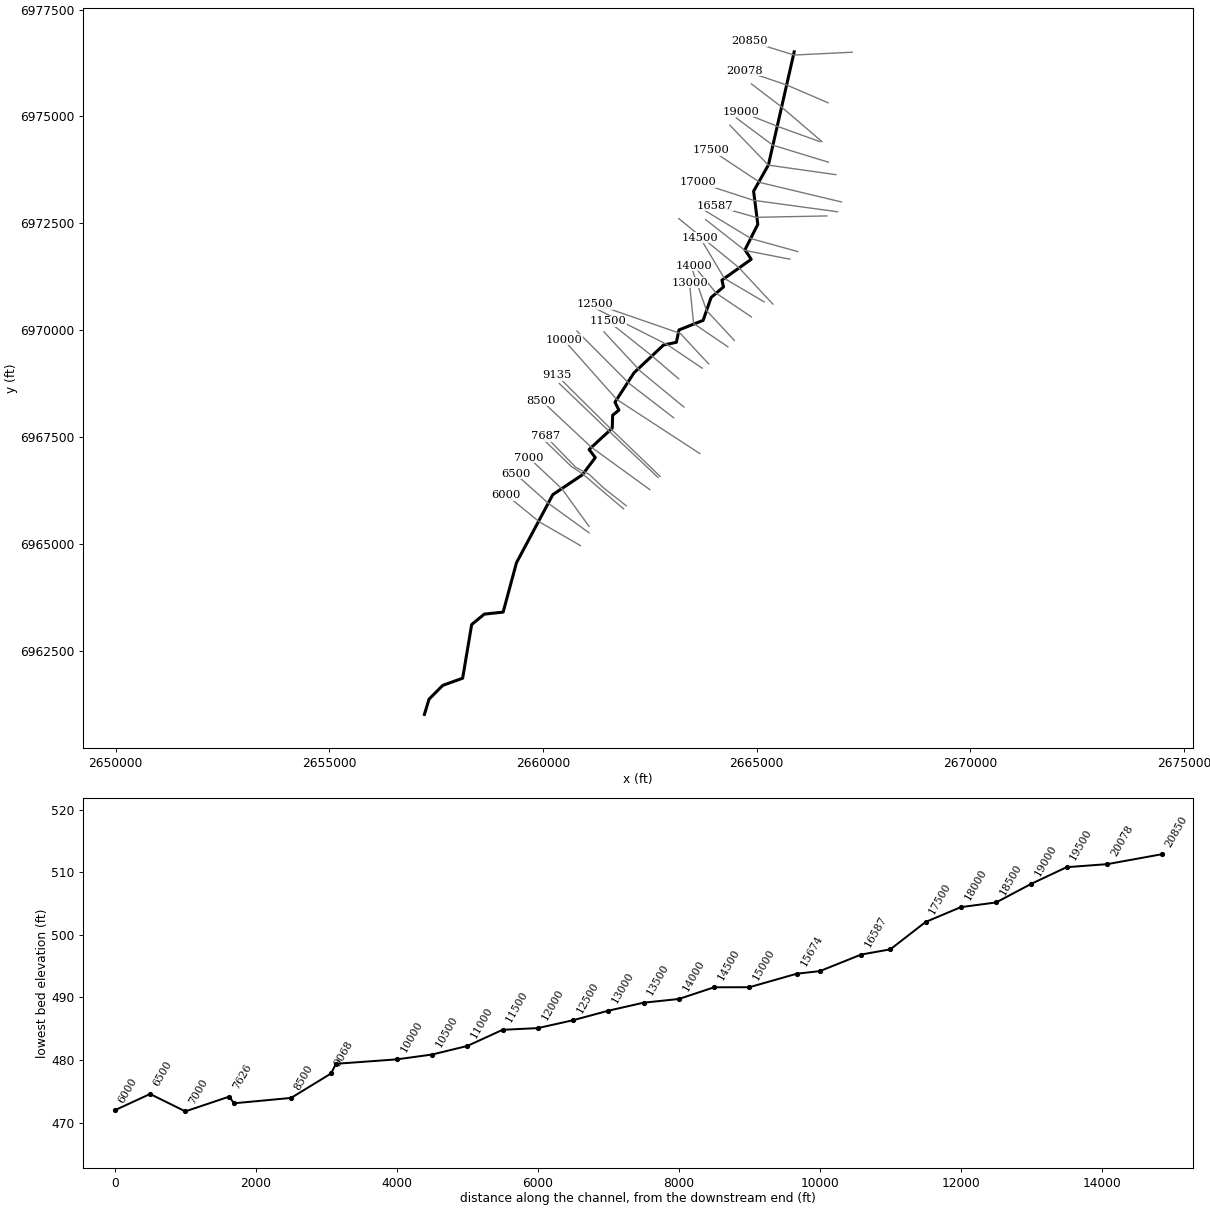
--- Kings Creek Trib 8.prj (project) ---

Proj Title=Kings Creek Trib 8 Base Level Engineering
Current Plan=p01
Default Exp/Contr=0.3,0.1
English Units
Geom File=g01
Flow File=f01
Plan File=p01
Y Axis Title=Elevation
X Axis Title(PF)=Main Channel Distance
X Axis Title(XS)=Station
BEGIN DESCRIPTION:
Kings Creek Trib 8
END DESCRIPTION:
DSS Export Rating Curves= 0
DSS Export Rating Curve Sorted= 0
DSS Export Volume Flow Curves= 0
DXF OffsetX= 0
DXF OffsetY= 0
DXF ScaleX= 1
DXF ScaleY= 10

--- Kings Creek Trib 8.p01 (plan) ---

Plan Title=Multiple Run
Short Identifier=Multiple
Geom File=g01
Flow File=f01
Subcritical Flow
K Sum by GR= 0
Std Step Tol= 0.01
Critical Tol= 0.01
Num of Std Step Trials= 20
Max Error Tol= 0.3
Flow Tol Ratio= 0.001
Split Flow NTrial= 30
Split Flow Tol= 0.02
Split Flow Ratio= 0.02
Log Output Level= 0
Friction Slope Method= 1
Unsteady Friction Slope Method= 2
Unsteady Bridges Friction Slope Method= 1
Parabolic Critical Depth
Global Vel Dist=  1 , 1 , 1
Global Log Level= 0
CheckData=True
Encroach Param= -1, 0, 0, 0
BEGIN DESCRIPTION:
Multiple Run
END DESCRIPTION:

--- Kings Creek Trib 8.f01 (steady flow) ---

Flow Title=Multiple
Number of Profiles=7
Profile Names=10-year,25-year,50-year,1pct_min,100-year,1pct_plu,500-year
River Rch & RM= Kings Creek Trib,Reach-1,20850
     579     773     930     555    1107    2209    1569
River Rch & RM= Kings Creek Trib,Reach-1,19500
     659     886    1070     641    1278    2550    1822
River Rch & RM= Kings Creek Trib,Reach-1,18000
     849    1153    1401     843    1682    3356    2426
River Rch & RM= Kings Creek Trib,Reach-1,11500
    1443    2005    2473    1507    3006    5999    4448
River Rch & RM= Kings Creek Trib,Reach-1,3911
    1455    2017    2483    1511    3014    6014    4443
River Rch & RM= Kings Creek Trib,Reach-1,1047
    1520    2116    2613    1594    3181    6348    4718
Boundary for River Rch & Prof#=Kings Creek Trib,Reach-1,1
Up Type=0
Dn Type=3
Dn Slope=0.005
Boundary for River Rch & Prof#=Kings Creek Trib,Reach-1,2
Up Type=0
Dn Type=3
Dn Slope=0.005
Boundary for River Rch & Prof#=Kings Creek Trib,Reach-1,3
Up Type=0
Dn Type=3
Dn Slope=0.005
Boundary for River Rch & Prof#=Kings Creek Trib,Reach-1,4
Up Type=0
Dn Type=3
Dn Slope=0.005
Boundary for River Rch & Prof#=Kings Creek Trib,Reach-1,5
Up Type=0
Dn Type=3
Dn Slope=0.005
Boundary for River Rch & Prof#=Kings Creek Trib,Reach-1,6
Up Type=0
Dn Type=3
Dn Slope=0.005
Boundary for River Rch & Prof#=Kings Creek Trib,Reach-1,7
Up Type=0
Dn Type=3
Dn Slope=0.005

--- Kings Creek Trib 8.g01 (geometry) ---

Geom Title=Existing Conditions
Program Version=4.10

River Reach=Kings Creek Trib,Reach-1
Reach XY= 30
        2665876.        6976511.      2665273.94      6973866.85
      2664926.99      6973250.72      2665025.52      6972476.23
      2664725.23      6971880.85      2664870.75      6971658.35
      2664186.03      6971171.06      2664222.86      6971012.64
      2663931.82      6970763.31      2663746.54      6970230.46
      2663180.76      6970005.42      2663120.38      6969716.62
      2662819.76      6969653.25      2662128.51      6969002.89
      2661683.84      6968314.23      2661776.13      6968131.26
      2661629.52      6968009.54      2661620.19      6967708.71
      2661079.08      6967209.32       2661223.4      6967019.54
      2660920.41      6966616.61      2660229.51      6966152.52
      2659379.62       6964559.5      2659067.89      6963404.93
      2658627.63      6963357.87      2658331.42      6963113.67
      2658120.64       6961858.3      2657655.84      6961691.39
      2657333.82      6961367.19        2657226.        6961011.

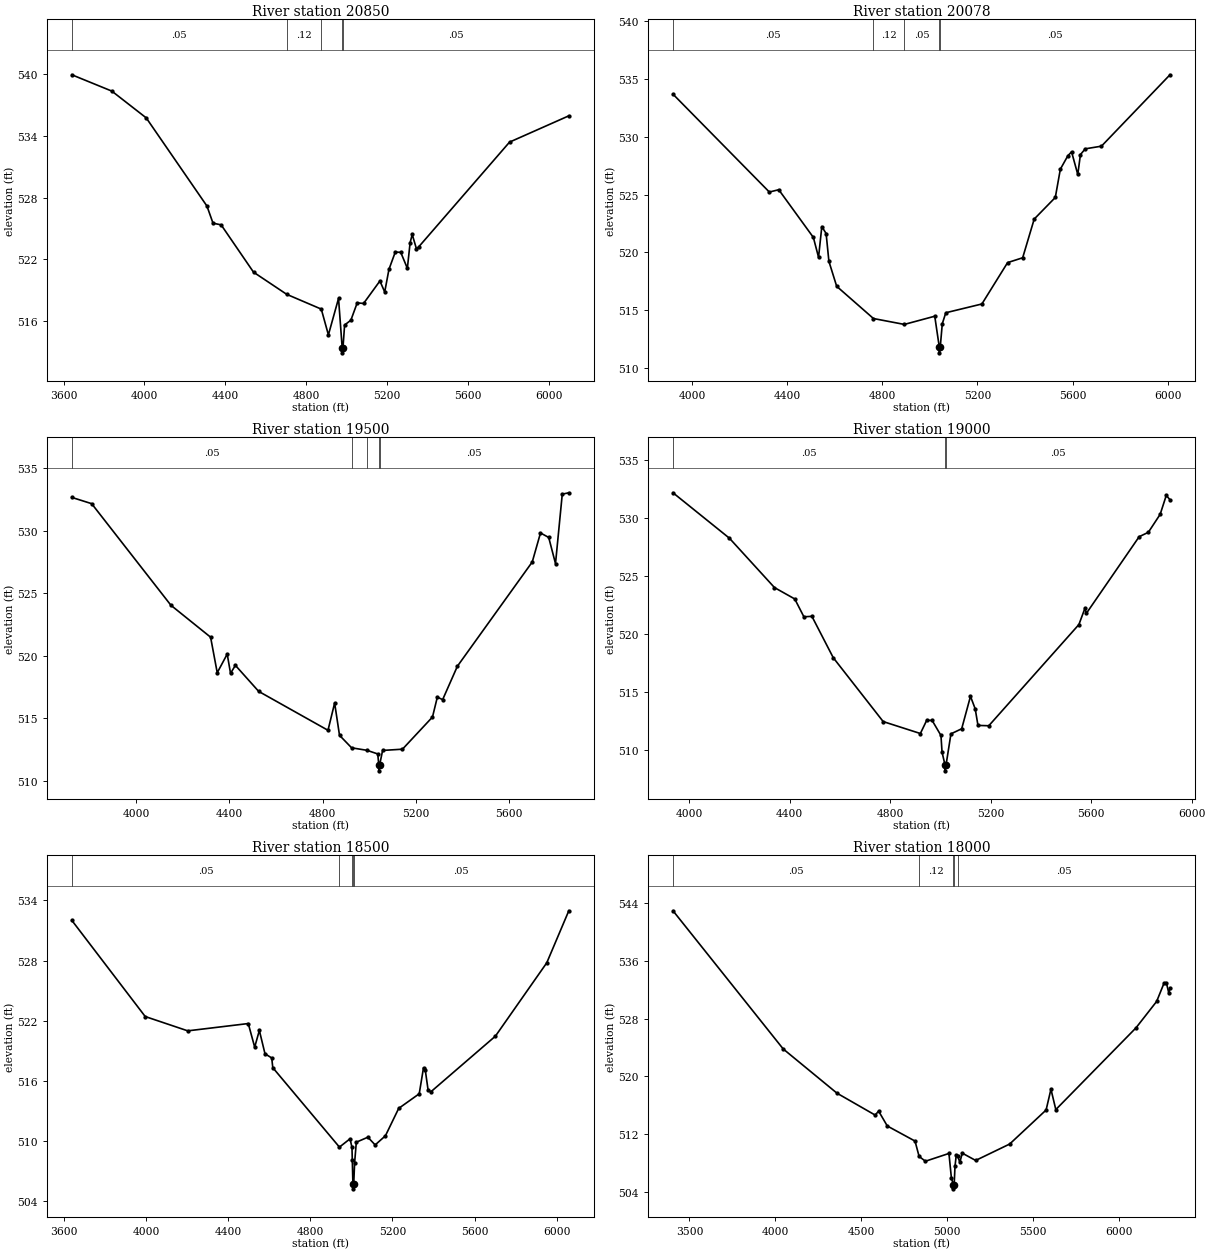
Type RM Length L Ch R = 1 ,20850   ,772,772,772
BEGIN DESCRIPTION:
Kings Creek Trib 8 41.0
END DESCRIPTION:
XS GIS Cut Line= 3
      2667233.52      6976502.75      2665876.03      6976436.77
      2664826.04      6976760.99
#Sta/Elev= 30
  3640.9  539.97  3838.7  538.38  4008.9  535.77  4309.2  527.18  4339.2  525.51
  4379.3  525.35  4539.5  520.74  4703.7  518.58  4874.7  517.14  4909.9  514.63
    4960  518.18    4978  513.38  4978.3  512.88    4982  513.38    4990  515.59
    5021  516.06  5052.4  517.75  5083.8  517.69  5164.6  519.88  5188.4  518.81
  5209.3  521.01  5240.7   522.7  5267.7  522.67  5300.4  521.11    5314  523.61
  5324.5  524.41  5345.4  523.01  5355.9  523.19  5805.8  533.41  6098.9  535.97
#Mann= 5 ,-1 , 0
  3640.9     .05       0  4703.7     .12       0  4874.7     .05       0
    4978     .03       0    4982     .05       0
Bank Sta=4978,4982
XS Rating Curve= 0 ,0
Exp/Cntr=0.3,0.1

Type RM Length L Ch R = 1 ,20078   ,578,578,578
BEGIN DESCRIPTION:
Kings Creek Trib 8 40.0
END DESCRIPTION:
XS GIS Cut Line= 3
      2666667.91      6975319.42      2665700.73      6975736.28
      2664719.46       6976068.9
#Sta/Elev= 30
    3920  533.69    4325  525.22  4364.6  525.42  4510.1  521.29  4531.9  519.57
  4545.6  522.23  4563.7  521.63  4575.4  519.22  4608.1  517.06  4762.7  514.27
  4892.5  513.76  5020.4  514.47  5039.5   511.8  5039.8   511.3  5043.5   511.8
  5052.1  513.82  5066.8  514.77  5218.6  515.53  5326.6  519.11    5390  519.53
  5438.5  522.88  5527.2  524.75  5548.4   527.2    5580  528.36  5595.6   528.7
  5621.7  526.74  5632.8  528.46  5653.1  528.96  5721.2  529.19  6009.3  535.37
#Mann= 5 ,-1 , 0
    3920     .05       0  4762.7     .12       0  4892.5     .05       0
  5039.5     .03       0  5043.5     .05       0
Bank Sta=5039.5,5043.5
XS Rating Curve= 0 ,0
Exp/Cntr=0.3,0.1

Type RM Length L Ch R = 1 ,19500   ,500,500,500
BEGIN DESCRIPTION:
Kings Creek Trib 8 39.0
END DESCRIPTION:
XS GIS Cut Line= 3
      2666526.01      6974410.99      2665556.53      6975241.39
      2664876.02      6975760.98
#Sta/Elev= 30
  3723.5  532.66  3808.6  532.16  4148.8  524.04    4319  521.49  4347.5  518.65
  4390.3  520.14  4404.6   518.6  4425.4  519.24  4525.3  517.16  4822.8  514.05
  4851.3  516.23  4872.2  513.65  4924.1  512.65  4990.1  512.45  5036.3  512.16
  5040.6  511.31  5040.9  510.81  5044.6  511.31  5057.2  512.44  5142.4  512.54
  5271.2  515.11    5292   516.7  5314.8   516.5  5378.1  519.17  5699.3   527.5
  5734.7  529.82    5770  529.46  5799.1  527.37  5828.1  532.92  5856.2  533.03
#Mann= 5 ,-1 , 0
  3723.5     .05       0  4924.1     .12       0  4990.1     .05       0
  5040.6     .03       0  5044.6     .05       0
Bank Sta=5040.6,5044.6
XS Rating Curve= 0 ,0
Exp/Cntr=0.3,0.1

Type RM Length L Ch R = 1 ,19000   ,500,500,500
BEGIN DESCRIPTION:
Kings Creek Trib 8 38.0
END DESCRIPTION:
XS GIS Cut Line= 3
      2666475.97      6974411.01      2665474.83      6974772.79
      2664626.03      6975110.99
#Sta/Elev= 30
  3935.5  532.15  4160.1  528.23  4339.5  523.97  4420.1  522.99  4456.5  521.45
  4488.4  521.49  4573.4  517.92  4772.1  512.41  4920.1  511.38  4945.4  512.52
  4966.9  512.51  5002.1  511.21  5006.4  509.77  5018.3  508.66  5018.5  508.16
  5022.3  508.66  5041.8  511.35  5084.6  511.79  5119.6  514.59  5138.5   513.5
  5149.4  512.08  5192.5  512.05  5551.1  520.78  5575.3  522.19  5580.7  521.74
    5791  528.36  5827.6  528.74  5874.6  530.29  5898.9  531.92  5913.7  531.55
#Mann= 3 ,-1 , 0
  3935.5     .05       0  5018.3     .03       0  5022.3     .05       0
Bank Sta=5018.3,5022.3
XS Rating Curve= 0 ,0
Exp/Cntr=0.3,0.1

Type RM Length L Ch R = 1 ,18500   ,500,500,500
BEGIN DESCRIPTION:
Kings Creek Trib 8 37.0
END DESCRIPTION:
XS GIS Cut Line= 3
      2666677.97      6973929.83      2665375.23      6974328.25
      2664526.03      6974960.98
#Sta/Elev= 30
  3637.7  532.01  3995.3   522.4  4202.5  520.97  4497.3   521.7  4528.6  519.34
  4551.3  521.01  4578.8  518.68  4611.6  518.26  4616.8  517.29  4941.5  509.35
  4993.1  510.18  5002.6  509.32  5004.2  508.03  5007.1  505.68  5007.4  505.18
  5011.1  505.68  5015.4  507.77  5023.7  509.84    5080  510.34  5115.5  509.57
  5165.5  510.48  5230.2  513.22  5330.2  514.68  5351.1  517.28  5359.5  517.08
  5373.2  515.09  5386.5  514.87  5701.4  520.44  5951.6  527.77    6059  532.97
#Mann= 5 ,-1 , 0
  3637.7     .05       0  4941.5     .12       0  5004.2     .05       0
  5007.1     .07       0  5011.1     .05       0
Bank Sta=5007.1,5011.1
XS Rating Curve= 0 ,0
Exp/Cntr=0.3,0.1

Type RM Length L Ch R = 1 ,18000   ,500,500,500
BEGIN DESCRIPTION:
Kings Creek Trib 8 36.0
END DESCRIPTION:
XS GIS Cut Line= 3
      2666851.55      6973638.17      2665271.66      6973860.82
      2664370.85       6974795.9
#Sta/Elev= 30
  3404.5  542.92  4046.3  523.79  4359.4  517.67  4581.6  514.64  4601.8  515.19
  4652.3  513.13  4813.8  511.04  4837.5  508.92  4874.4  508.25  5011.3  509.33
  5025.4  505.97  5037.6  504.93  5037.8  504.43  5041.6  504.93  5046.5  507.53
  5053.7  509.06  5062.4  508.93  5074.8  508.11    5089  509.37  5166.9  508.36
  5364.8  510.63    5577  515.34  5605.3  518.22  5633.6   515.4  6100.3  526.71
  6220.7  530.37  6263.1  532.86  6277.3  532.97  6291.4  531.54  6298.4   532.2
#Mann= 5 ,-1 , 0
  3404.5     .05       0  4837.5     .12       0  5037.6     .07       0
  5041.6     .12       0  5062.4     .05       0
Bank Sta=5037.6,5041.6
XS Rating Curve= 0 ,0
Exp/Cntr=0.3,0.1

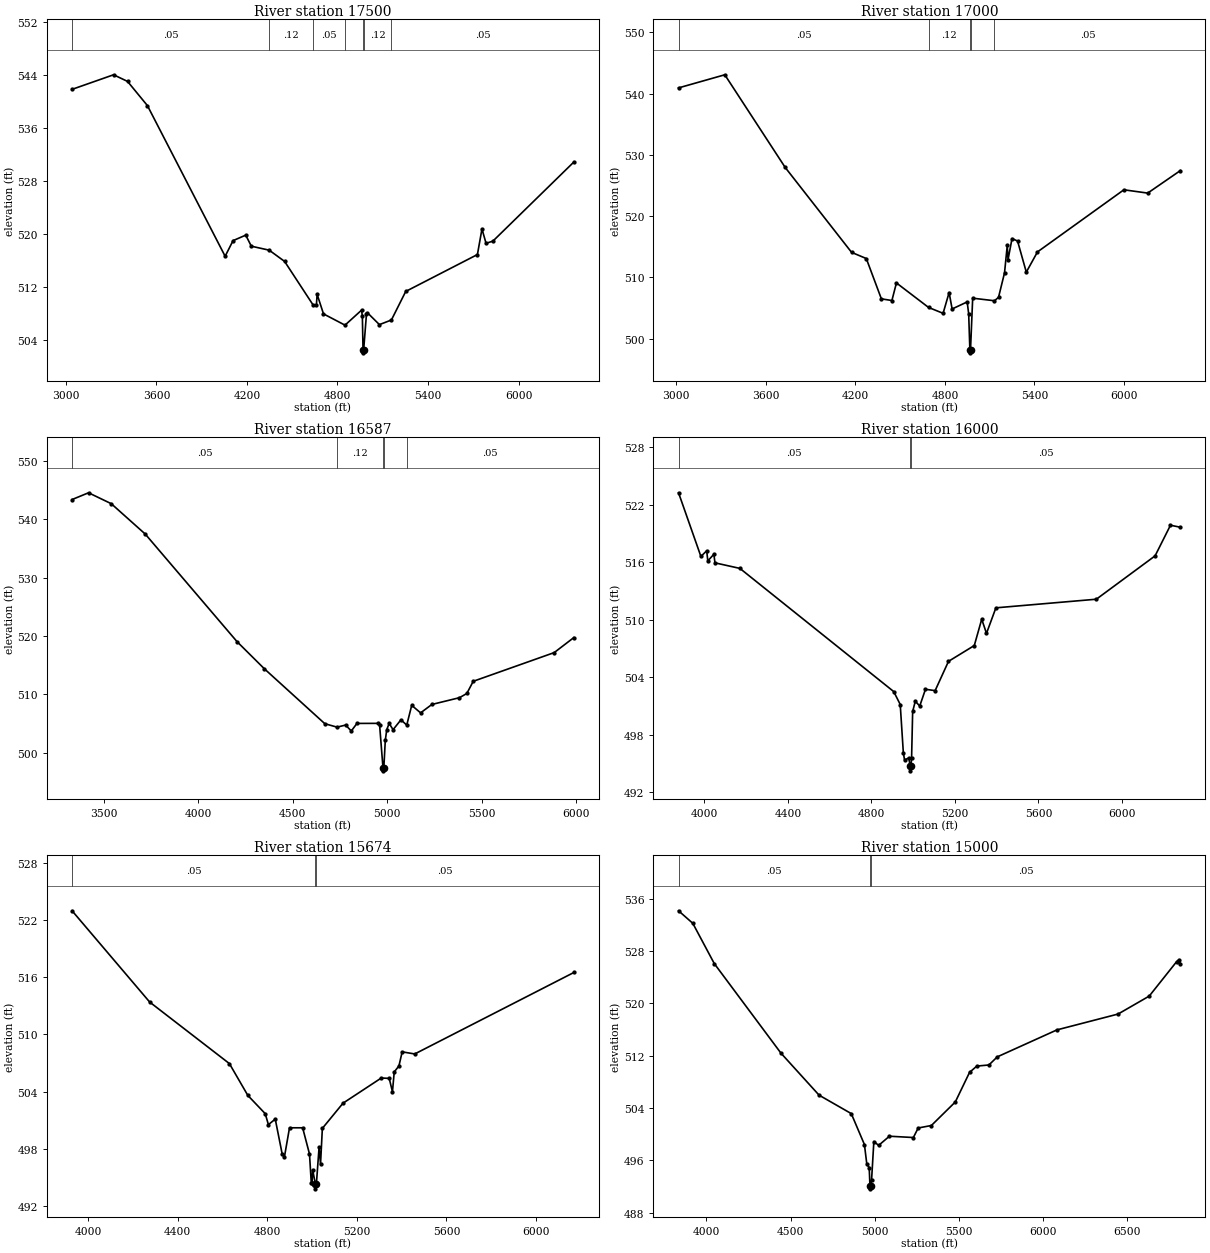
Type RM Length L Ch R = 1 ,17500   ,500,500,500
BEGIN DESCRIPTION:
Kings Creek Trib 8 35.0
END DESCRIPTION:
XS GIS Cut Line= 3
      2666983.52      6972999.28      2665078.24      6973454.48
      2663939.72      6974210.19
#Sta/Elev= 30
  3041.1  541.84  3316.1  544.04  3408.7  543.04  3540.3  539.39  4055.5  516.64
  4107.9     519    4192  519.83    4229  518.16  4347.5  517.56  4449.7  515.86
  4640.3  509.22  4660.1  509.22  4665.2  510.89  4707.3  507.94  4849.9  506.24
  4959.8  508.51  4964.9  507.56  4969.3  502.56  4969.7  502.06  4973.6  502.56
    4992  507.87  4998.6  508.11  5077.9  506.32  5157.4  507.02  5252.3  511.33
  5727.4   516.9  5757.5  520.76  5784.6   518.6  5829.7  518.92  6366.5  530.87
#Mann= 7 ,-1 , 0
  3041.1     .05       0  4347.5     .12       0  4640.3     .05       0
  4849.9     .12       0  4969.3     .07       0  4973.6     .12       0
  5157.4     .05       0
Bank Sta=4969.3,4973.6
XS Rating Curve= 0 ,0
Exp/Cntr=0.3,0.1

Type RM Length L Ch R = 1 ,17000   ,413,413,413
BEGIN DESCRIPTION:
Kings Creek Trib 8 34.0
END DESCRIPTION:
XS GIS Cut Line= 3
      2666893.27      6972770.11      2664925.97      6973037.63
      2663615.46      6973464.56
#Sta/Elev= 30
  3014.6  540.93  3324.7  543.07  3729.8  527.94  4174.5  514.09  4273.3  513.08
  4374.3   506.5  4444.9  506.23  4475.2   509.1  4690.6   505.1    4788  504.14
  4828.4  507.53  4848.6  504.85  4949.5     506  4959.6  504.04  4967.5  498.19
  4967.9  497.69  4971.8  498.19  4986.4  506.61  5132.6  506.19  5159.6  506.75
  5199.8  510.74  5218.2  515.22  5223.4   512.9  5250.1  516.34  5287.2  515.94
  5345.8  510.86  5420.7  514.16    6000   524.3  6159.6  523.76  6378.3  527.43
#Mann= 5 ,-1 , 0
  3014.6     .05       0  4690.6     .12       0  4967.5     .07       0
  4971.8     .12       0  5132.6     .05       0
Bank Sta=4967.5,4971.8
XS Rating Curve= 0 ,0
Exp/Cntr=0.3,0.1

Type RM Length L Ch R = 1 ,16587   ,587,587,587
BEGIN DESCRIPTION:
Kings Creek Trib 8 33.0
END DESCRIPTION:
XS GIS Cut Line= 3
      2666643.23      6972672.89      2664975.64      6972640.64
      2664025.98      6972911.01
#Sta/Elev= 30
  3332.1  543.37  3419.3  544.53  3539.4  542.66  3719.4  537.45    4205  519.01
  4349.5  514.36  4669.6  504.94  4734.4  504.35  4779.6  504.71  4809.6  503.69
  4839.6  504.99  4949.6     505  4959.6  504.65  4977.4  497.36  4977.8  496.86
  4981.8  497.36  4989.6  502.09  4997.3  503.92    5010  504.99  5030.8  503.92
  5072.4  505.61  5103.1   504.7  5129.4  508.09  5176.4   506.8  5236.1  508.24
    5382   509.4    5421  510.12  5454.9  512.21  5883.4  517.13  5987.4  519.71
#Mann= 5 ,-1 , 0
  3332.1     .05       0  4734.4     .12       0  4977.4     .07       0
  4981.8     .12       0  5103.1     .05       0
Bank Sta=4977.4,4981.8
XS Rating Curve= 0 ,0
Exp/Cntr=0.3,0.1

Type RM Length L Ch R = 1 ,16000   ,326,326,326
BEGIN DESCRIPTION:
Kings Creek Trib 8 32.0
END DESCRIPTION:
XS GIS Cut Line= 3
       2665959.2      6971839.56      2664876.27      6972138.75
      2663782.16      6972801.34
#Sta/Elev= 30
  3876.5  523.26  3983.6  516.61  4011.4   517.2  4016.6  516.14  4045.8  516.84
  4050.9  515.94  4170.3  515.36  4906.9  502.49    4938  501.14  4952.9  496.09
  4958.8  495.33  4979.5  495.57  4984.9  494.71  4985.4  494.21  4989.5  494.71
  4992.4  495.56  4997.5  500.41  5010.1  501.48  5031.4  500.98  5058.8  502.73
  5105.1  502.59  5169.1  505.65  5292.6   507.3  5328.2  510.05    5351  508.57
    5396  511.24    5877  512.14  6158.3  516.67  6231.9  519.87  6279.1  519.66
#Mann= 3 ,-1 , 0
  3876.5     .05       0  4984.9     .03       0  4989.5     .05       0
Bank Sta=4984.9,4989.5
XS Rating Curve= 0 ,0
Exp/Cntr=0.3,0.1

Type RM Length L Ch R = 1 ,15674   ,674,674,674
BEGIN DESCRIPTION:
Kings Creek Trib 8 31.0
END DESCRIPTION:
XS GIS Cut Line= 3
      2665776.04      6971660.99      2664724.99       6971865.7
      2663804.79      6972586.01
#Sta/Elev= 30
  3929.2  522.95  4275.6  513.38  4631.3  506.93  4713.7  503.59  4791.2  501.68
  4805.4  500.53    4836  501.11  4866.5   497.5  4876.7  497.12  4899.6   500.2
  4958.2   500.2  4988.8  497.45  4996.9  494.37    5000  494.37  5002.8  495.81
  5014.9   494.3  5015.4   493.8  5019.5   494.3  5031.7   498.2    5038  496.38
  5046.2  500.14  5138.4  502.78  5309.3  505.42  5344.6  505.38    5359  503.98
    5367  506.06  5387.9  506.68  5402.4  508.16  5458.5  507.94  6168.6  516.48
#Mann= 3 ,-1 , 0
  3929.2     .05       0  5014.9     .03       0  5019.5     .05       0
Bank Sta=5014.9,5019.5
XS Rating Curve= 0 ,0
Exp/Cntr=0.3,0.1

Type RM Length L Ch R = 1 ,15000   ,500,500,500
BEGIN DESCRIPTION:
Kings Creek Trib 8 30.0
END DESCRIPTION:
XS GIS Cut Line= 3
        2665376.        6970611.      2664581.96      6971464.03
      2663175.97      6972611.03
#Sta/Elev= 30
  3834.6  534.18  3919.4  532.26  4046.9   526.1  4443.1  512.39  4669.3  505.97
  4860.4  503.15  4938.5  498.42  4952.7  495.42  4966.9   494.9  4971.3  492.14
  4971.9  491.64  4976.1  492.14    4981  493.01  4994.5  498.87    5023  498.29
  5086.9  499.69  5229.1  499.49  5257.8  500.95  5336.1  501.33  5478.2  504.93
  5562.9  509.46    5606  510.42  5677.8  510.59  5727.4  511.83  6082.1  515.96
  6444.7  518.38  6629.9  521.13  6792.9  526.41  6807.3  526.71  6814.5  526.03
#Mann= 3 ,-1 , 0
  3834.6     .05       0  4971.3     .04       0  4976.1     .05       0
Bank Sta=4971.3,4976.1
XS Rating Curve= 0 ,0
Exp/Cntr=0.3,0.1

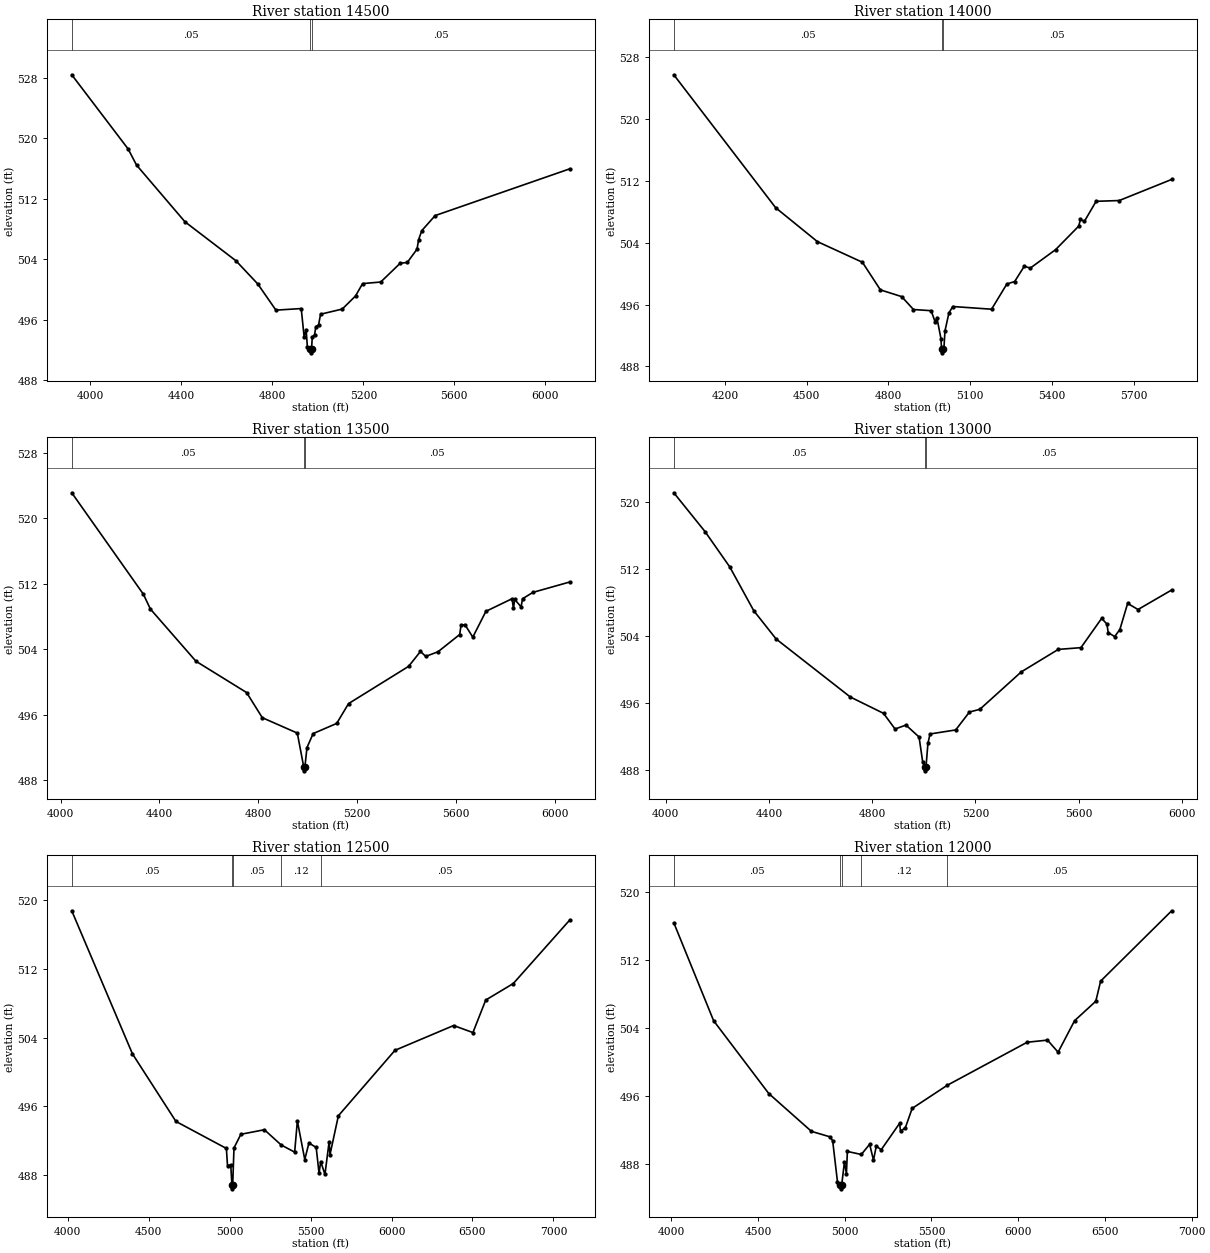
Type RM Length L Ch R = 1 ,14500   ,500,500,500
BEGIN DESCRIPTION:
Kings Creek Trib 8 29.0
END DESCRIPTION:
XS GIS Cut Line= 3
      2665176.03      6970660.98      2664243.96       6971210.9
      2663676.01      6972160.99
#Sta/Elev= 30
  3917.8  528.42  4165.6  518.61  4202.7  516.47  4415.5  508.97  4639.8  503.81
  4735.5  500.75  4815.5  497.28  4926.7  497.49  4939.6  493.74  4948.2   494.7
    4954  492.36  4967.2  492.13  4967.8  491.63  4972.1  492.13  4975.4  493.76
  4985.3     494  4991.1  495.11  5002.9  495.32  5011.8  496.74    5107  497.42
  5165.4  499.15  5196.5  500.79  5276.3     501  5361.8  503.48    5393  503.59
  5435.8  505.34  5442.8  506.61  5457.2  507.81  5515.5  509.79  6106.9  515.97
#Mann= 3 ,-1 , 0
  3917.8     .05       0  4967.2     .04       0  4972.1     .05       0
Bank Sta=4967.2,4972.1
XS Rating Curve= 0 ,0
Exp/Cntr=0.3,0.1

Type RM Length L Ch R = 1 ,14000   ,500,500,500
BEGIN DESCRIPTION:
Kings Creek Trib 8 28.0
END DESCRIPTION:
XS GIS Cut Line= 3
      2664875.96      6970311.03      2664056.06      6970861.05
      2663525.99      6971511.01
#Sta/Elev= 30
  4012.7  525.71  4386.3  508.52  4539.3  504.14  4704.4  501.47  4770.4   497.9
  4848.4  497.03  4891.7  495.36  4956.5  495.21  4971.5  493.72  4977.5  494.32
  4992.5  491.59  4994.6  490.26  4995.2  489.76  4999.5  490.26  5003.2  490.26
  5007.2  492.59  5021.6  494.91  5035.9  495.75  5178.1   495.4  5234.1  498.66
  5262.8  498.98    5298  500.95  5320.3  500.72  5412.9   503.1  5497.6  506.14
  5504.1  507.02  5518.4  506.75  5561.5  509.35  5646.2  509.45  5838.7  512.18
#Mann= 3 ,-1 , 0
  4012.7     .05       0  4994.6     .04       0  4999.5     .05       0
Bank Sta=4994.6,4999.5
XS Rating Curve= 0 ,0
Exp/Cntr=0.3,0.1

Type RM Length L Ch R = 1 ,13500   ,500,500,500
BEGIN DESCRIPTION:
Kings Creek Trib 8 27.0
END DESCRIPTION:
XS GIS Cut Line= 3
      2664475.97      6969761.04       2663825.7      6970459.77
      2663476.01      6971460.96
#Sta/Elev= 30
  4045.5  523.13  4335.4  510.74  4363.8  508.93    4548  502.56  4753.2  498.73
  4816.7  495.66  4958.4  493.78  4984.2  489.67  4984.9  489.17  4989.2  489.67
  4997.4  492.01  5022.5  493.72  5117.8  494.96  5165.7  497.38  5408.8  501.93
  5456.8  503.75    5478  503.15  5527.7  503.71  5615.6  505.82  5620.9  506.95
  5636.8  507.02  5668.6   505.5  5721.6  508.65  5827.5  510.19    5833  509.01
  5838.2   510.1    5864   509.2  5869.9  510.19  5912.3  510.97  6060.5  512.23
#Mann= 3 ,-1 , 0
  4045.5     .05       0  4984.2     .04       0  4989.2     .05       0
Bank Sta=4984.2,4989.2
XS Rating Curve= 0 ,0
Exp/Cntr=0.3,0.1

Type RM Length L Ch R = 1 ,13000   ,500,500,500
BEGIN DESCRIPTION:
Kings Creek Trib 8 26.0
END DESCRIPTION:
XS GIS Cut Line= 3
      2664325.97      6969611.02      2663523.78      6970154.94
      2663426.01      6971110.95
#Sta/Elev= 30
  4030.8  521.07  4152.1  516.43  4247.8  512.22  4340.7     507  4427.6  503.62
  4715.1   496.7  4843.9  494.75  4888.6  492.88  4930.7  493.35  4981.6  491.93
  4995.6  488.97  5003.5  488.39  5004.2  487.89  5008.6  488.39  5016.1   491.2
  5024.2  492.29  5123.6  492.77    5177  494.91  5217.2  495.23    5378   499.7
  5521.3  502.38  5609.2  502.59  5689.6  506.09  5709.7   505.4  5715.1  504.38
  5739.9  503.91    5760  504.75  5790.2  507.87  5830.4  507.14    5961  509.47
#Mann= 3 ,-1 , 0
  4030.8     .05       0  5003.5     .04       0  5008.6     .05       0
Bank Sta=5003.5,5008.6
XS Rating Curve= 0 ,0
Exp/Cntr=0.3,0.1

Type RM Length L Ch R = 1 ,12500   ,500,500,500
BEGIN DESCRIPTION:
Kings Creek Trib 8 25.0
END DESCRIPTION:
XS GIS Cut Line= 3
      2663876.02      6969210.98      2663211.32      6969925.11
      2661225.97      6970611.01
#Sta/Elev= 30
  4024.4  518.79  4399.4  502.11  4668.1  494.23  4979.8  491.08  4986.7  489.08
  5006.8  489.18  5013.7  486.87  5014.3  486.37  5018.8  486.87  5026.8  491.14
  5069.2  492.73  5214.5  493.26  5318.6  491.48  5401.6  490.65  5418.3  494.29
    5464  489.79  5489.9  491.72  5534.6  491.19  5552.2  488.19  5562.6  489.55
  5588.7  488.05  5614.6  491.87  5619.9  490.36  5671.7  494.89  6021.3  502.52
  6383.6  505.41    6503  504.59    6582  508.38  6752.5  510.31  7100.5   517.7
#Mann= 5 ,-1 , 0
  4024.4     .05       0  5013.7     .04       0  5018.8     .05       0
  5318.6     .12       0  5562.6     .05       0
Bank Sta=5013.7,5018.8
XS Rating Curve= 0 ,0
Exp/Cntr=0.3,0.1

Type RM Length L Ch R = 1 ,12000   ,500,500,500
BEGIN DESCRIPTION:
Kings Creek Trib 8 24.0
END DESCRIPTION:
XS GIS Cut Line= 3
      2663726.01        6969111.      2662908.33      6969660.92
        2661226.        6970511.
#Sta/Elev= 30
  4014.6   516.4  4244.1  504.88    4562  496.32    4808  491.87    4916  491.22
  4930.5  490.75    4958  485.97  4975.2  485.61  4976.4  485.11  4982.7  485.61
  4998.4  488.28  5009.7  486.89  5015.3  489.51  5095.7  489.15  5143.5  490.35
  5165.8  488.49  5181.9  490.13  5210.4  489.71  5316.2  492.81  5321.8  491.87
  5349.9  492.32  5388.7  494.57  5591.1  497.29  6051.8  502.35  6168.9   502.6
  6230.1  501.18  6324.9  504.88  6447.4  507.17  6475.3  509.54  6884.9  517.81
#Mann= 5 ,-1 , 0
  4014.6     .05       0  4975.2     .03       0  4982.7     .05       0
  5095.7     .12       0  5591.1     .05       0
Bank Sta=4975.2,4982.7
XS Rating Curve= 0 ,0
Exp/Cntr=0.3,0.1

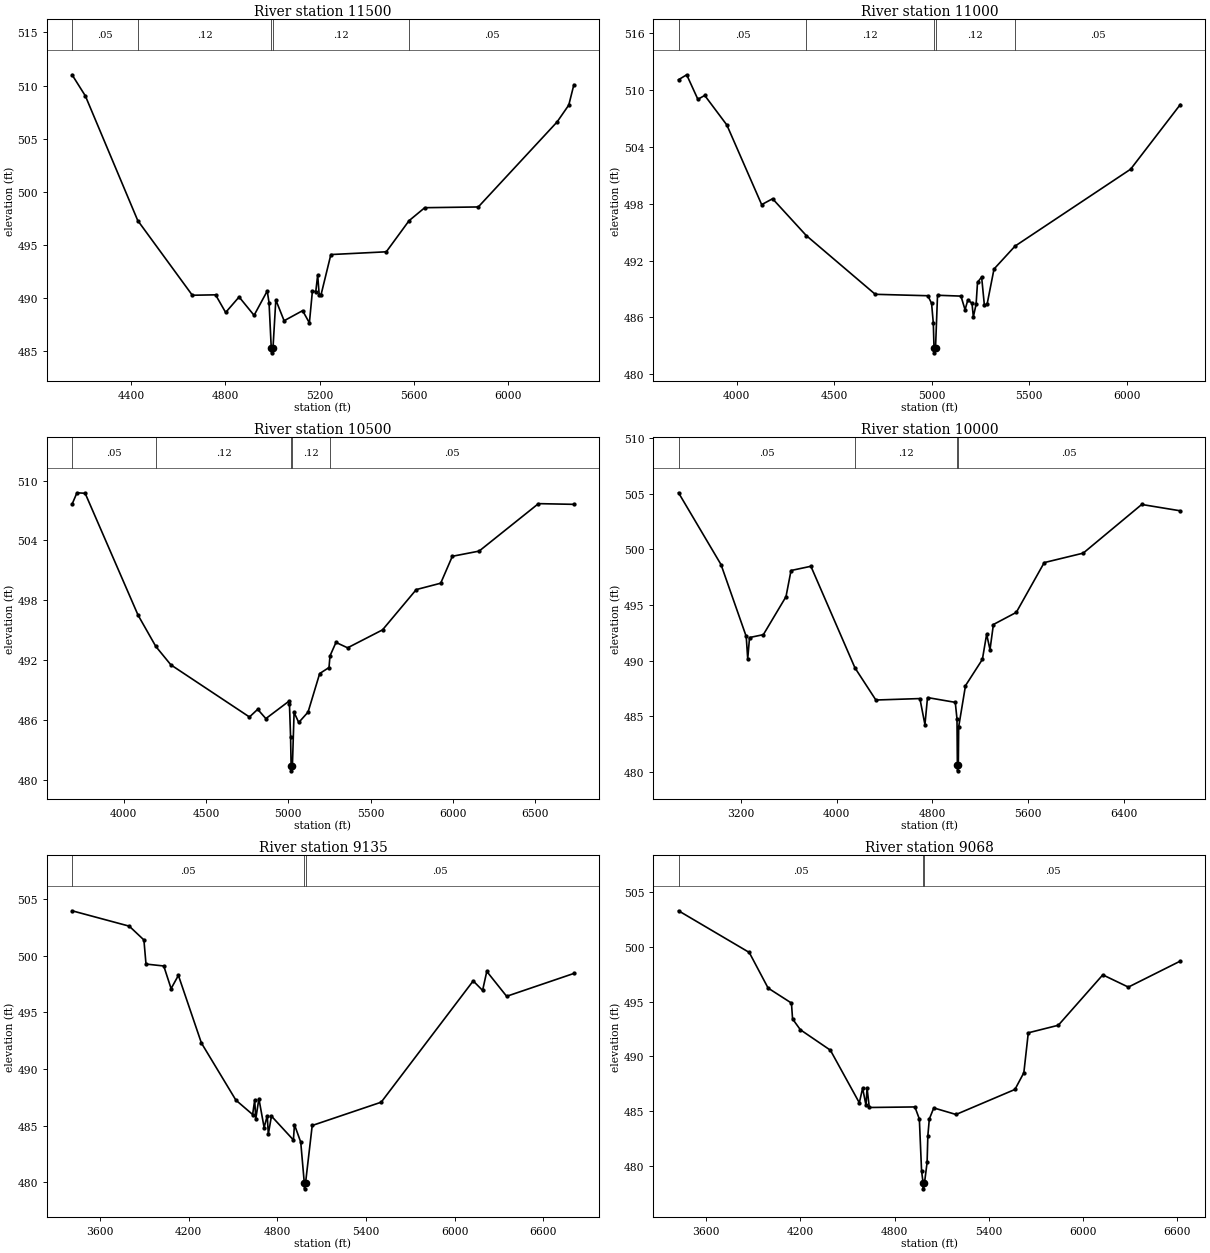
Type RM Length L Ch R = 1 ,11500   ,500,500,500
BEGIN DESCRIPTION:
Kings Creek Trib 8 23.0
END DESCRIPTION:
XS GIS Cut Line= 3
      2663175.99      6968861.01      2662528.78       6969414.5
      2661526.02      6970210.99
#Sta/Elev= 30
  4148.4  511.01  4204.9  509.02  4427.5  497.29  4659.4  490.26  4758.2   490.3
    4801  488.64  4858.1   490.1  4921.8  488.37  4977.7  490.66  4985.4  489.56
  4994.7  485.34  4995.9  484.84  5002.3  485.34  5014.2  489.82  5049.4  487.86
    5128  488.81  5156.8  487.66  5169.6  490.64    5184  490.61    5192  492.16
  5198.4  490.33  5206.5  490.32  5248.1  494.09  5483.6  494.35  5580.4  497.28
    5647   498.5  5874.5  498.57  6209.3  506.57    6259  508.16  6280.6  510.07
#Mann= 5 ,-1 , 0
  4148.4     .05       0  4427.5     .12       0  4994.7     .07       0
  5002.3     .12       0  5580.4     .05       0
Bank Sta=4994.7,5002.3
XS Rating Curve= 0 ,0
Exp/Cntr=0.3,0.1

Type RM Length L Ch R = 1 ,11000   ,500,500,500
BEGIN DESCRIPTION:
Kings Creek Trib 8 22.0
END DESCRIPTION:
XS GIS Cut Line= 3
      2663296.86      6968202.42      2662293.64      6969027.63
      2661425.97      6969961.03
#Sta/Elev= 30
    3701   511.1  3742.8  511.62  3800.2  509.03  3835.3  509.44  3948.7  506.32
  4127.3  497.91  4183.3  498.53  4356.3  494.64  4709.9  488.44  4979.6  488.29
  4998.7  487.49  5007.7  485.36  5011.2  482.76  5012.3  482.26  5018.9  482.76
  5029.2  488.34  5149.4  488.25  5170.4  486.81  5184.5  487.83    5206   487.5
  5212.9  486.06    5227  487.38  5234.4  489.71  5255.4  490.26  5269.6  487.27
  5283.7  487.42  5318.9  491.11  5426.8  493.53  6019.5  501.65  6274.4  508.48
#Mann= 5 ,-1 , 0
    3701     .05       0  4356.3     .12       0  5011.2     .07       0
  5018.9     .12       0  5426.8     .05       0
Bank Sta=5011.2,5018.9
XS Rating Curve= 0 ,0
Exp/Cntr=0.3,0.1

Type RM Length L Ch R = 1 ,10500   ,500,500,500
BEGIN DESCRIPTION:
Kings Creek Trib 8 21.0
END DESCRIPTION:
XS GIS Cut Line= 3
      2663058.14      6967950.69      2662016.74      6968752.15
      2660792.55      6969981.91
#Sta/Elev= 30
  3685.9  507.63  3715.6  508.78  3765.4  508.73  4087.1   496.5  4194.7  493.37
  4286.4  491.52  4763.9  486.29  4813.8  487.06  4863.6  486.13  5002.7  487.86
  5006.8  487.63  5013.8  484.28    5017  481.39  5018.2  480.89  5024.8  481.39
  5035.1  486.75  5063.3  485.74  5119.9  486.78  5190.6  490.65  5247.2  491.25
  5253.3  492.42  5289.6  493.77  5360.3  493.23  5572.5  495.03  5777.5  499.07
    5926  499.71  5996.7  502.41  6159.4  502.93    6520  507.69  6735.2  507.62
#Mann= 5 ,-1 , 0
  3685.9     .05       0  4194.7     .12       0    5017     .07       0
  5024.8     .12       0  5253.3     .05       0
Bank Sta=5017,5024.8
XS Rating Curve= 0 ,0
Exp/Cntr=0.3,0.1

Type RM Length L Ch R = 1 ,10000   ,865,865,865
BEGIN DESCRIPTION:
Kings Creek Trib 8 20.0
END DESCRIPTION:
XS GIS Cut Line= 3
      2663670.13      6967113.01      2661725.31      6968380.52
       2660480.5      6969781.75
#Sta/Elev= 30
  2678.6  505.09  3033.9  498.64  3244.5  492.19  3257.1  490.19  3272.3  492.09
  3387.8  492.35  3577.1  495.76  3619.3  498.11  3785.3  498.49  4153.6  489.37
  4328.6  486.48  4696.7  486.61  4738.9  484.27  4760.4   486.7  4992.5  486.27
  5006.9  484.78  5010.1  480.62  5011.3  480.12    5018  480.62  5021.1  484.08
    5078  487.77  5219.3  490.13  5254.8  492.39  5282.9     491  5311.3  493.26
  5502.8  494.35  5736.3  498.82  6062.3  499.67  6551.5  504.04  6874.3  503.47
#Mann= 4 ,-1 , 0
  2678.6     .05       0  4153.6     .12       0  5010.1     .07       0
    5018     .05       0
Bank Sta=5010.1,5018
XS Rating Curve= 0 ,0
Exp/Cntr=0.3,0.1

Type RM Length L Ch R = 1 ,9135    ,67,67,67
BEGIN DESCRIPTION:
Mapping XS aa221722
END DESCRIPTION:
XS GIS Cut Line= 3
       2662741.3      6966579.17      2661591.16      6967685.91
      2660315.13      6968953.26
#Sta/Elev= 30
  3411.1  503.99    3798  502.63  3897.1  501.41  3911.2  499.28  4031.4  499.11
    4081  497.11  4130.4  498.28  4286.1   492.3  4519.4  487.25  4632.6  485.98
  4646.7  487.27  4653.7  485.58    4675  487.38  4710.3  484.83  4731.6  485.88
  4738.6  484.24  4759.9  485.84  4908.4  483.73  4915.6  485.08    4958  483.54
  4982.2  479.91  4983.5  479.41  4990.4  479.91  5035.7  485.01  5502.4  487.07
  6124.7  497.79  6188.3  496.95  6216.6  498.63    6351  496.43  6805.7  498.45
#Mann= 3 ,-1 , 0
  3411.1     .05       0  4982.2     .05       0  4990.4     .05       0
Bank Sta=4982.2,4990.4
XS Rating Curve= 0 ,0
Exp/Cntr=0.3,0.1

Type RM Length L Ch R = 1 ,9068    ,568,568,568
BEGIN DESCRIPTION:
Mapping XS 455b0cb4
END DESCRIPTION:
XS GIS Cut Line= 3
      2662693.61      6966553.07      2661539.07      6967642.51
      2660380.62      6968753.23
#Sta/Elev= 30
  3425.7   503.3  3875.5  499.49  3995.6  496.23  4144.1  494.86  4151.1  493.41
  4200.7  492.42  4391.7  490.55  4575.8  485.74  4596.8  487.07  4618.2  485.52
  4625.1  487.08  4639.3  485.31  4929.4  485.36  4957.7  484.26  4971.8  479.52
  4981.9  478.37  4983.1  477.87  4990.1  478.37    5007  480.28  5011.8  482.73
  5021.2  484.26  5049.5  485.27    5191  484.67  5565.9  486.96  5622.5  488.49
  5650.8  492.14  5841.7  492.83  6124.7  497.44  6287.3  496.32    6618   498.7
#Mann= 3 ,-1 , 0
  3425.7     .05       0  4981.9    .085       0  4990.1     .05       0
Bank Sta=4981.9,4990.1
XS Rating Curve= 0 ,0
Exp/Cntr=0.3,0.1

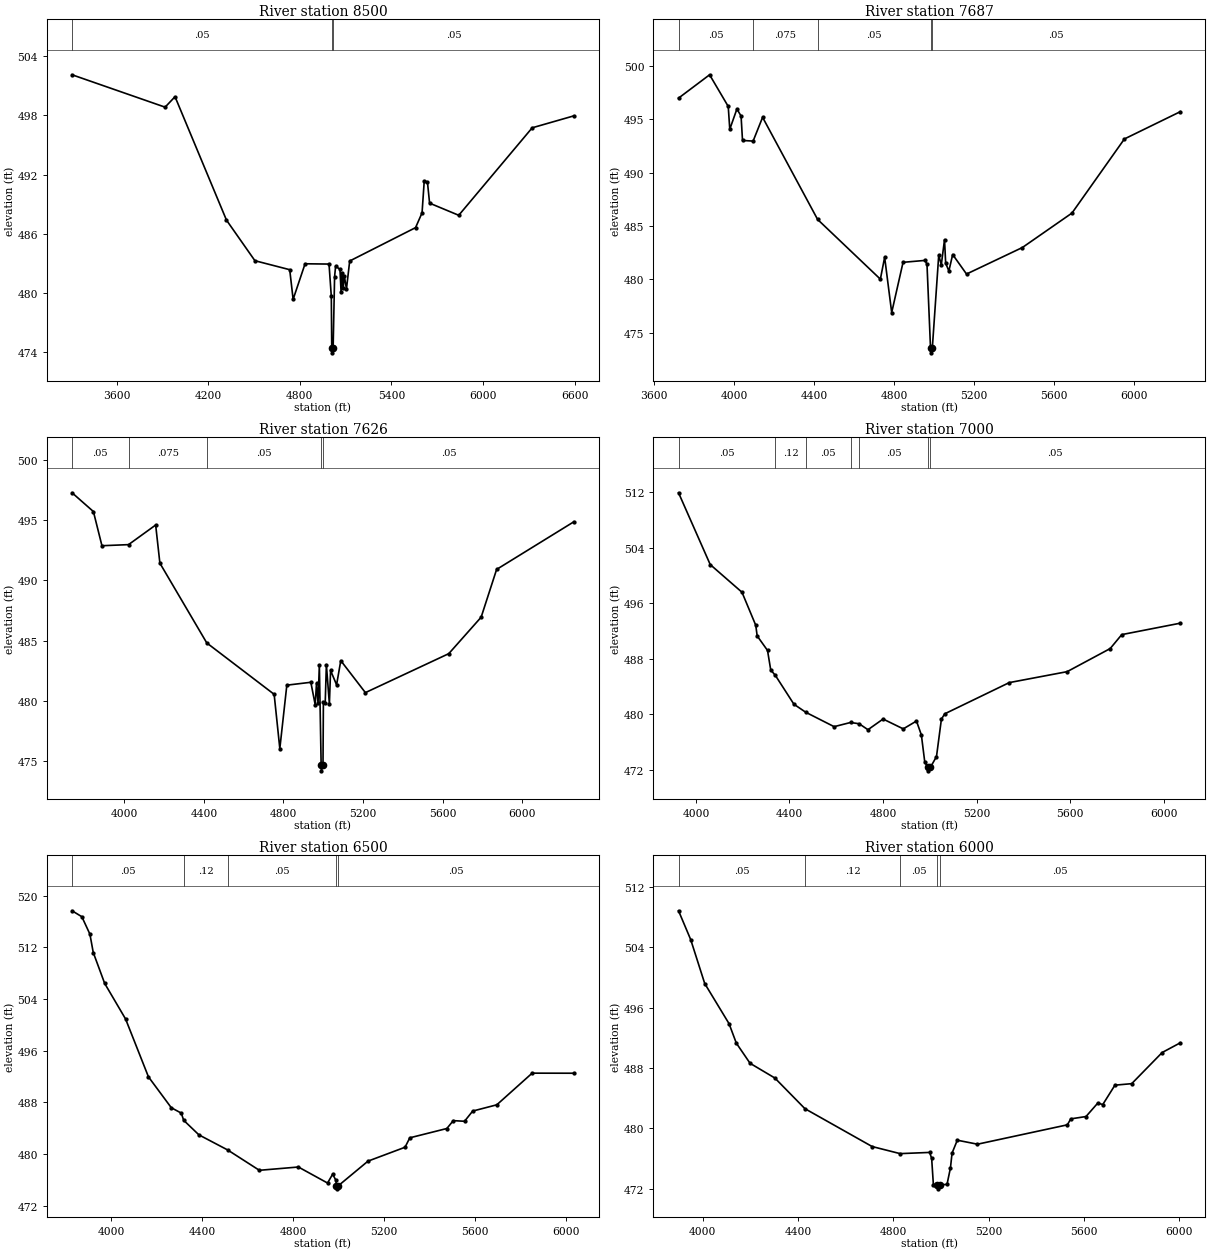
Type RM Length L Ch R = 1 ,8500    ,813,813,813
BEGIN DESCRIPTION:
Kings Creek Trib 8 17.0
END DESCRIPTION:
XS GIS Cut Line= 3
      2662498.29      6966270.97      2661128.84      6967264.19
      2659963.56      6968354.31
#Sta/Elev= 30
  3308.3  502.12  3917.8  498.84  3982.8   499.9  4319.9   487.4  4506.2  483.29
  4734.2  482.38  4756.5  479.38  4834.8  482.98  4991.7  482.95  5006.7  479.67
  5009.5  474.46  5010.8  473.96  5018.6  474.46  5028.2  481.68    5035  482.74
  5063.4  482.41  5070.7  480.11  5077.5  482.09  5084.8  480.51  5091.7  481.77
  5105.9  480.43  5127.1  483.26  5558.7  486.64  5601.2  488.14  5615.4  491.35
  5636.4  491.27  5650.5  489.12  5841.5  487.89  6322.7  496.75  6595.7  497.96
#Mann= 3 ,-1 , 0
  3308.3     .05       0  5009.5     .03       0  5018.6     .05       0
Bank Sta=5009.5,5018.6
XS Rating Curve= 0 ,0
Exp/Cntr=0.3,0.1

Type RM Length L Ch R = 1 ,7687    ,61,61,61
BEGIN DESCRIPTION:
Mapping XS 19188a42
END DESCRIPTION:
XS GIS Cut Line= 6
      2661947.09      6965893.35      2661417.54      6966310.04
      2661087.68      6966622.54      2660961.82      6966687.65
       2660766.5      6966791.81      2660059.99        6967520.
#Sta/Elev= 30
  3723.2  496.99  3878.3  499.18  3971.4  496.21  3979.1  494.07  4014.7  495.97
  4035.5  495.31  4042.7  493.02  4095.6  492.96    4143  495.19  4417.8  485.61
  4731.1  480.01  4752.5  482.06  4787.7  476.88  4844.4  481.59  4954.6  481.77
    4964  481.39  4981.5   473.6  4982.9   473.1  4990.8   473.6  5022.6  482.26
  5035.5  481.36  5051.5  483.72  5057.3   481.5  5073.3  480.78  5092.2  482.32
  5161.4  480.49  5440.5  482.98    5688  486.21  5949.8  493.16  6229.1  495.72
#Mann= 5 ,-1 , 0
  3723.2     .05       0  4095.6    .075       0  4417.8     .05       0
  4981.5     .04       0  4990.8     .05       0
Bank Sta=4981.5,4990.8
XS Rating Curve= 0 ,0
Exp/Cntr=0.3,0.1

Type RM Length L Ch R = 1 ,7626    ,626,626,626
BEGIN DESCRIPTION:
Mapping XS a285a54c
END DESCRIPTION:
XS GIS Cut Line= 5
      2661886.29       6965819.6      2661313.38       6966305.7
      2660931.43      6966635.56      2660666.68      6966809.17
      2659985.23      6967468.91
#Sta/Elev= 30
    3738  497.29  3845.2  495.73  3888.1  492.89  4021.7  492.98    4158  494.61
  4179.2  491.44  4414.8  484.81  4753.3  480.54  4781.8  476.03    4817   481.3
  4937.6  481.54  4959.5  479.68  4966.1  481.44  4973.8  479.83  4980.4  482.97
  4989.4  474.68  4990.7  474.18  4998.7  474.68  5000.7  479.86  5009.8  479.81
  5015.7  483.01  5030.8  479.73  5036.8  482.52    5067  481.33  5088.1  483.34
  5211.7  480.68  5630.7  483.92  5793.3  486.95    5871  490.92  6259.1  494.88
#Mann= 5 ,-1 , 0
    3738     .05       0  4021.7    .075       0  4414.8     .05       0
  4989.4     .04       0  4998.7     .05       0
Bank Sta=4989.4,4998.7
XS Rating Curve= 0 ,0
Exp/Cntr=0.3,0.1

Type RM Length L Ch R = 1 ,7000    ,500,500,500
BEGIN DESCRIPTION:
Kings Creek Trib 8 14.0
END DESCRIPTION:
XS GIS Cut Line= 3
      2661076.01      6965410.99      2660448.44      6966283.05
       2659668.4      6967017.52
#Sta/Elev= 30
  3925.6   511.9  4061.1  501.55  4196.9  497.56  4255.8   492.8  4261.9  491.26
  4306.1  489.17  4319.9  486.35  4339.5  485.58  4419.1  481.41  4469.9  480.25
  4590.9  478.18  4661.1  478.78  4697.8   478.6  4735.7  477.74  4800.3  479.28
  4886.6  477.86  4943.1  478.99    4964  476.99  4978.7  473.04    4993  472.31
  4994.4  471.81  5002.6  472.31  5028.7  473.87  5049.7  479.26  5063.9  480.03
  5339.8  484.53  5587.4  486.11  5771.5  489.44  5820.9  491.45  6071.4   493.1
#Mann= 7 ,-1 , 0
  3925.6     .05       0  4339.5     .12       0  4469.9     .05       0
  4661.1     .12       0  4697.8     .05       0    4993     .03       0
  5002.6     .05       0
Bank Sta=4993,5002.6
XS Rating Curve= 0 ,0
Exp/Cntr=0.3,0.1

Type RM Length L Ch R = 1 ,6500    ,500,500,500
BEGIN DESCRIPTION:
Kings Creek Trib 8 13.0
END DESCRIPTION:
XS GIS Cut Line= 3
      2661076.03      6965260.98      2660127.38      6965948.52
      2659355.95      6966639.87
#Sta/Elev= 30
  3828.4  517.64  3871.4  516.72  3906.9  514.02  3921.6  511.18  3971.9  506.39
  4063.9  500.88  4164.4  491.93  4264.9  487.15    4309  486.31  4319.2  485.21
  4386.3  482.95  4512.9  480.61  4652.3  477.46    4824  477.97  4952.3  475.49
  4974.8  476.86  4989.4  475.89  4990.8  475.09  4992.2  474.59  5000.4  475.09
  5130.3  478.88  5293.2  481.03  5314.2  482.49  5477.1  483.93  5505.5  485.15
  5554.9  485.05  5590.8  486.63  5696.9   487.6  5852.4   492.5  6035.9  492.49
#Mann= 5 ,-1 , 0
  3828.4     .05       0  4319.2     .12       0  4512.9     .05       0
  4990.8     .03       0  5000.4     .05       0
Bank Sta=4990.8,5000.4
XS Rating Curve= 0 ,0
Exp/Cntr=0.3,0.1

Type RM Length L Ch R = 1 ,6000    ,819,819,819
BEGIN DESCRIPTION:
Kings Creek Trib 8 12.0
END DESCRIPTION:
XS GIS Cut Line= 3
      2660876.02      6964960.99       2659921.5      6965511.52
      2659143.21      6966145.14
#Sta/Elev= 30
  3898.1  508.87  3949.1  505.05    4008  499.22    4110   493.9  4140.5  491.32
  4198.3  488.64  4302.2  486.69  4428.5  482.62  4710.4   477.6  4827.8  476.66
  4951.7  476.82  4960.2  476.03  4967.4  472.55  4984.1  472.49  4985.5  471.99
  4993.8  472.49  5024.7  472.59  5039.1  474.78  5045.8  476.73  5067.8  478.44
  5152.5  477.91  5529.6  480.48  5543.9  481.27  5607.8  481.58  5657.4  483.37
  5678.2  483.17  5729.2  485.74  5799.6  485.94  5927.4  490.07  6003.6  491.36
#Mann= 5 ,-1 , 0
  3898.1     .05       0  4428.5     .12       0  4827.8     .05       0
  4984.1     .03       0  4993.8     .05       0
Bank Sta=4984.1,4993.8
XS Rating Curve= 0 ,0
Exp/Cntr=0.3,0.1