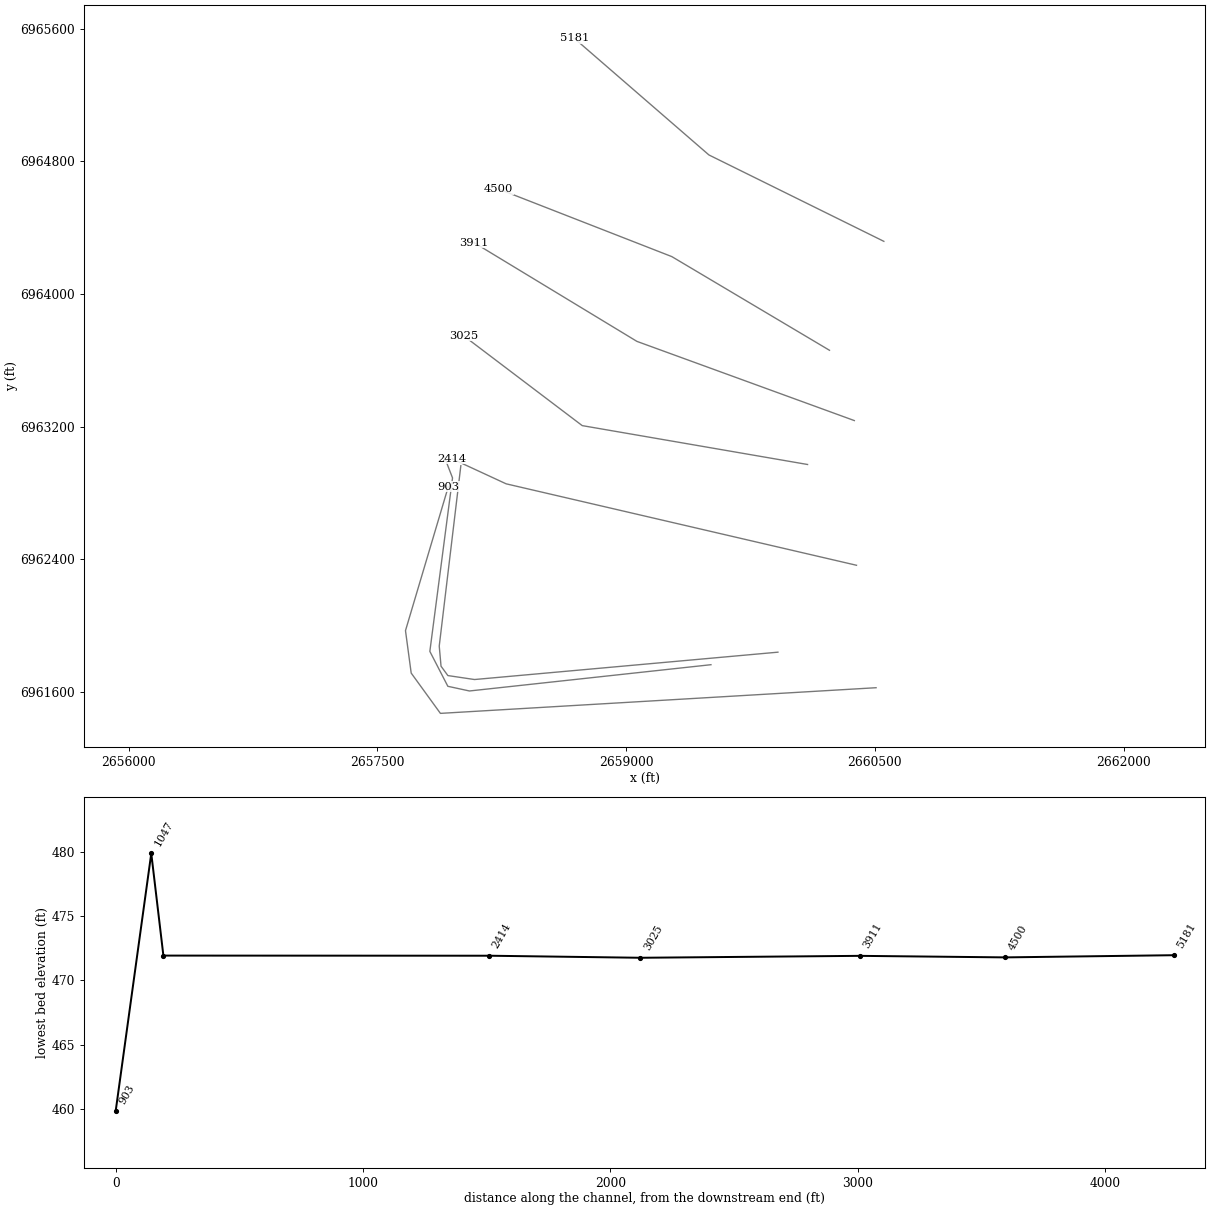
HEC-RAS study Kings Creek Trib 8.prj: Kings Creek Trib 8 Base Level Engineering

--- Kings Creek Trib 8.g01 (geometry) --- (continued)

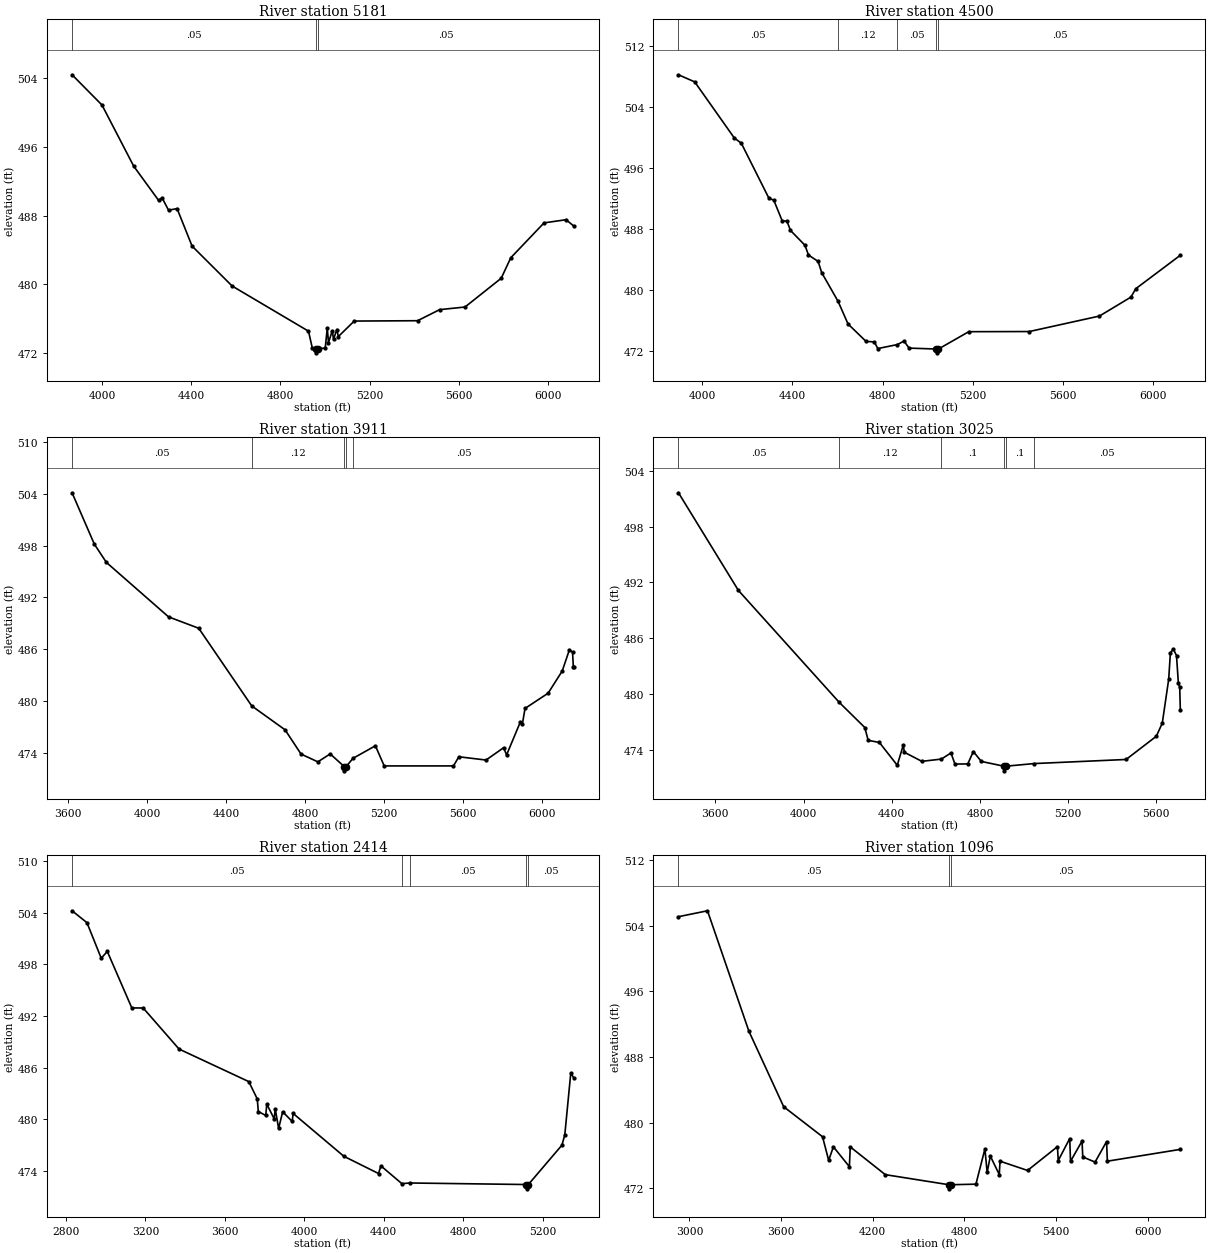
Type RM Length L Ch R = 1 ,5181    ,681,681,681
BEGIN DESCRIPTION:
Mapping XS 17d00e0c
END DESCRIPTION:
XS GIS Cut Line= 3
      2660553.81      6964317.86      2659499.14      6964838.69
      2658687.51      6965541.82
#Sta/Elev= 30
  3865.7  504.43  3999.8   500.9  4142.1  493.76  4253.6  489.77  4269.2  490.07
  4298.2  488.62  4336.5  488.81  4403.8  484.43  4583.4  479.77  4925.7   474.5
  4942.5  472.57    4960  472.47  4961.4  471.97  4969.9  472.47  5000.8  472.52
  5009.9  474.86  5015.4  473.17  5032.3  474.55  5037.9  473.56  5052.9  474.69
  5059.5  473.87  5130.8  475.68  5414.8  475.72  5513.5  477.01  5627.6  477.32
  5789.9  480.68  5832.7  483.07  5981.8  487.14  6080.5  487.51  6115.8  486.76
#Mann= 3 ,-1 , 0
  3865.7     .05       0    4960     .03       0  4969.9     .05       0
Bank Sta=4960,4969.9
XS Rating Curve= 0 ,0
Exp/Cntr=0.3,0.1

Type RM Length L Ch R = 1 ,4500    ,589,589,589
BEGIN DESCRIPTION:
Kings Creek Trib 8 9.0
END DESCRIPTION:
XS GIS Cut Line= 3
      2660225.99      6963661.01      2659275.59       6964225.7
      2658231.95        6964633.
#Sta/Elev= 30
  3894.5  508.22  3966.5  507.29  4141.9  499.95  4173.1  499.26  4295.8  492.04
  4317.2   491.8  4354.2  489.11  4375.7  489.04  4391.3  487.83  4455.5  485.89
  4471.1  484.61    4514  483.77  4529.6  482.31  4602.3  478.55  4646.5  475.58
  4726.3   473.3  4763.4  473.23  4778.5  472.36  4865.1  472.88  4894.8  473.34
  4917.3  472.42  5037.5   472.3  5038.9   471.8  5047.5   472.3    5182  474.57
  5450.4  474.59  5761.7  476.62  5901.3   479.1  5922.7   480.2  6120.3  484.58
#Mann= 5 ,-1 , 0
  3894.5     .05       0  4602.3     .12       0  4865.1     .05       0
  5037.5     .04       0  5047.5     .05       0
Bank Sta=5037.5,5047.5
XS Rating Curve= 0 ,0
Exp/Cntr=0.3,0.1

Type RM Length L Ch R = 1 ,3911    ,886,886,886
BEGIN DESCRIPTION:
Mapping XS 2cd23b27
END DESCRIPTION:
XS GIS Cut Line= 3
      2660375.84      6963237.14      2659065.11      6963714.56
      2658084.23      6964309.16
#Sta/Elev= 30
  3620.3  504.12  3732.9  498.18    3794  496.06    4109  489.75  4261.9  488.43
  4530.3  479.44  4699.2  476.67  4780.2  473.86  4865.3  472.96  4927.8  473.88
  4998.6  472.42    5000  471.92  5008.7  472.42  5043.4  473.37  5156.7  474.82
  5201.3  472.49  5552.2  472.49  5579.4  473.55  5717.1  473.17  5806.3   474.6
  5821.1  473.76  5891.6  477.61  5901.3  477.35  5914.7  479.15  6031.6  480.91
    6103  483.48  6139.8  485.96  6155.3  485.65  6159.3     484  6162.3     484
#Mann= 5 ,-1 , 0
  3620.3     .05       0  4530.3     .12       0  4998.6     .07       0
  5008.7     .12       0  5043.4     .05       0
Bank Sta=4998.6,5008.7
XS Rating Curve= 0 ,0
Exp/Cntr=0.3,0.1

Type RM Length L Ch R = 1 ,3025    ,611,611,611
BEGIN DESCRIPTION:
Mapping XS b7a5a564
END DESCRIPTION:
XS GIS Cut Line= 3
      2660093.78      6962972.37      2658735.25      6963206.74
      2658020.02      6963748.59
#Sta/Elev= 30
  3432.9  501.62  3704.6  491.14  4161.6  479.13  4277.9  476.42  4293.2  475.04
  4343.9  474.82  4425.1  472.37  4452.3  474.53  4457.4  473.76  4536.7  472.79
  4624.9  473.03  4668.7  473.69  4686.7   472.5  4744.8  472.51  4770.1  473.84
  4806.4  472.78  4908.3  472.27  4909.7  471.77  4918.6  472.27  5045.4  472.55
  5462.9  472.99  5599.9  475.48    5627  476.89  5656.1  481.61  5663.7  484.43
  5676.9  484.86  5691.5  484.14  5699.8  481.22    5706  480.74  5708.8  478.32
#Mann= 6 ,-1 , 0
  3432.9     .05       0  4161.6     .12       0  4624.9      .1       0
  4908.3     .07       0  4918.6      .1       0  5045.4     .05       0
Bank Sta=4908.3,4918.6
XS Rating Curve= 0 ,0
Exp/Cntr=0.3,0.1

Type RM Length L Ch R = 1 ,2414    ,1318,1318,1318
BEGIN DESCRIPTION:
Mapping XS 06baa6ff
END DESCRIPTION:
XS GIS Cut Line= 3
      2660388.94      6962364.72      2658276.38      6962855.84
       2657951.5      6963006.24
#Sta/Elev= 30
  2831.1  504.22    2906  502.84  2977.9  498.71  3008.5   499.5  3131.9  492.94
  3189.2  492.93  3369.9  488.16  3721.1  484.38  3763.7  482.36  3768.8  480.91
  3806.3  480.45  3811.5  481.76  3848.9  480.06  3854.1  481.22  3871.1  478.95
  3891.5  480.88  3939.3  479.76  3944.4  480.68  4199.6  475.71  4374.1  473.71
    4386   474.6  4491.8  472.53  4531.5  472.61    5118  472.43  5119.5  471.93
  5128.5  472.43  5297.9  477.01  5312.1  478.21    5342  485.34    5358  484.81
#Mann= 5 ,-1 , 0
  2831.1     .05       0  4491.8      .1       0  4531.5     .05       0
    5118     .03       0  5128.5     .05       0
Bank Sta=5118,5128.5
XS Rating Curve= 0 ,0
Exp/Cntr=0.3,0.1

Type RM Length L Ch R = 1 ,1096    ,49,49,49
BEGIN DESCRIPTION:
Mapping XS 65e0057c
END DESCRIPTION:
XS GIS Cut Line= 6
      2659915.19      6961840.77      2658085.77      6961675.84
      2657925.18      6961699.71      2657883.95      6961756.13
       2657873.1      6961877.66      2658003.31      6962964.94
#Sta/Elev= 30
    2928  505.11    3118  505.83  3389.2  491.15  3616.9  481.95  3871.3  478.29
  3911.5  475.42  3942.6  477.06  4047.1  474.64  4052.9  477.05  4282.3  473.67
  4699.1  472.44  4700.6  471.94  4709.8  472.44  4875.8  472.51  4934.7   476.8
  4949.3  473.94  4970.2  475.93  5028.7  473.68  5033.7  475.31  5213.8  474.18
  5409.7  477.08  5414.8  475.39  5490.1  478.07  5495.2  475.29  5570.6  477.76
  5575.6  475.83    5656   475.2  5731.4   477.7  5736.5  475.31  6214.3  476.75
#Mann= 3 ,-1 , 0
    2928     .05       0  4699.1     .04       0  4709.8     .05       0
Bank Sta=4699.1,4709.8
XS Rating Curve= 0 ,0
Exp/Cntr=0.3,0.1

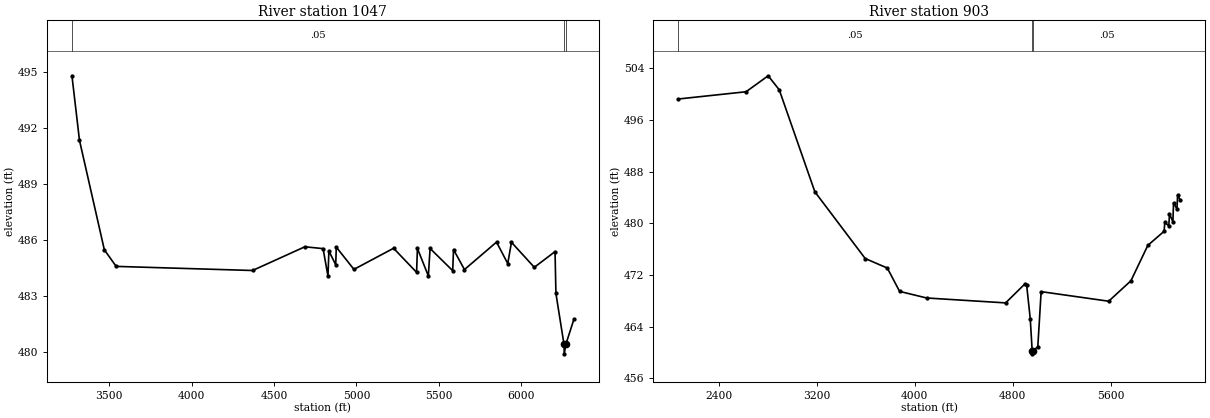
Type RM Length L Ch R = 1 ,1047    ,144,144,144
BEGIN DESCRIPTION:
Mapping XS eaed04eb
END DESCRIPTION:
XS GIS Cut Line= 6
      2659511.31      6961765.22      2658055.19      6961606.81
      2657924.98      6961635.02      2657816.47      6961845.52
      2657953.19      6962891.53      2657901.14      6963026.01
#Sta/Elev= 30
  3273.2  494.79  3318.8  491.34  3469.7  485.48  3541.5  484.59  4369.2  484.37
  4686.8  485.64  4797.2  485.54  4826.9  484.07  4832.5  485.41  4873.9  484.68
  4877.4  485.62  4984.5  484.43    5225  485.56  5364.7  484.27  5369.7  485.55
  5436.1  484.08  5446.6  485.55  5583.9  484.36  5588.9  485.49  5655.2  484.42
  5849.9  485.89    5918  484.74  5940.4  485.88  6079.1  484.54  6204.9  485.38
  6210.3  483.14  6259.4  480.41  6260.9  479.91  6270.1  480.41  6319.1  481.75
#Mann= 3 ,-1 , 0
  3273.2     .05       0  6259.4     .04       0  6270.1     .05       0
Bank Sta=6259.4,6270.1
XS Rating Curve= 0 ,0
Exp/Cntr=0.3,0.1

Type RM Length L Ch R = 1 ,903     ,0,0,0
BEGIN DESCRIPTION:
Kings Creek Trib 8 8.0
END DESCRIPTION:
XS GIS Cut Line= 5
      2660506.93      6961626.48       2657880.2      6961471.75
      2657704.01      6961714.66      2657669.58       6961970.6
      2657927.33      6962837.17
#Sta/Elev= 30
  2072.7  499.22  2624.6  500.34  2804.9  502.81  2895.1  500.64  3185.6  484.86
  3596.3  474.54  3776.5  473.07  3876.8  469.46  4097.1  468.44  4741.5  467.68
  4900.7  470.65  4913.1  470.41  4942.5  465.21    4958   460.3  4959.5   459.8
  4968.7   460.3  5004.1  460.92  5031.2  469.42    5582  467.94  5763.5   471.1
  5901.5  476.58  6034.3  478.76  6039.5  480.14  6072.7   479.6  6077.9  481.46
  6105.8  480.23  6111.1  483.15    6139  482.19  6144.3  484.36  6166.4  483.57
#Mann= 3 ,-1 , 0
  2072.7     .05       0    4958     .04       0  4968.7     .05       0
Bank Sta=4958,4968.7
XS Rating Curve= 0 ,0
Exp/Cntr=0.3,0.1

Chan Stop Cuts=-1
Use User Specified Reach Order=0
Composite Channel Slope=5