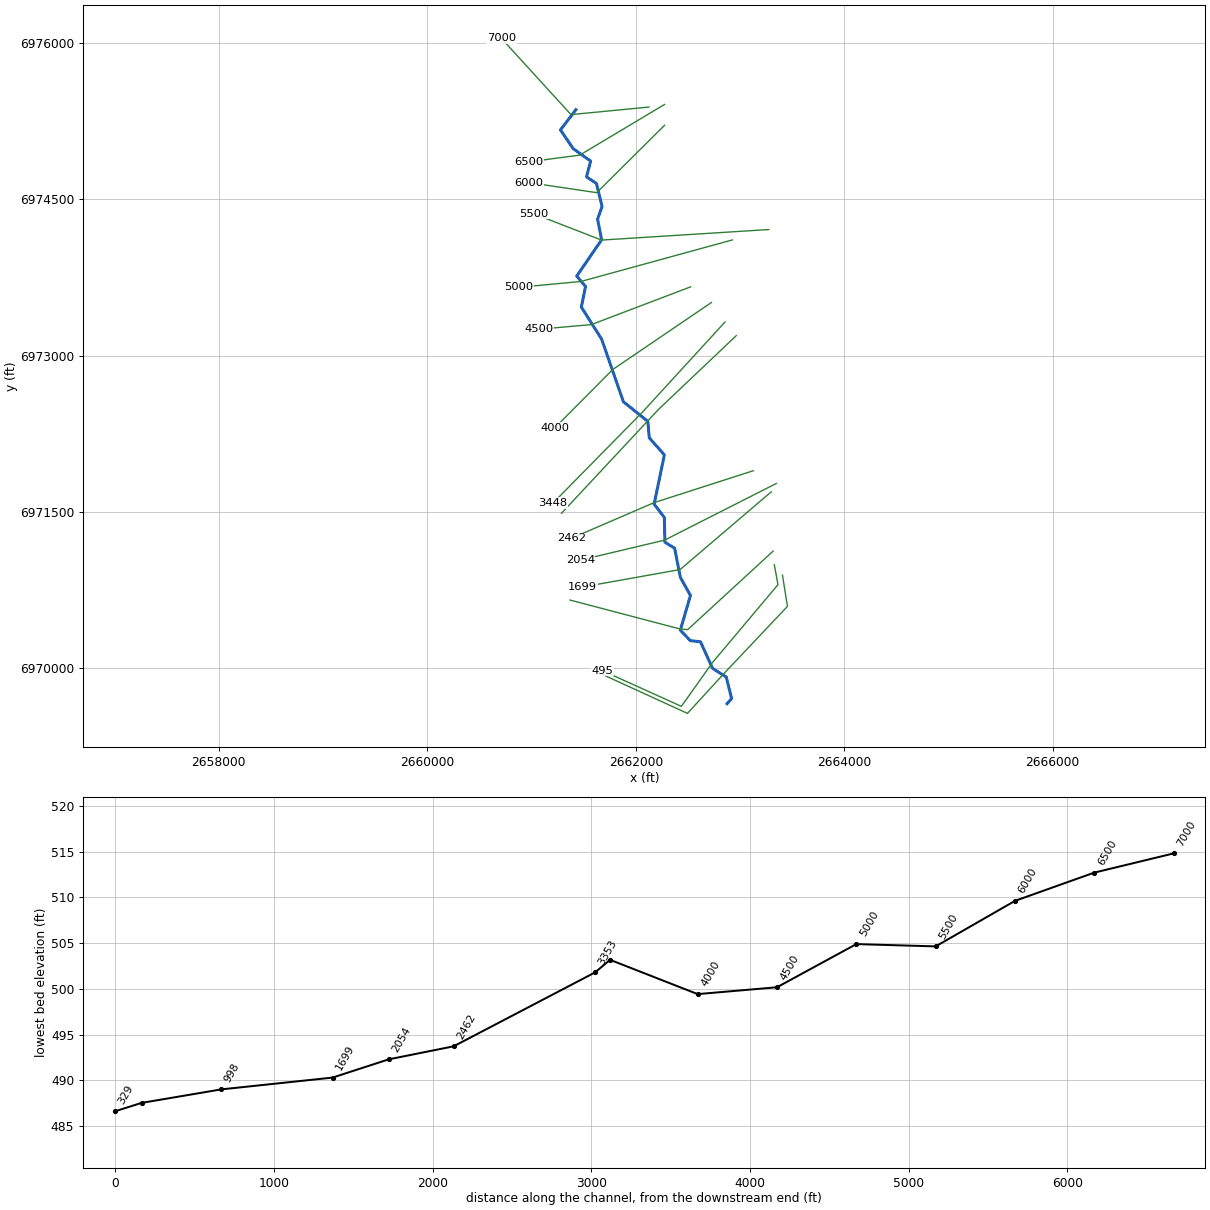
--- Kings Creek Trib 8_1.prj (project) ---

Proj Title=Kings Creek Trib 8_1 Base Level Engineering
Current Plan=p01
Default Exp/Contr=0.3,0.1
English Units
Geom File=g01
Flow File=f01
Plan File=p01
BEGIN DESCRIPTION:
Kings Creek Trib 8_1
END DESCRIPTION:

--- Kings Creek Trib 8_1.p01 (plan) ---

Plan Title=Multiple Run
Short Identifier=Multiple
Geom File=g01
Flow File=f01
Subcritical Flow
K Sum by GR= 0
Std Step Tol= 0.01
Critical Tol= 0.01
Num of Std Step Trials= 20
Max Error Tol= 0.3
Flow Tol Ratio= 0.001
Split Flow NTrial= 30
Split Flow Tol= 0.02
Split Flow Ratio= 0.02
Log Output Level= 0
Friction Slope Method= 1
Unsteady Friction Slope Method= 2
Unsteady Bridges Friction Slope Method= 1
Parabolic Critical Depth
Global Vel Dist=  1 , 1 , 1
Global Log Level= 0
CheckData=True
Encroach Param= -1, 0, 0, 0
BEGIN DESCRIPTION:
Multiple Run
END DESCRIPTION:

--- Kings Creek Trib 8_1.f01 (steady flow) ---

Flow Title=Multiple
Number of Profiles=7
Profile Names=10-year,25-year,50-year,1pct_min,100-year,1pct_plu,500-year
River Rch & RM= Kings Creek Trib,Reach-1,7000
     500     657     781     461     920    1835    1273
River Rch & RM= Kings Creek Trib,Reach-1,4000
     595     791     948     563    1124    2242    1578
River Rch & RM= Kings Creek Trib,Reach-1,998
     605     805     965     573    1143    2281    1605
Boundary for River Rch & Prof#=Kings Creek Trib,Reach-1,1
Up Type=0
Dn Type=3
Dn Slope=0.005
Boundary for River Rch & Prof#=Kings Creek Trib,Reach-1,2
Up Type=0
Dn Type=3
Dn Slope=0.005
Boundary for River Rch & Prof#=Kings Creek Trib,Reach-1,3
Up Type=0
Dn Type=3
Dn Slope=0.005
Boundary for River Rch & Prof#=Kings Creek Trib,Reach-1,4
Up Type=0
Dn Type=3
Dn Slope=0.005
Boundary for River Rch & Prof#=Kings Creek Trib,Reach-1,5
Up Type=0
Dn Type=3
Dn Slope=0.005
Boundary for River Rch & Prof#=Kings Creek Trib,Reach-1,6
Up Type=0
Dn Type=3
Dn Slope=0.005
Boundary for River Rch & Prof#=Kings Creek Trib,Reach-1,7
Up Type=0
Dn Type=3
Dn Slope=0.005

--- Kings Creek Trib 8_1.g01 (geometry) ---

Geom Title=Existing Conditions

River Reach=Kings Creek Trib,Reach-1
Reach XY= 30
      2661426.00      6975361.00      2661277.59      6975167.05
      2661398.99      6974987.49      2661566.99      6974868.02
      2661527.92      6974716.72      2661622.89      6974652.68
      2661676.58      6974431.04      2661633.56      6974311.00
      2661672.26      6974112.56      2661433.62      6973764.33
      2661517.99      6973664.33      2661477.84      6973467.13
      2661672.38      6973159.50      2661881.42      6972558.33
      2662115.52      6972370.80      2662129.76      6972212.56
      2662274.36      6972049.17      2662176.07      6971576.37
      2662274.08      6971449.05      2662279.48      6971212.26
      2662372.81      6971152.65      2662427.98      6970872.97
      2662524.80      6970700.48      2662427.65      6970367.04
      2662523.62      6970266.55      2662620.89      6970255.89
      2662736.65      6970001.01      2662868.30      6969917.47
      2662919.09      6969710.86      2662876.00      6969661.00

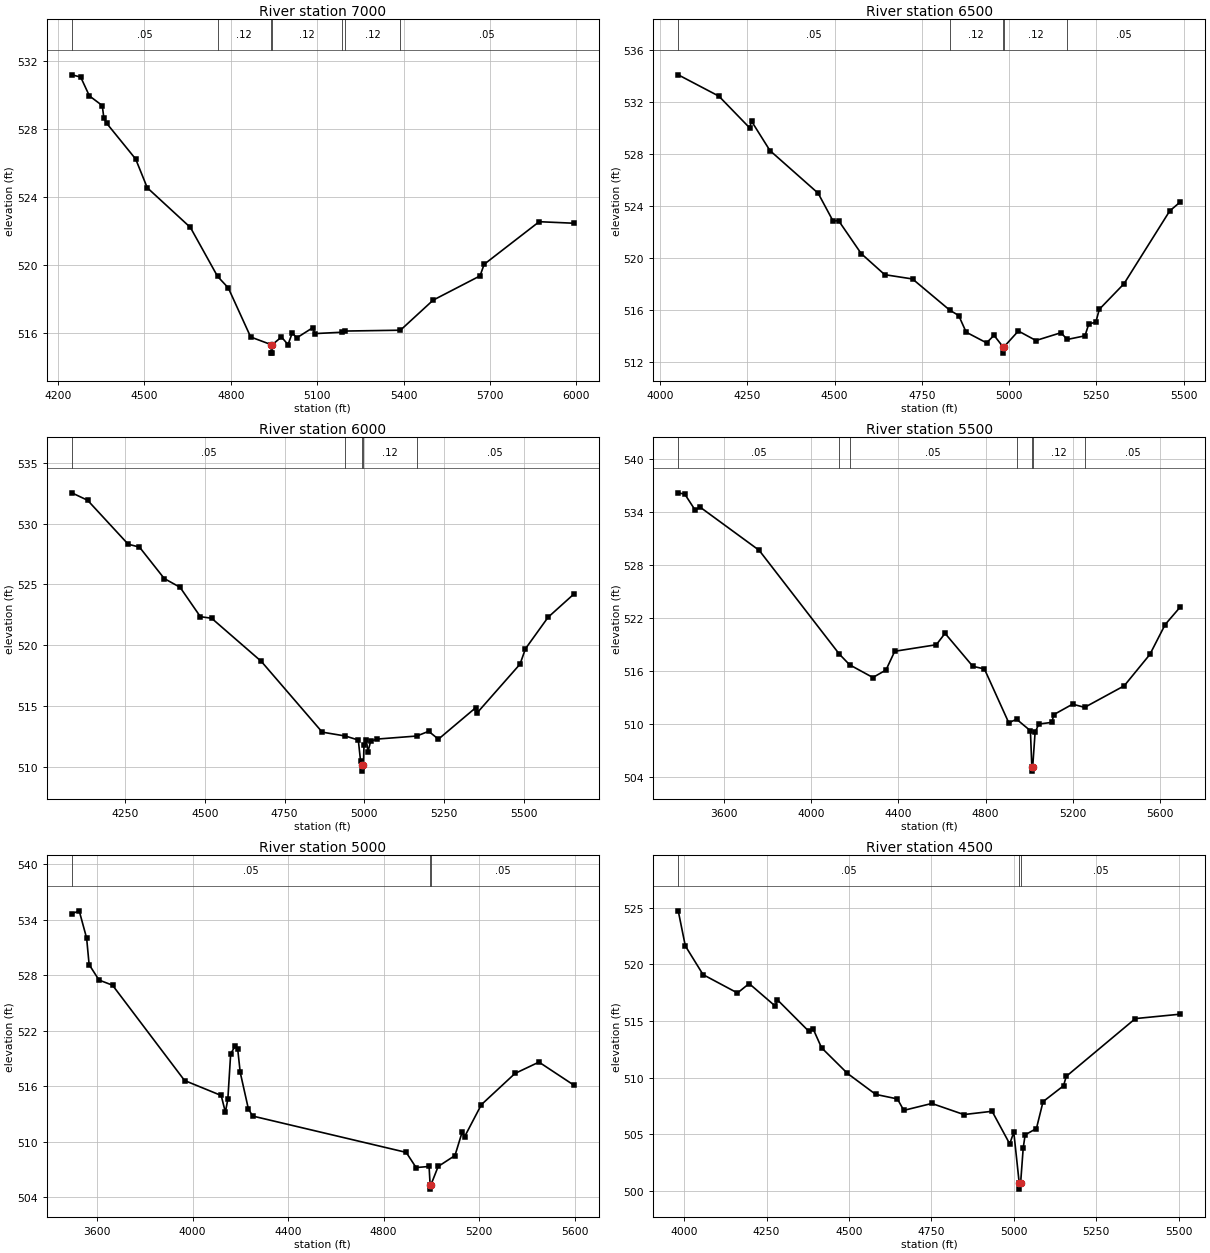
Type RM Length L Ch R = 1,7000,500,500,500
BEGIN DESCRIPTION:
Kings Creek Trib 8_1 13.0
END DESCRIPTION:
XS GIS Cut Line= 3
      2662126.79      6975386.16      2661378.50      6975313.57
      2660710.59      6976045.40
#Sta/Elev= 30
  4248.2  531.20  4279.1  531.07  4309.3  529.96  4354.0  529.39  4359.5  528.67
  4369.6  528.34  4470.0  526.24  4510.2  524.55  4660.0  522.21  4754.2  519.33
  4791.5  518.65  4869.1  515.76  4940.2  515.31  4940.5  514.81  4944.0  514.81
  4944.2  515.31  4976.1  515.76  4998.7  515.31  5014.0  516.02  5028.2  515.70
  5084.9  516.31  5091.7  515.96  5185.2  516.04  5196.2  516.11  5388.9  516.16
  5502.4  517.93  5665.3  519.36  5679.4  520.04  5870.6  522.55  5990.8  522.46
#Mann=7,-1,0
  4248.2    0.05       0  4754.2    0.12       0  4940.2    0.07       0
  4944.2    0.12       0  5185.2    0.05       0  5196.2    0.12       0
  5388.9    0.05       0
Bank Sta=4940.2,4944.2
Exp/Cntr=0.3,0.1

Type RM Length L Ch R = 1,6500,500,500,500
BEGIN DESCRIPTION:
Kings Creek Trib 8_1 12.0
END DESCRIPTION:
XS GIS Cut Line= 3
      2662276.01      6975411.00      2661462.48      6974924.89
      2660975.95      6974860.99
#Sta/Elev= 30
  4052.3  534.10  4168.8  532.46  4256.6  530.03  4262.4  530.53  4315.0  528.28
  4453.1  525.00  4495.9  522.86  4511.5  522.90  4576.5  520.36  4643.8  518.74
  4723.5  518.41  4830.3  516.01  4855.8  515.60  4877.2  514.32  4935.6  513.50
  4957.0  514.08  4982.2  513.21  4982.5  512.71  4986.2  513.21  5026.7  514.41
  5077.1  513.68  5148.9  514.28  5166.6  513.76  5217.6  514.04  5228.4  514.95
  5248.6  515.09  5258.7  516.08  5329.3  518.04  5460.4  523.64  5490.7  524.33
#Mann=5,-1,0
  4052.3    0.05       0  4830.3    0.12       0  4982.2    0.07       0
  4986.2    0.12       0  5166.6    0.05       0
Bank Sta=4982.2,4986.2
Exp/Cntr=0.3,0.1

Type RM Length L Ch R = 1,6000,500,500,500
BEGIN DESCRIPTION:
Kings Creek Trib 8_1 11.0
END DESCRIPTION:
XS GIS Cut Line= 3
      2662275.97      6975210.97      2661625.76      6974564.78
      2660976.05      6974660.99
#Sta/Elev= 30
  4083.3  532.54  4132.8  531.93  4260.0  528.31  4295.4  528.07  4373.2  525.48
  4422.7  524.76  4486.3  522.34  4521.6  522.21  4677.2  518.66  4868.2  512.83
  4941.0  512.51  4981.3  512.18  4988.3  510.47  4993.4  510.12  4993.7  509.62
  4997.4  510.12  4999.1  511.79  5006.6  512.16  5011.6  511.22  5020.0  512.08
  5040.2  512.26  5164.3  512.51  5201.9  512.90  5232.3  512.25  5349.1  514.84
  5354.1  514.43  5488.1  518.43  5505.2  519.70  5576.0  522.29  5656.8  524.20
#Mann=5,-1,0
  4083.3    0.05       0  4941.0    0.12       0  4993.4    0.07       0
  4997.4    0.12       0  5164.3    0.05       0
Bank Sta=4993.4,4997.4
Exp/Cntr=0.3,0.1

Type RM Length L Ch R = 1,5500,500,500,500
BEGIN DESCRIPTION:
Kings Creek Trib 8_1 10.0
END DESCRIPTION:
XS GIS Cut Line= 3
      2663276.02      6974211.00      2661670.90      6974109.86
      2661025.98      6974361.01
#Sta/Elev= 30
  3391.7  536.15  3421.8  536.00  3469.0  534.20  3491.9  534.53  3762.5  529.64
  4129.8  517.89  4176.9  516.68  4283.5  515.24  4343.6  516.09  4383.7  518.21
  4574.1  518.95  4614.1  520.24  4741.3  516.51  4794.5  516.21  4906.0  510.12
  4942.2  510.51  5005.3  509.21  5011.8  505.14  5012.0  504.64  5015.8  505.14
  5026.7  509.02  5043.7  509.97  5103.4  510.16  5112.6  511.04  5198.4  512.22
  5253.8  511.86  5435.1  514.30  5552.6  517.85  5622.8  521.24  5692.1  523.23
#Mann=7,-1,0
  3391.7    0.05       0  4129.8    0.12       0  4176.9    0.05       0
  4942.2    0.12       0  5011.8    0.07       0  5015.8    0.12       0
  5253.8    0.05       0
Bank Sta=5011.8,5015.8
Exp/Cntr=0.3,0.1

Type RM Length L Ch R = 1,5000,500,500,500
BEGIN DESCRIPTION:
Kings Creek Trib 8_1 9.0
END DESCRIPTION:
XS GIS Cut Line= 3
      2662925.97      6974110.99      2661474.22      6973712.70
      2660880.62      6973657.03
#Sta/Elev= 30
  3494.6  534.65  3525.7  534.97  3556.8  532.02  3567.2  529.16  3608.6  527.49
  3665.2  526.93  3966.7  516.63  4120.1  515.01  4137.5  513.21  4147.9  514.61
  4159.7  519.51  4179.0  520.38  4189.0  520.06  4199.7  517.51  4233.8  513.57
  4251.5  512.79  4894.5  508.86  4935.9  507.22  4990.2  507.34  4994.5  505.39
  4994.7  504.89  4998.5  505.39  5028.3  507.34  5098.6  508.52  5128.8  511.07
  5138.8  510.55  5209.1  514.02  5349.7  517.39  5450.2  518.62  5596.2  516.13
#Mann=3,-1,0
  3494.6    0.05       0  4994.5    0.03       0  4998.5    0.05       0
Bank Sta=4994.5,4998.5
Exp/Cntr=0.3,0.1

Type RM Length L Ch R = 1,4500,500,500,500
BEGIN DESCRIPTION:
Kings Creek Trib 8_1 8.0
END DESCRIPTION:
XS GIS Cut Line= 3
      2662525.99      6973660.99      2661574.48      6973299.12
      2661071.28      6973254.22
#Sta/Elev= 30
  3982.0  524.73  4003.4  521.64  4057.3  519.10  4161.7  517.48  4197.1  518.31
  4276.8  516.31  4282.1  516.90  4377.8  514.11  4391.9  514.27  4416.7  512.65
  4495.5  510.38  4581.1  508.53  4646.9  508.13  4666.3  507.12  4751.3  507.73
  4848.6  506.75  4934.2  507.04  4987.7  504.16  5000.0  505.20  5016.6  500.67
  5016.8  500.17  5020.6  500.67  5028.6  503.80  5034.4  504.96  5068.7  505.52
  5088.8  507.89  5150.9  509.29  5159.1  510.12  5368.8  515.22  5505.2  515.61
#Mann=3,-1,0
  3982.0    0.05       0  5016.6    0.05       0  5020.6    0.05       0
Bank Sta=5016.6,5020.6
Exp/Cntr=0.3,0.1

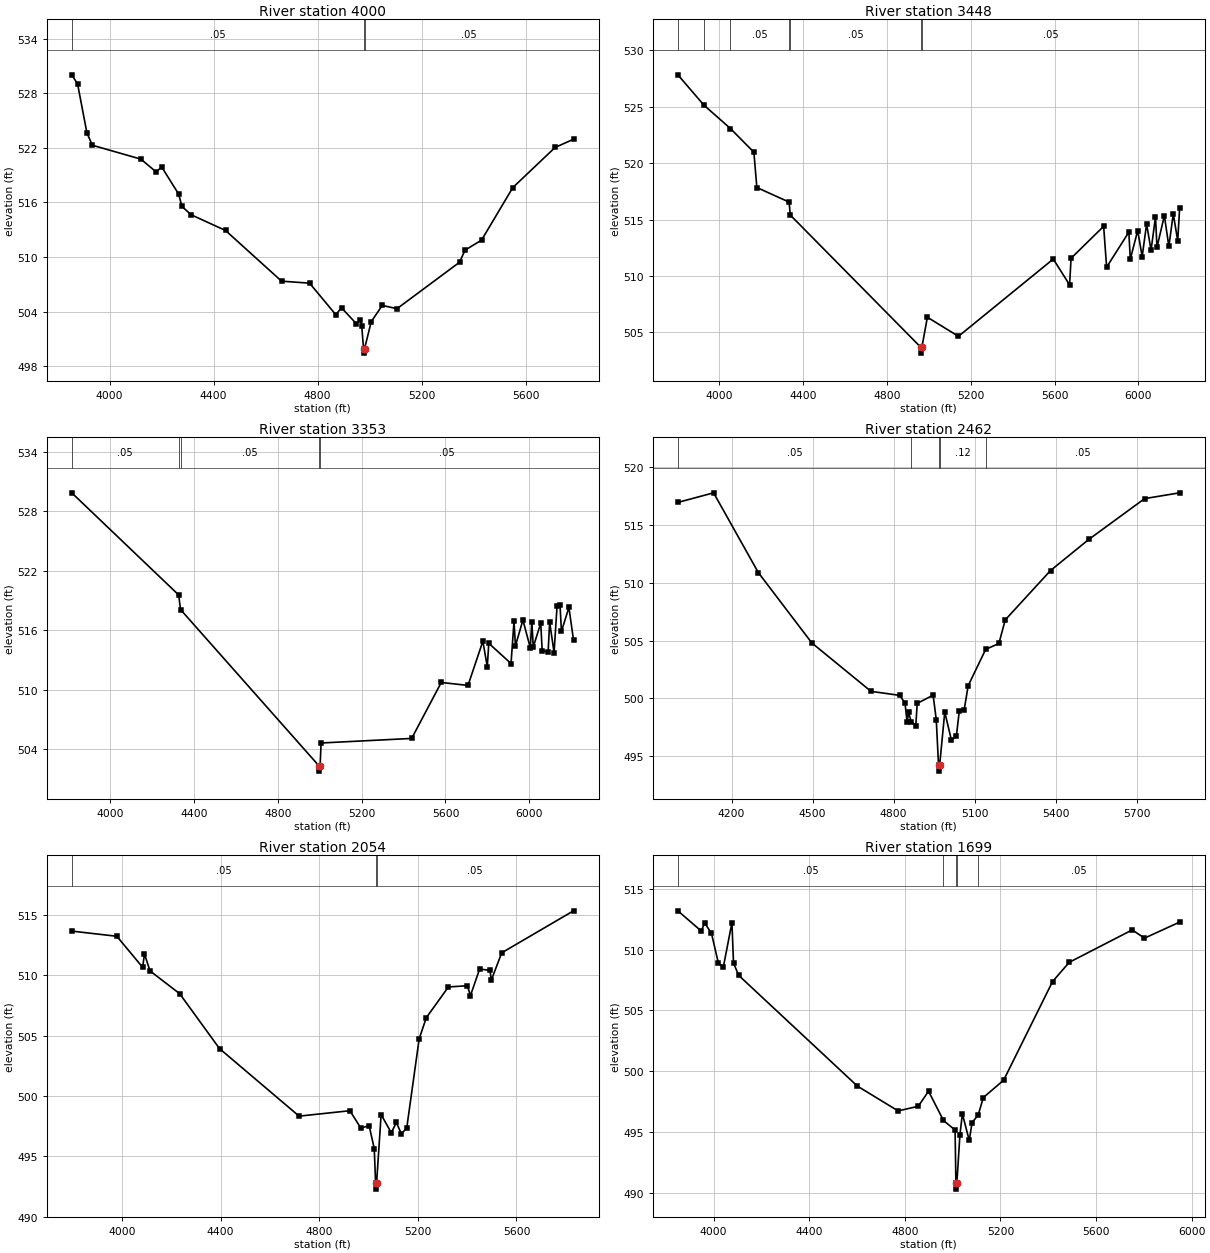
Type RM Length L Ch R = 1,4000,552,552,552
BEGIN DESCRIPTION:
Kings Creek Trib 8_1 7.0
END DESCRIPTION:
XS GIS Cut Line= 3
      2662726.00      6973511.00      2661778.58      6972867.68
      2661225.98      6972310.98
#Sta/Elev= 30
  3854.8  530.05  3877.2  529.05  3913.2  523.65  3934.1  522.30  4120.7  520.77
  4179.6  519.36  4200.6  519.91  4265.8  516.93  4278.5  515.56  4314.5  514.64
  4446.1  512.92  4661.7  507.34  4769.5  507.12  4870.2  503.65  4892.2  504.41
  4949.2  502.66  4964.1  503.12  4970.1  502.37  4976.9  499.92  4977.2  499.42
  4980.9  499.92  5006.6  502.89  5049.0  504.67  5105.6  504.31  5346.0  509.42
  5367.2  510.75  5430.8  511.86  5551.0  517.64  5713.7  522.06  5784.4  522.96
#Mann=3,-1,0
  3854.8    0.05       0  4976.9    0.03       0  4980.9    0.05       0
Bank Sta=4976.9,4980.9
Exp/Cntr=0.3,0.1

Type RM Length L Ch R = 1,3448,95,95,95
BEGIN DESCRIPTION:
Mapping XS 2f449fa6
END DESCRIPTION:
XS GIS Cut Line= 3
      2662855.99      6973323.68      2662060.83      6972455.61
      2661206.70      6971587.59
#Sta/Elev= 30
  3802.1  527.84  3926.1  525.16  4053.0  523.08  4165.0  520.98  4179.1  517.85
  4333.1  516.56  4338.7  515.41  4962.7  503.67  4963.0  503.17  4966.7  503.67
  4993.1  506.35  5141.5  504.66  5594.1  511.51  5672.0  509.22  5679.0  511.58
  5834.5  514.41  5848.7  510.79  5954.7  513.89  5961.8  511.50  5997.1  514.04
  6018.4  511.73  6039.6  514.62  6060.8  512.29  6082.0  515.24  6089.1  512.55
  6124.4  515.36  6145.7  512.63  6166.9  515.51  6188.1  513.13  6197.1  516.01
#Mann=7,-1,0
  3802.1    0.05       0  3926.1   0.075       0  4053.0    0.05       0
  4333.1   0.075       0  4338.7    0.05       0  4962.7    0.03       0
  4966.7    0.05       0
Bank Sta=4962.7,4966.7
Exp/Cntr=0.3,0.1

Type RM Length L Ch R = 1,3353,891,891,891
BEGIN DESCRIPTION:
Mapping XS 05fe5dca
END DESCRIPTION:
XS GIS Cut Line= 4
      2662964.58      6973193.45      2662218.04      6972485.11
      2662117.34      6972377.47      2661287.46      6971488.55
#Sta/Elev= 30
  3817.8  529.88  4327.8  519.57  4336.5  518.10  4998.0  502.29  4998.2  501.79
  5002.0  502.29  5006.8  504.63  5438.7  505.09  5579.8  510.74  5707.3  510.44
  5778.2  514.90  5799.2  512.33  5806.5  514.69  5912.5  512.65  5926.7  516.90
  5933.5  514.44  5969.2  517.04  6004.4  514.23  6011.7  516.89  6018.5  514.32
  6054.2  516.72  6061.0  513.95  6089.4  513.84  6096.7  516.83  6117.7  513.76
  6131.9  518.42  6146.0  518.60  6152.9  515.89  6188.5  518.31  6210.4  515.03
#Mann=5,-1,0
  3817.8    0.05       0  4327.8   0.075       0  4336.5    0.05       0
  4998.0    0.05       0  5002.0    0.05       0
Bank Sta=4998,5002
Exp/Cntr=0.3,0.1

Type RM Length L Ch R = 1,2462,408,408,408
BEGIN DESCRIPTION:
Kings Creek Trib 8_1 4.0
END DESCRIPTION:
XS GIS Cut Line= 3
      2663126.77      6971896.57      2662175.71      6971590.81
      2661387.21      6971250.75
#Sta/Elev= 30
  4001.0  516.95  4133.3  517.78  4299.0  510.88  4496.9  504.80  4716.1  500.61
  4823.0  500.26  4842.1  499.58  4849.9  497.93  4855.1  498.79  4865.0  497.98
  4882.0  497.65  4887.2  499.57  4946.1  500.28  4957.7  498.17  4966.2  494.21
  4966.4  493.71  4970.2  494.21  4989.2  498.82  5014.1  496.36  5032.2  496.75
  5043.2  498.95  5061.1  499.01  5075.9  501.10  5140.7  504.24  5189.6  504.75
  5213.1  506.79  5380.8  511.06  5522.5  513.75  5729.3  517.28  5858.7  517.78
#Mann=5,-1,0
  4001.0    0.05       0  4865.0    0.12       0  4966.2    0.07       0
  4970.2    0.12       0  5140.7    0.05       0
Bank Sta=4966.2,4970.2
Exp/Cntr=0.3,0.1

Type RM Length L Ch R = 1,2054,355,355,355
BEGIN DESCRIPTION:
Kings Creek Trib 8_1 3.0
END DESCRIPTION:
XS GIS Cut Line= 3
      2663349.04      6971775.06      2662275.93      6971230.88
      2661467.09      6971038.95
#Sta/Elev= 30
  3796.8  513.68  3979.6  513.25  4084.1  510.68  4091.7  511.78  4114.1  510.38
  4234.4  508.49  4395.9  503.94  4718.7  498.34  4924.7  498.79  4969.2  497.34
  5002.5  497.56  5023.4  495.65  5028.8  492.79  5029.0  492.29  5032.8  492.79
  5051.3  498.47  5092.4  496.96  5113.0  497.82  5133.5  496.86  5155.2  497.37
  5205.5  504.75  5234.4  506.50  5324.0  509.05  5400.8  509.15  5413.6  508.34
  5450.6  510.53  5492.8  510.43  5498.0  509.61  5540.2  511.88  5831.3  515.36
#Mann=3,-1,0
  3796.8    0.05       0  5028.8    0.05       0  5032.8    0.05       0
Bank Sta=5028.8,5032.8
Exp/Cntr=0.3,0.1

Type RM Length L Ch R = 1,1699,701,701,701
BEGIN DESCRIPTION:
Mapping XS ac81d77c
END DESCRIPTION:
XS GIS Cut Line= 3
      2663300.39      6971695.17      2662425.42      6970948.67
      2661491.42      6970782.01
#Sta/Elev= 30
  3850.8  513.20  3948.6  511.54  3962.8  512.20  3991.4  511.35  4019.9  508.93
  4040.8  508.54  4077.0  512.23  4083.6  508.90  4105.6  507.88  4601.9  498.77
  4772.1  496.73  4856.6  497.11  4899.4  498.35  4962.0  495.94  5010.5  495.15
  5013.9  490.79  5014.1  490.29  5017.9  490.79  5030.8  494.78  5041.0  496.49
  5069.7  494.30  5081.6  495.76  5107.2  496.40  5128.7  497.83  5213.7  499.26
  5418.3  507.38  5487.9  508.96  5751.6  511.63  5802.8  510.95  5949.7  512.27
#Mann=5,-1,0
  3850.8    0.05       0  4962.0    0.12       0  5013.9    0.07       0
  5017.9    0.12       0  5107.2    0.05       0
Bank Sta=5013.9,5017.9
Exp/Cntr=0.3,0.1

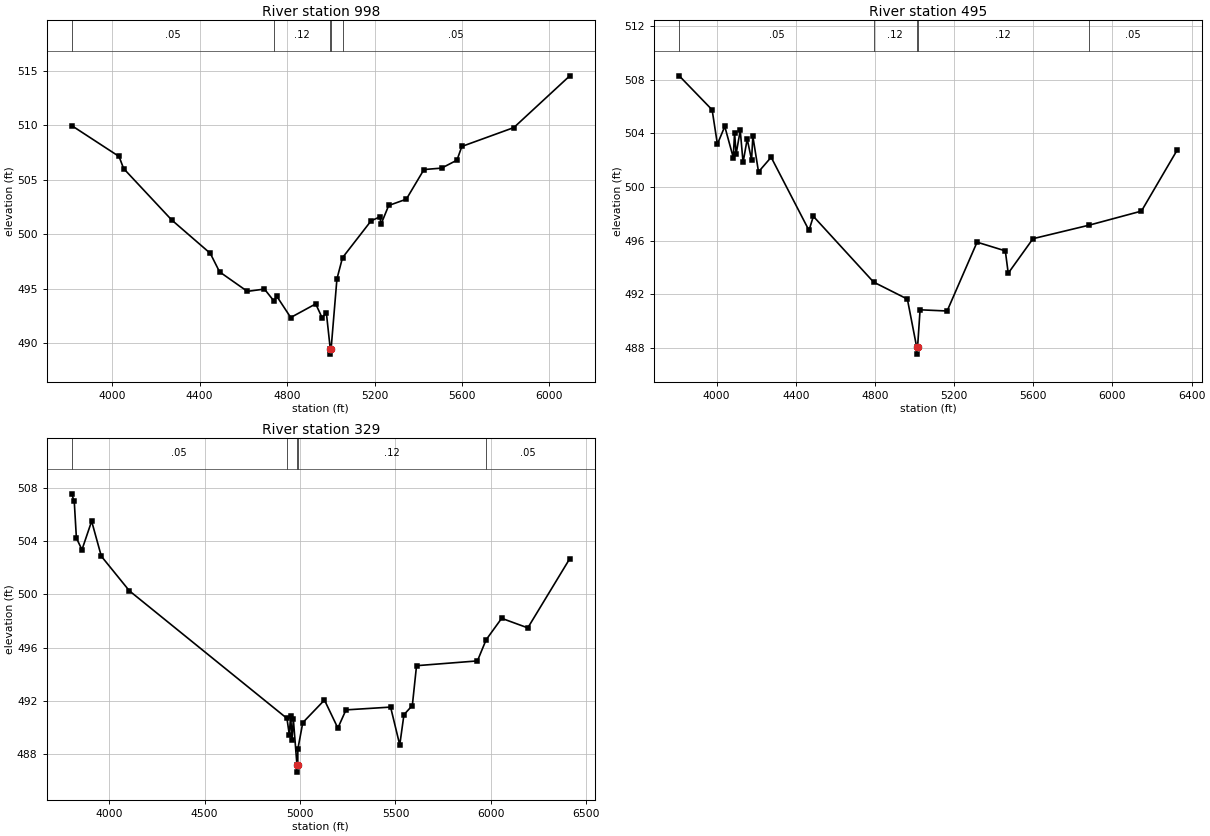
Type RM Length L Ch R = 1,998,503,503,503
BEGIN DESCRIPTION:
Mapping XS c36573d7
END DESCRIPTION:
XS GIS Cut Line= 4
      2663317.78      6971125.75      2662498.33      6970372.28
      2662421.94      6970379.22      2661368.32      6970656.49
#Sta/Elev= 30
  3814.0  509.98  4031.1  507.14  4052.1  506.03  4271.6  501.32  4448.5  498.25
  4491.1  496.55  4618.1  494.76  4696.4  494.97  4739.5  493.88  4753.1  494.30
  4816.6  492.36  4930.9  493.61  4959.7  492.36  4979.7  492.78  4997.4  489.50
  4997.6  489.00  5001.4  489.50  5028.0  495.90  5053.5  497.85  5184.2  501.23
  5224.5  501.60  5229.7  500.92  5264.8  502.64  5345.5  503.22  5426.2  505.94
  5506.8  506.07  5577.1  506.80  5599.5  508.06  5837.3  509.79  6093.4  514.54
#Mann=5,-1,0
  3814.0    0.05       0  4739.5    0.12       0  4997.4    0.07       0
  5001.4    0.12       0  5053.5    0.05       0
Bank Sta=4997.4,5001.4
Exp/Cntr=0.3,0.1

Type RM Length L Ch R = 1,495,166,166,166
BEGIN DESCRIPTION:
Mapping XS c95cd966
END DESCRIPTION:
XS GIS Cut Line= 5
      2663329.50      6970994.66      2663364.22      6970803.70
      2662734.88      6970055.00      2662437.57      6969636.17
      2661680.62      6969978.85
#Sta/Elev= 30
  3811.6  508.30  3977.9  505.76  4004.5  503.20  4041.8  504.52  4084.7  502.20
  4091.3  504.06  4099.0  502.46  4119.9  504.22  4134.2  501.83  4155.0  503.58
  4177.1  502.03  4183.6  503.78  4212.2  501.13  4276.0  502.22  4467.2  496.76
  4489.3  497.81  4793.4  492.90  4964.1  491.63  5011.5  488.02  5011.8  487.52
  5015.6  488.02  5028.3  490.83  5164.9  490.74  5316.2  495.88  5458.9  495.23
  5473.6  493.56  5598.7  496.14  5882.4  497.15  6146.5  498.20  6328.3  502.79
#Mann=5,-1,0
  3811.6    0.05       0  4793.4    0.12       0  5011.5    0.07       0
  5015.6    0.12       0  5882.4    0.05       0
Bank Sta=5011.5,5015.6
Exp/Cntr=0.3,0.1

Type RM Length L Ch R = 1,329,0,0,0
BEGIN DESCRIPTION:
Mapping XS 0da65efd
END DESCRIPTION:
XS GIS Cut Line= 5
      2663407.62      6970894.83      2663455.36      6970595.37
      2662847.72      6969953.01      2662496.16      6969568.89
      2661675.87      6969944.32
#Sta/Elev= 30
  3803.1  507.58  3817.1  507.02  3828.4  504.24  3857.6  503.37  3908.2  505.52
  3958.9  502.88  4106.0  500.27  4931.5  490.66  4943.7  489.44  4950.9  490.86
  4957.8  489.06  4965.1  490.58  4984.1  487.11  4984.4  486.61  4988.2  487.11
  4988.5  488.34  5014.5  490.34  5128.0  492.04  5198.2  489.93  5240.8  491.30
  5474.5  491.51  5522.5  488.66  5544.5  490.94  5588.4  491.63  5610.4  494.63
  5929.4  494.99  5974.9  496.58  6056.4  498.20  6193.3  497.48  6413.4  502.70
#Mann=5,-1,0
  3803.1    0.05       0  4931.5    0.12       0  4984.1    0.07       0
  4988.2    0.12       0  5974.9    0.05       0
Bank Sta=4984.1,4988.2
Exp/Cntr=0.3,0.1

Chan Stop Cuts=-1