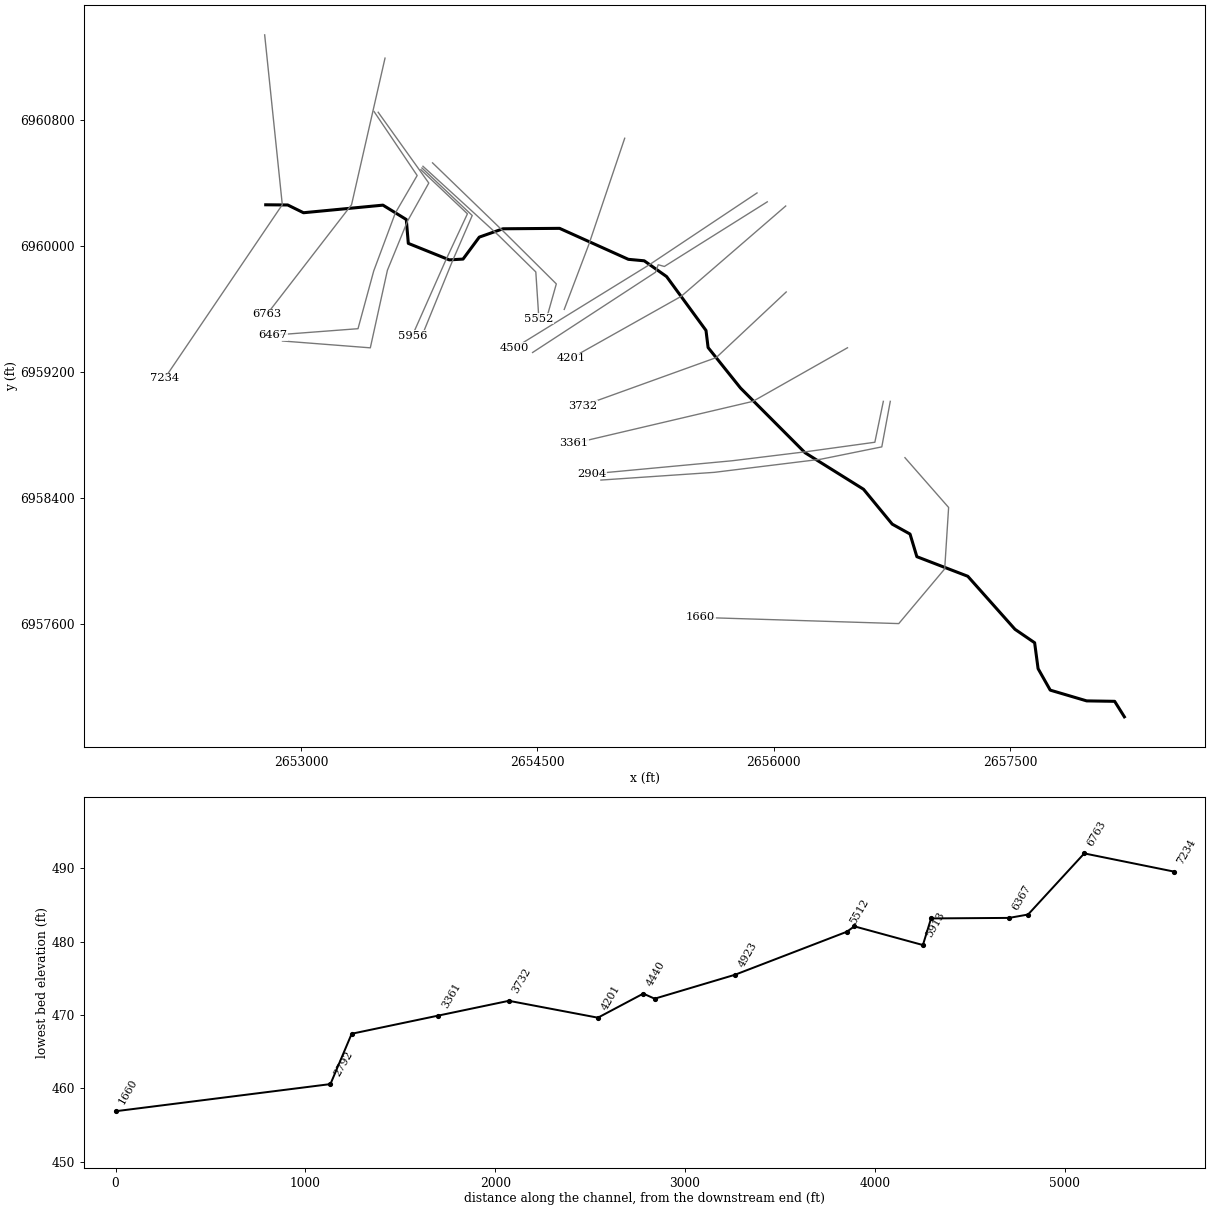
--- Kings Creek Trib 9.prj (project) ---

Proj Title=Kings Creek Trib 9 Base Level Engineering
Current Plan=p01
Default Exp/Contr=0.3,0.1
English Units
Geom File=g01
Flow File=f01
Plan File=p01
Y Axis Title=Elevation
X Axis Title(PF)=Main Channel Distance
X Axis Title(XS)=Station
BEGIN DESCRIPTION:
Kings Creek Trib 9
END DESCRIPTION:
DSS Export Rating Curves= 0
DSS Export Rating Curve Sorted= 0
DSS Export Volume Flow Curves= 0
DXF OffsetX= 0
DXF OffsetY= 0
DXF ScaleX= 1
DXF ScaleY= 10

--- Kings Creek Trib 9.p01 (plan) ---

Plan Title=Multiple Run
Short Identifier=Multiple
Geom File=g01
Flow File=f01
Subcritical Flow
K Sum by GR= 0
Std Step Tol= 0.01
Critical Tol= 0.01
Num of Std Step Trials= 20
Max Error Tol= 0.3
Flow Tol Ratio= 0.001
Split Flow NTrial= 30
Split Flow Tol= 0.02
Split Flow Ratio= 0.02
Log Output Level= 0
Friction Slope Method= 1
Unsteady Friction Slope Method= 2
Unsteady Bridges Friction Slope Method= 1
Parabolic Critical Depth
Global Vel Dist=  1 , 1 , 1
Global Log Level= 0
CheckData=True
Encroach Param= -1, 0, 0, 0
BEGIN DESCRIPTION:
Multiple Run
END DESCRIPTION:

--- Kings Creek Trib 9.f01 (steady flow) ---

Flow Title=Multiple
Number of Profiles=7
Profile Names=10-year,25-year,50-year,1pct_min,100-year,1pct_plu,500-year
River Rch & RM= Kings Creek Trib,Reach-1,7234
     557     744     896     535    1068    2130    1516
River Rch & RM= Kings Creek Trib,Reach-1,3361
     693     937    1136     683    1363    2720    1961
Boundary for River Rch & Prof#=Kings Creek Trib,Reach-1,1
Up Type=0
Dn Type=3
Dn Slope=0.005
Boundary for River Rch & Prof#=Kings Creek Trib,Reach-1,2
Up Type=0
Dn Type=3
Dn Slope=0.005
Boundary for River Rch & Prof#=Kings Creek Trib,Reach-1,3
Up Type=0
Dn Type=3
Dn Slope=0.005
Boundary for River Rch & Prof#=Kings Creek Trib,Reach-1,4
Up Type=0
Dn Type=3
Dn Slope=0.005
Boundary for River Rch & Prof#=Kings Creek Trib,Reach-1,5
Up Type=0
Dn Type=3
Dn Slope=0.005
Boundary for River Rch & Prof#=Kings Creek Trib,Reach-1,6
Up Type=0
Dn Type=3
Dn Slope=0.005
Boundary for River Rch & Prof#=Kings Creek Trib,Reach-1,7
Up Type=0
Dn Type=3
Dn Slope=0.005

--- Kings Creek Trib 9.g01 (geometry) ---

Geom Title=Existing Conditions
Program Version=4.10

River Reach=Kings Creek Trib,Reach-1
Reach XY= 30
        2652776.        6960261.      2652915.52      6960259.83
      2653015.81      6960210.55      2653520.07      6960258.76
       2653668.3      6960167.47      2653681.04      6960016.08
      2653941.27      6959911.36      2654028.44      6959916.39
      2654131.47      6960055.74      2654281.93      6960108.74
      2654641.18      6960111.44      2655077.59      6959914.83
      2655178.42      6959905.46      2655320.38      6959805.38
      2655570.48      6959463.43      2655583.86      6959354.83
      2655789.63      6959097.79      2656199.18       6958687.3
      2656570.39      6958455.41      2656752.54      6958234.02
      2656865.61       6958171.1      2656908.87      6958027.45
      2657232.17      6957903.14      2657531.62      6957566.62
      2657656.41       6957481.2      2657678.25      6957316.93
      2657755.45      6957180.44      2657986.51      6957112.22
      2658164.29      6957109.46        2658226.        6957011.

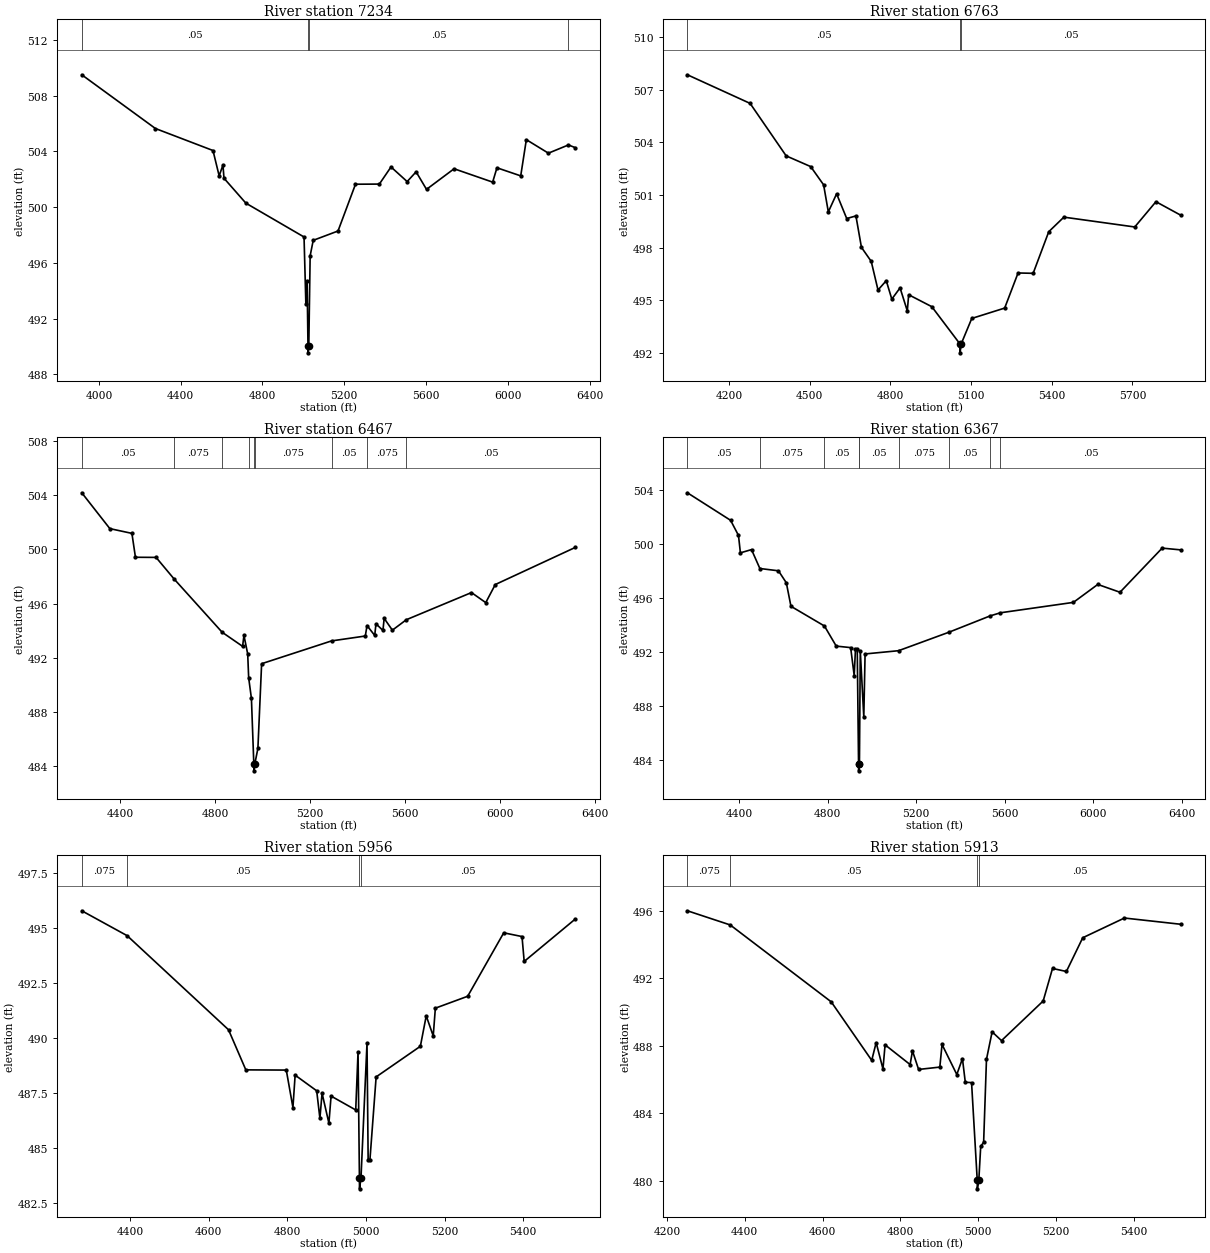
Type RM Length L Ch R = 1 ,7234    ,471,471,471
BEGIN DESCRIPTION:
Kings Creek Trib 9 14.0
END DESCRIPTION:
XS GIS Cut Line= 3
      2652769.36      6961339.43      2652881.22      6960261.52
      2652135.66      6959160.62
#Sta/Elev= 30
  3916.3  509.51  4276.7  505.65  4558.2  504.07  4588.3  502.25  4606.9  503.03
  4611.9  502.08    4719  500.29  5003.5  497.86  5012.4  493.07  5018.5   494.7
  5022.8  490.04    5023  489.54  5026.8  490.04  5033.4  496.51  5048.4  497.62
  5169.7  498.29  5255.2  501.65  5371.9  501.66  5428.9  502.89  5507.9  501.84
  5551.7  502.54  5602.6  501.28  5737.5  502.76  5926.1   501.8  5947.1  502.83
  6063.4  502.25  6090.9  504.85  6198.8  503.88  6296.8  504.47  6329.6  504.28
#Mann= 4 ,-1 , 0
  3916.3     .05       0  5022.8     .05       0  5026.8     .05       0
  6296.8    .075       0
Bank Sta=5022.8,5026.8
XS Rating Curve= 0 ,0
Exp/Cntr=0.3,0.1

Type RM Length L Ch R = 1 ,6763    ,296,296,296
BEGIN DESCRIPTION:
Kings Creek Trib 9 13.0
END DESCRIPTION:
XS GIS Cut Line= 3
      2653533.25       6961191.9      2653320.82      6960261.44
      2652783.03      6959565.14
#Sta/Elev= 30
  4045.6  507.85  4278.8  506.22  4412.9  503.23    4504  502.62  4552.1  501.58
  4569.6  500.04  4600.4  501.07    4638  499.66  4672.2  499.81  4692.7  498.02
  4729.1  497.22  4754.3  495.59    4785  496.12  4805.6  495.07  4836.3  495.71
  4863.2   494.4  4868.3  495.32  4954.3  494.64  5059.3  492.51  5059.5  492.01
  5063.3  492.51  5102.9  493.97  5225.2  494.56    5275  496.56  5331.1  496.54
  5389.1  498.91  5445.3  499.74  5708.8  499.18  5787.6  500.62  5879.8  499.85
#Mann= 3 ,-1 , 0
  4045.6     .05       0  5059.3     .03       0  5063.3     .05       0
Bank Sta=5059.3,5063.3
XS Rating Curve= 0 ,0
Exp/Cntr=0.3,0.1

Type RM Length L Ch R = 1 ,6467    ,100,100,100
BEGIN DESCRIPTION:
Mapping XS e716ffeb
END DESCRIPTION:
XS GIS Cut Line= 6
       2653463.8      6960852.62      2653737.24      6960446.81
      2653598.35      6960208.09      2653461.63      6959841.34
       2653361.8      6959474.58      2652820.18      6959433.42
#Sta/Elev= 30
  4238.1  504.16  4356.5  501.52  4449.5  501.17  4464.4  499.41  4551.4   499.4
  4627.9   497.8  4829.8  493.89  4916.1  492.85  4921.9  493.65  4937.7  492.29
  4941.8  490.53  4953.4  489.01  4963.5  484.18  4963.8  483.68  4967.5  484.18
  4980.7  485.33  4996.4  491.57  5291.4  493.25  5433.6  493.61  5440.8  494.38
  5473.3  493.65  5478.5  494.51  5507.9  494.02  5513.1  494.91  5547.7  494.04
  5606.6  494.81  5881.2  496.81  5941.4  496.07  5981.5   497.4  6318.3  500.13
#Mann= 9 ,-1 , 0
  4238.1     .05       0  4627.9    .075       0  4829.8     .05       0
  4941.8    .075       0  4963.5    .085       0  4967.5    .075       0
  5291.4     .05       0  5440.8    .075       0  5606.6     .05       0
Bank Sta=4963.5,4967.5
XS Rating Curve= 0 ,0
Exp/Cntr=0.3,0.1

Type RM Length L Ch R = 1 ,6367    ,411,411,411
BEGIN DESCRIPTION:
Mapping XS 9852ac46
END DESCRIPTION:
XS GIS Cut Line= 6
      2653489.83       6960848.3      2653811.02      6960399.06
      2653676.47      6960158.18      2653548.43      6959845.68
      2653439.93      6959353.06      2652882.22      6959396.46
#Sta/Elev= 30
  4166.5  503.82  4361.8  501.78  4397.5  500.66  4406.1  499.37  4456.4  499.61
  4494.1  498.21  4578.1  498.04  4613.7  497.15  4634.6  495.41  4785.9  493.95
  4839.3  492.46  4904.4  492.35  4920.4  490.28  4926.1  492.21  4934.2  492.22
  4940.1  483.72  4940.4  483.22  4944.1  483.72  4947.9   492.1  4963.8   487.2
  4969.6  491.88  5120.8  492.12  5348.6  493.49    5535   494.7  5581.3  494.93
    5911   495.7  6021.3  497.03  6121.6  496.45  6312.2  499.72  6396.2  499.59
#Mann= 9 ,-1 , 0
  4166.5     .05       0  4494.1    .075       0  4785.9     .05       0
  4940.1     .06       0  4944.1     .05       0  5120.8    .075       0
  5348.6     .05       0    5535    .075       0  5581.3     .05       0
Bank Sta=4940.1,4944.1
XS Rating Curve= 0 ,0
Exp/Cntr=0.3,0.1

Type RM Length L Ch R = 1 ,5956    ,43,43,43
BEGIN DESCRIPTION:
Mapping XS 9d72c239
END DESCRIPTION:
XS GIS Cut Line= 4
      2653761.14      6960483.67      2654056.25      6960203.75
      2653919.53      6959910.78      2653706.85      6959431.16
#Sta/Elev= 30
  4277.2  495.77  4392.6  494.64  4650.4  490.37  4694.4  488.55  4797.3  488.54
  4814.2  486.84  4819.8  488.31  4874.6   487.6  4882.8  486.35  4888.3  487.49
  4905.7  486.13  4911.2  487.36  4973.9  486.73  4979.8  489.37  4983.3  483.65
  4983.5  483.15  4987.3  483.65  5002.6  489.77  5005.5  484.44  5009.9  484.44
  5025.8  488.23  5138.3  489.62  5153.2     491    5171  490.09  5176.4  491.35
  5258.6  491.89  5350.3  494.77  5396.8   494.6  5402.3  493.47  5531.9  495.39
#Mann= 4 ,-1 , 0
  4277.2    .075       0  4392.6     .05       0  4983.3     .03       0
  4987.3     .05       0
Bank Sta=4983.3,4987.3
XS Rating Curve= 0 ,0
Exp/Cntr=0.3,0.1

Type RM Length L Ch R = 1 ,5913    ,361,361,361
BEGIN DESCRIPTION:
Mapping XS d042a9bd
END DESCRIPTION:
XS GIS Cut Line= 4
      2653767.59      6960494.58      2654086.63       6960192.9
      2653958.59      6959897.76       2653767.6      6959428.97
#Sta/Elev= 30
  4252.8  496.01  4362.8  495.17  4622.2  490.61  4726.2  487.14  4737.6  488.19
  4755.1  486.63  4760.5  488.06  4824.8  486.89  4830.9   487.7  4846.6   486.6
  4901.1  486.74  4906.8  488.08  4944.7   486.3  4959.2  487.24  4966.5  485.84
  4982.6  485.82  4997.2  480.02  4997.4  479.52  5001.2  480.02  5006.1  482.04
  5013.6  482.28  5020.9   487.2  5035.4  488.83  5059.5  488.31  5166.5  490.66
  5190.5  492.59  5226.1  492.41  5268.1  494.41  5375.1  495.58  5519.8  495.21
#Mann= 4 ,-1 , 0
  4252.8    .075       0  4362.8     .05       0  4997.2     .03       0
  5001.2     .05       0
Bank Sta=4997.2,5001.2
XS Rating Curve= 0 ,0
Exp/Cntr=0.3,0.1

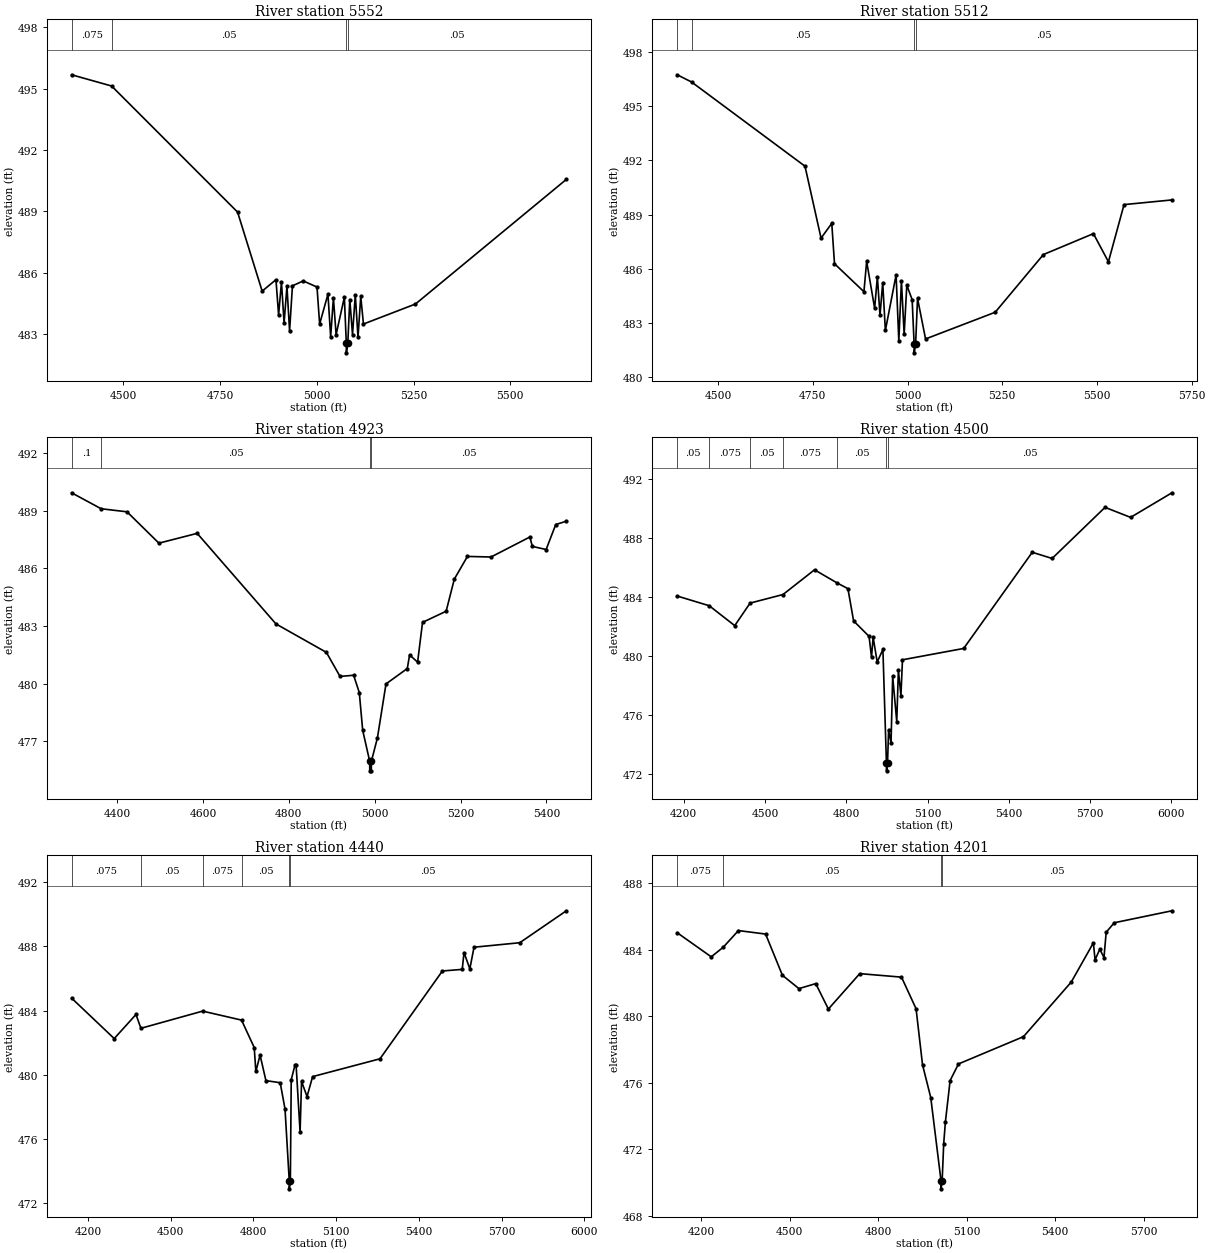
Type RM Length L Ch R = 1 ,5552    ,40,40,40
BEGIN DESCRIPTION:
Mapping XS c07bb868
END DESCRIPTION:
XS GIS Cut Line= 4
       2653774.1      6960505.42      2654258.07      6960062.69
      2654490.27      6959834.83      2654509.81      6959537.52
#Sta/Elev= 30
  4365.9  495.68  4469.4  495.13    4795  488.96  4858.6  485.09  4894.3  485.65
  4901.1  483.92  4908.5  485.53  4915.3  483.53  4922.7  485.33  4929.5  483.14
  4936.9  485.35  4964.8  485.59  5000.4  485.29  5007.2  483.48  5028.7  484.94
  5035.7  482.85  5042.8  484.76  5049.8  482.96  5071.1  484.79  5076.1  482.57
  5076.3  482.07  5080.1  482.57  5085.2  484.68  5092.2  482.96  5099.4  484.91
  5106.4  482.83  5113.5  484.83  5120.5  483.48    5255  484.46  5645.1  490.56
#Mann= 4 ,-1 , 0
  4365.9    .075       0  4469.4     .05       0  5076.1     .05       0
  5080.1     .05       0
Bank Sta=5076.1,5080.1
XS Rating Curve= 0 ,0
Exp/Cntr=0.3,0.1

Type RM Length L Ch R = 1 ,5512    ,589,589,589
BEGIN DESCRIPTION:
Mapping XS 34429c4c
END DESCRIPTION:
XS GIS Cut Line= 4
      2653834.92      6960527.08      2654297.13      6960080.05
      2654620.48      6959758.87      2654564.07      6959559.26
#Sta/Elev= 30
  4391.8  496.75  4429.7  496.35  4729.2  491.68  4771.6  487.69  4799.9  488.51
  4807.1  486.27  4884.8  484.72    4892   486.4  4913.1   483.8  4920.3  485.55
  4927.2  483.41  4934.4  485.22  4941.4  482.57  4969.7  485.65  4976.9     482
  4983.8  485.31    4991  482.36    4998  485.08  5012.1  484.28  5017.3  481.83
  5017.6  481.33  5021.3  481.83  5026.3  484.35  5047.5   482.1  5231.3  483.58
  5358.6  486.78  5490.6  487.94  5530.3  486.38  5571.5  489.55    5698  489.81
#Mann= 4 ,-1 , 0
  4391.8    .075       0  4429.7     .05       0  5017.3    .065       0
  5021.3     .05       0
Bank Sta=5017.3,5021.3
XS Rating Curve= 0 ,0
Exp/Cntr=0.3,0.1

Type RM Length L Ch R = 1 ,4923    ,423,423,423
BEGIN DESCRIPTION:
Mapping XS fe5d1f72
END DESCRIPTION:
XS GIS Cut Line= 3
      2655054.51      6960683.36      2654826.65      6960008.44
      2654670.71      6959596.94
#Sta/Elev= 30
    4294  489.93  4362.8   489.1  4423.1  488.94  4497.4  487.31  4586.5  487.82
    4770  483.11  4887.5  481.63  4919.2  480.38  4950.9  480.44  4964.1  479.54
    4972  477.58  4988.3  475.97  4988.5  475.47    4992  475.47  4992.3  475.97
  5006.3  477.18  5026.3  479.99  5075.9  480.79  5081.3   481.5  5099.9  481.12
  5111.4  483.19  5166.4  483.77  5185.4  485.44    5216  486.62  5270.9  486.59
  5361.4  487.63  5367.2  487.14  5399.3  486.98  5421.7  488.28  5446.4  488.45
#Mann= 4 ,-1 , 0
    4294      .1       0  4362.8     .05       0  4988.3     .03       0
  4992.3     .05       0
Bank Sta=4988.3,4992.3
XS Rating Curve= 0 ,0
Exp/Cntr=0.3,0.1

Type RM Length L Ch R = 1 ,4500    ,60,60,60
BEGIN DESCRIPTION:
Mapping XS 0c067e4a
END DESCRIPTION:
XS GIS Cut Line= 3
      2655894.34      6960336.12      2655210.76       6959880.4
      2654355.76      6959353.08
#Sta/Elev= 30
  4175.8  484.08  4294.1  483.42  4388.2  482.07  4444.9   483.6  4566.2  484.18
  4682.7  485.86  4766.8  484.96  4805.9  484.58  4826.9  482.39    4884  481.34
    4893  479.93    4899  481.28    4914   479.6  4935.1  480.45  4948.1  472.71
  4948.4  472.21  4952.1  472.71  4956.1  475.01  4965.1   474.1  4971.1  478.62
  4986.2  475.55  4992.2  479.05  5001.6  477.31  5007.3  479.75  5233.2  480.52
  5486.3  487.05  5559.6  486.63  5754.9   490.1  5849.3  489.42  6001.9  491.09
#Mann= 7 ,-1 , 0
  4175.8     .05       0  4294.1    .075       0  4444.9     .05       0
  4566.2    .075       0  4766.8     .05       0  4948.1     .03       0
  4952.1     .05       0
Bank Sta=4948.1,4952.1
XS Rating Curve= 0 ,0
Exp/Cntr=0.3,0.1

Type RM Length L Ch R = 1 ,4440    ,239,239,239
BEGIN DESCRIPTION:
Mapping XS d795bc4d
END DESCRIPTION:
XS GIS Cut Line= 5
      2655959.47      6960279.71      2655306.25      6959869.55
      2655267.18       6959880.4      2655249.82      6959832.66
      2654469.78      6959323.46
#Sta/Elev= 30
  4140.7  484.78  4295.3  482.26  4374.2  483.76  4392.1   482.9  4615.9  483.97
    4757  483.41    4803   481.7  4808.9  480.21  4824.2  481.23  4845.4  479.64
  4897.2  479.51  4914.7  477.87    4930   473.4  4930.2   472.9    4934   473.4
  4937.2   479.7  4950.6   480.6  4954.9   480.6  4969.3  476.44  4974.6  479.59
  4994.5  478.65  5014.7  479.89    5259     481  5485.4  486.47  5557.3  486.57
  5563.8  487.62  5584.9   486.6    5600  487.95  5765.9  488.23  5934.9  490.22
#Mann= 6 ,-1 , 0
  4140.7    .075       0  4392.1     .05       0  4615.9    .075       0
    4757     .05       0    4930     .07       0    4934     .05       0
Bank Sta=4930,4934
XS Rating Curve= 0 ,0
Exp/Cntr=0.3,0.1

Type RM Length L Ch R = 1 ,4201    ,469,469,469
BEGIN DESCRIPTION:
Mapping XS 3efb6424
END DESCRIPTION:
XS GIS Cut Line= 3
      2656076.42      6960253.27      2655413.02      6959679.88
      2654715.11      6959287.52
#Sta/Elev= 30
  4118.8  485.02  4234.3  483.57    4275  484.15  4326.5  485.15  4418.6  484.94
  4475.6  482.46  4531.6  481.66  4588.6  481.96  4631.4  480.43  4737.8  482.56
  4879.3  482.35  4928.7  480.45  4950.6  477.08  4978.5  475.11  5013.2  470.12
  5013.4  469.62  5017.2  470.12  5022.4  472.34  5028.2  473.65  5044.1  476.13
  5072.5  477.13  5292.8  478.77  5454.7  482.05  5529.9  484.41  5535.6  483.39
  5551.6  484.03  5565.8  483.53  5573.3  485.05  5600.7  485.62  5796.3  486.34
#Mann= 4 ,-1 , 0
  4118.8    .075       0    4275     .05       0  5013.2    .085       0
  5017.2     .05       0
Bank Sta=5013.2,5017.2
XS Rating Curve= 0 ,0
Exp/Cntr=0.3,0.1

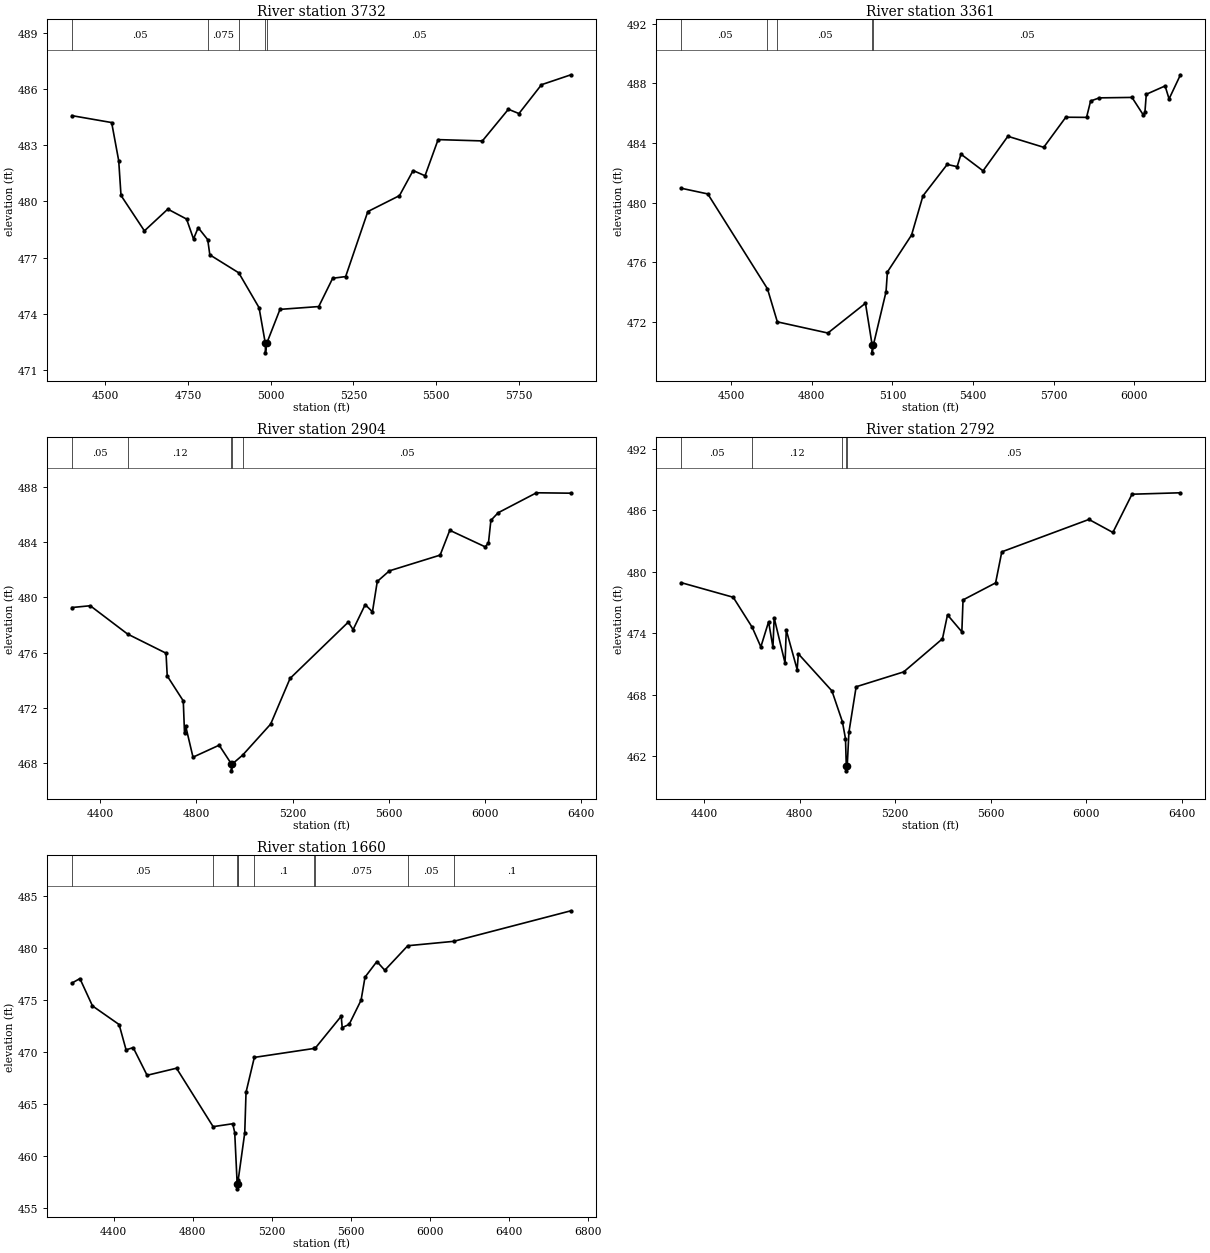
Type RM Length L Ch R = 1 ,3732    ,371,371,371
BEGIN DESCRIPTION:
Mapping XS c820f8b6
END DESCRIPTION:
XS GIS Cut Line= 3
      2656079.67      6959707.65      2655635.24      6959290.99
      2654788.05      6958985.45
#Sta/Elev= 30
  4398.3  484.58  4518.8  484.21  4540.2  482.17  4547.1  480.32  4617.9  478.43
  4688.7  479.59  4745.4  479.06  4766.4     478  4780.6   478.6  4809.4  477.96
  4815.8  477.15  4903.3  476.19  4964.7  474.33  4983.7  472.42    4984  471.92
  4987.7  472.42    5028  474.24  5145.2  474.39  5187.4   475.9  5226.6  475.99
  5293.7  479.46  5389.4  480.31  5430.7  481.65  5466.7  481.37  5506.3   483.3
  5640.2  483.23  5718.9  484.92  5750.8  484.69    5819  486.23  5908.1  486.76
#Mann= 5 ,-1 , 0
  4398.3     .05       0  4809.4    .075       0  4903.3     .05       0
  4983.7    .075       0  4987.7     .05       0
Bank Sta=4983.7,4987.7
XS Rating Curve= 0 ,0
Exp/Cntr=0.3,0.1

Type RM Length L Ch R = 1 ,3361    ,457,457,457
BEGIN DESCRIPTION:
Mapping XS 8191954d
END DESCRIPTION:
XS GIS Cut Line= 3
      2656468.58       6959353.5      2655867.88      6959013.21
       2654730.3      6958746.16
#Sta/Elev= 30
  4313.9  480.96  4412.4  480.58  4634.7  474.21  4671.5  471.99  4859.7  471.24
  4999.7  473.24  5024.8  470.41    5025  469.91  5028.8  470.41  5076.3  474.01
  5081.4  475.34  5171.4  477.82  5213.8  480.45  5304.1  482.56  5341.1  482.41
  5355.5  483.25  5437.6  482.13  5530.1  484.45  5663.6  483.71  5745.8  485.73
  5823.1  485.72  5838.2  486.82  5870.7  487.03  5992.3  487.06  6033.4  485.91
  6040.4  486.05  6045.5  487.27  6115.6  487.83  6130.4  486.96  6172.8  488.58
#Mann= 5 ,-1 , 0
  4313.9     .05       0  4634.7      .1       0  4671.5     .05       0
  5024.8     .07       0  5028.8     .05       0
Bank Sta=5024.8,5028.8
XS Rating Curve= 0 ,0
Exp/Cntr=0.3,0.1

Type RM Length L Ch R = 1 ,2904    ,112,112,112
BEGIN DESCRIPTION:
Mapping XS 5dd5a8a7
END DESCRIPTION:
XS GIS Cut Line= 5
      2656696.08       6959013.4      2656642.21      6958753.81
      2656216.09      6958695.04       2655736.1      6958636.26
      2654844.73        6958553.
#Sta/Elev= 30
  4282.6  479.27  4359.2   479.4  4514.2  477.35  4674.1  475.96  4679.1  474.31
  4745.8   472.5    4751  470.14  4756.1  470.65  4786.2  468.42  4894.9  469.29
  4945.7  467.93  4945.9  467.43  4949.7  467.93  4992.5  468.57  5108.9  470.82
  5189.5  474.13  5431.3  478.21  5451.5  477.67  5501.7  479.48  5531.9  478.96
  5551.9  481.16  5602.2  481.93  5813.1  483.07  5853.2  484.87  6000.4  483.67
  6013.9  483.95    6024  485.59  6054.1  486.14  6213.4  487.59  6356.7  487.56
#Mann= 5 ,-1 , 0
  4282.6     .05       0  4514.2     .12       0  4945.7     .03       0
  4949.7     .12       0  4992.5     .05       0
Bank Sta=4945.7,4949.7
XS Rating Curve= 0 ,0
Exp/Cntr=0.3,0.1

Type RM Length L Ch R = 1 ,2792    ,1132,1132,1132
BEGIN DESCRIPTION:
Mapping XS de74e41d
END DESCRIPTION:
XS GIS Cut Line= 5
      2656740.17      6959013.43      2656686.29      6958724.42
      2656299.35      6958646.06      2655623.45      6958562.79
       2654903.5      6958513.82
#Sta/Elev= 30
  4303.6  478.92    4521   477.5  4600.8  474.56  4636.8  472.66  4669.3  475.11
  4687.5  472.62  4692.6  475.49  4738.2  471.08  4743.3   474.3  4788.9  470.45
    4794  471.98  4934.6  468.37  4978.5  465.36  4991.5   463.7  4994.8  461.07
  4995.1  460.57  4998.8  461.07  5005.8  464.33  5036.1  468.77  5235.4  470.22
  5397.8  473.45  5418.9  475.78    5479  474.13    5484  477.24  5620.4   478.9
  5646.4  481.93  6011.6  485.09  6111.8  483.82    6192  487.55    6395  487.69
#Mann= 5 ,-1 , 0
  4303.6     .05       0  4600.8     .12       0  4978.5     .05       0
  4994.8     .04       0  4998.8     .05       0
Bank Sta=4994.8,4998.8
XS Rating Curve= 0 ,0
Exp/Cntr=0.3,0.1

Type RM Length L Ch R = 1 ,1660    ,0,0,0
BEGIN DESCRIPTION:
Kings Creek Trib 9 5.0
END DESCRIPTION:
XS GIS Cut Line= 5
      2656833.24      6958655.83       2657110.4      6958339.92
      2657085.53      6957949.86      2656794.04      6957602.81
      2655535.27      6957641.99
#Sta/Elev= 30
  4188.9  476.65  4229.8  477.09  4293.4  474.46  4428.1  472.67  4463.2  470.24
  4499.3  470.45  4569.5  467.79  4718.3  468.47  4903.4  462.85  5002.5  463.13
  5012.6  462.28  5024.9  457.37  5025.1  456.87  5028.9  457.37    5030  457.69
  5063.3  462.26  5069.8  466.16  5111.7  469.51  5413.3  470.37  5419.8   470.4
    5551  473.47  5556.1  472.37  5591.3  472.69  5651.4  475.01  5671.4  477.23
  5731.4  478.73  5771.4  477.89  5887.6  480.25  6119.3  480.67  6712.6  483.61
#Mann= 10 ,-1 , 0
  4188.9     .05       0  4903.4     .12       0  5024.9     .07       0
  5028.9     .12       0    5030     .05       0  5111.7      .1       0
  5413.3     .05       0  5419.8    .075       0  5887.6     .05       0
  6119.3      .1       0
Bank Sta=5024.9,5028.9
XS Rating Curve= 0 ,0
Exp/Cntr=0.3,0.1

Chan Stop Cuts=-1
Use User Specified Reach Order=0
Composite Channel Slope=5