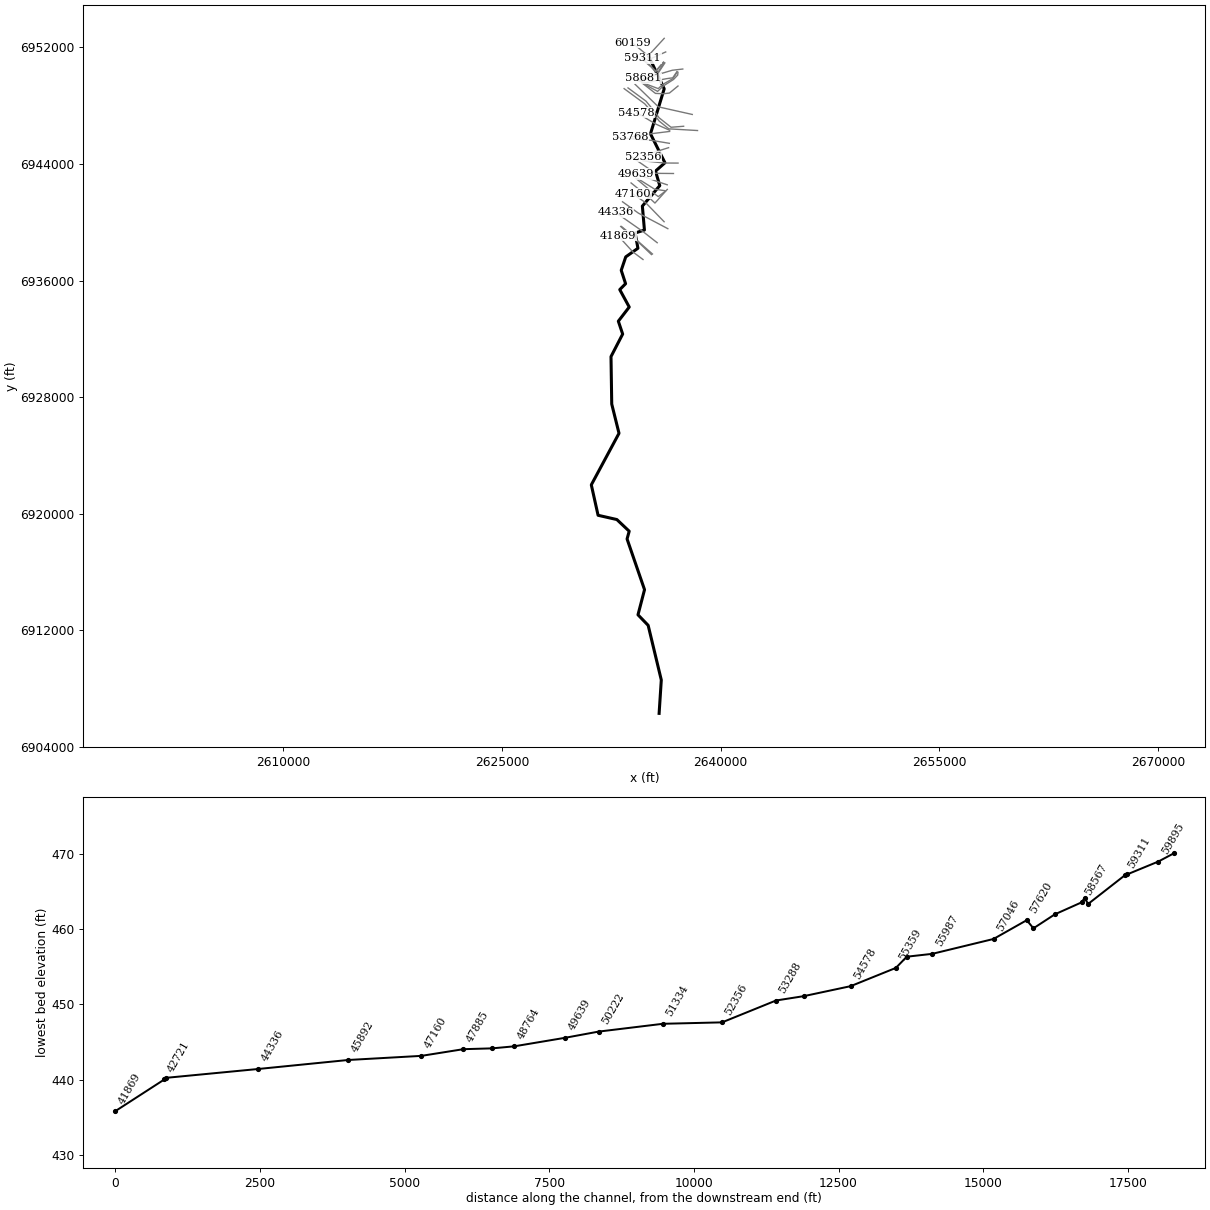
--- Little Brushy Creek.prj (project) ---

Proj Title=Little Brushy Creek Base Level Engineering
Current Plan=p01
Default Exp/Contr=0.3,0.1
English Units
Geom File=g01
Flow File=f01
Plan File=p01
Y Axis Title=Elevation
X Axis Title(PF)=Main Channel Distance
X Axis Title(XS)=Station
BEGIN DESCRIPTION:
Little Brushy Creek
END DESCRIPTION:
DSS Export Rating Curves= 0
DSS Export Rating Curve Sorted= 0
DSS Export Volume Flow Curves= 0
DXF OffsetX= 0
DXF OffsetY= 0
DXF ScaleX= 1
DXF ScaleY= 10

--- Little Brushy Creek.p01 (plan) ---

Plan Title=Multiple Run
Short Identifier=Multiple
Geom File=g01
Flow File=f01
Subcritical Flow
K Sum by GR= 0
Std Step Tol= 0.01
Critical Tol= 0.01
Num of Std Step Trials= 20
Max Error Tol= 0.3
Flow Tol Ratio= 0.001
Split Flow NTrial= 30
Split Flow Tol= 0.02
Split Flow Ratio= 0.02
Log Output Level= 0
Friction Slope Method= 1
Unsteady Friction Slope Method= 2
Unsteady Bridges Friction Slope Method= 1
Parabolic Critical Depth
Global Vel Dist=  1 , 1 , 1
Global Log Level= 0
CheckData=True
Encroach Param= -1, 0, 0, 0
BEGIN DESCRIPTION:
Multiple Run
END DESCRIPTION:

--- Little Brushy Creek.f01 (steady flow) ---

Flow Title=Multiple
Program Version=4.10
Number of Profiles= 7
Profile Names=10-year,25-year,50-year,1pct_min,100-year,1pct_plu,500-year
River Rch & RM=Little Brushy Cr,Reach-1         ,60159
     468     610     721     423     844    1683    1153
River Rch & RM=Little Brushy Cr,Reach-1         ,58567
    1038    1408    1709    1025    2045    4080    2930
River Rch & RM=Little Brushy Cr,Reach-1         ,47885
    1255    1717    2095    1262    2518    5023    3641
River Rch & RM=Little Brushy Cr,Reach-1         ,45892
    1430    1965    2405    1452    2897    5780    4210
River Rch & RM=Little Brushy Cr,Reach-1         ,37789
    1503    2070    2536    1533    3058    6101    4453
River Rch & RM=Little Brushy Cr,Reach-1         ,35547
    1863    2589    3191    1940    3871    7723    5703
River Rch & RM=Little Brushy Cr,Reach-1         ,33667
    1989    2768    3415    2078    4146    8271    6115
River Rch & RM=Little Brushy Cr,Reach-1         ,27874
    2018    2810    3469    2111    4211    8402    6215
River Rch & RM=Little Brushy Cr,Reach-1         ,26348
    2210    3089    3823    2332    4653    9283    6900
River Rch & RM=Little Brushy Cr,Reach-1         ,25516
    2323    3251    4028    2459    4907    9790    7290
River Rch & RM=Little Brushy Cr,Reach-1         ,24269
    2346    3283    4067    2482    4953    9883    7355
River Rch & RM=Little Brushy Cr,Reach-1         ,20833
    2260    3165    3922    2394    4777    9532    7101
River Rch & RM=Little Brushy Cr,Reach-1         ,19617
    2731    3859    4811    2954    5894   11760    8860
River Rch & RM=Little Brushy Cr,Reach-1         ,15060
    2868    4059    5065    3113    6212   12394    9357
River Rch & RM=Little Brushy Cr,Reach-1         ,14516
    2893    4095    5111    3142    6269   12507    9444
River Rch & RM=Little Brushy Cr,Reach-1         ,12298
    3024    4290    5361    3300    6584   13137    9945
River Rch & RM=Little Brushy Cr,Reach-1         ,9030
    3151    4475    5598    3448    6880   13727   10407
River Rch & RM=Little Brushy Cr,Reach-1         ,6374
    3177    4512    5643    3476    6935   13837   10489
River Rch & RM=Little Brushy Cr,Reach-1         ,5438
    3306    4702    5888    3630    7243   14452   10976
River Rch & RM=Little Brushy Cr,Reach-1         ,4378
    3289    4674    5850    3605    7193   14352   10890
River Rch & RM=Little Brushy Cr,Reach-1         ,2370
    3404    4843    6065    3740    7462   14888   11308
Boundary for River Rch & Prof#=Little Brushy Cr,Reach-1         , 1
Up Type= 0
Dn Type= 3
Dn Slope=0.005
Boundary for River Rch & Prof#=Little Brushy Cr,Reach-1         , 2
Up Type= 0
Dn Type= 3
Dn Slope=0.005
Boundary for River Rch & Prof#=Little Brushy Cr,Reach-1         , 3
Up Type= 0
Dn Type= 3
Dn Slope=0.005
Boundary for River Rch & Prof#=Little Brushy Cr,Reach-1         , 4
Up Type= 0
Dn Type= 3
Dn Slope=0.005
Boundary for River Rch & Prof#=Little Brushy Cr,Reach-1         , 5
Up Type= 0
Dn Type= 3
Dn Slope=0.005
Boundary for River Rch & Prof#=Little Brushy Cr,Reach-1         , 6
Up Type= 0
Dn Type= 3
Dn Slope=0.005
Boundary for River Rch & Prof#=Little Brushy Cr,Reach-1         , 7
Up Type= 0
Dn Type= 3
Dn Slope=0.005
DSS Import GetInterval= 0
DSS Import GetPeak= 0
DSS Import FillOption= 0

--- Little Brushy Creek.g01 (geometry) ---

Geom Title=Existing Conditions
Program Version=4.10

River Reach=Little Brushy Cr,Reach-1
Reach XY= 30
        2635026.        6951461.      2636124.79      6949150.49
      2635183.53      6946060.99      2636176.11      6944076.36
      2635527.97      6943505.35      2635821.05      6942508.43
      2634627.58      6941104.95      2634768.72      6939460.95
      2634129.45      6939259.75      2634322.56      6938212.22
      2633486.74       6937620.7      2633177.07      6936700.47
      2633476.42      6935781.45      2633076.41      6935376.65
      2633726.41      6934181.07      2632979.11      6933209.35
      2633275.75      6932327.02      2632475.57      6930781.18
      2632526.37      6927526.16      2633025.04       6925521.4
      2631125.37      6921985.68      2631589.61      6919897.75
      2632878.32      6919605.21      2633724.42      6918804.95
      2633577.85      6918273.02      2634775.63      6914795.73
      2634326.68      6913071.75      2635024.36      6912349.17
      2635925.23      6908600.31        2635776.        6906311.

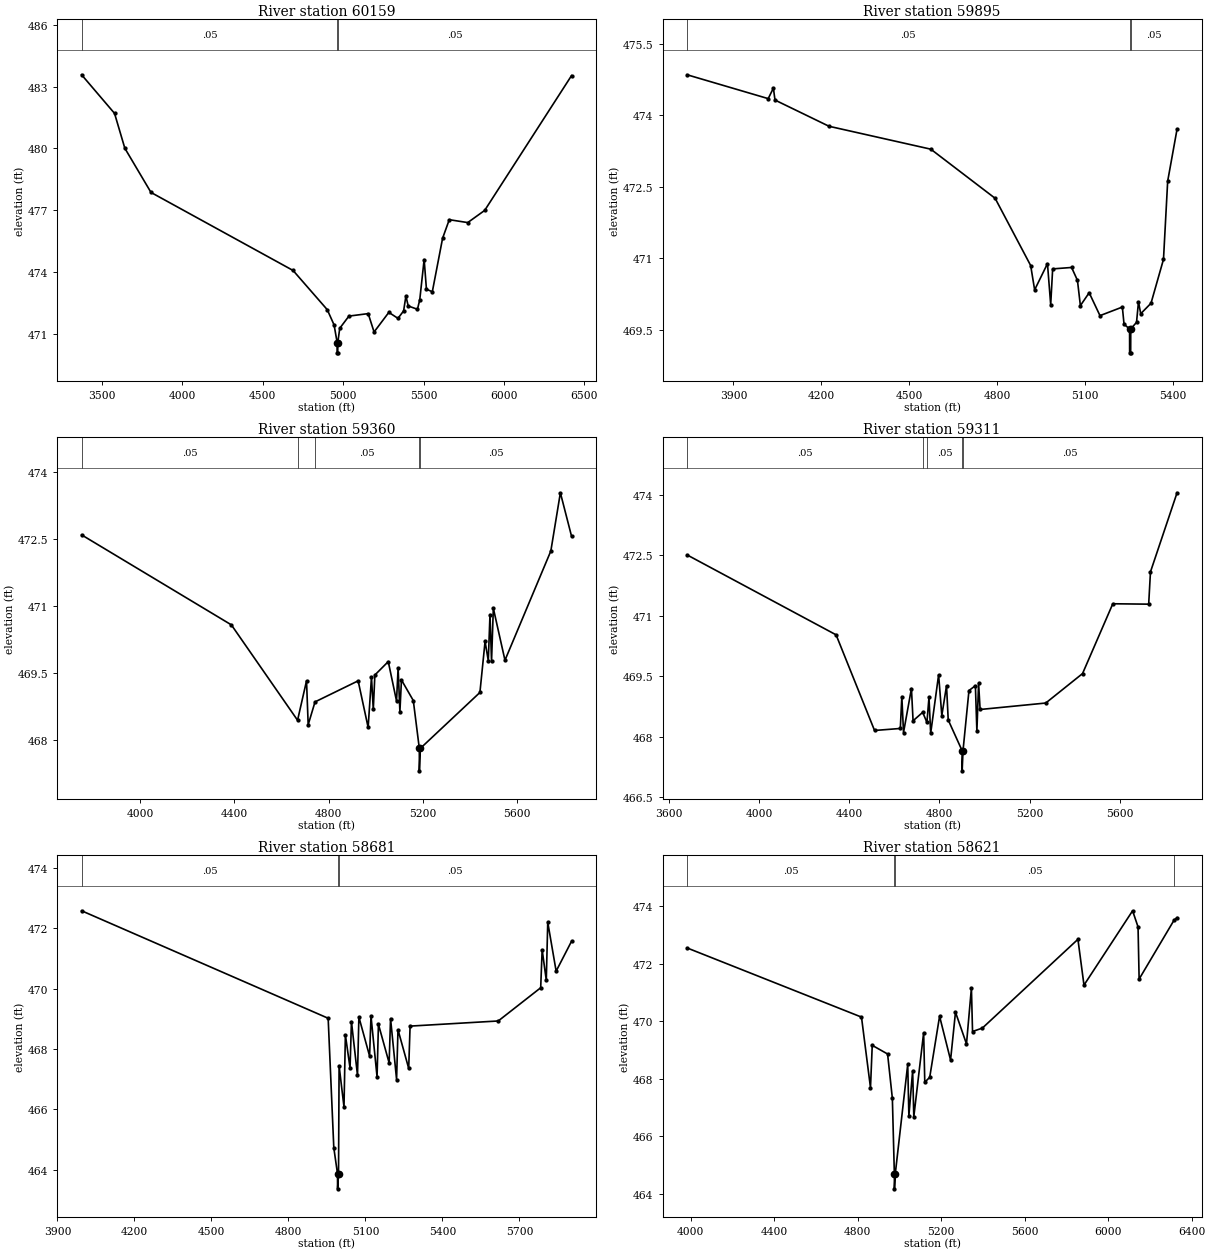
Type RM Length L Ch R = 1 ,60159   ,264,264,264
BEGIN DESCRIPTION:
Little Brushy Creek 91.0
END DESCRIPTION:
XS GIS Cut Line= 3
      2636125.98      6952610.98        2635026.        6951411.
      2633926.01      6952310.99
#Sta/Elev= 30
  3372.1  483.57  3577.1   481.7  3641.2  480.01    3804  477.87  4688.2  474.09
    4901  472.19  4943.5  471.45  4962.5   470.6  4962.7   470.1  4966.2   470.1
  4966.5   470.6  4978.7  471.29  5035.8  471.88  5155.7     472  5192.3  471.11
  5284.2  472.06  5340.9  471.77  5376.1  472.13  5390.4  472.85  5404.8  472.37
  5462.2  472.21  5476.6  472.67  5503.9  474.62  5518.2  473.18  5554.8  473.06
  5618.7  475.65  5660.3  476.55  5775.2  476.41  5880.7     477  6421.2  483.53
#Mann= 3 ,-1 , 0
  3372.1     .05       0  4962.5     .03       0  4966.5     .05       0
Bank Sta=4962.5,4966.5
XS Rating Curve= 0 ,0
Exp/Cntr=0.3,0.1

Type RM Length L Ch R = 1 ,59895   ,535,535,535
BEGIN DESCRIPTION:
Mapping XS ac16fcc6
END DESCRIPTION:
XS GIS Cut Line= 4
      2636227.89      6951677.31      2635082.08        6951163.
      2634858.55      6951167.34      2634730.85      6951311.23
#Sta/Elev= 30
  3741.8  474.85  4018.5  474.35  4036.2  474.57  4041.7  474.32  4226.2  473.77
  4573.4  473.29  4792.9  472.26  4914.2  470.85  4927.7  470.34  4971.5  470.89
  4982.5  470.03  4989.2  470.78  5053.8  470.81  5073.8  470.54  5083.8  470.01
  5113.8  470.28  5150.7   469.8    5227  469.98  5232.8  469.62  5251.7  469.52
  5251.9  469.02  5255.4  469.02  5255.7  469.52  5275.4  469.66  5282.1  470.09
  5289.7  469.84  5324.8  470.06  5367.4  470.98  5381.7  472.62  5413.7  473.71
#Mann= 3 ,-1 , 0
  3741.8     .05       0  5251.7     .03       0  5255.7     .05       0
Bank Sta=5251.7,5255.7
XS Rating Curve= 0 ,0
Exp/Cntr=0.3,0.1

Type RM Length L Ch R = 1 ,59360   ,49,49,49
BEGIN DESCRIPTION:
Mapping XS de65385b
END DESCRIPTION:
XS GIS Cut Line= 5
      2636065.18      6950969.88      2635542.15       6950370.9
      2635233.99      6950689.91        2634724.      6951134.78
      2634698.26      6951297.86
#Sta/Elev= 30
  3750.7  472.59  4386.7  470.58  4667.8  468.45  4705.9  469.33  4712.9  468.35
    4742  468.86  4925.1  469.33  4967.5  468.29  4981.7  469.41  4989.4  468.69
  4996.1  469.46    5053  469.76  5088.1  468.88  5094.8  469.62  5102.4  468.64
    5109  469.35  5159.3  468.89  5184.9  467.82  5185.1  467.32  5188.9  467.82
  5442.2  469.07  5464.1  470.21  5477.8  469.78    5485  470.81  5491.6  469.77
  5499.2  470.95  5548.6  469.79  5743.4  472.23  5783.9  473.53  5831.3  472.56
#Mann= 5 ,-1 , 0
  3750.7     .05       0  4667.8    .075       0    4742     .05       0
  5184.9     .03       0  5188.9     .05       0
Bank Sta=5184.9,5188.9
XS Rating Curve= 0 ,0
Exp/Cntr=0.3,0.1

Type RM Length L Ch R = 1 ,59311   ,630,630,630
BEGIN DESCRIPTION:
Mapping XS ecae6762
END DESCRIPTION:
XS GIS Cut Line= 5
      2636080.33      6950967.67      2635529.13      6950305.79
      2635225.31      6950648.67      2634701.96      6951097.85
      2634650.62      6951252.93
#Sta/Elev= 30
  3681.6  472.51  4342.2  470.53  4512.7  468.16    4627  468.21  4633.7     469
  4641.2  468.11  4676.3   469.2  4683.5   468.4  4726.2  468.61    4745  468.36
  4754.1  468.98  4761.6  468.09  4796.8  469.54    4811  468.53  4831.9  469.27
  4839.4  468.42    4901  467.66  4901.2  467.16    4905  467.66  4931.4  469.15
  4959.9  469.27  4966.5  468.14  4974.1  469.33  4980.8  468.68  5271.8  468.84
    5435  469.57  5569.2   471.3  5728.3  471.29  5736.2  472.09  5854.1  474.05
#Mann= 5 ,-1 , 0
  3681.6     .05       0  4726.2    .075       0    4745     .05       0
    4901     .03       0    4905     .05       0
Bank Sta=4901,4905
XS Rating Curve= 0 ,0
Exp/Cntr=0.3,0.1

Type RM Length L Ch R = 1 ,58681   ,60,60,60
BEGIN DESCRIPTION:
Little Brushy Creek 88.0
END DESCRIPTION:
XS GIS Cut Line= 6
      2636113.33       6950953.8      2635674.53      6950242.86
      2635523.56      6950163.53       2634887.1      6949890.95
      2634771.75      6949828.36      2634704.45      6949870.48
#Sta/Elev= 30
    3994  472.58  4954.7  469.02  4976.7  464.73  4991.1  463.87  4991.4  463.37
  4995.1  463.87  4997.3  467.45  5016.4  466.08  5021.8  468.47    5040  467.37
  5045.4  468.91    5069  467.13  5074.4  469.06  5116.1  467.77  5121.6  469.09
  5145.2  467.08  5150.6  468.82  5192.3  467.54  5197.8  469.01  5221.3  466.99
  5226.8  468.64  5268.5  467.36  5273.9  468.76  5617.4  468.93  5782.8  470.03
  5788.5  471.29  5804.6  470.28  5810.3   472.2    5843  470.58    5903  471.57
#Mann= 3 ,-1 , 0
    3994     .05       0  4991.1     .05       0  4995.1     .05       0
Bank Sta=4991.1,4995.1
XS Rating Curve= 0 ,0
Exp/Cntr=0.3,0.1

Type RM Length L Ch R = 1 ,58621   ,54,54,54
BEGIN DESCRIPTION:
Mapping XS dd1ae3fa
END DESCRIPTION:
XS GIS Cut Line= 6
      2636171.48      6950924.27      2635683.21       6950188.6
      2635566.59      6950121.91      2634741.37      6949769.77
      2634548.22      6949732.87       2634320.7      6949795.71
#Sta/Elev= 30
  3982.7  472.54  4818.1  470.14  4861.2  467.69  4869.6  469.16  4943.1  468.86
    4966  467.32  4975.6  464.68  4975.9  464.18  4979.6  464.68  5039.6   468.5
  5045.1  466.71  5063.2  468.28  5068.7  466.68  5115.9   469.6  5121.3  467.88
  5144.9  468.05  5192.2  470.17  5244.8  468.65  5268.4  470.31  5321.1  469.21
  5344.7  471.15  5350.1  469.64  5397.4  469.76    5855  472.84    5884  471.25
  6116.9  473.83    6143  473.27  6148.2  471.46    6316  473.51  6329.9  473.59
#Mann= 4 ,-1 , 0
  3982.7     .05       0  4975.6     .05       0  4979.6     .05       0
    6316    .075       0
Bank Sta=4975.6,4979.6
XS Rating Curve= 0 ,0
Exp/Cntr=0.3,0.1

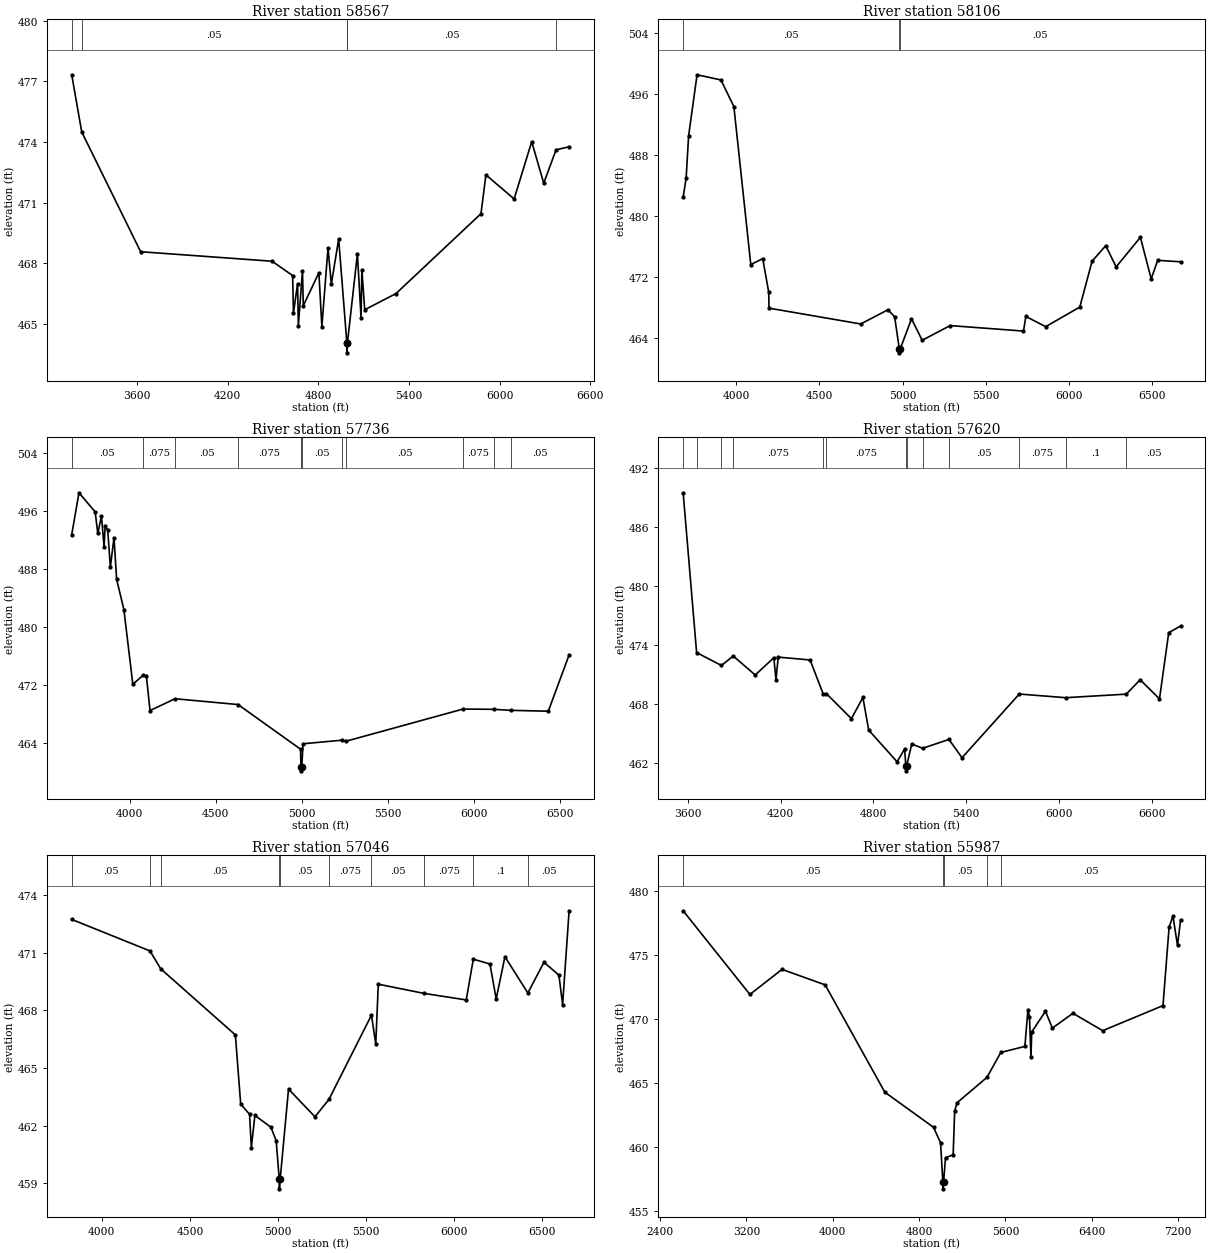
Type RM Length L Ch R = 1 ,58567   ,461,461,461
BEGIN DESCRIPTION:
Mapping XS a70076b0
END DESCRIPTION:
XS GIS Cut Line= 6
      2637399.25        6950505.      2636678.79      6950422.53
       2635617.5      6950107.45      2634897.81      6949814.97
      2634518.03      6949685.41      2634254.25      6949786.06
#Sta/Elev= 30
  3167.7  477.33    3234   474.5  3623.9  468.58  4494.4  468.11  4630.2   467.4
  4635.5  465.54  4662.9     467  4668.1  464.93  4695.5  467.63  4700.8  465.91
    4804  467.54  4823.8  464.88  4864.3  468.76  4886.5  466.98  4935.1  469.21
  4989.1  464.08  4989.4  463.58  4993.1  464.08  5059.1  468.47  5083.2  465.32
  5088.6  467.67  5107.4  465.71  5314.4  466.51  5877.1  470.46  5909.9  472.38
  6096.6  471.19    6213  474.02  6292.6  471.97  6374.3  473.62  6460.7  473.77
#Mann= 5 ,-1 , 0
  3167.7    .075       0    3234     .05       0  4989.1     .05       0
  4993.1     .05       0  6374.3    .075       0
Bank Sta=4989.1,4993.1
XS Rating Curve= 0 ,0
Exp/Cntr=0.3,0.1

Type RM Length L Ch R = 1 ,58106   ,370,370,370
BEGIN DESCRIPTION:
Little Brushy Creek 87.0
END DESCRIPTION:
XS GIS Cut Line= 6
      2637001.09      6950330.79      2636708.67      6949903.53
      2636302.42      6949847.05      2635436.02      6949680.89
      2634860.94      6949550.68      2634294.42      6949716.41
#Sta/Elev= 30
  3681.2  482.44  3699.1  484.93    3714  490.49  3764.8  498.51  3908.3  497.83
  3986.1  494.34  4087.7  473.59  4159.5  474.36  4195.4  469.98  4197.4  467.86
  4748.5  465.78  4912.6  467.65  4952.4  466.73  4980.9  462.49  4981.5  461.99
  4985.9  462.49  5053.9  466.45  5118.3  463.64  5286.1  465.57  5727.2  464.85
  5741.3  466.77  5860.5  465.43  6065.6     468  6139.5  474.02  6221.6  476.07
  6284.1  473.28    6430  477.16  6494.8  471.71  6534.2  474.14  6671.3  473.95
#Mann= 3 ,-1 , 0
  3681.2     .05       0  4980.9     .03       0  4985.9     .05       0
Bank Sta=4980.9,4985.9
XS Rating Curve= 0 ,0
Exp/Cntr=0.3,0.1

Type RM Length L Ch R = 1 ,57736   ,116,116,116
BEGIN DESCRIPTION:
Mapping XS d74767b9
END DESCRIPTION:
XS GIS Cut Line= 5
      2637012.61      6950293.17      2636730.51       6949850.5
      2636025.55      6949450.81      2635713.88      6949162.21
       2634660.6      6949559.55
#Sta/Elev= 30
  3664.7  492.77  3706.8  498.55  3800.8  495.91    3816  492.93  3837.2  495.34
  3852.4  491.09  3858.4  493.92  3873.6   493.4  3888.8  488.28    3910  492.35
  3925.2   486.6  3967.5  482.39  4019.2  472.09  4078.2  473.32  4097.9  473.23
    4119  468.46  4264.1  470.09  4629.7  469.29  4992.3  463.12  4994.3  460.63
    4995  460.13  4999.5  460.63  5006.6  463.87  5231.2  464.36  5258.8  464.24
  5935.4  468.67  6112.8  468.63  6211.2  468.49  6429.8  468.37  6550.5  476.15
#Mann= 12 ,-1 , 0
  3664.7     .05       0  4078.2    .075       0  4264.1     .05       0
  4629.7    .075       0  4992.3     .05       0  4994.3     .03       0
  4999.5     .05       0  5231.2      .1       0  5258.8     .05       0
  5935.4    .075       0  6112.8      .1       0  6211.2     .05       0
Bank Sta=4994.3,4999.5
XS Rating Curve= 0 ,0
Exp/Cntr=0.3,0.1

Type RM Length L Ch R = 1 ,57620   ,574,574,574
BEGIN DESCRIPTION:
Mapping XS 87e7e8c5
END DESCRIPTION:
XS GIS Cut Line= 6
      2637069.06      6950284.54       2637051.7      6950093.55
      2636765.24      6949789.73      2636074.77      6949350.49
      2635670.47      6948972.98      2634586.39      6949564.05
#Sta/Elev= 30
  3569.2  489.45  3656.3  473.22  3816.8  471.91  3893.6  472.87  4035.7  470.94
  4155.9   472.7    4170  470.46  4184.2  472.76  4390.6  472.47  4475.6  469.01
  4495.8  469.06    4658  466.51  4732.3  468.66  4769.9  465.35  4953.5  462.13
  5002.6  463.44  5010.1  461.71  5010.8  461.21  5015.3  461.71  5048.4  463.93
  5119.3   463.5  5289.2   464.4  5373.7  462.54  5744.3  469.01  6044.1  468.64
  6436.9     469  6526.4  470.46  6651.7  468.52  6711.4  475.24  6787.9  475.92
#Mann= 13 ,-1 , 0
  3569.2     .05       0  3656.3    .075       0  3816.8     .05       0
  3893.6    .075       0  4475.6     .05       0  4495.8    .075       0
  5010.1     .07       0  5015.3    .075       0  5119.3      .1       0
  5289.2     .05       0  5744.3    .075       0  6044.1      .1       0
  6436.9     .05       0
Bank Sta=5010.1,5015.3
XS Rating Curve= 0 ,0
Exp/Cntr=0.3,0.1

Type RM Length L Ch R = 1 ,57046   ,1059,1059,1059
BEGIN DESCRIPTION:
Little Brushy Creek 86.0
END DESCRIPTION:
XS GIS Cut Line= 5
      2637071.49      6949341.01      2636485.58      6948859.26
      2636076.01      6948808.82      2635523.92      6948834.87
      2634655.86      6949511.96
#Sta/Elev= 30
  3828.8  472.73  4273.1  471.09  4334.2  470.16  4758.2  466.72  4788.4  463.12
  4838.8  462.59  4848.9  460.86    4869  462.53  4959.7  461.92  4989.9  461.22
  5007.4  459.21  5008.1  458.71  5012.7  459.21  5060.1   463.9  5210.2  462.46
  5289.4  463.36  5531.1  467.75  5555.5  466.26  5569.9  469.36  5829.9  468.88
  6069.3  468.54  6109.5  470.66  6204.1  470.41  6239.3  468.59  6289.1  470.79
  6419.2   468.9  6510.7   470.5  6595.7  469.83  6616.6   468.3  6653.6  473.18
#Mann= 10 ,-1 , 0
  3828.8     .05       0  4273.1    .075       0  4334.2     .05       0
  5007.4     .03       0  5012.7     .05       0  5289.4    .075       0
  5531.1     .05       0  5829.9    .075       0  6109.5      .1       0
  6419.2     .05       0
Bank Sta=5007.4,5012.7
XS Rating Curve= 0 ,0
Exp/Cntr=0.3,0.1

Type RM Length L Ch R = 1 ,55987   ,440,440,440
BEGIN DESCRIPTION:
Little Brushy Creek 84.0
END DESCRIPTION:
XS GIS Cut Line= 3
      2638049.99      6947389.55        2635726.        6947911.
      2634126.03      6949460.97
#Sta/Elev= 30
  2613.9  478.46  3232.5  471.92  3530.1  473.88  3929.8  472.67  4483.2  464.28
  4934.2  461.54  4999.2  460.33  5020.8  457.23  5021.8  456.73  5026.9  457.23
  5045.2  459.17  5115.9  459.39  5130.1   462.8  5151.2  463.45  5429.1  465.44
  5557.9  467.39  5780.6  467.86  5808.9  470.73  5823.1  470.19  5837.2  467.02
  5844.4  468.99  5971.5  470.61  6035.3  469.29  6226.2  470.45  6501.9  469.09
  7060.6  471.05  7117.2  477.17  7152.7  478.06  7195.2  475.75  7223.3  477.72
#Mann= 5 ,-1 , 0
  2613.9     .05       0  5020.8     .03       0  5026.9     .05       0
  5429.1    .075       0  5557.9     .05       0
Bank Sta=5020.8,5026.9
XS Rating Curve= 0 ,0
Exp/Cntr=0.3,0.1

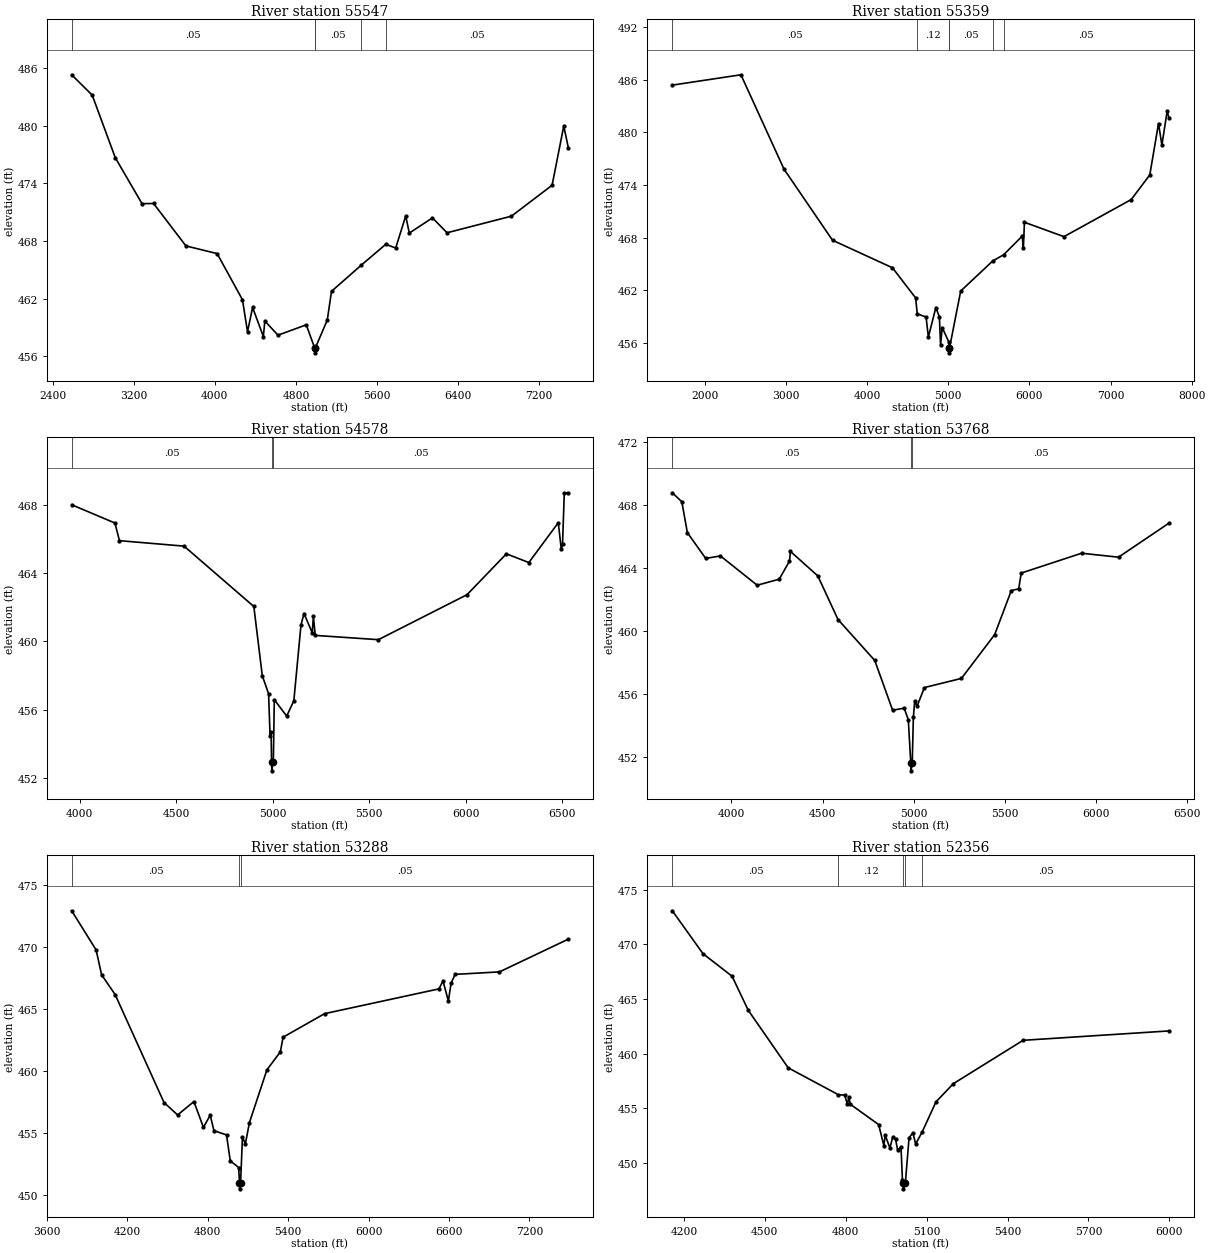
Type RM Length L Ch R = 1 ,55547   ,188,188,188
BEGIN DESCRIPTION:
Little Brushy Creek 85.0
END DESCRIPTION:
XS GIS Cut Line= 6
      2637457.78      6946580.61      2636594.08      6946511.17
      2635773.77      6947162.21      2635484.47      6947566.92
      2634875.33       6948303.7      2633642.71      6949210.81
#Sta/Elev= 30
  2587.5  485.32  2789.9   483.2  3017.5  476.68  3281.5  471.89  3395.3  471.91
  3714.4  467.49  4022.4  466.69  4272.2  461.88  4322.1  458.55  4372.1  461.08
  4478.3  458.05  4492.8  459.67  4622.7  458.19  4901.7  459.27  4984.6  456.85
  4985.6  456.35  4990.7  456.85    5109  459.77  5150.6  462.76  5442.4  465.47
    5686  467.66  5783.7  467.27  5882.7  470.61  5917.9  468.83  6146.5  470.41
  6290.4  468.86  6925.7  470.59  7326.8  473.81  7441.7  479.98  7486.4  477.74
#Mann= 5 ,-1 , 0
  2587.5     .05       0  4984.6     .03       0  4990.7     .05       0
  5442.4    .075       0    5686     .05       0
Bank Sta=4984.6,4990.7
XS Rating Curve= 0 ,0
Exp/Cntr=0.3,0.1

Type RM Length L Ch R = 1 ,55359   ,781,781,781
BEGIN DESCRIPTION:
Little Brushy Creek 83.0
END DESCRIPTION:
XS GIS Cut Line= 6
      2638410.21      6946287.13      2636442.17      6946402.66
      2635782.45      6946932.18      2635426.15      6947395.94
      2634788.53      6948121.41        2633376.        6949161.
#Sta/Elev= 30
  1597.8  485.39  2443.5  486.57  2974.4  475.81  3572.6   467.7  4311.9  464.56
  4597.3  461.12  4617.4  459.31    4726  458.94  4754.2  456.66  4846.5  460.03
  4890.1  458.94  4904.6  455.79  4925.4  457.74  5005.7  456.11  5007.5  455.36
  5008.5  454.86  5013.7  455.36  5152.9  461.91  5546.8  465.33  5681.3  466.04
    5911  468.17  5925.3  466.82  5938.7  469.75  6425.6  468.11  7254.9  472.34
  7483.8  475.15  7591.2  481.01    7633  478.55  7697.7  482.42  7719.7  481.65
#Mann= 7 ,-1 , 0
  1597.8     .05       0  4617.4     .12       0  5005.7     .05       0
  5007.5     .07       0  5013.7     .05       0  5546.8    .075       0
  5681.3     .05       0
Bank Sta=5007.5,5013.7
XS Rating Curve= 0 ,0
Exp/Cntr=0.3,0.1

Type RM Length L Ch R = 1 ,54578   ,810,810,810
BEGIN DESCRIPTION:
Little Brushy Creek 82.0
END DESCRIPTION:
XS GIS Cut Line= 3
      2636497.74      6946305.29       2635546.6      6946730.84
      2634230.29      6947514.85
#Sta/Elev= 30
    3958  467.99  4182.3  466.92  4205.5  465.89  4540.5  465.57  4902.1  462.04
  4945.9     458  4978.7  456.93  4986.2  454.49  4991.7  454.72  4994.1  452.93
  4995.2  452.43  5001.1  452.93  5003.3  452.93  5008.3  456.59  5072.5  455.63
  5109.5  456.53  5146.5  460.95  5162.1  461.63  5204.9   460.5  5210.8  461.46
  5220.5  460.35  5547.7   460.1  6007.1  462.73  6211.2  465.12  6327.6  464.61
  6480.2  466.94  6495.8  465.39  6502.2  465.67  6511.4  468.69  6532.1  468.67
#Mann= 3 ,-1 , 0
    3958     .05       0  4994.1     .03       0  5001.1     .05       0
Bank Sta=4994.1,5001.1
XS Rating Curve= 0 ,0
Exp/Cntr=0.3,0.1

Type RM Length L Ch R = 1 ,53768   ,480,480,480
BEGIN DESCRIPTION:
Little Brushy Creek 81.0
END DESCRIPTION:
XS GIS Cut Line= 3
      2636497.75      6946225.44        2635176.        6946061.
      2633803.24      6945833.07
#Sta/Elev= 30
  3675.8  468.76    3728  468.19  3758.2  466.23    3859  464.59  3939.6  464.75
  4141.1  462.89    4262  463.27  4318.4  464.42  4323.4  465.04  4473.7  463.48
  4584.5  460.71    4786  458.11    4884  454.95  4947.3  455.08  4969.9  454.36
  4983.6   451.6  4984.8   451.1  4991.6   451.6  4997.7  454.49  5005.2  455.55
  5017.9   455.2  5058.4  456.39  5261.2  456.97  5443.6  459.75  5534.9  462.55
  5575.4  462.66  5589.2  463.66  5920.1  464.92  6122.8  464.67  6399.3  466.83
#Mann= 3 ,-1 , 0
  3675.8     .05       0  4983.6     .03       0  4991.6     .05       0
Bank Sta=4983.6,4991.6
XS Rating Curve= 0 ,0
Exp/Cntr=0.3,0.1

Type RM Length L Ch R = 1 ,53288   ,932,932,932
BEGIN DESCRIPTION:
Little Brushy Creek 80.0
END DESCRIPTION:
XS GIS Cut Line= 3
      2636476.03      6945410.99        2635276.        6945611.
      2632793.88      6945814.04
#Sta/Elev= 30
  3783.4  472.95  3965.9  469.79  4006.5  467.79  4107.8  466.19  4472.8  457.48
  4574.2  456.48  4695.8  457.56  4766.8  455.48  4817.5  456.46  4845.4  455.21
  4939.2  454.87    4967  452.78  5030.1  452.24    5036  451.02  5037.2  450.52
  5044.2  451.02  5058.2  454.68  5080.3  454.17  5110.4  455.87  5240.8  460.12
  5341.1  461.57  5361.2  462.75  5670.9  464.65  6525.1  466.65  6555.2  467.29
  6595.3  465.67  6615.4  467.11  6645.5  467.82  6976.6  468.02  7490.4  470.66
#Mann= 3 ,-1 , 0
  3783.4     .05       0    5036     .03       0  5044.2     .05       0
Bank Sta=5036,5044.2
XS Rating Curve= 0 ,0
Exp/Cntr=0.3,0.1

Type RM Length L Ch R = 1 ,52356   ,1022,1022,1022
BEGIN DESCRIPTION:
Little Brushy Creek 78.0
END DESCRIPTION:
XS GIS Cut Line= 3
      2636425.97      6945110.99        2635626.        6944861.
      2634690.24        6944500.
#Sta/Elev= 30
  4157.3  473.09  4270.9  469.16  4378.9  467.09  4438.6  463.98  4586.8   458.7
  4773.3  456.23  4796.4   456.2  4806.3  455.36  4811.6  455.99  4817.3  455.36
  4922.1   453.5  4941.5  451.58  4946.7  452.52    4964  451.35  4973.9  452.32
  4984.9  452.16  4992.8  451.14    5005  451.47  5010.4  448.45  5012.6  448.11
  5013.9  447.61  5021.1  448.11    5035   452.3    5049  452.73  5059.6  451.72
  5084.1  452.85  5134.8  455.58  5198.8  457.24  5457.8  461.22  5998.4  462.08
#Mann= 5 ,-1 , 0
  4157.3     .05       0  4773.3     .12       0  5012.6     .07       0
  5021.1     .12       0  5084.1     .05       0
Bank Sta=5012.6,5021.1
XS Rating Curve= 0 ,0
Exp/Cntr=0.3,0.1

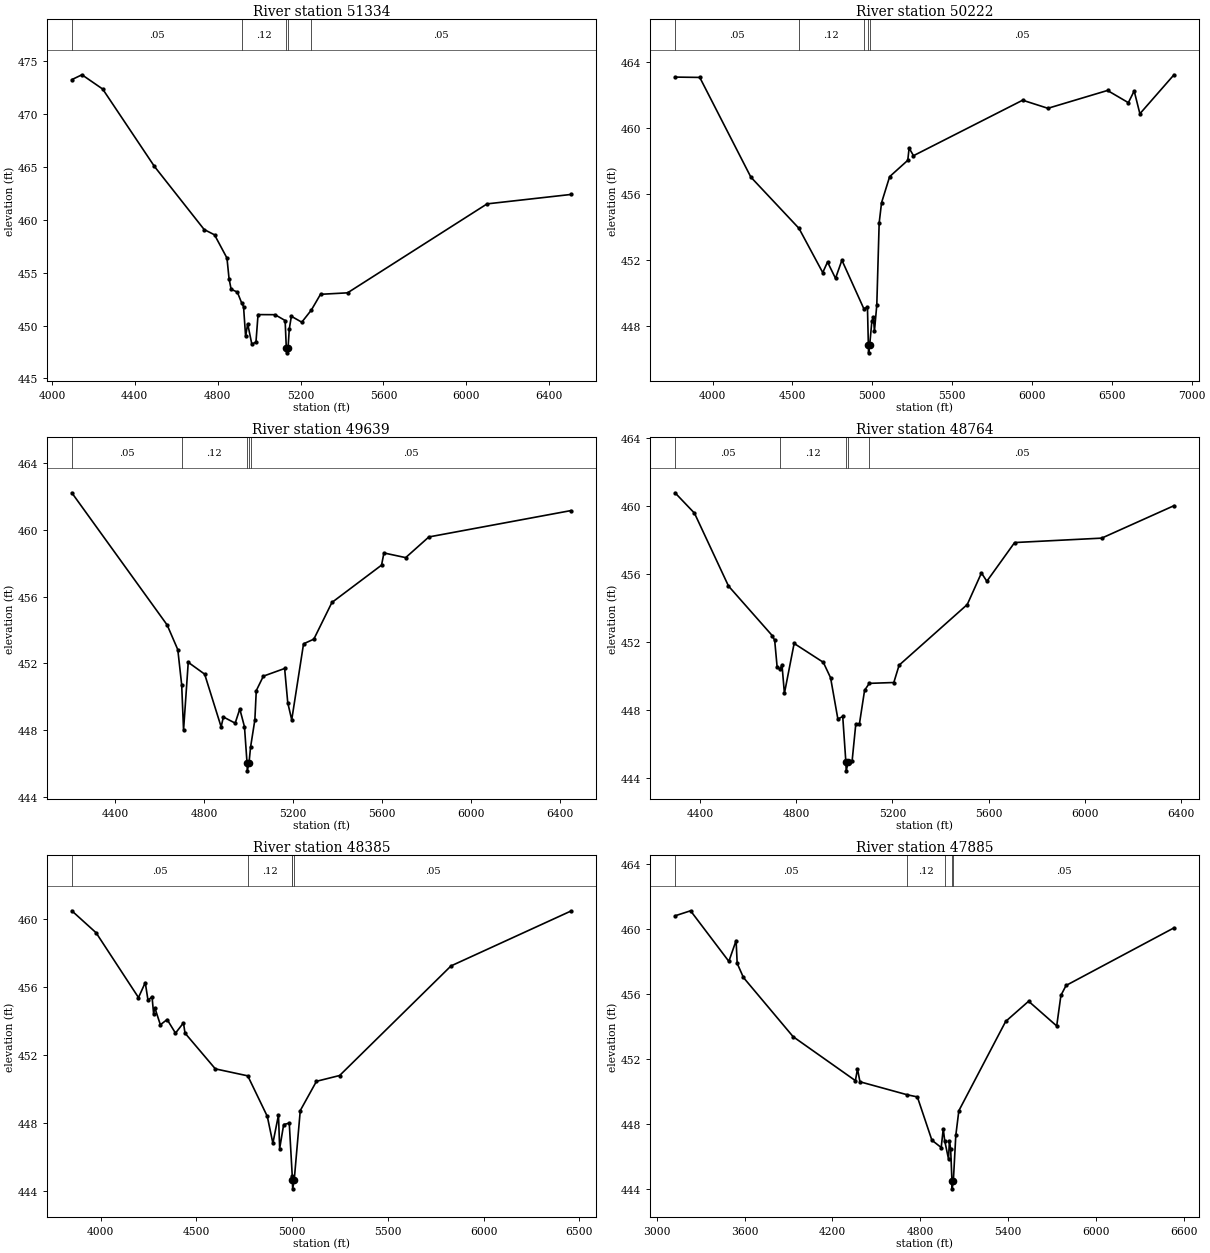
Type RM Length L Ch R = 1 ,51334   ,1112,1112,1112
BEGIN DESCRIPTION:
Little Brushy Creek 77.0
END DESCRIPTION:
XS GIS Cut Line= 3
      2637075.03      6944054.43      2636170.94      6944058.71
      2634673.97      6944208.07
#Sta/Elev= 30
  4095.9  473.28  4144.9  473.74  4244.9  472.39  4494.9  465.06  4734.9  459.09
  4784.9  458.59  4844.9  456.39  4854.9  454.45  4864.9  453.44  4894.9  453.17
  4915.9  452.14  4924.9  451.79  4934.9  448.98  4944.9  450.17  4964.9  448.24
  4984.9  448.44  4994.9  451.04  5076.9  451.03  5125.6  450.48  5131.3  447.92
  5132.6  447.42  5139.9  447.92  5145.7  449.68  5155.7  450.88    5206  450.32
  5252.2  451.47  5296.4  452.96    5427   453.1  6100.4  461.52  6504.4  462.41
#Mann= 5 ,-1 , 0
  4095.9     .05       0  4915.9     .12       0  5131.3     .07       0
  5139.9     .12       0  5252.2     .05       0
Bank Sta=5131.3,5139.9
XS Rating Curve= 0 ,0
Exp/Cntr=0.3,0.1

Type RM Length L Ch R = 1 ,50222   ,583,583,583
BEGIN DESCRIPTION:
Little Brushy Creek 75.0
END DESCRIPTION:
XS GIS Cut Line= 3
      2636760.93      6943340.08      2635525.88      6943350.95
      2633970.88      6944424.18
#Sta/Elev= 30
  3764.9  463.08  3919.8  463.06  4239.9  457.02    4541  453.92  4689.9  451.24
  4719.9  451.88  4769.9  450.89  4809.9  451.99  4946.8  449.06  4969.9  449.14
  4975.5  446.88  4976.8  446.38  4984.2  446.88  4997.4  448.29  5007.4  448.55
  5013.5  447.68  5028.4  449.28  5043.2  454.24  5058.1  455.47  5108.8  457.05
  5222.4  458.04  5230.7  458.78  5258.2  458.32  5941.7  461.68  6099.9  461.19
  6473.1  462.27  6603.7  461.53  6640.1  462.24  6675.9  460.86  6889.4  463.22
#Mann= 5 ,-1 , 0
  3764.9     .05       0    4541     .12       0  4946.8     .05       0
  4975.5     .05       0  4984.2     .05       0
Bank Sta=4975.5,4984.2
XS Rating Curve= 0 ,0
Exp/Cntr=0.3,0.1

Type RM Length L Ch R = 1 ,49639   ,875,875,875
BEGIN DESCRIPTION:
Little Brushy Creek 74.0
END DESCRIPTION:
XS GIS Cut Line= 3
      2636332.79      6942564.85      2635577.96      6942816.89
      2634215.63      6943309.63
#Sta/Elev= 30
  4204.2  462.23  4633.1   454.3    4681  452.82  4698.5  450.71  4706.9  447.99
    4728  452.06  4801.8  451.35  4875.9  448.19  4886.1  448.78  4939.1  448.41
  4959.9  449.26    4981  448.19  4992.3  446.05  4993.7  445.55  5001.6  446.05
  5008.2  446.96  5027.7  448.61    5034  450.36  5065.9  451.23  5161.6  451.69
  5175.7  449.63  5193.5  448.61  5246.7  453.17    5293  453.45  5374.3  455.65
  5597.6  457.89  5608.2  458.62  5706.1  458.34  5810.3  459.58  6448.7  461.16
#Mann= 5 ,-1 , 0
  4204.2     .05       0  4698.5     .12       0  4992.3     .07       0
  5001.6     .12       0  5008.2     .05       0
Bank Sta=4992.3,5001.6
XS Rating Curve= 0 ,0
Exp/Cntr=0.3,0.1

Type RM Length L Ch R = 1 ,48764   ,379,379,379
BEGIN DESCRIPTION:
Little Brushy Creek 73.0
END DESCRIPTION:
XS GIS Cut Line= 3
        2636176.        6942161.        2635476.        6942261.
      2634317.78      6942986.34
#Sta/Elev= 30
  4296.9  460.79  4377.7  459.59  4519.1   455.3    4701  452.38  4711.1   452.1
  4721.2  450.54  4733.1   450.4  4741.4  450.67  4751.5  448.98  4791.9  451.92
  4913.1  450.81  4943.4   449.9  4973.7  447.47  4993.9  447.62    5007  444.92
  5008.3  444.42  5016.4  444.92  5032.9     445  5048.2  447.18    5063  447.16
  5084.7  449.16  5104.2  449.57  5206.2  449.62  5228.2  450.64  5511.4  454.21
  5570.4  456.07  5592.8  455.58  5708.3  457.86  6070.2  458.12  6370.6  460.03
#Mann= 5 ,-1 , 0
  4296.9     .05       0  4733.1     .12       0    5007     .07       0
  5016.4     .12       0  5104.2     .05       0
Bank Sta=5007,5016.4
XS Rating Curve= 0 ,0
Exp/Cntr=0.3,0.1

Type RM Length L Ch R = 1 ,48385   ,500,500,500
BEGIN DESCRIPTION:
Little Brushy Creek 72.0
END DESCRIPTION:
XS GIS Cut Line= 4
       2636206.5      6942128.38      2635719.81      6941754.97
       2635289.2      6942074.74      2634175.98      6943011.02
#Sta/Elev= 30
  3850.2  460.49  3976.9   459.2  4198.3  455.39  4233.6  456.27  4248.1  455.22
  4268.9  455.45  4277.2  454.44  4283.5  454.79  4312.5  453.79  4347.8   454.1
  4391.4   453.3    4433   453.9  4441.2   453.3  4599.4   451.2  4768.6  450.79
  4870.6  448.41  4899.8  446.83    4929  448.49  4935.2  446.52  4956.1  447.93
  4985.3  448.01  5000.8  444.92  5001.6  444.65    5003  444.15    5011  444.65
  5042.7  448.75  5127.3  450.47  5248.2  450.81  5829.6  457.25  6454.6  460.47
#Mann= 5 ,-1 , 0
  3850.2     .05       0  4768.6     .12       0  5000.8     .05       0
  5001.6     .07       0    5011     .05       0
Bank Sta=5001.6,5011
XS Rating Curve= 0 ,0
Exp/Cntr=0.3,0.1

Type RM Length L Ch R = 1 ,47885   ,725,725,725
BEGIN DESCRIPTION:
Little Brushy Creek 71.0
END DESCRIPTION:
XS GIS Cut Line= 4
      2636336.37      6942249.79      2635490.44      6941312.08
      2635042.02      6941728.13      2633852.88       6942693.4
#Sta/Elev= 30
  3125.4  460.82  3231.4  461.13  3492.9  458.02  3542.3   459.3  3549.7   457.9
  3592.3  457.03  3931.8  453.39  4356.8  450.69    4371  451.41  4387.9  450.62
  4711.2  449.82  4779.7  449.69  4878.9  447.03  4942.4  446.58  4956.6  447.73
  4966.3     447  4992.3  445.88  4998.4  446.95  5006.9  446.51  5015.8  444.54
  5017.1  444.04  5025.5  444.54  5042.1  447.32  5062.9  448.84  5382.6  454.33
  5539.2  455.57    5731  454.05  5759.7  455.93  5794.9  456.54  6531.6  460.08
#Mann= 5 ,-1 , 0
  3125.4     .05       0  4711.2     .12       0  4966.3     .05       0
  5015.8     .03       0  5025.5     .05       0
Bank Sta=5015.8,5025.5
XS Rating Curve= 0 ,0
Exp/Cntr=0.3,0.1

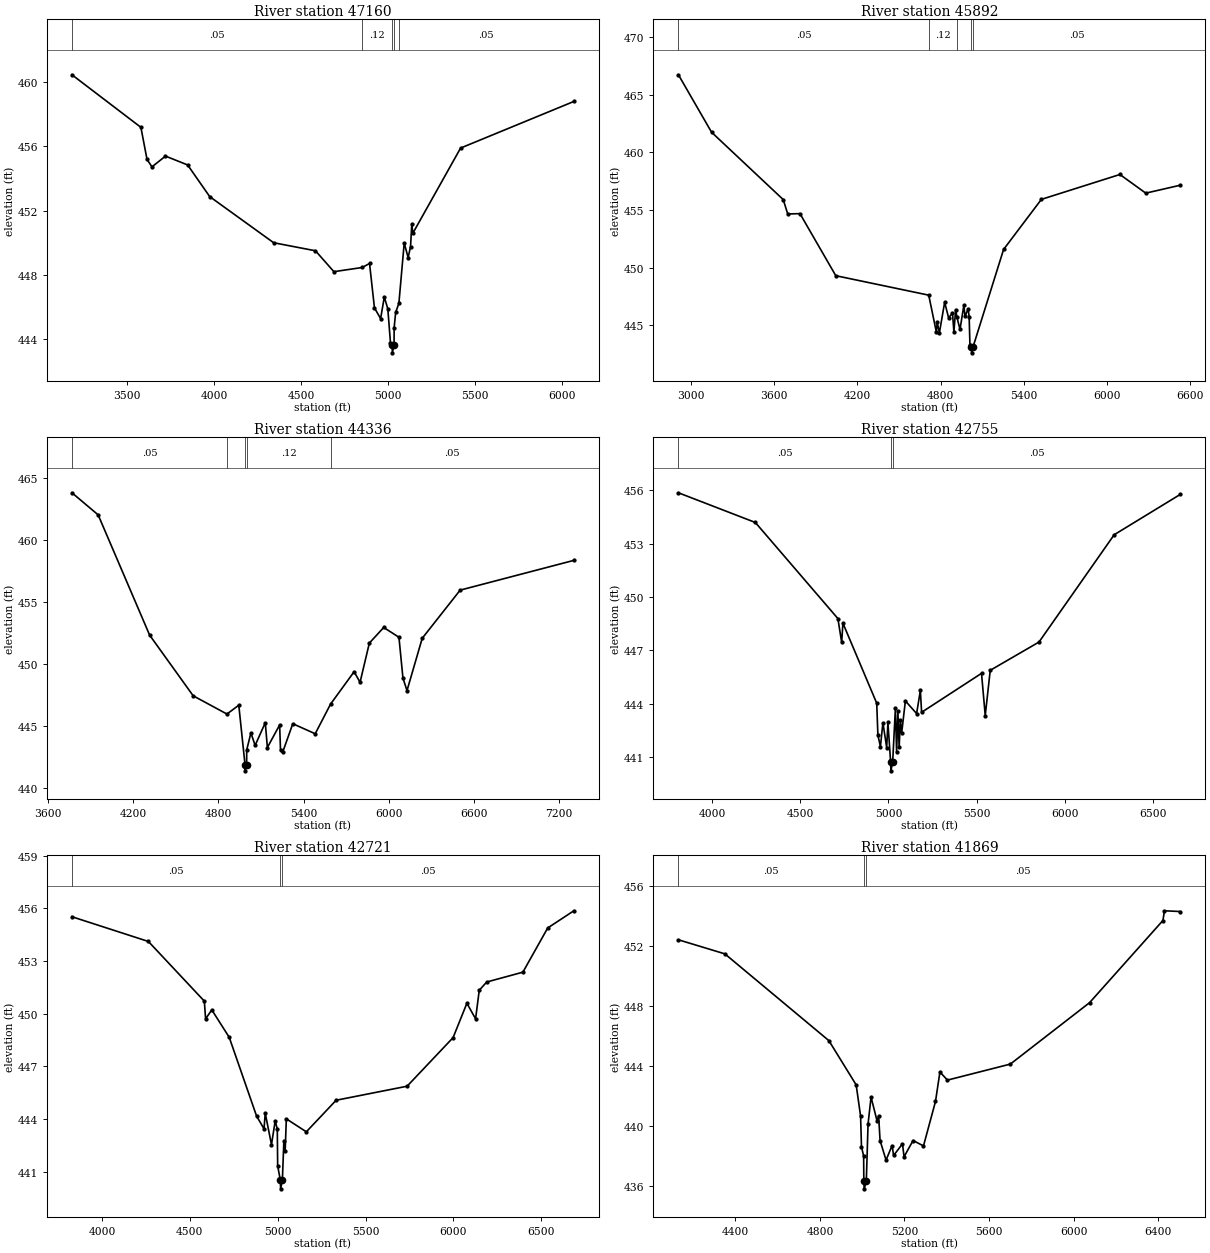
Type RM Length L Ch R = 1 ,47160   ,1268,1268,1268
BEGIN DESCRIPTION:
Little Brushy Creek 70.0
END DESCRIPTION:
XS GIS Cut Line= 3
      2636118.55      6940032.77      2634852.47      6941338.14
      2633971.84      6941943.63
#Sta/Elev= 30
  3181.5  460.45  3578.1  457.18  3613.4  455.18  3641.7  454.72  3719.6  455.39
  3846.9  454.84    3974  452.87  4341.8     450  4582.3   449.5  4688.3   448.2
  4851.4  448.46  4893.4  448.71  4921.6  445.95  4957.1  445.28  4978.2  446.62
  4998.5  445.89  5013.9  443.76  5023.2  443.65  5024.7  443.15  5034.4  443.65
  5034.9  444.71  5043.7  445.67  5062.2  446.23  5092.8  449.98  5115.4  449.08
  5129.2  449.75  5136.3  451.14  5142.4  450.59  5417.1  455.89  6068.7  458.79
#Mann= 5 ,-1 , 0
  3181.5     .05       0  4851.4     .12       0  5023.2     .07       0
  5034.4     .12       0  5062.2     .05       0
Bank Sta=5023.2,5034.4
XS Rating Curve= 0 ,0
Exp/Cntr=0.3,0.1

Type RM Length L Ch R = 1 ,45892   ,1556,1556,1556
BEGIN DESCRIPTION:
Little Brushy Creek 67.0
END DESCRIPTION:
XS GIS Cut Line= 3
      2636374.58      6939555.38      2634355.04       6940622.2
      2633266.95      6941399.99
#Sta/Elev= 30
  2908.6  466.75  3147.8  461.76  3664.8  455.91  3697.5  454.66  3785.6  454.69
  4044.1   449.3  4714.8  447.61    4770  444.39  4775.6  445.25    4792  444.35
  4829.6  446.99    4858  445.65  4886.2  446.05  4896.4  444.41  4908.8  446.36
  4917.9  445.72  4940.4  444.63  4968.1  446.72  4976.6  445.77  4999.3  446.42
  5006.5  445.71  5012.1  443.29  5022.8   443.1  5024.4   442.6  5034.1   443.1
  5254.9  451.58  5527.7  455.93  6094.1  458.09  6280.9  456.47  6530.1  457.16
#Mann= 5 ,-1 , 0
  2908.6     .05       0  4714.8     .12       0  4917.9     .05       0
  5022.8     .05       0  5034.1     .05       0
Bank Sta=5022.8,5034.1
XS Rating Curve= 0 ,0
Exp/Cntr=0.3,0.1

Type RM Length L Ch R = 1 ,44336   ,1581,1581,1581
BEGIN DESCRIPTION:
Little Brushy Creek 65.0
END DESCRIPTION:
XS GIS Cut Line= 3
      2635645.45      6938591.81      2634677.23       6939350.4
      2632790.25      6940670.31
#Sta/Elev= 30
    3770  463.82  3954.3  462.04  4316.9  452.34  4623.4  447.45    4861  445.98
  4944.3  446.69  4988.2   441.9  4989.8   441.4  4999.8   441.9    5000  443.08
  5029.6  444.46  5059.3  443.45  5130.8  445.28  5145.6  443.28  5231.9   445.1
    5238  443.06  5252.9  442.89  5324.4   445.2  5482.2  444.39  5590.2  446.78
    5756  449.39  5797.9  448.54  5863.3   451.7  5964.4  452.96  6071.7  452.17
  6099.8  448.88  6128.3  447.87  6235.6  452.09  6502.5  455.97  7302.8  458.37
#Mann= 5 ,-1 , 0
    3770     .05       0    4861     .12       0  4988.2     .07       0
  4999.8     .12       0  5590.2     .05       0
Bank Sta=4988.2,4999.8
XS Rating Curve= 0 ,0
Exp/Cntr=0.3,0.1

Type RM Length L Ch R = 1 ,42755   ,34,34,34
BEGIN DESCRIPTION:
Mapping XS b01ca8f7
END DESCRIPTION:
XS GIS Cut Line= 4
      2635319.92      6937819.25      2634438.85      6938596.16
      2633904.99      6939116.99      2633193.97      6939706.62
#Sta/Elev= 30
  3810.1  455.86  4246.1  454.19  4713.8  448.79  4735.3  447.45  4742.3  448.53
  4933.9  444.03  4940.5  442.24  4954.8  441.59    4969  442.93  4990.3  441.54
  4997.3  442.95  5012.6  440.73  5014.2  440.23  5024.3  440.73  5039.7  443.74
  5046.7  441.27  5053.9  443.58  5060.9  441.55    5068   443.1    5075  442.34
  5096.3  444.16  5159.9  443.45  5181.2  444.75  5188.2  443.52  5527.7  445.71
  5548.8  443.34  5577.1  445.88  5853.5  447.47  6279.4   453.5  6654.3  455.77
#Mann= 3 ,-1 , 0
  3810.1     .05       0  5012.6     .04       0  5024.3     .05       0
Bank Sta=5012.6,5024.3
XS Rating Curve= 0 ,0
Exp/Cntr=0.3,0.1

Type RM Length L Ch R = 1 ,42721   ,852,852,852
BEGIN DESCRIPTION:
Mapping XS b8e3b6f5
END DESCRIPTION:
XS GIS Cut Line= 3
      2635250.45      6937780.21      2634404.13      6938583.13
       2633141.8      6939706.65
#Sta/Elev= 30
  3828.9  455.53    4264  454.12  4582.3  450.72  4589.6  449.71  4624.8  450.22
  4723.9  448.66  4879.6  444.17  4922.1  443.44    4929  444.33  4964.5  442.54
  4985.6  443.89  4997.6  443.43  4999.7  441.33  5014.8  440.52  5016.5  440.02
  5026.5  440.52  5034.9  442.72  5042.4  442.19  5049.1  444.01  5162.8  443.27
  5332.5  445.07  5736.4  445.87  5998.1  448.64  6076.7   450.6  6126.1  449.71
    6147  451.34  6189.6  451.81  6395.3  452.37  6536.6  454.89  6685.4  455.87
#Mann= 3 ,-1 , 0
  3828.9     .05       0  5014.8     .04       0  5026.5     .05       0
Bank Sta=5014.8,5026.5
XS Rating Curve= 0 ,0
Exp/Cntr=0.3,0.1

Type RM Length L Ch R = 1 ,41869   ,1214,1214,1214
BEGIN DESCRIPTION:
Little Brushy Creek 62.0
END DESCRIPTION:
XS GIS Cut Line= 3
       2634671.9      6937440.77        2633976.        6937961.
       2632961.8      6939072.73
#Sta/Elev= 30
  4130.9  452.43  4350.5  451.49  4842.4  445.69  4971.6  442.73  4992.5  440.64
  4996.6   438.6  5006.9  437.97  5007.8  436.28  5009.4  435.78  5019.5  436.28
  5027.8  440.12    5042  441.91  5070.4  440.32  5077.8  440.65  5084.6  439.01
  5112.9   437.7  5141.3  438.67  5148.7  438.01  5190.6  438.79    5198  437.92
  5240.6  439.01  5289.9  438.65  5346.7  441.62  5367.6  443.59  5403.4  443.05
  5700.7  444.12  6075.7  448.23  6422.3  453.72  6429.7  454.37  6504.6  454.32
#Mann= 3 ,-1 , 0
  4130.9     .05       0  5007.8     .03       0  5019.5     .05       0
Bank Sta=5007.8,5019.5
XS Rating Curve= 0 ,0
Exp/Cntr=0.3,0.1