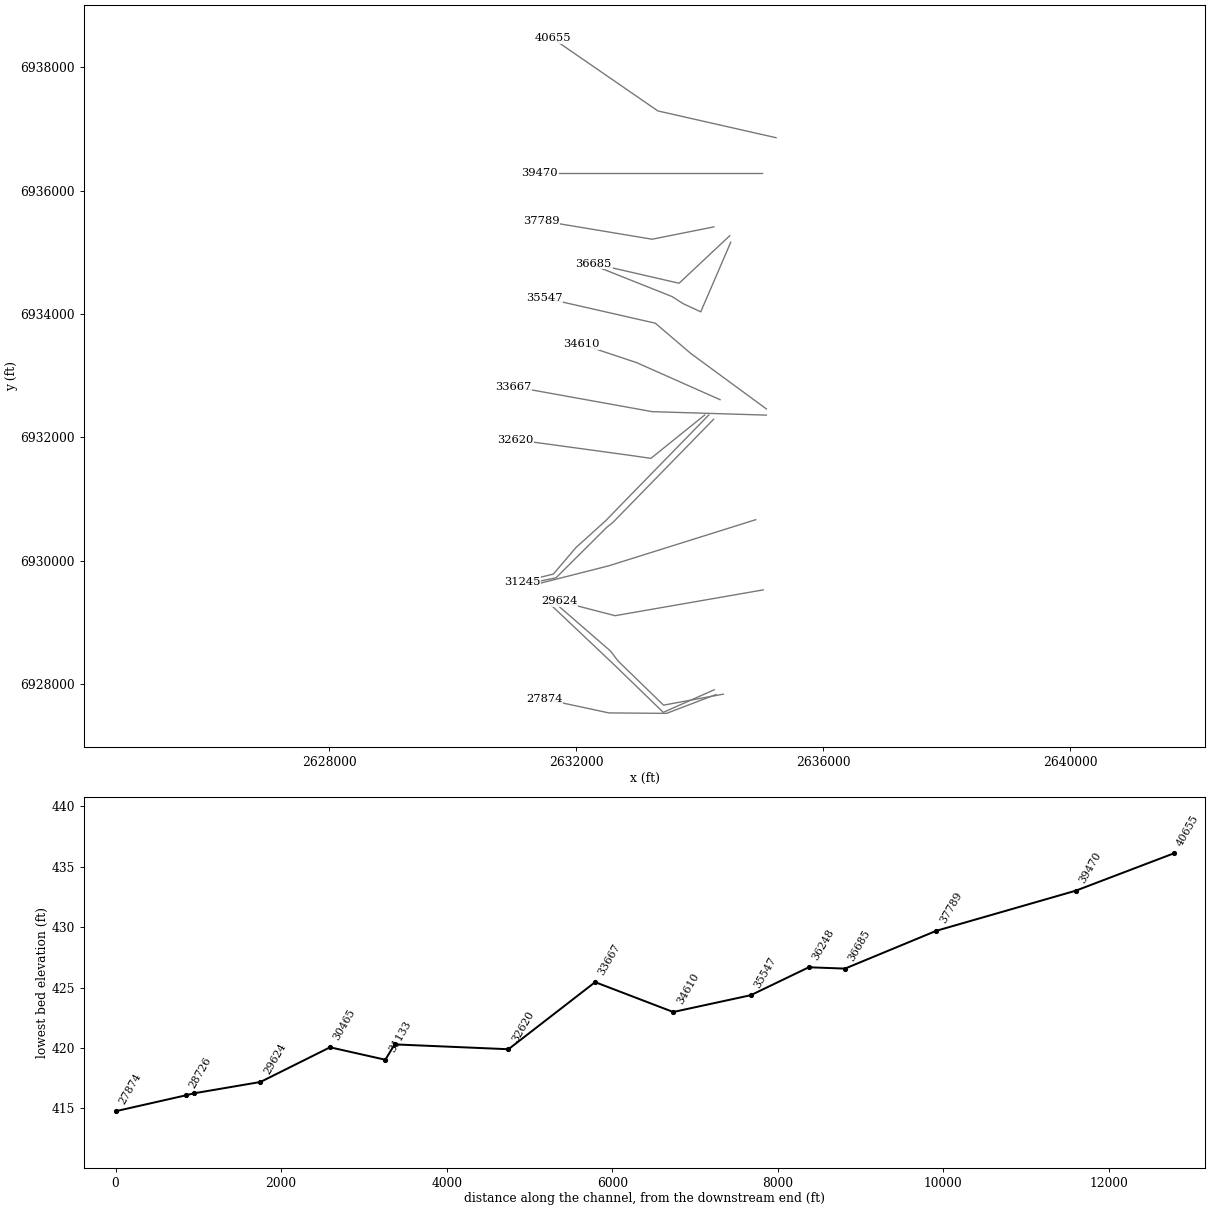
HEC-RAS study Little Brushy Creek.prj: Little Brushy Creek Base Level Engineering

--- Little Brushy Creek.g01 (geometry) --- (continued)

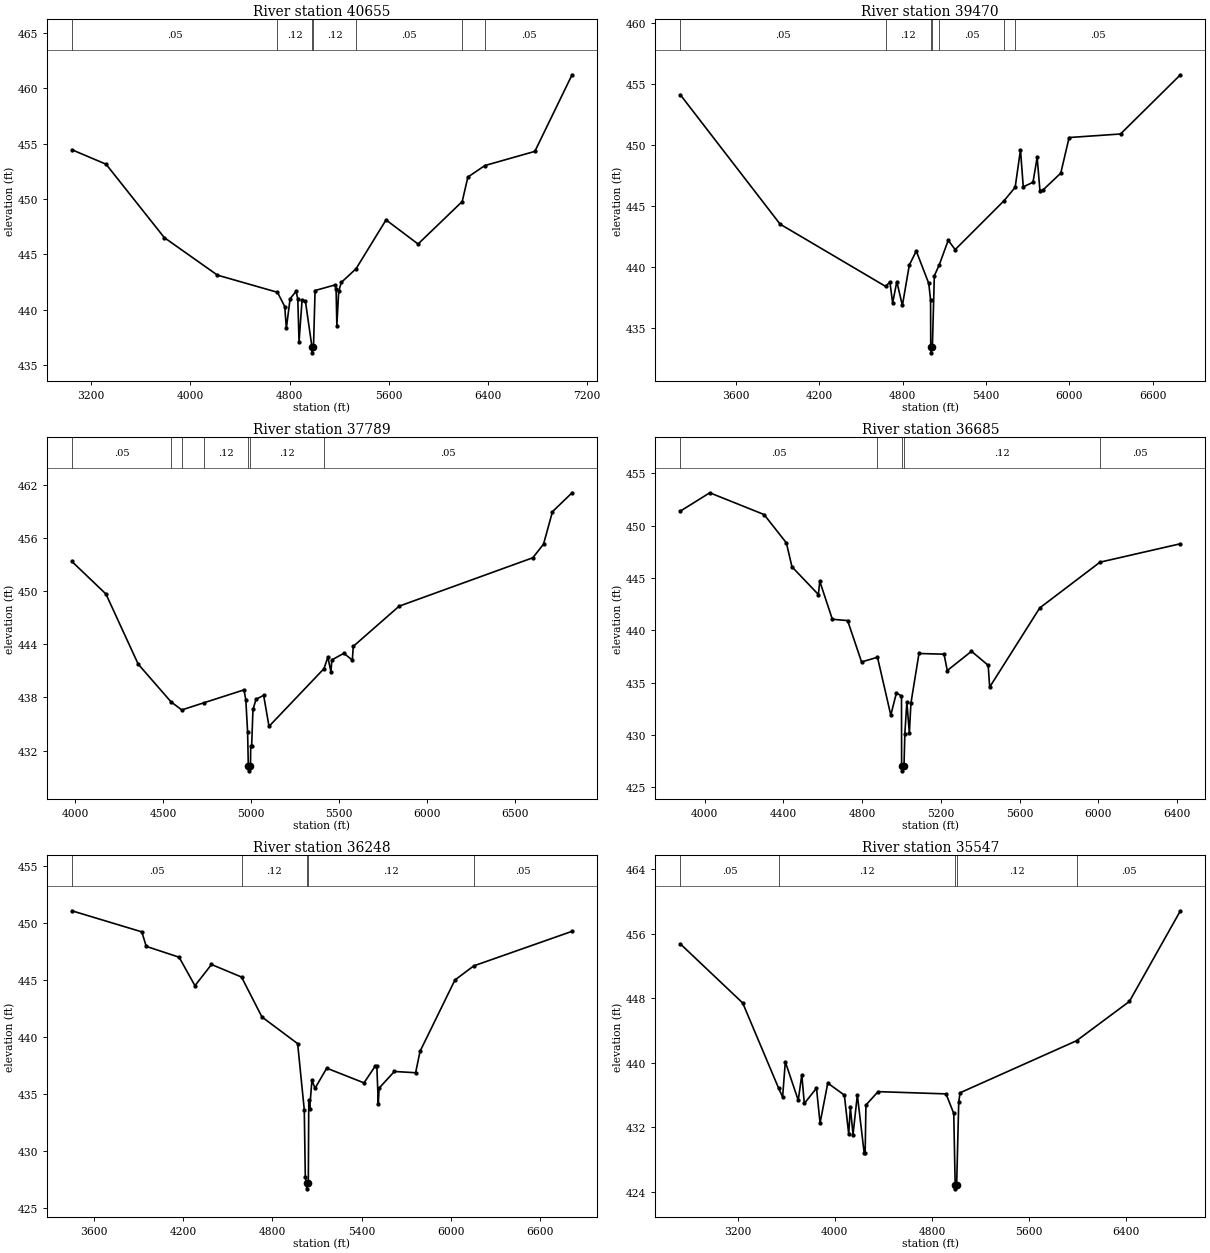
Type RM Length L Ch R = 1 ,40655   ,1185,1185,1185
BEGIN DESCRIPTION:
Mapping XS b2a2c1fd
END DESCRIPTION:
XS GIS Cut Line= 3
      2635233.16       6936855.7      2633319.06      6937289.73
      2631613.29      6938465.98
#Sta/Elev= 30
  3043.9  454.45  3319.8  453.14  3789.5  446.51    4218  443.12  4702.1  441.57
  4761.1  440.28  4773.9  438.31  4804.2  440.99  4852.4  441.66  4866.2  440.97
  4876.4  437.11  4900.7  440.86  4927.7  440.77    4981   436.6  4982.6   436.1
  4992.9   436.6  5005.6  441.73  5168.2  442.24  5175.2  441.86  5181.3  438.56
  5196.2  441.66  5217.1  442.46  5336.4   443.7  5578.2  448.11  5836.3  445.93
  6192.6  449.77  6238.2  451.98  6375.5  453.02  6778.4   454.3  7078.6  461.22
#Mann= 7 ,-1 , 0
  3043.9     .05       0  4702.1     .12       0    4981     .07       0
  4992.9     .12       0  5336.4     .05       0  6192.6     .12       0
  6375.5     .05       0
Bank Sta=4981,4992.9
XS Rating Curve= 0 ,0
Exp/Cntr=0.3,0.1

Type RM Length L Ch R = 1 ,39470   ,1681,1681,1681
BEGIN DESCRIPTION:
Little Brushy Creek 60.0
END DESCRIPTION:
XS GIS Cut Line= 3
      2635005.02        6936281.      2633205.02        6936281.
      2631405.02        6936281.
#Sta/Elev= 30
    3200  454.12    3919  443.53  4678.5  438.44    4709   438.8    4729  437.09
    4759  438.83    4799  436.88    4849  440.19    4899  441.33    4989  438.68
    5002  437.32  5003.1  433.51  5004.7  433.01    5015  433.51    5029  439.31
    5065  440.22    5129  442.21    5179  441.45  5531.2  445.45  5610.7  446.54
    5649   449.6    5669  446.58    5739  446.95    5769  448.99    5789  446.28
    5809   446.3    5939   447.7    5999  450.61    6369   450.9    6800  455.74
#Mann= 7 ,-1 , 0
    3200     .05       0  4678.5     .12       0  5003.1     .07       0
    5015     .12       0    5065     .05       0  5531.2     .12       0
  5610.7     .05       0
Bank Sta=5003.1,5015
XS Rating Curve= 0 ,0
Exp/Cntr=0.3,0.1

Type RM Length L Ch R = 1 ,37789   ,1104,1104,1104
BEGIN DESCRIPTION:
Little Brushy Creek 58.0
END DESCRIPTION:
XS GIS Cut Line= 3
      2634225.96      6935410.99        2633226.        6935211.
      2631425.99        6935511.
#Sta/Elev= 30
  3980.7  453.39  4174.4  449.71    4358  441.77  4544.9   437.5  4605.8  436.59
  4734.6  437.42  4959.7  438.86  4969.9  437.73  4980.1  434.11  4984.2   430.2
  4985.9   429.7  4996.4   430.2  4997.9  432.47    5003  432.47  5010.6  436.64
  5028.3   437.8  5071.4  438.24  5101.8  434.73  5414.4  441.26  5436.4  442.55
  5454.1  440.91  5459.2  442.25  5527.6     443  5575.8  442.22  5580.9  443.78
  5841.9  448.33  6602.3  453.81  6663.1  455.35  6713.8  459.02  6825.3  461.16
#Mann= 7 ,-1 , 0
  3980.7     .05       0  4544.9     .12       0  4605.8     .05       0
  4734.6     .12       0  4984.2     .07       0  4996.4     .12       0
  5414.4     .05       0
Bank Sta=4984.2,4996.4
XS Rating Curve= 0 ,0
Exp/Cntr=0.3,0.1

Type RM Length L Ch R = 1 ,36685   ,437,437,437
BEGIN DESCRIPTION:
Little Brushy Creek 57.0
END DESCRIPTION:
XS GIS Cut Line= 3
      2634482.26      6935267.17      2633662.55      6934497.68
      2632281.72      6934815.78
#Sta/Elev= 30
  3875.7  451.37  4025.9  453.13  4301.9  451.05  4415.2  448.34  4443.5  446.06
  4577.8  443.41  4584.7  444.68  4648.7  441.05  4726.3  440.92  4797.1  436.97
    4878  437.42  4945.6  431.89    4974     434    5000  433.73  5000.6  427.07
  5002.3  426.57  5012.8  427.07    5017   430.1  5027.2  433.15  5039.9  430.18
  5047.8  433.02  5088.8  437.78  5216.2  437.71  5232.5  436.15  5355.6  437.99
  5440.4  436.65    5448  434.57  5702.3  442.13  6008.5   446.5    6417  448.26
#Mann= 5 ,-1 , 0
  3875.7     .05       0    4878     .12       0  5000.6     .07       0
  5012.8     .12       0  6008.5     .05       0
Bank Sta=5000.6,5012.8
XS Rating Curve= 0 ,0
Exp/Cntr=0.3,0.1

Type RM Length L Ch R = 1 ,36248   ,701,701,701
BEGIN DESCRIPTION:
Little Brushy Creek 56.0
END DESCRIPTION:
XS GIS Cut Line= 5
      2634499.62      6935163.01       2634013.5      6934034.52
      2633723.51      6934169.03      2633549.09      6934281.92
      2632056.75      6934876.25
#Sta/Elev= 30
  3451.6  451.06    3922  449.21  3951.4  447.94  4172.4  446.99    4279  444.49
  4390.2  446.35  4592.1  445.25  4729.3  441.75  4969.4  439.41  5013.9  433.61
  5020.9  427.72  5028.9  427.18  5030.6  426.68  5041.1  427.18  5044.2  434.49
  5050.1  433.68  5065.3   436.2  5086.4   435.5  5164.9  437.26  5415.6  435.97
  5492.7  437.48  5501.7  437.42  5511.6  434.13    5517  435.51  5619.5  436.97
  5762.4  436.86  5792.3  438.74  6026.7  444.99  6153.5  446.23  6814.1  449.26
#Mann= 5 ,-1 , 0
  3451.6     .05       0  4592.1     .12       0  5028.9     .07       0
  5041.1     .12       0  6153.5     .05       0
Bank Sta=5028.9,5041.1
XS Rating Curve= 0 ,0
Exp/Cntr=0.3,0.1

Type RM Length L Ch R = 1 ,35547   ,937,937,937
BEGIN DESCRIPTION:
Little Brushy Creek 55.0
END DESCRIPTION:
XS GIS Cut Line= 4
      2635075.97      6932461.02      2633851.01      6933360.98
      2633277.11      6933850.45      2631476.01        6934261.
#Sta/Elev= 30
  2725.7  454.75  3240.7  447.41  3537.6  436.81  3569.5  435.76  3591.8  440.11
  3698.3  435.35  3727.6  438.51  3748.4  434.95  3848.7  436.85    3878  432.52
  3941.7  437.48  4078.2  435.99  4114.2  431.16  4127.8  434.48  4149.7  431.09
  4185.2     436  4241.5  428.83  4249.6  428.84  4256.2  434.76  4356.1  436.42
  4916.1  436.14  4979.7  433.72  4991.3  424.87    4993  424.37  5003.6  424.87
  5020.8  435.12  5031.9  436.28  5991.6  442.73  6426.8   447.6  6847.3  458.84
#Mann= 5 ,-1 , 0
  2725.7     .05       0  3537.6     .12       0  4991.3     .07       0
  5003.6     .12       0  5991.6     .05       0
Bank Sta=4991.3,5003.6
XS Rating Curve= 0 ,0
Exp/Cntr=0.3,0.1

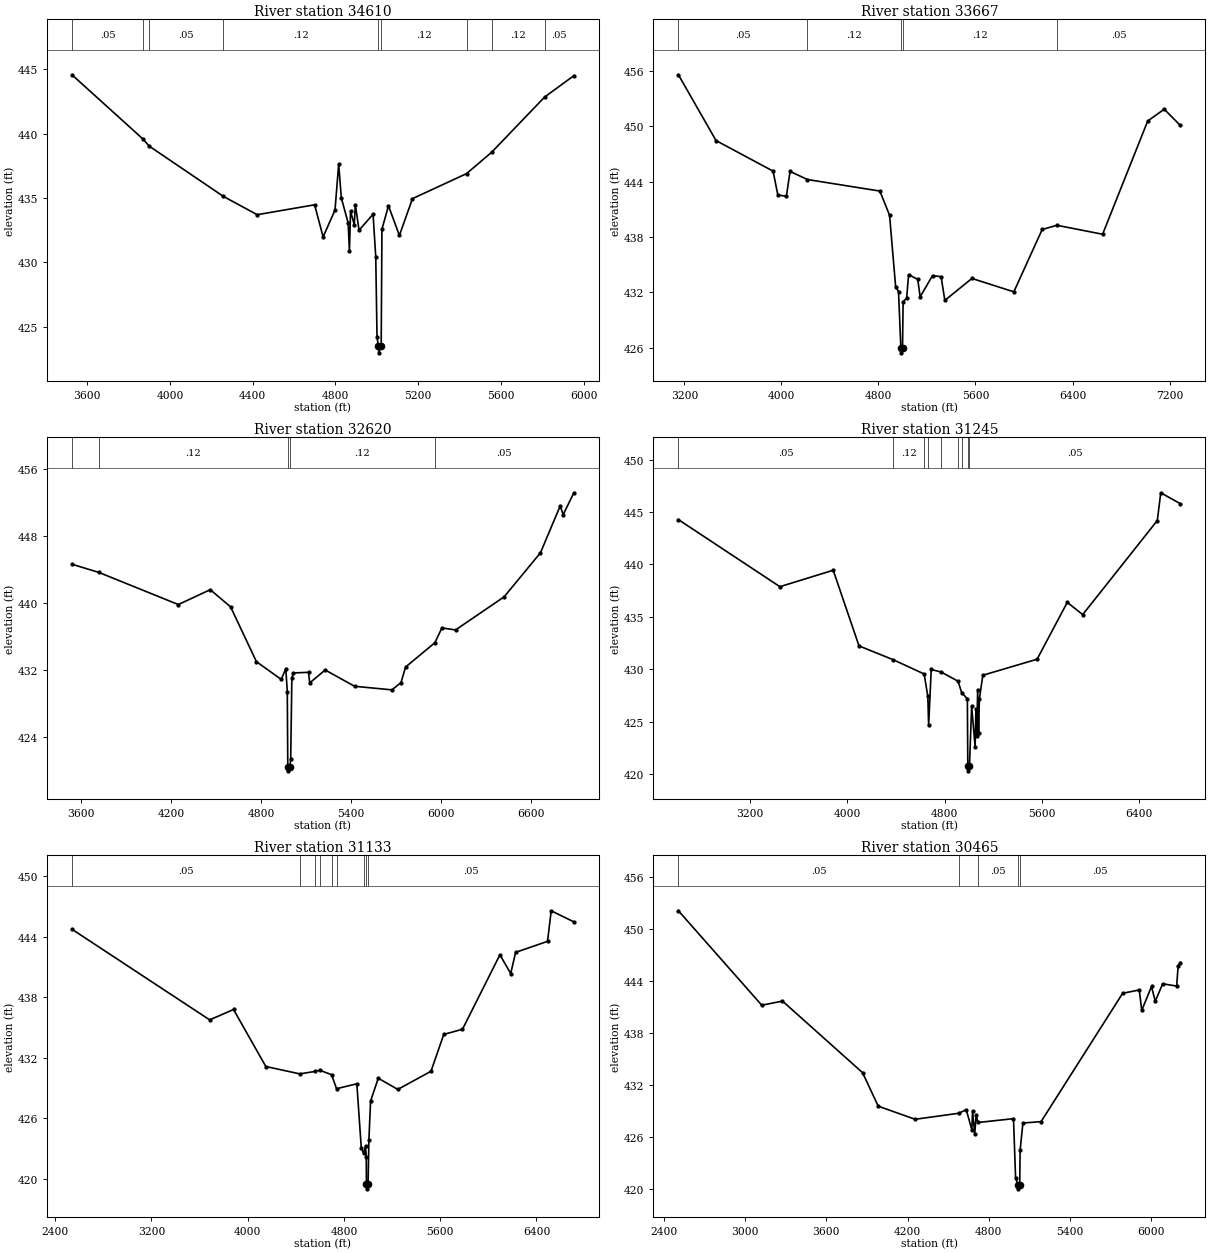
Type RM Length L Ch R = 1 ,34610   ,943,943,943
BEGIN DESCRIPTION:
Little Brushy Creek 53.0
END DESCRIPTION:
XS GIS Cut Line= 3
      2634325.99        6932611.        2632976.        6933211.
        2632076.        6933511.
#Sta/Elev= 30
  3526.2  444.58  3868.7   439.6  3899.5  439.04  4257.4  435.14  4421.5  433.71
  4699.2  434.48  4740.2  431.98  4797.7  434.07  4815.4  437.63  4828.4     435
  4861.3  433.07  4867.4  430.87  4872.9  433.98  4890.7  432.94  4896.1  434.49
  4913.9   432.5  4981.6  433.75  4994.6  430.45  5000.8  424.23  5007.3  423.48
  5009.2  422.98  5020.9  423.48  5024.6  432.59  5056.2   434.4  5108.9   432.1
  5172.2  434.96  5433.4   436.9  5554.8  438.56  5810.9  442.85  5952.2  444.51
#Mann= 9 ,-1 , 0
  3526.2     .05       0  3868.7     .12       0  3899.5     .05       0
  4257.4     .12       0  5007.3     .07       0  5020.9     .12       0
  5433.4     .05       0  5554.8     .12       0  5810.9     .05       0
Bank Sta=5007.3,5020.9
XS Rating Curve= 0 ,0
Exp/Cntr=0.3,0.1

Type RM Length L Ch R = 1 ,33667   ,1047,1047,1047
BEGIN DESCRIPTION:
Little Brushy Creek 52.0
END DESCRIPTION:
XS GIS Cut Line= 3
      2635076.01        6932361.      2633227.86      6932417.09
      2630975.35      6932823.58
#Sta/Elev= 30
    3151  455.58  3461.2  448.45  3931.4  445.14  3970.8  442.55  4041.4  442.42
  4071.4  445.11  4214.5  444.23  4811.8  442.98  4891.8  440.36  4941.8  432.62
  4965.5  432.09    4985  425.95    4987  425.45  4998.7  425.95  5003.5  430.99
  5032.4  431.38  5048.9  433.93  5123.8  433.41  5144.2  431.52  5245.8  433.82
  5316.9   433.7  5347.4  431.13  5570.9  433.51  5916.4  432.06  6150.1  438.82
  6271.8  439.27  6648.1   438.3    7020  450.57  7156.1  451.85  7288.9  450.09
#Mann= 5 ,-1 , 0
    3151     .05       0  4214.5     .12       0    4985     .07       0
  4998.7     .12       0  6271.8     .05       0
Bank Sta=4985,4998.7
XS Rating Curve= 0 ,0
Exp/Cntr=0.3,0.1

Type RM Length L Ch R = 1 ,32620   ,1375,1375,1375
BEGIN DESCRIPTION:
Mapping XS 88086dc0
END DESCRIPTION:
XS GIS Cut Line= 4
      2634078.58      6932363.49      2633206.21      6931660.39
      2632876.35      6931708.13      2631005.73      6931964.21
#Sta/Elev= 30
  3541.1  444.65  3721.7  443.66  4249.3  439.82    4462   441.6  4597.6  439.54
  4769.2  432.98  4934.6  430.85  4964.9  432.14  4974.9  429.39  4978.2   420.4
  4980.2   419.9  4991.9   420.4  4997.5  421.28  5005.3  431.01  5015.4  431.63
  5116.3   431.7    5124  430.43  5227.3  431.98  5422.8  430.03  5671.4   429.6
    5732  430.47  5762.3  432.33  5957.5  435.25  6004.5  437.02  6095.3  436.78
  6418.3  440.74  6660.6  446.02  6791.8  451.63    6812   450.6  6882.9  453.21
#Mann= 5 ,-1 , 0
  3541.1     .05       0  3721.7     .12       0  4978.2     .07       0
  4991.9     .12       0  5957.5     .05       0
Bank Sta=4978.2,4991.9
XS Rating Curve= 0 ,0
Exp/Cntr=0.3,0.1

Type RM Length L Ch R = 1 ,31245   ,112,112,112
BEGIN DESCRIPTION:
Mapping XS 15a03d9c
END DESCRIPTION:
XS GIS Cut Line= 6
       2634143.7      6932363.51      2632675.46      6930857.88
      2632475.88      6930650.95      2631995.78      6930218.56
      2631626.35      6929785.39       2631119.8      6929659.84
#Sta/Elev= 30
  2609.5  444.27  3444.1  437.87  3882.6  439.44  4094.6  432.22  4372.3  430.92
  4630.4  429.54  4660.7   427.4  4667.4  424.63  4688.7  429.97    4770  429.73
  4909.3  428.85  4938.7  427.77  4985.9  427.17  4989.5   420.8  4991.5   420.3
  5003.4   420.8  5021.2  426.49  5049.6  422.58  5056.3  426.24  5063.8  423.63
  5070.5  428.05    5078  423.88  5084.7  427.16  5113.1  429.42  5559.3  430.95
  5807.4  436.37  5934.7  435.21    6548  444.18  6576.4  446.83  6737.3  445.79
#Mann= 9 ,-1 , 0
  2609.5     .05       0  4372.3     .12       0  4630.4     .05       0
  4660.7     .12       0    4770     .05       0  4909.3     .12       0
  4938.7     .05       0  4989.5     .03       0  5003.4     .05       0
Bank Sta=4989.5,5003.4
XS Rating Curve= 0 ,0
Exp/Cntr=0.3,0.1

Type RM Length L Ch R = 1 ,31133   ,668,668,668
BEGIN DESCRIPTION:
Mapping XS e0171829
END DESCRIPTION:
XS GIS Cut Line= 5
      2634221.83      6932294.07      2632593.43      6930624.81
      2632492.89      6930544.43      2631669.75      6929724.63
      2631131.52      6929616.11
#Sta/Elev= 30
  2539.3  444.75  3684.1  435.77  3882.2   436.8  4150.8  431.15  4432.8  430.42
  4558.6  430.66  4598.5  430.78  4696.9  430.34  4738.5  428.95  4907.1  429.44
  4943.9   423.1  4963.3  422.54  4979.1  423.26  4985.5   422.2  4986.6  419.53
  4988.6  419.03  5000.5  419.53  5007.3  423.88  5021.4  427.73  5085.1  429.99
  5247.7  428.88  5523.5  430.68  5629.6  434.33  5785.1  434.84  6096.3  442.22
    6186  440.36  6226.8  442.46    6492  443.55  6522.6  446.58  6710.8  445.48
#Mann= 9 ,-1 , 0
  2539.3     .05       0  4432.8     .12       0  4558.6     .05       0
  4598.5     .12       0  4696.9     .05       0  4738.5     .12       0
  4963.3     .05       0  4986.6     .03       0  5000.5     .05       0
Bank Sta=4986.6,5000.5
XS Rating Curve= 0 ,0
Exp/Cntr=0.3,0.1

Type RM Length L Ch R = 1 ,30465   ,841,841,841
BEGIN DESCRIPTION:
Little Brushy Creek 46.0
END DESCRIPTION:
XS GIS Cut Line= 3
      2634903.22      6930666.46      2632525.98      6929919.94
      2631349.83      6929620.78
#Sta/Elev= 30
  2508.3  452.12  3123.8  441.23  3276.6  441.71    3868  433.45  3983.5  429.59
  4255.8  428.08  4576.3  428.77  4633.1  429.18  4674.6  426.87  4679.8  428.99
    4696  426.42  4706.5   428.6    4719  427.71    4982  428.15  4997.4  421.36
  5013.8  420.56  5015.8  420.06    5028  420.56  5030.9   424.5  5051.5  427.65
  5185.7  427.81    5788  442.61  5910.8  442.99  5928.6  440.63  6000.9  443.39
  6028.4  441.69  6083.4   443.7  6186.6  443.44  6197.3  445.74  6213.6  446.15
#Mann= 5 ,-1 , 0
  2508.3     .05       0  4576.3     .12       0    4719     .05       0
  5013.8     .03       0    5028     .05       0
Bank Sta=5013.8,5028
XS Rating Curve= 0 ,0
Exp/Cntr=0.3,0.1

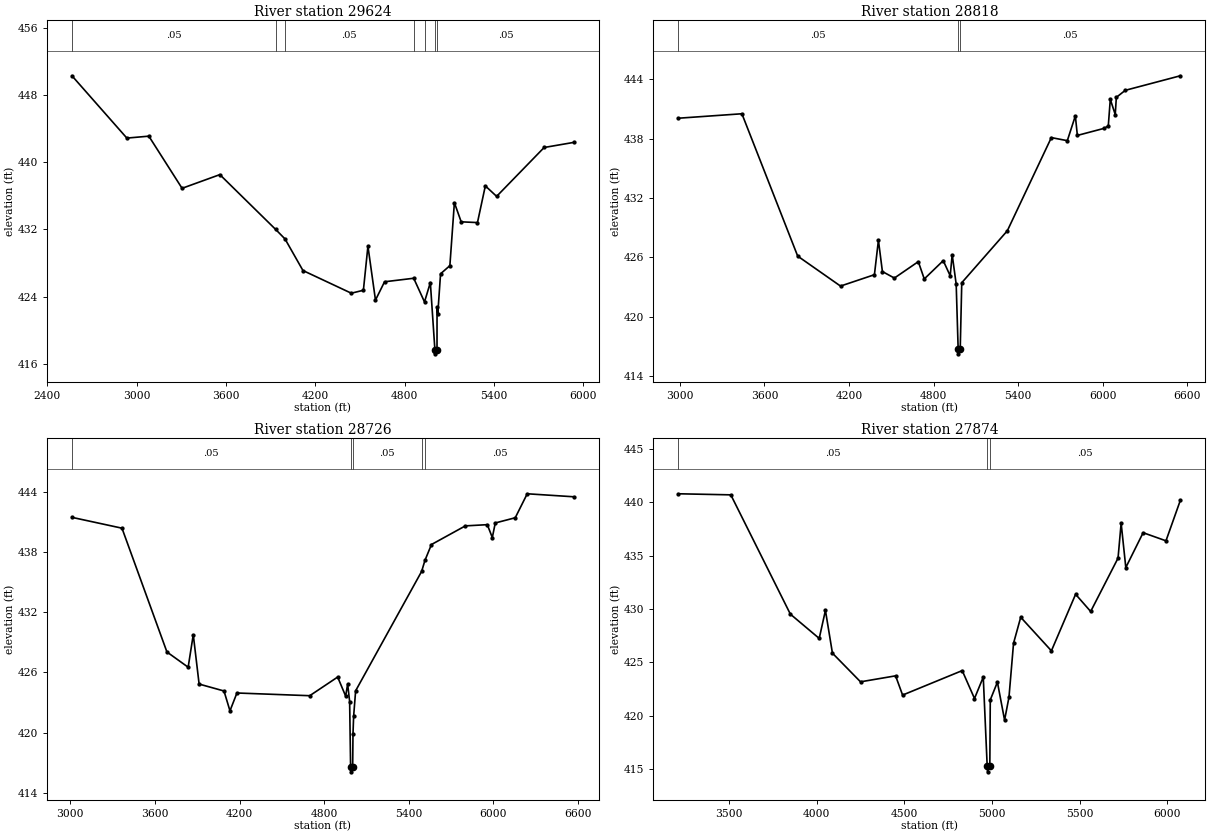
Type RM Length L Ch R = 1 ,29624   ,806,806,806
BEGIN DESCRIPTION:
Little Brushy Creek 44.0
END DESCRIPTION:
XS GIS Cut Line= 3
      2635024.79      6929529.32        2632626.        6929111.
      2631719.29      6929346.56
#Sta/Elev= 30
  2565.4   450.3  2934.3  442.88  3081.9  443.11  3305.2   436.9    3559  438.53
  3934.1     432  3996.8  430.87  4117.3  427.11  4442.1  424.41  4523.3  424.76
  4553.8  430.01  4604.5  423.59  4665.4  425.77  4861.3  426.19  4933.9  423.37
  4973.1  425.68  5003.6  417.69  5005.6  417.19  5017.9  417.69  5018.1   422.8
  5023.2  421.98  5041.7  426.72  5104.3  427.69  5134.6  435.19  5180.3  432.91
  5289.7  432.82  5342.5  437.19  5418.4  435.94  5737.6  441.76  5937.2  442.37
#Mann= 7 ,-1 , 0
  2565.4     .05       0  3934.1     .12       0  3996.8     .05       0
  4861.3     .12       0  4933.9     .05       0  5003.6     .04       0
  5017.9     .05       0
Bank Sta=5003.6,5017.9
XS Rating Curve= 0 ,0
Exp/Cntr=0.3,0.1

Type RM Length L Ch R = 1 ,28818   ,92,92,92
BEGIN DESCRIPTION:
Mapping XS e716e2b1
END DESCRIPTION:
XS GIS Cut Line= 5
      2634378.76      6927839.73      2633410.92      6927661.78
      2632675.06      6928376.39      2632549.38      6928540.69
      2631535.19      6929420.82
#Sta/Elev= 30
  2990.2  440.07  3440.4  440.52  3836.1  426.13  4139.8   423.1  4380.3  424.25
  4408.6  427.73  4436.9  424.57  4521.8  423.91  4691.5  425.57  4733.8  423.82
  4868.3  425.67  4917.7  424.14  4931.8  426.27  4960.1   423.3  4974.1  416.75
  4976.1  416.25  4988.8  416.75  4999.7  423.44  5322.8  428.69    5635  438.11
  5748.3   437.8  5805.3  440.31  5819.5  438.33  6010.4  439.05  6038.9   439.3
  6053.1  441.98  6088.2  440.44  6095.9  442.18  6159.5  442.89  6549.7  444.36
#Mann= 3 ,-1 , 0
  2990.2     .05       0  4974.1     .04       0  4988.8     .05       0
Bank Sta=4974.1,4988.8
XS Rating Curve= 0 ,0
Exp/Cntr=0.3,0.1

Type RM Length L Ch R = 1 ,28726   ,852,852,852
BEGIN DESCRIPTION:
Little Brushy Creek 42.0
END DESCRIPTION:
XS GIS Cut Line= 4
      2634232.23      6927911.25      2633406.58       6927544.6
       2632627.6       6928300.3      2631487.43      6929380.04
#Sta/Elev= 30
  3011.3  441.46    3366  440.38  3684.8  428.04  3835.3  426.52  3871.6  429.76
    3913  424.84  4089.4  424.15  4131.8  422.17  4181.2  423.95  4697.5  423.68
  4895.5  425.54  4952.1  423.64  4966.3  424.84  4980.4   423.1  4987.2  416.59
  4989.2  416.09  5001.9  416.59  5004.1  419.85  5008.7  421.63  5022.9  424.17
  5490.9  436.07  5514.4  437.17  5560.5  438.75    5801  440.61  5956.5  440.73
  5992.1  439.45  6013.1   440.9  6154.7  441.42  6239.7  443.81  6570.3  443.51
#Mann= 5 ,-1 , 0
  3011.3     .05       0  4987.2     .03       0  5001.9     .05       0
  5490.9    .075       0  5514.4     .05       0
Bank Sta=4987.2,5001.9
XS Rating Curve= 0 ,0
Exp/Cntr=0.3,0.1

Type RM Length L Ch R = 1 ,27874   ,570,570,570
BEGIN DESCRIPTION:
Little Brushy Creek 40.0
END DESCRIPTION:
XS GIS Cut Line= 4
      2634258.32      6927833.14      2633458.67      6927528.32
      2632525.68      6927535.89      2631476.05      6927760.99
#Sta/Elev= 30
  3211.2  440.78    3510  440.68  3849.7  429.52  4014.2  427.25  4049.6  429.87
  4089.6  425.87  4249.7  423.19  4449.7  423.75  4489.7  421.95  4829.7  424.24
  4899.7  421.63  4949.7  423.63  4972.2  415.27  4974.2  414.77  4987.1  415.27
  4989.7   421.5  5030.4  423.16  5071.3  419.61  5096.4  421.76  5122.4   426.8
  5163.3  429.23  5338.3  426.09  5476.3  431.38  5562.2  429.77  5718.3  434.76
    5736  438.03  5762.6  433.88  5861.4  437.14  5991.7  436.38  6073.5  440.16
#Mann= 3 ,-1 , 0
  3211.2     .05       0  4972.2     .04       0  4987.1     .05       0
Bank Sta=4972.2,4987.1
XS Rating Curve= 0 ,0
Exp/Cntr=0.3,0.1