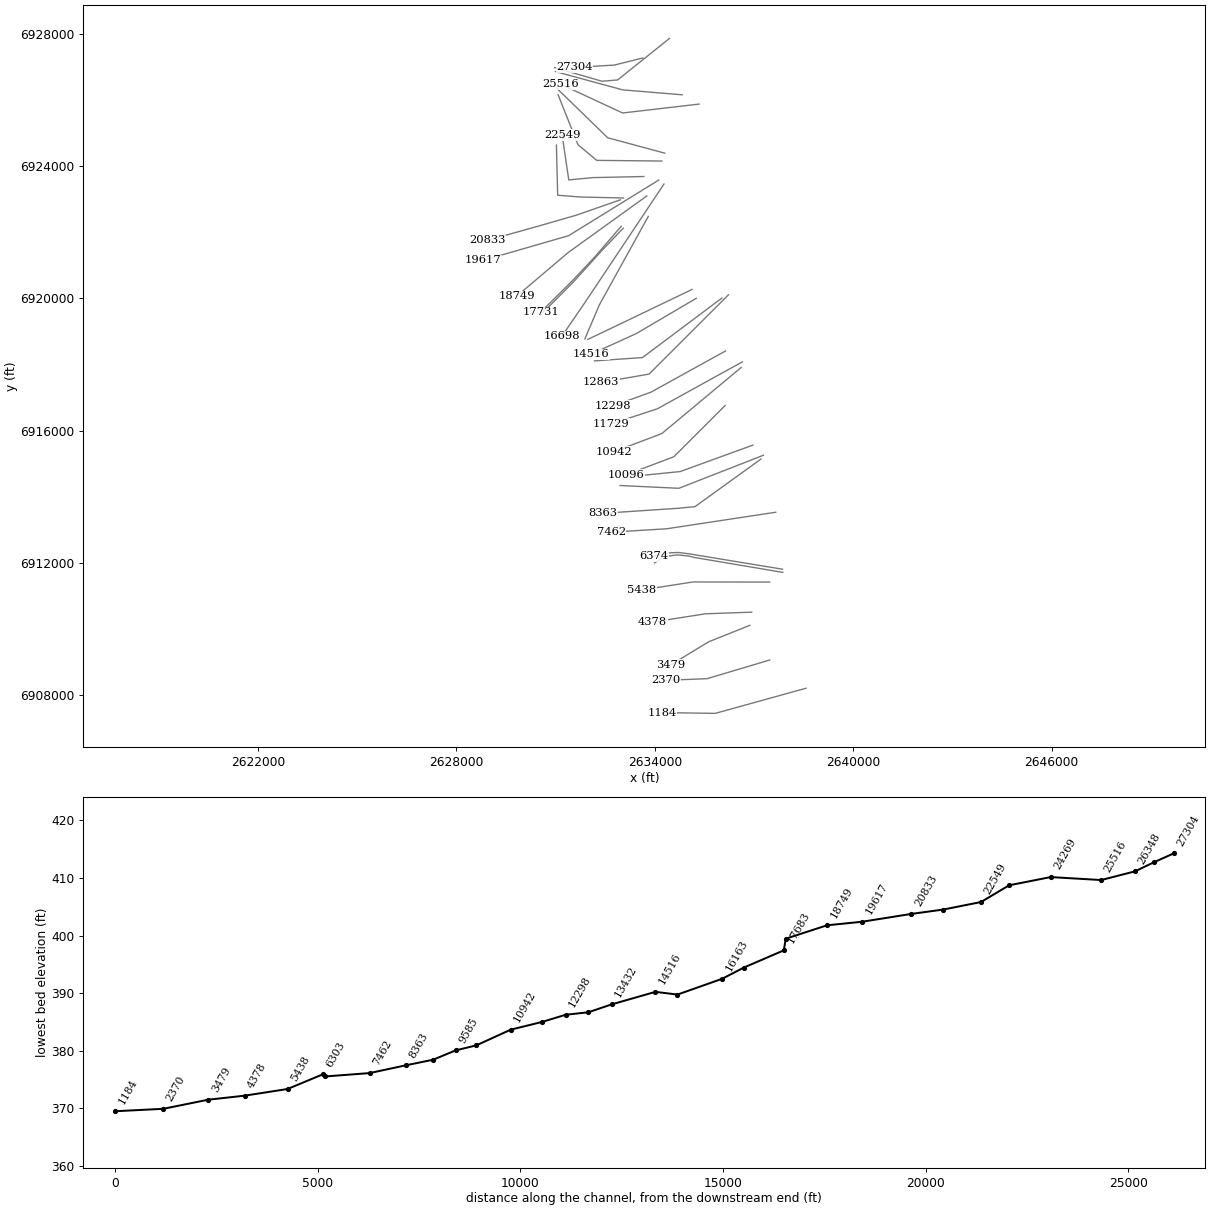
HEC-RAS study Little Brushy Creek.prj: Little Brushy Creek Base Level Engineering

--- Little Brushy Creek.g01 (geometry) --- (continued)

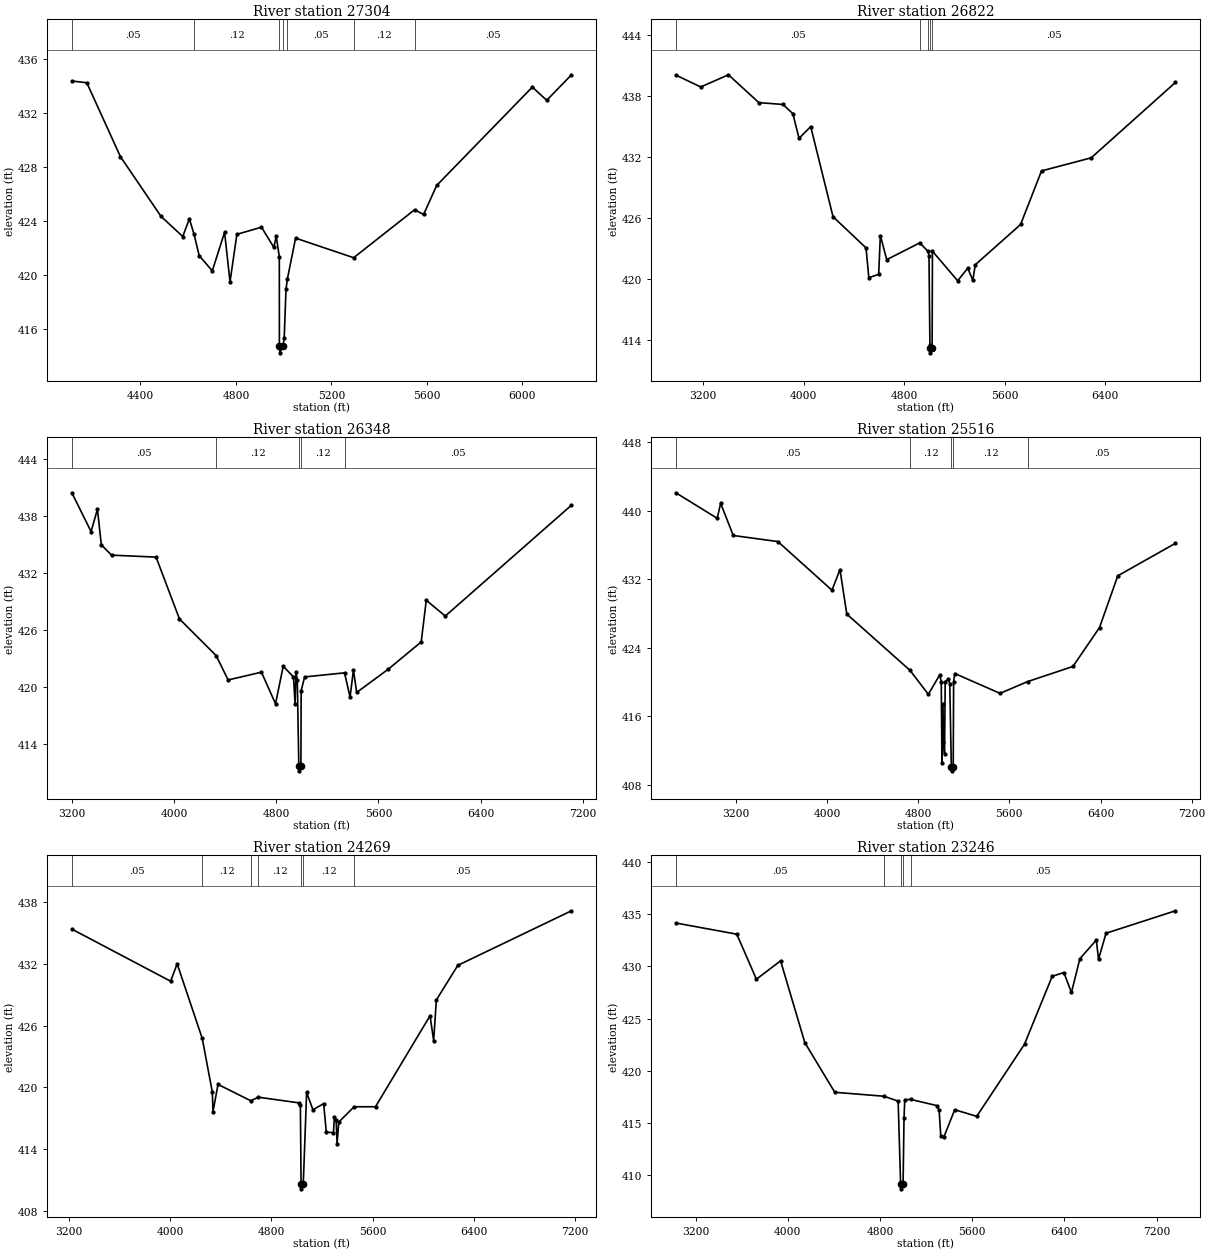
Type RM Length L Ch R = 1 ,27304   ,482,482,482
BEGIN DESCRIPTION:
Little Brushy Creek 39.0
END DESCRIPTION:
XS GIS Cut Line= 3
       2633636.8      6927275.49        2632776.        6927061.
      2631572.47      6926989.04
#Sta/Elev= 30
  4112.8  434.37  4175.5  434.24    4316  428.78  4486.4  424.35  4577.4  422.86
  4605.1  424.17  4624.8  423.02  4646.4  421.44  4701.1  420.32  4752.6  423.17
  4775.4  419.51  4804.1  423.02  4907.2  423.55  4958.7  422.06    4969  422.87
  4981.9  421.35  4982.2  414.75  4984.2  414.25  4997.1  414.75  5002.4  415.37
  5009.9  418.96  5015.9  419.74    5050  422.74  5293.2  421.29  5548.4  424.84
  5586.2  424.49  5641.1  426.64  6041.8  433.92  6101.9  432.94  6205.6  434.83
#Mann= 7 ,-1 , 0
  4112.8     .05       0  4624.8     .12       0  4982.2     .07       0
  4997.1     .12       0  5015.9     .05       0  5293.2     .12       0
  5548.4     .05       0
Bank Sta=4982.2,4997.1
XS Rating Curve= 0 ,0
Exp/Cntr=0.3,0.1

Type RM Length L Ch R = 1 ,26822   ,474,474,474
BEGIN DESCRIPTION:
Little Brushy Creek 38.0
END DESCRIPTION:
XS GIS Cut Line= 4
       2634445.8       6927869.6        2632876.        6926611.
      2632401.87      6926571.32      2630971.81      6926984.18
#Sta/Elev= 30
  2983.4  440.06  3181.4  438.89  3402.3  440.09  3643.9  437.35    3836  437.17
  3914.4  436.27    3964  433.84  4056.8  434.99  4234.5  426.12  4496.9  423.06
  4519.3  420.13  4597.7  420.45  4610.9  424.27  4661.8   421.9  4924.5  423.55
  4991.1  422.71    4998  422.28  5005.5  413.48  5008.1  413.23  5010.1  412.73
    5023  413.23  5025.6  422.73  5226.3  419.82  5306.5  421.06  5346.7  419.88
  5366.7   421.4  5727.1  425.36  5893.7  430.63  6289.2  431.92  6959.7  439.34
#Mann= 5 ,-1 , 0
  2983.4     .05       0  4924.5     .12       0  4991.1     .05       0
  5008.1     .03       0    5023     .05       0
Bank Sta=5008.1,5023
XS Rating Curve= 0 ,0
Exp/Cntr=0.3,0.1

Type RM Length L Ch R = 1 ,26348   ,832,832,832
BEGIN DESCRIPTION:
Little Brushy Creek 37.0
END DESCRIPTION:
XS GIS Cut Line= 3
      2634826.01        6926161.        2633026.        6926311.
      2630992.71      6926864.37
#Sta/Elev= 30
  3198.2  440.47  3348.7  436.38  3398.9  438.73    3429  434.98  3509.3  433.89
    3858  433.68  4041.1  427.16  4328.5  423.29  4422.4  420.72  4683.3  421.54
  4793.7   418.2  4853.9  422.17  4934.2  421.04  4946.7  418.21  4954.3  421.55
  4964.3  420.67  4976.1  411.63  4978.1  411.13  4992.6  411.63  4994.4  419.58
  5021.7  421.04  5334.2  421.47  5377.5  418.91  5403.9  421.77  5429.4   419.4
  5678.1  421.87  5934.7  424.73  5974.5  429.13  6123.2  427.46  7111.7  439.16
#Mann= 5 ,-1 , 0
  3198.2     .05       0  4328.5     .12       0  4976.1     .07       0
  4992.6     .12       0  5334.2     .05       0
Bank Sta=4976.1,4992.6
XS Rating Curve= 0 ,0
Exp/Cntr=0.3,0.1

Type RM Length L Ch R = 1 ,25516   ,1247,1247,1247
BEGIN DESCRIPTION:
Little Brushy Creek 35.0
END DESCRIPTION:
XS GIS Cut Line= 3
      2635336.46      6925880.01      2633026.07      6925610.97
      2631160.21      6926478.56
#Sta/Elev= 30
    2674  442.11  3036.9  439.13  3067.1  440.88  3177.8  437.12  3569.3  436.41
  4043.6  430.73  4114.1  433.13    4174  427.94  4728.4  421.37  4889.3  418.57
    4990  420.85  5002.8     420  5008.8  410.51  5014.3  417.41  5022.1  412.96
  5031.6  411.62  5037.2  420.04  5066.2  420.34  5077.3  419.79    5091  410.13
    5093  409.63  5107.6  410.13  5111.3  420.05  5121.4     421  5518.4  418.68
  5761.6  420.06    6158  421.82  6391.3  426.37  6551.5  432.41  7057.7  436.21
#Mann= 5 ,-1 , 0
    2674     .05       0  4728.4     .12       0    5091     .07       0
  5107.6     .12       0  5761.6     .05       0
Bank Sta=5091,5107.6
XS Rating Curve= 0 ,0
Exp/Cntr=0.3,0.1

Type RM Length L Ch R = 1 ,24269   ,1023,1023,1023
BEGIN DESCRIPTION:
Little Brushy Creek 34.0
END DESCRIPTION:
XS GIS Cut Line= 3
      2634299.96      6924395.63        2632576.        6924861.
      2631023.93      6926369.58
#Sta/Elev= 30
  3222.3  435.36  4003.3   430.3    4055  431.99  4253.4  424.74    4333  419.54
  4338.2  417.64  4378.1  420.28  4637.4  418.69  4696.3  419.04    5022  418.48
  5029.2  418.24  5034.7  410.64  5036.7  410.14    5052  410.64  5078.6   419.5
  5128.2  417.82  5213.1  418.41  5234.2  415.63  5290.8  415.61    5298  417.14
  5312.1  416.81  5319.1  414.54  5333.2  416.63  5454.2  418.11  5623.1  418.11
  6054.5  426.95  6082.8  424.53  6104.1  428.48  6273.9  431.84  7172.4  437.14
#Mann= 7 ,-1 , 0
  3222.3     .05       0  4253.4     .12       0  4637.4     .05       0
  4696.3     .12       0  5034.7     .07       0    5052     .12       0
  5454.2     .05       0
Bank Sta=5034.7,5052
XS Rating Curve= 0 ,0
Exp/Cntr=0.3,0.1

Type RM Length L Ch R = 1 ,23246   ,697,697,697
BEGIN DESCRIPTION:
Little Brushy Creek 33.0
END DESCRIPTION:
XS GIS Cut Line= 4
      2634214.92      6924157.44      2632243.12      6924177.48
       2631676.7       6924650.5      2631076.01      6926160.98
#Sta/Elev= 30
  3028.1  434.16    3557  433.09  3727.1  428.78  3937.1  430.54  4147.1  422.72
  4407.1  417.96  4835.3  417.58  4957.1  417.11  4978.4  409.22  4980.4  408.72
  4995.8  409.22    5000  409.24    5008  415.48  5014.5  417.24  5065.6  417.28
  5291.8  416.69  5312.6  416.27  5326.9  413.81  5355.5  413.72  5447.9  416.29
  5639.2  415.66  6053.5  422.56  6293.7  429.06    6395  429.42  6460.9  427.51
  6533.8  430.74  6676.8  432.53  6695.7  430.69  6760.9  433.18  7363.5  435.33
#Mann= 5 ,-1 , 0
  3028.1     .05       0  4835.3     .12       0  4978.4     .07       0
  4995.8     .12       0  5065.6     .05       0
Bank Sta=4978.4,4995.8
XS Rating Curve= 0 ,0
Exp/Cntr=0.3,0.1

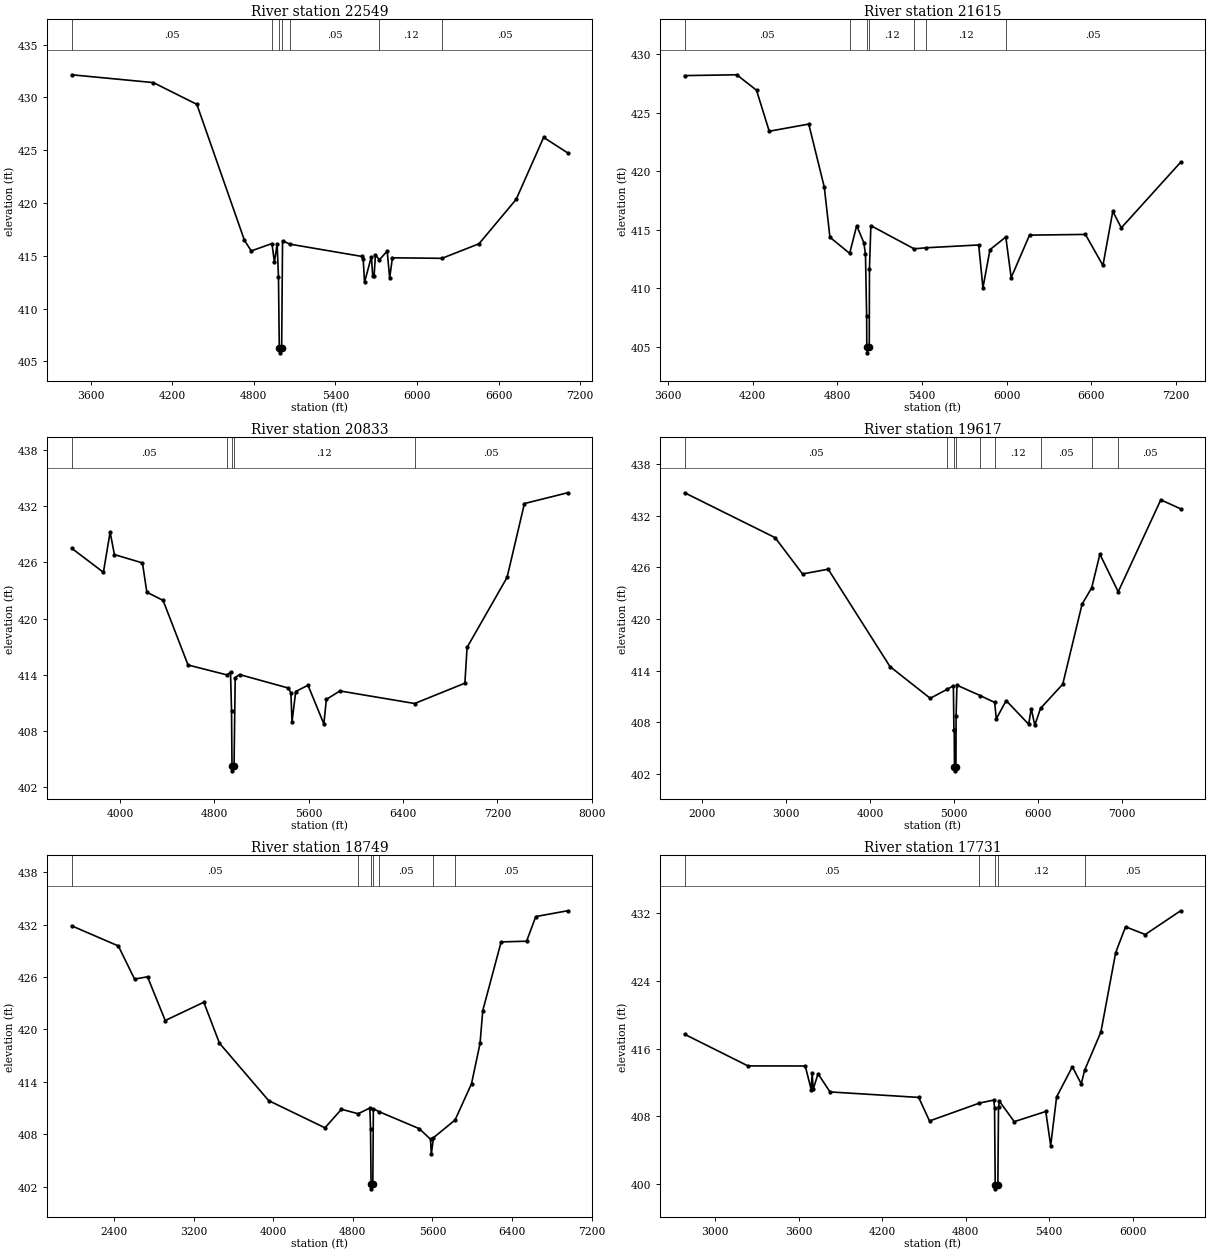
Type RM Length L Ch R = 1 ,22549   ,934,934,934
BEGIN DESCRIPTION:
Little Brushy Creek 32.0
END DESCRIPTION:
XS GIS Cut Line= 4
      2633666.32      6923688.69      2632127.17      6923655.91
      2631397.42      6923586.02      2631197.29      6924945.17
#Sta/Elev= 30
  3460.5  432.14  4061.2   431.4    4381  429.34  4731.1  416.46  4781.1  415.46
  4933.5  416.16  4951.2  414.38  4971.2  416.13  4981.2  413.01  4987.2  406.31
  4989.2  405.81  5004.6  406.31  5011.2  416.42  5065.9   416.1  5593.9  414.94
  5603.9  414.73    5614  412.48  5664.2  414.92  5674.2   413.1  5684.3  413.13
  5694.3  415.07  5723.8  414.63  5780.4  415.44  5798.8   412.9    5819  414.81
  6183.5  414.76  6455.8  416.14  6728.7  420.34  6930.8  426.21  7106.9  424.75
#Mann= 7 ,-1 , 0
  3460.5     .05       0  4933.5     .12       0  4987.2     .07       0
  5004.6     .12       0  5065.9     .05       0  5723.8     .12       0
  6183.5     .05       0
Bank Sta=4987.2,5004.6
XS Rating Curve= 0 ,0
Exp/Cntr=0.3,0.1

Type RM Length L Ch R = 1 ,21615   ,782,782,782
BEGIN DESCRIPTION:
Mapping XS 077dc401
END DESCRIPTION:
XS GIS Cut Line= 4
      2633054.93      6923039.75      2631777.39      6923067.16
      2631062.74      6923122.22      2631023.68      6924641.32
#Sta/Elev= 30
  3718.5  428.17  4087.5  428.24  4227.5  426.92  4317.6  423.42  4597.6  424.03
  4707.7  418.65  4747.7  414.37  4887.5  412.99  4937.4  415.36  4987.7  413.91
  4999.5  412.95  5007.8  407.67  5009.1     405  5011.1   404.5  5026.5     405
  5027.8   411.7  5037.8  415.36  5344.1  413.38  5428.2  413.47  5801.9  413.71
  5831.9  410.05  5881.9  413.31  5993.9  414.39    6032  410.92    6162  414.55
    6558  414.61  6682.2  411.96  6752.2  416.58  6812.2  415.17  7232.7  420.77
#Mann= 7 ,-1 , 0
  3718.5     .05       0  4887.5     .12       0  5009.1     .07       0
  5026.5     .12       0  5344.1     .05       0  5428.2     .12       0
  5993.9     .05       0
Bank Sta=5009.1,5026.5
XS Rating Curve= 0 ,0
Exp/Cntr=0.3,0.1

Type RM Length L Ch R = 1 ,20833   ,1216,1216,1216
BEGIN DESCRIPTION:
Mapping XS 62dc8824
END DESCRIPTION:
XS GIS Cut Line= 4
      2632957.93      6922983.82      2631624.61      6922518.55
      2630457.95      6922181.75      2628937.11      6921758.14
#Sta/Elev= 30
  3589.7  427.52    3859  424.95  3915.9  429.24  3952.2  426.84  4190.1  425.95
  4227.2  422.82  4364.9  421.95  4576.7  415.05  4907.4  413.99  4936.8  414.28
  4945.5  410.11  4949.3  404.25  4951.3  403.75  4966.7  404.25  4976.6  413.71
  5013.5  414.03  5427.2  412.59  5448.4   412.1  5458.4  408.99  5489.6  412.22
  5593.7  412.89    5728  408.77  5749.8  411.38  5864.3  412.28  6498.3  410.94
  6924.1  413.11  6942.7  416.93  7281.7   424.4  7428.9  432.29  7794.9  433.44
#Mann= 5 ,-1 , 0
  3589.7     .05       0  4907.4     .12       0  4949.3     .07       0
  4966.7     .12       0  6498.3     .05       0
Bank Sta=4949.3,4966.7
XS Rating Curve= 0 ,0
Exp/Cntr=0.3,0.1

Type RM Length L Ch R = 1 ,19617   ,868,868,868
BEGIN DESCRIPTION:
Little Brushy Creek 31.0
END DESCRIPTION:
XS GIS Cut Line= 3
      2634117.67      6923581.05      2631390.58      6921898.05
      2628798.24      6921149.34
#Sta/Elev= 30
  1795.4  434.66  2871.9  429.45  3198.3  425.24  3503.4  425.79    4239  414.49
  4717.9  410.81  4915.8  411.83  4993.6  412.26  4999.8  407.09  5003.7  407.09
  5006.5  402.89  5008.5  402.39  5023.9  402.89  5025.6  408.71    5036  412.33
  5311.4  411.13  5484.9  410.33  5504.4  408.43  5622.1  410.54  5889.5   407.8
  5920.7  409.61  5962.4  407.67    6031  409.64  6295.5  412.45  6525.3  421.73
    6640  423.64  6737.6  427.53  6955.5  423.17  7462.3  433.84  7698.3   432.8
#Mann= 9 ,-1 , 0
  1795.4     .05       0  4915.8     .12       0  5006.5     .07       0
  5023.9     .12       0  5311.4     .05       0  5484.9     .12       0
    6031     .05       0    6640     .12       0  6955.5     .05       0
Bank Sta=5006.5,5023.9
XS Rating Curve= 0 ,0
Exp/Cntr=0.3,0.1

Type RM Length L Ch R = 1 ,18749   ,1018,1018,1018
BEGIN DESCRIPTION:
Mapping XS f1ca0d5e
END DESCRIPTION:
XS GIS Cut Line= 3
       2633758.3      6923102.47      2631372.88      6921383.71
      2629815.57      6920060.78
#Sta/Elev= 30
  1975.1  431.85  2444.1  429.55  2607.3  425.76  2737.4  426.02  2915.4  421.02
  3303.1  423.11  3460.2  418.43  3954.8  411.86  4520.5  408.75  4686.1  410.87
  4853.9  410.36  4971.8  411.01  4978.4  408.65    4984  402.27    4986  401.77
  5001.4  402.27    5007  410.93  5065.2  410.59  5468.3  408.65  5581.4  407.44
  5589.1   405.7  5610.9  407.62  5827.9  409.64  5993.3  413.79  6078.9   418.4
  6106.4  422.16  6290.9  430.01  6546.8  430.09  6639.1  432.91  6958.6  433.57
#Mann= 7 ,-1 , 0
  1975.1     .05       0  4853.9     .12       0    4984     .07       0
  5001.4     .12       0  5065.2     .05       0  5610.9     .12       0
  5827.9     .05       0
Bank Sta=4984,5001.4
XS Rating Curve= 0 ,0
Exp/Cntr=0.3,0.1

Type RM Length L Ch R = 1 ,17731   ,48,48,48
BEGIN DESCRIPTION:
Mapping XS 305a4ef6
END DESCRIPTION:
XS GIS Cut Line= 4
      2632983.99      6922184.06      2632185.38      6921256.98
      2631504.37      6920532.81      2630550.45      6919587.32
#Sta/Elev= 30
  2782.3  417.68  3236.5  413.95  3647.9  413.94  3690.7  411.16  3697.3  413.12
  3704.9   411.2    3740  413.02  3825.6  410.88  4462.5  410.23  4540.2  407.45
  4897.9  409.56  5002.4  409.92  5007.2  408.95  5011.9  399.94  5013.9  399.44
  5030.9  399.94  5035.5  409.07  5042.5  409.77  5148.6  407.37  5374.9  408.57
  5410.2  404.55  5452.7  410.29  5565.8  413.85  5629.5  411.83  5654.4  413.46
  5770.9  417.96  5876.9  427.33  5947.7  430.37  6089.1  429.46  6343.1  432.26
#Mann= 5 ,-1 , 0
  2782.3     .05       0  4897.9     .12       0  5011.9     .08       0
  5030.9     .12       0  5654.4     .05       0
Bank Sta=5011.9,5030.9
XS Rating Curve= 0 ,0
Exp/Cntr=0.3,0.1

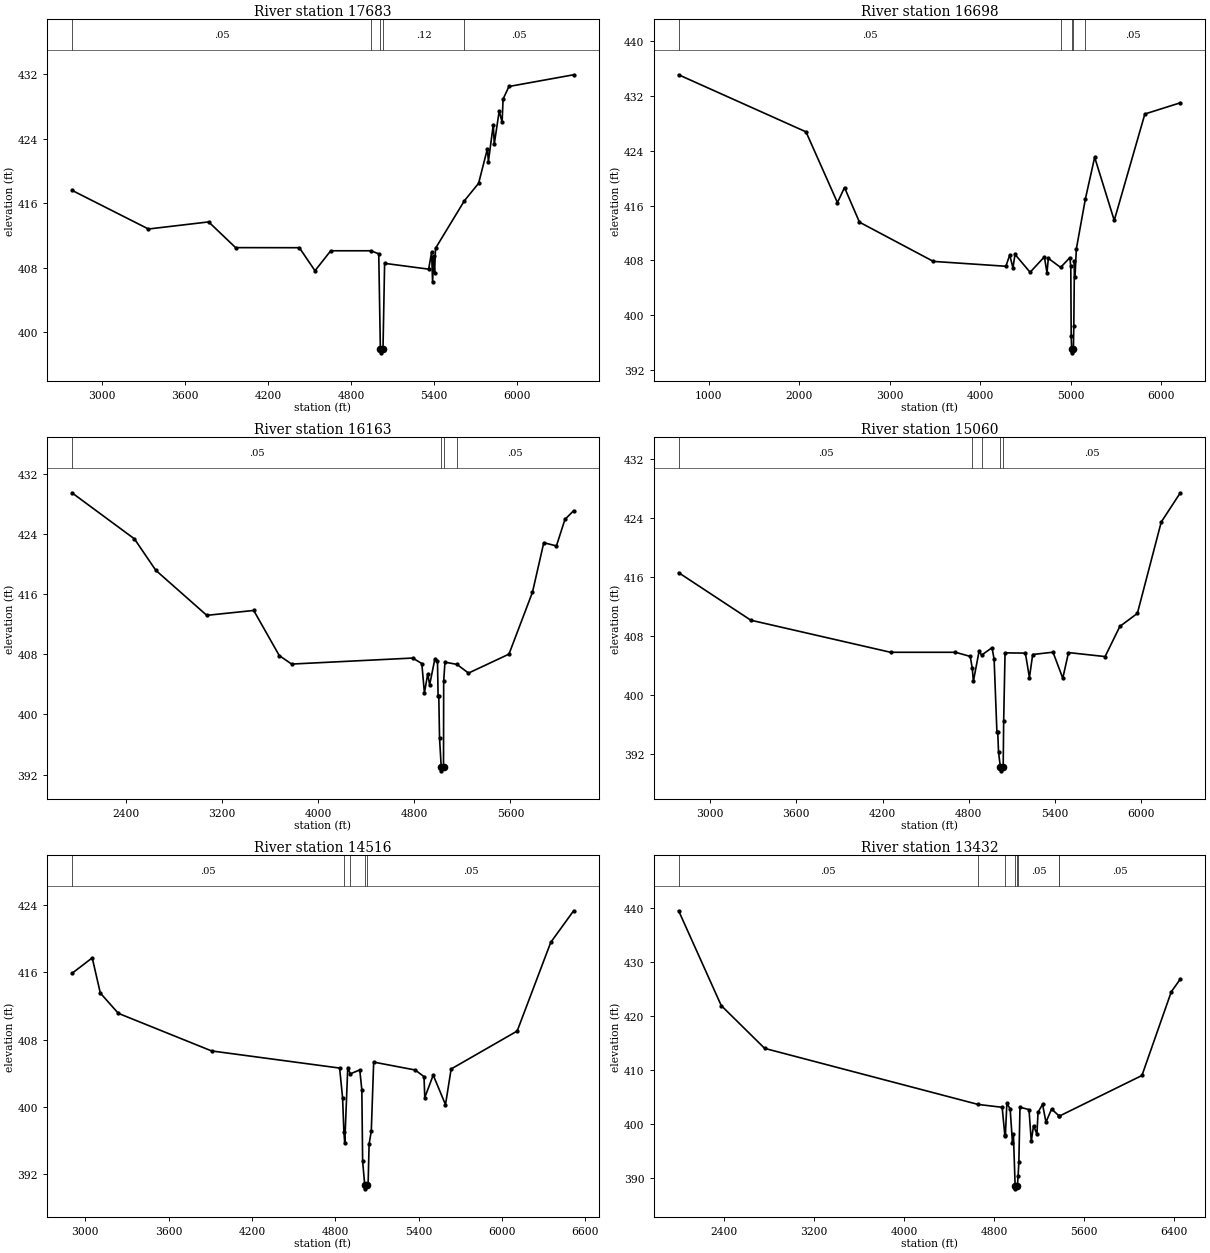
Type RM Length L Ch R = 1 ,17683   ,985,985,985
BEGIN DESCRIPTION:
Mapping XS 2e1717b2
END DESCRIPTION:
XS GIS Cut Line= 4
        2633043.      6922125.01      2632362.46      6921409.76
      2631546.92      6920508.27      2630546.47      6919500.02
#Sta/Elev= 30
  2784.7  417.58  3337.2  412.78    3772  413.66  3966.9  410.47  4427.2  410.46
    4540   407.6  4653.6  410.08  4944.4  410.08  5000.5   409.7  5012.2  397.92
  5014.2  397.42  5031.2  397.92  5042.9  408.52  5361.1   407.8  5382.3   409.9
  5389.4  406.16  5396.5  409.42  5403.6  407.29  5410.6  410.39  5619.3  416.29
  5721.7  418.45  5785.4  422.74  5792.4  421.14  5827.8  425.72  5834.9  423.32
  5870.3   427.4  5891.4  426.04  5898.5   428.9    5941  430.46    6408  431.91
#Mann= 5 ,-1 , 0
  2784.7     .05       0  4944.4     .12       0  5012.2     .07       0
  5031.2     .12       0  5619.3     .05       0
Bank Sta=5012.2,5031.2
XS Rating Curve= 0 ,0
Exp/Cntr=0.3,0.1

Type RM Length L Ch R = 1 ,16698   ,535,535,535
BEGIN DESCRIPTION:
Little Brushy Creek 28.0
END DESCRIPTION:
XS GIS Cut Line= 3
      2634276.01      6923461.01        2631876.        6919861.
      2631191.47       6918860.3
#Sta/Elev= 30
   669.4  435.13  2075.6  426.78  2422.6  416.42  2500.7  418.63    2666  413.56
  3481.7  407.82  4282.5  407.11  4324.5  408.75  4360.6  406.88  4383.1  408.85
  4549.9  406.23  4707.6  408.49  4736.2  406.15  4751.2  408.27  4886.7  406.94
  4988.6  408.37  4999.1  407.08  5003.5  396.92  5008.9  394.94  5010.9  394.44
  5027.9  394.94  5032.4  398.43  5039.4  407.86  5045.5  405.52  5060.4  409.65
  5160.7     417  5262.6  423.06  5478.9  413.82  5816.8  429.39  6208.5  431.03
#Mann= 5 ,-1 , 0
   669.4     .05       0  4886.7     .12       0  5008.9     .07       0
  5027.9     .12       0  5160.7     .05       0
Bank Sta=5008.9,5027.9
XS Rating Curve= 0 ,0
Exp/Cntr=0.3,0.1

Type RM Length L Ch R = 1 ,16163   ,1103,1103,1103
BEGIN DESCRIPTION:
Little Brushy Creek 27.0
END DESCRIPTION:
XS GIS Cut Line= 3
      2633802.33      6922482.03        2632326.        6919811.
      2631884.06      6918775.76
#Sta/Elev= 30
  1948.3  429.47  2468.6  423.34  2646.5  419.16  3071.1  413.17  3461.8  413.82
  3674.8  407.82  3777.6  406.69    4786  407.49  4861.6  406.76  4883.3  402.85
  4910.8  405.39  4926.9  403.93  4970.4  407.38  4992.1  407.08  4997.3  402.48
  5002.9  402.48  5009.3  396.84  5023.3  392.99  5025.3  392.49  5042.3  392.99
  5043.7  404.41  5054.5  406.94  5153.9  406.65  5250.3  405.49  5587.3  408.01
    5783  416.24  5877.2  422.83  5982.5   422.4  6053.3  425.92  6125.8  427.09
#Mann= 4 ,-1 , 0
  1948.3     .05       0  5023.3     .05       0  5042.3     .05       0
  5153.9     .05       0
Bank Sta=5023.3,5042.3
XS Rating Curve= 0 ,0
Exp/Cntr=0.3,0.1

Type RM Length L Ch R = 1 ,15060   ,544,544,544
BEGIN DESCRIPTION:
Little Brushy Creek 25.0
END DESCRIPTION:
XS GIS Cut Line= 3
      2635126.14      6920272.84        2633126.        6919311.
      2631976.04      6918761.02
#Sta/Elev= 30
  2780.1  416.56  3282.8  410.13    4256  405.79  4708.2  405.79  4810.9  405.23
  4825.3  403.61    4833  401.88  4872.2   405.9  4890.2  405.41  4962.8  406.41
  4977.3  404.84  4996.7  395.03  5002.3  395.03  5008.1  392.27  5020.9  390.25
  5022.9  389.75  5040.5  390.25  5043.8  396.45  5053.4  405.71    5195  405.68
  5223.2  402.36  5245.9  405.49  5387.5   405.8  5455.5  402.28  5495.3  405.75
  5750.2  405.21    5853  409.29    5975  411.05  6141.2  423.41  6274.2  427.37
#Mann= 5 ,-1 , 0
  2780.1     .05       0  4825.3     .12       0  4890.2     .05       0
  5020.9     .03       0  5040.5     .05       0
Bank Sta=5020.9,5040.5
XS Rating Curve= 0 ,0
Exp/Cntr=0.3,0.1

Type RM Length L Ch R = 1 ,14516   ,1084,1084,1084
BEGIN DESCRIPTION:
Little Brushy Creek 24.0
END DESCRIPTION:
XS GIS Cut Line= 3
      2635251.96      6920003.72      2633445.63      6918940.32
       2632066.2      6918311.01
#Sta/Elev= 30
  2903.9  415.89  3050.1  417.74  3108.1  413.55    3238  411.13  3909.6  406.65
  4831.2  404.61  4852.7  401.05  4862.1  396.95  4868.3  395.63  4889.8  404.67
  4908.2  403.92  4976.4  404.39  4991.3  402.01  4996.9  393.51  5011.8  390.72
  5013.8  390.22  5031.4  390.72  5036.3  390.73  5043.6  395.56  5059.3  397.11
  5076.5  405.32  5375.3  404.38  5438.9  403.59  5444.4   401.1  5505.2  403.77
  5593.6  400.25  5634.2   404.5  6109.7  409.02  6351.5  419.59  6516.2  423.35
#Mann= 5 ,-1 , 0
  2903.9     .05       0  4862.1     .12       0  4908.2     .05       0
  5011.8     .03       0  5031.4     .05       0
Bank Sta=5011.8,5031.4
XS Rating Curve= 0 ,0
Exp/Cntr=0.3,0.1

Type RM Length L Ch R = 1 ,13432   ,569,569,569
BEGIN DESCRIPTION:
Little Brushy Creek 22.0
END DESCRIPTION:
XS GIS Cut Line= 3
      2636026.03      6920011.02        2633626.        6918211.
      2632175.98        6918111.
#Sta/Elev= 30
  2000.5  439.43  2378.7  421.91  2764.1     414  4658.4  403.64  4872.4  403.11
  4895.6  398.08  4900.5  397.75  4914.1  403.82  4943.2  402.84  4964.1  396.52
  4972.4  398.12  4987.6  388.54  4989.6  388.04  5007.2  388.54    5014   390.4
  5020.6  392.98  5030.6  403.13  5110.8  402.68  5130.8   396.8  5150.9  399.72
    5181  398.15    5191   402.2  5231.1  403.66  5261.2  400.37  5311.3  402.79
  5374.9  401.57  5376.9  401.45  6113.2  408.99  6373.8  424.47    6454  426.81
#Mann= 8 ,-1 , 0
  2000.5     .05       0  4658.4     .12       0  4895.6     .05       0
  4987.6     .07       0  5007.2     .05       0    5014     .05       0
  5374.9     .12       0  5376.9     .05       0
Bank Sta=4987.6,5007.2
XS Rating Curve= 0 ,0
Exp/Cntr=0.3,0.1

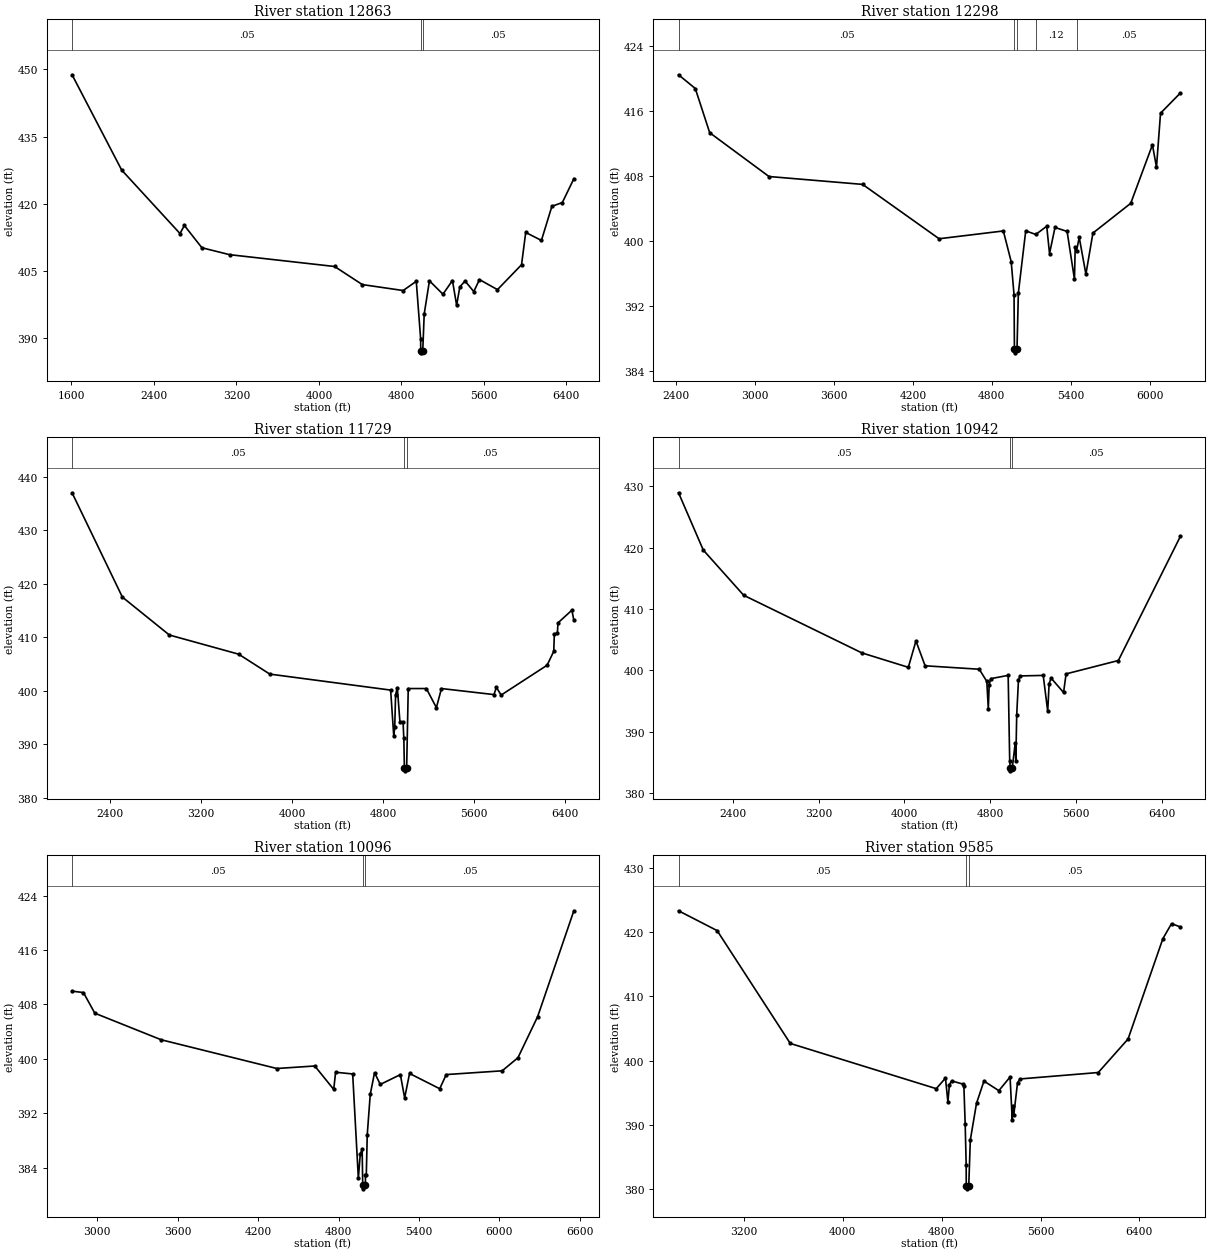
Type RM Length L Ch R = 1 ,12863   ,565,565,565
BEGIN DESCRIPTION:
Little Brushy Creek 21.0
END DESCRIPTION:
XS GIS Cut Line= 3
      2636226.03      6920111.03        2633826.        6917711.
      2632375.95      6917460.99
#Sta/Elev= 30
  1606.4   448.8  2087.3  427.52    2653  413.33  2695.4  415.13  2865.1  410.16
  3133.8  408.61    4152  405.97  4420.7  401.93  4816.7   400.6    4944  402.66
  4986.4  389.77  4987.2  387.18  4989.2  386.68  5006.9  387.18  5020.9  395.36
  5071.6  402.77  5202.5  399.78  5294.8  402.84  5335.4  397.28  5365.9  401.39
  5416.6  402.73  5501.8  400.36  5556.6  403.05  5731.2   400.8  5964.6  406.36
  6005.2  413.58  6157.4  411.79  6258.9  419.41  6360.3  420.26    6472  425.58
#Mann= 3 ,-1 , 0
  1606.4     .05       0  4987.2     .03       0  5006.9     .05       0
Bank Sta=4987.2,5006.9
XS Rating Curve= 0 ,0
Exp/Cntr=0.3,0.1

Type RM Length L Ch R = 1 ,12298   ,569,569,569
BEGIN DESCRIPTION:
Little Brushy Creek 20.0
END DESCRIPTION:
XS GIS Cut Line= 3
      2636137.43      6918410.86        2633876.        6917161.
      2632721.59      6916744.17
#Sta/Elev= 30
  2420.3  420.46  2547.6  418.77    2657  413.33  3107.2  407.94  3818.5  406.97
  4399.3  400.28  4887.3  401.24  4946.9  397.46  4968.6  393.37  4971.4  386.74
  4973.4  386.24  4991.1  386.74  5001.3  393.61  5057.3  401.25  5133.7  400.81
  5216.8  401.82    5238  398.46  5279.6  401.67  5371.6  401.18  5427.6  395.28
  5432.9  399.22    5443  398.78  5463.6  400.45  5514.3  395.92  5567.6  400.98
  5854.7  404.64  6019.7  411.84  6050.4  409.08  6081.1  415.73  6231.5  418.21
#Mann= 5 ,-1 , 0
  2420.3     .05       0  4971.4     .05       0  4991.1     .05       0
  5133.7     .12       0    5443     .05       0
Bank Sta=4971.4,4991.1
XS Rating Curve= 0 ,0
Exp/Cntr=0.3,0.1

Type RM Length L Ch R = 1 ,11729   ,787,787,787
BEGIN DESCRIPTION:
Little Brushy Creek 19.0
END DESCRIPTION:
XS GIS Cut Line= 3
       2636645.2      6918080.98        2634076.        6916661.
      2632679.57      6916202.09
#Sta/Elev= 30
  2069.1  437.02  2510.8  417.51  2923.2  410.42  3531.4  406.84  3804.9  403.11
    4866  400.12  4893.5  391.46  4901.8  393.18  4909.5  399.26  4924.6  400.58
  4947.3  394.23  4974.8   394.2  4981.7  391.08  4986.7  385.52  4988.7  385.02
  5006.4  385.52  5020.5  400.41  5179.5  400.41  5267.7  396.84    5312  400.41
    5773  399.28  5794.3  400.62  5836.2  399.19  6239.6  404.77  6297.9  407.37
  6303.2  410.64  6329.7  410.74    6335  412.69    6457  415.06  6474.5  413.18
#Mann= 3 ,-1 , 0
  2069.1     .05       0  4986.7     .03       0  5006.4     .05       0
Bank Sta=4986.7,5006.4
XS Rating Curve= 0 ,0
Exp/Cntr=0.3,0.1

Type RM Length L Ch R = 1 ,10942   ,846,846,846
BEGIN DESCRIPTION:
Little Brushy Creek 18.0
END DESCRIPTION:
XS GIS Cut Line= 3
       2636610.7      6917911.33      2634210.72      6915911.35
      2632760.89      6915361.41
#Sta/Elev= 30
  1895.9  428.94  2126.4  419.61  2502.6  412.25  3603.8  402.86  4036.8  400.51
  4107.6   404.8    4193  400.76  4697.2   400.2  4767.5  398.23  4781.8  393.76
  4789.7  397.65    4804  398.66  4966.7   399.2    4981  385.31  4985.4  384.15
  4987.4  383.65  5005.3  384.15  5032.7  388.22  5038.1   385.3  5046.4  392.78
  5062.8  398.47  5078.5  399.11  5293.3  399.19  5335.2  393.35  5348.2  397.85
  5367.3  398.74  5482.9  396.41  5506.3  399.44  5993.3  401.62  6570.6  421.82
#Mann= 3 ,-1 , 0
  1895.9     .05       0  4985.4     .03       0  5005.3     .05       0
Bank Sta=4985.4,5005.3
XS Rating Curve= 0 ,0
Exp/Cntr=0.3,0.1

Type RM Length L Ch R = 1 ,10096   ,511,511,511
BEGIN DESCRIPTION:
Little Brushy Creek 16.0
END DESCRIPTION:
XS GIS Cut Line= 3
      2636125.98      6916760.98        2634576.        6915211.
      2633126.01      6914661.01
#Sta/Elev= 30
  2812.6  409.96  2897.4  409.75  2982.3  406.72  3477.3  402.82  4339.9   398.6
  4622.8  398.97  4764.2  395.53  4778.3  398.05  4905.6   397.8    4948  382.48
  4962.2  386.02  4976.3  386.77  4980.5  381.43  4982.5  380.93  5000.5  381.43
  5001.1  383.02  5007.3  383.02  5014.3  388.86  5036.7  394.81  5068.8  397.99
  5111.6  396.26  5261.3   397.7  5293.4  394.28  5329.8  397.87  5554.9  395.63
  5603.5  397.71  6020.7  398.26  6138.3  400.18  6285.1  406.21  6555.4  421.76
#Mann= 3 ,-1 , 0
  2812.6     .05       0  4980.5     .03       0  5000.5     .05       0
Bank Sta=4980.5,5000.5
XS Rating Curve= 0 ,0
Exp/Cntr=0.3,0.1

Type RM Length L Ch R = 1 ,9585    ,555,555,555
BEGIN DESCRIPTION:
Little Brushy Creek 15.0
END DESCRIPTION:
XS GIS Cut Line= 3
      2636965.75       6915562.2      2634765.78      6914762.21
       2633055.2      6914590.31
#Sta/Elev= 30
  2670.8  423.28    2983   420.2    3575  402.66  4756.1  395.63  4830.6  397.27
  4850.4  393.56  4862.5  396.25    4881  396.83  4972.8  396.34  4979.6  396.01
  4990.2  390.07  4998.1  383.82  4998.8  380.56  5000.8  380.06  5019.1  380.56
  5031.6  387.64  5081.8  393.36  5142.1  396.81  5262.7  395.32  5353.2  397.44
    5371  390.75  5376.1  393.01  5383.4  391.54  5413.5  396.54  5433.6  397.14
  6066.8  398.14    6308  403.35  6589.4  418.93  6659.7  421.28  6730.9  420.77
#Mann= 3 ,-1 , 0
  2670.8     .05       0  4998.8     .04       0  5019.1     .05       0
Bank Sta=4998.8,5019.1
XS Rating Curve= 0 ,0
Exp/Cntr=0.3,0.1

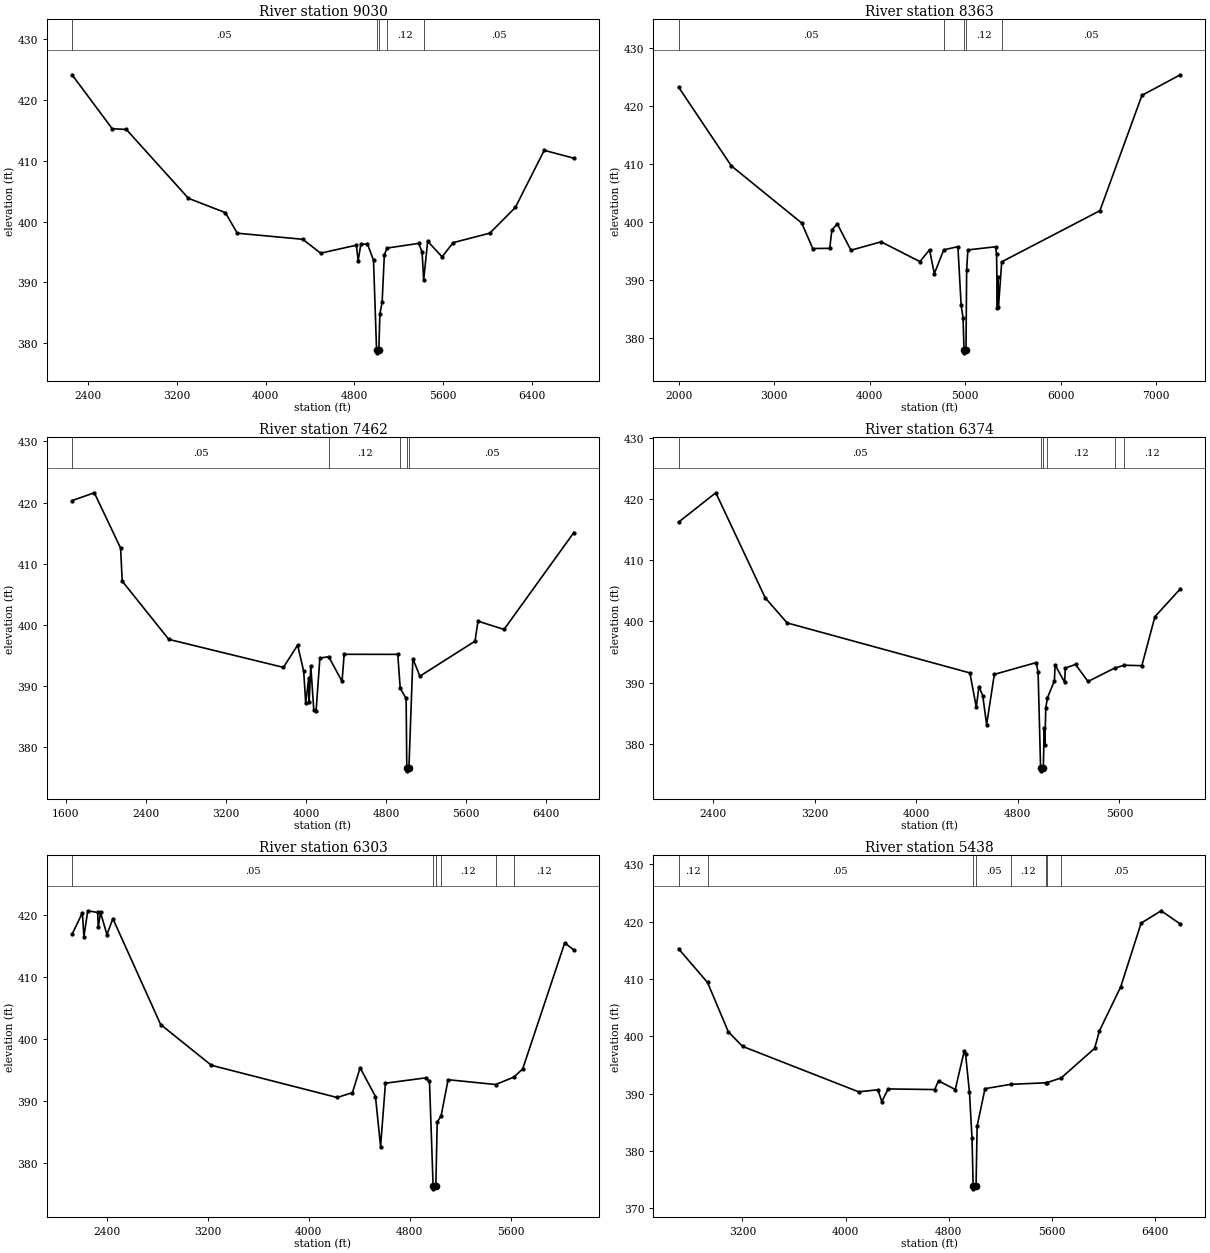
Type RM Length L Ch R = 1 ,9030    ,667,667,667
BEGIN DESCRIPTION:
Little Brushy Creek 14.0
END DESCRIPTION:
XS GIS Cut Line= 3
      2637283.21      6915255.45      2634726.74      6914255.96
      2632949.11      6914339.58
#Sta/Elev= 30
  2255.1  424.11  2617.2  415.25  2744.3  415.13  3304.3  403.82  3637.2  401.47
  3744.6  398.09  4335.1  397.09  4496.2  394.81  4818.3  396.12  4834.7  393.59
  4859.2  396.28  4918.9   396.3  4973.2  393.66  5000.5  378.94  5002.5  378.44
  5021.1  378.94  5030.8  384.88  5050.8  386.73  5070.8  394.56  5095.6  395.65
  5381.2  396.42  5411.2  394.96  5425.5  390.42  5461.3  396.77  5591.4  394.21
  5691.5  396.54  6021.9   398.1  6252.1  402.32  6512.4   411.7  6779.6  410.41
#Mann= 5 ,-1 , 0
  2255.1     .05       0  5000.5     .03       0  5021.1     .05       0
  5095.6     .12       0  5425.5     .05       0
Bank Sta=5000.5,5021.1
XS Rating Curve= 0 ,0
Exp/Cntr=0.3,0.1

Type RM Length L Ch R = 1 ,8363    ,901,901,901
BEGIN DESCRIPTION:
Mapping XS 1e21c8c4
END DESCRIPTION:
XS GIS Cut Line= 4
      2637208.54      6915140.39        2635212.      6913699.41
      2634656.44      6913647.33      2632425.54      6913499.76
#Sta/Elev= 30
  1998.6  423.23  2551.7  409.67  3289.1  399.82  3404.4  395.44  3582.3  395.47
    3605  398.66    3662  399.66  3804.3  395.15  4120.8  396.59  4527.1  393.18
  4627.6  395.22  4677.8  391.11  4776.8  395.21  4924.9  395.76    4959  385.63
  4979.1   383.5  4988.8  377.98  4990.9  377.48  5009.5  377.98  5016.5  391.78
  5029.3   395.2  5319.9  395.74  5329.9  394.41  5338.4  385.18  5343.4  390.54
    5350   385.4  5383.8  393.15  6412.3  401.95  6852.6  421.81  7254.6  425.35
#Mann= 5 ,-1 , 0
  1998.6     .05       0  4776.8     .12       0  4988.8     .07       0
  5009.5     .12       0  5383.8     .05       0
Bank Sta=4988.8,5009.5
XS Rating Curve= 0 ,0
Exp/Cntr=0.3,0.1

Type RM Length L Ch R = 1 ,7462    ,1088,1088,1088
BEGIN DESCRIPTION:
Little Brushy Creek 13.0
END DESCRIPTION:
XS GIS Cut Line= 3
      2637655.89      6913531.29      2634355.61      6913030.93
      2632679.26      6912928.09
#Sta/Elev= 30
    1662  420.32  1884.4   421.6  2147.4  412.55  2163.4  407.15  2629.5  397.62
  3775.8  393.04  3917.4  396.68  3978.1  392.41  3998.3  387.16  4027.9  391.26
  4032.9  387.36  4048.9  393.32  4079.2  386.02  4101.7  385.84  4139.9  394.56
    4228  394.79  4361.6  390.75  4382.6  395.18  4918.7  395.17  4943.3  389.62
  5002.3  387.96    5009  376.62  5011.1  376.12  5030.3  376.62  5069.7  394.47
  5139.9   391.6  5690.9  397.33    5721   400.6  5981.4  399.25  6679.5   415.1
#Mann= 5 ,-1 , 0
    1662     .05       0    4228     .12       0  4943.3     .05       0
    5009     .03       0  5030.3     .05       0
Bank Sta=5009,5030.3
XS Rating Curve= 0 ,0
Exp/Cntr=0.3,0.1

Type RM Length L Ch R = 1 ,6374    ,71,71,71
BEGIN DESCRIPTION:
Little Brushy Creek 12.0
END DESCRIPTION:
XS GIS Cut Line= 5
      2637859.86      6911808.19      2635025.92       6912274.8
      2634710.55      6912314.27      2634394.58      6912300.38
       2633960.8      6912199.74
#Sta/Elev= 30
  2127.9  416.26  2421.4  421.07  2810.8  403.86  2983.1  399.76  4422.2  391.57
  4472.9  385.94  4493.2  389.34  4523.6  387.84    4554  383.11  4614.8  391.34
    4945  393.27  4959.4  391.67    4979  376.04  4981.1  375.54  5000.6  376.04
  5007.3   382.5  5012.4  379.84  5020.1  385.86  5032.2  387.45  5087.9  390.27
  5092.9  392.88  5168.5  390.05  5173.5  392.37  5254.1  392.96  5352.4  390.17
  5563.3  392.38  5639.1  392.83  5776.4  392.76  5879.4  400.79  6079.4  405.34
#Mann= 6 ,-1 , 0
  2127.9     .05       0    4979     .03       0  5000.6     .05       0
  5032.2     .12       0  5563.3     .05       0  5639.1     .12       0
Bank Sta=4979,5000.6
XS Rating Curve= 0 ,0
Exp/Cntr=0.3,0.1

Type RM Length L Ch R = 1 ,6303    ,865,865,865
BEGIN DESCRIPTION:
Little Brushy Creek 11.0
END DESCRIPTION:
XS GIS Cut Line= 6
      2637868.58      6911711.83      2635195.56      6912163.01
      2635034.15      6912204.95        2634691.      6912241.14
      2634342.49      6912199.69      2633989.67      6911999.06
#Sta/Elev= 30
  2122.4  416.82  2204.3  420.29  2216.3  416.44  2246.7  420.61  2325.2  420.34
  2330.3  417.97  2348.1  420.34  2398.8  416.79  2446.2  419.34  2824.8  402.32
  3227.2  395.76  4224.3  390.58    4346  391.36  4406.8  395.36  4528.5  390.74
  4569.1  382.68  4607.7  392.88  4927.8  393.74  4956.8  393.19  4985.7  376.39
  4987.8  375.89  5007.3  376.39  5018.3  386.64  5049.1  387.62  5104.5  393.44
  5481.6  392.67  5625.3  393.85    5696  395.17  6029.3  415.43  6101.9  414.31
#Mann= 6 ,-1 , 0
  2122.4     .05       0  4985.7     .03       0  5007.3     .05       0
  5049.1     .12       0  5481.6     .05       0  5625.3     .12       0
Bank Sta=4985.7,5007.3
XS Rating Curve= 0 ,0
Exp/Cntr=0.3,0.1

Type RM Length L Ch R = 1 ,5438    ,1060,1060,1060
BEGIN DESCRIPTION:
Little Brushy Creek 10.0
END DESCRIPTION:
XS GIS Cut Line= 3
      2637472.38      6911418.54      2635151.74      6911421.87
      2633599.23      6911179.24
#Sta/Elev= 30
    2704  415.27  2929.1  409.38  3090.4  400.76  3200.4  398.23  4100.4   390.3
  4250.4  390.65  4280.4  388.59  4330.4   390.8  4690.4  390.69  4720.4  392.21
  4850.4   390.7  4920.4  397.46  4930.4  396.86  4960.4  390.23  4980.4  382.15
  4989.2  373.86  4991.4  373.36  5011.6  373.86    5020  384.32  5081.1  390.85
  5280.5   391.6  5551.1  391.87  5560.2  391.89  5672.4  392.73  5931.3  397.88
    5968   400.9  6133.7  408.63  6291.9  419.74  6447.4   421.9    6596  419.58
#Mann= 8 ,-1 , 0
    2704     .12       0  2929.1     .05       0  4989.2     .03       0
  5011.6     .05       0  5280.5     .12       0  5551.1     .05       0
  5560.2     .12       0  5672.4     .05       0
Bank Sta=4989.2,5011.6
XS Rating Curve= 0 ,0
Exp/Cntr=0.3,0.1

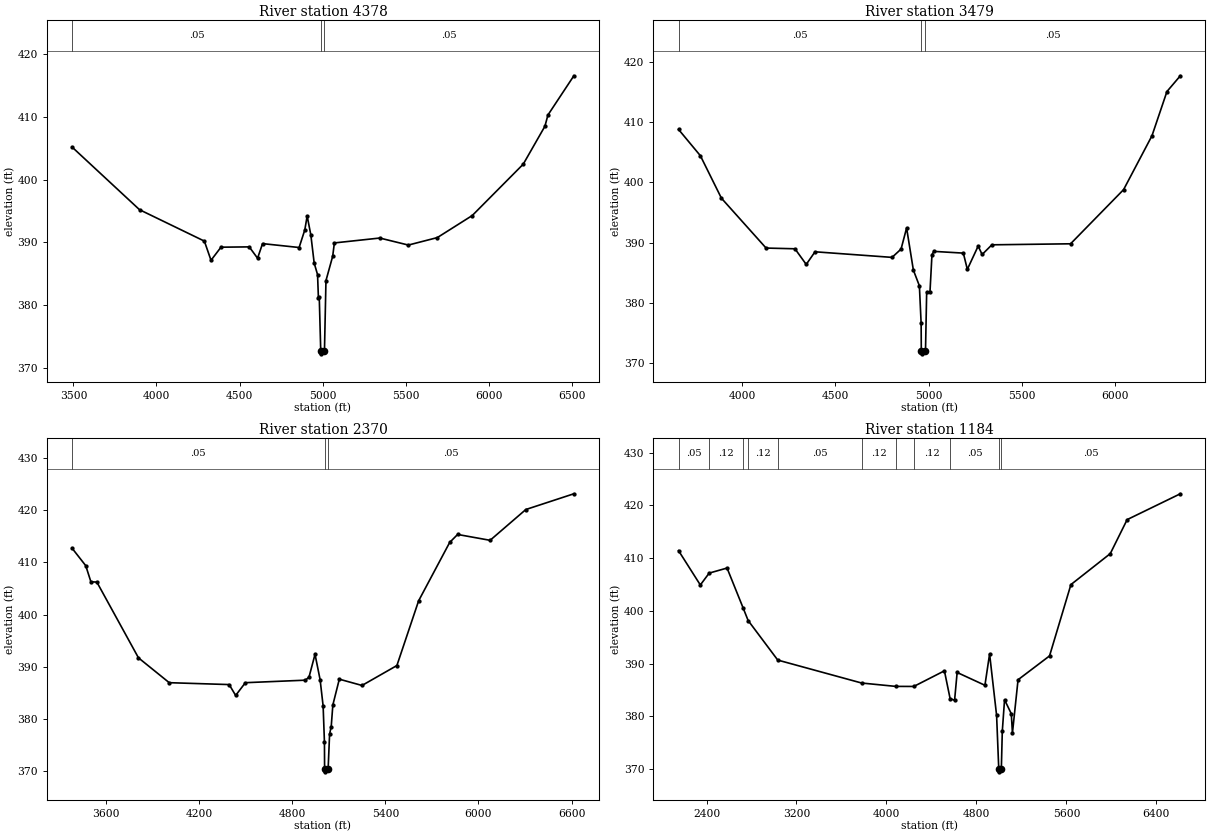
Type RM Length L Ch R = 1 ,4378    ,899,899,899
BEGIN DESCRIPTION:
Little Brushy Creek 7.0
END DESCRIPTION:
XS GIS Cut Line= 3
      2636931.77      6910508.67      2635531.75      6910458.67
      2633931.78      6910208.67
#Sta/Elev= 30
  3491.9  405.18  3897.9  395.19  4288.2  390.18  4328.2  387.12  4388.2  389.21
  4558.3  389.26  4608.4  387.45  4638.4  389.78  4858.5  389.16  4892.8  391.97
  4906.9  394.19    4929  391.18  4949.2  386.68  4969.5  384.83  4974.7  381.08
  4979.8  381.19  4988.6   372.7  4990.8   372.2  5011.1   372.7  5020.1  383.88
  5060.6  387.77  5070.7  389.89    5344  390.67    5516  389.55  5690.3  390.74
  5900.6  394.26  6207.5  402.45    6338   408.5  6356.1  410.29  6512.2  416.55
#Mann= 3 ,-1 , 0
  3491.9     .05       0  4988.6     .03       0  5011.1     .05       0
Bank Sta=4988.6,5011.1
XS Rating Curve= 0 ,0
Exp/Cntr=0.3,0.1

Type RM Length L Ch R = 1 ,3479    ,1109,1109,1109
BEGIN DESCRIPTION:
Little Brushy Creek 6.0
END DESCRIPTION:
XS GIS Cut Line= 3
      2636875.97      6910110.99        2635626.        6909611.
      2634475.96      6908910.98
#Sta/Elev= 30
  3657.8  408.82  3774.9  404.45    3888  397.38  4127.6  389.09  4282.5  388.97
    4343  386.37  4390.2  388.47  4803.5  387.54  4851.9  388.92  4881.6  392.43
  4917.9  385.43  4950.2  382.81  4959.6  376.56  4960.5     372  4962.8   371.5
    4983     372  4989.3  381.77    5007  381.78  5017.7  387.97  5027.3  388.54
  5186.1  388.25  5207.5  385.55  5265.6  389.42  5286.9  388.02  5339.2  389.63
  5761.5   389.8    6046  398.81  6198.2  407.76  6278.6  415.12  6350.4  417.74
#Mann= 3 ,-1 , 0
  3657.8     .05       0  4960.5     .03       0    4983     .05       0
Bank Sta=4960.5,4983
XS Rating Curve= 0 ,0
Exp/Cntr=0.3,0.1

Type RM Length L Ch R = 1 ,2370    ,1186,1186,1186
BEGIN DESCRIPTION:
Little Brushy Creek 4.0
END DESCRIPTION:
XS GIS Cut Line= 3
      2637475.99        6909061.        2635578.      6908495.75
      2634326.85      6908446.21
#Sta/Elev= 30
  3382.1  412.69  3470.2  409.35  3503.4  406.27  3541.8  406.21  3809.9  391.72
  4008.1  386.97  4394.2  386.61  4435.9  384.53  4498.5  386.97  4884.6  387.45
  4908.4  388.03  4947.2   392.4    4980  387.54  4999.4  382.52  5007.9  375.58
  5008.9  370.42  5011.1  369.92  5031.6  370.42  5041.1  377.17  5051.5  378.56
    5062  382.71  5103.7  387.64  5249.8  386.44  5474.6  390.25  5614.7  402.64
  5814.8   413.8  5865.8  415.32    6075   414.2  6305.2  420.09  6614.6   423.1
#Mann= 3 ,-1 , 0
  3382.1     .05       0  5008.9     .03       0  5031.6     .05       0
Bank Sta=5008.9,5031.6
XS Rating Curve= 0 ,0
Exp/Cntr=0.3,0.1

Type RM Length L Ch R = 1 ,1184    ,0,0,0
BEGIN DESCRIPTION:
Little Brushy Creek 3.0
END DESCRIPTION:
XS GIS Cut Line= 3
      2638571.71      6908206.64      2635826.14      6907445.94
      2634213.12      6907469.87
#Sta/Elev= 30
    2151  411.44  2344.8  404.93  2423.5  407.18  2582.4  408.14  2727.1  400.48
  2769.9  398.19  3033.3  390.69  3778.9  386.34  4082.9   385.7  4243.1  385.69
  4515.3  388.65  4565.9  383.39  4605.8  383.06  4628.5  388.34  4875.6  385.91
  4917.1  391.85  4979.4   380.2  4998.7     370    5001   369.5  5021.5     370
  5030.1   377.2  5050.1  383.17  5110.2  380.51  5120.2  376.85  5170.2  386.96
  5450.2  391.48  5640.2     405  5990.2  410.87  6140.3  417.32  6613.2  422.22
#Mann= 11 ,-1 , 0
    2151     .05       0  2423.5     .12       0  2727.1     .05       0
  2769.9     .12       0  3033.3     .05       0  3778.9     .12       0
  4082.9     .05       0  4243.1     .12       0  4565.9     .05       0
  4998.7     .04       0  5021.5     .05       0
Bank Sta=4998.7,5021.5
XS Rating Curve= 0 ,0
Exp/Cntr=0.3,0.1

Chan Stop Cuts=-1
Use User Specified Reach Order=0
Composite Channel Slope=5