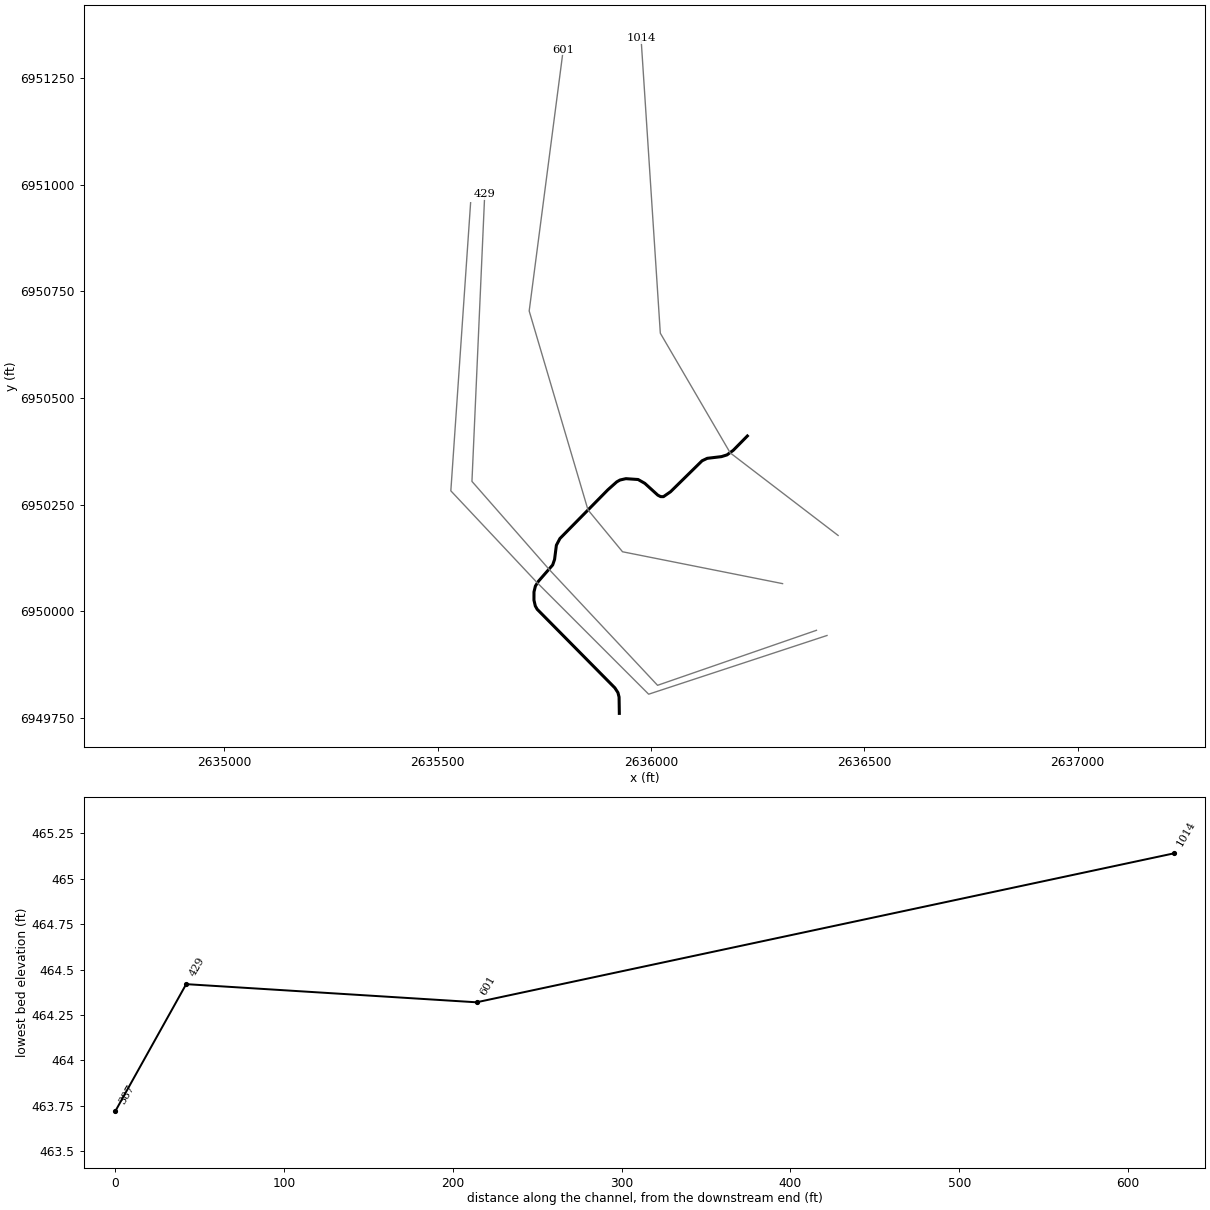
--- Little Brushy Creek Trib 1.prj (project) ---

Proj Title=Little Brushy Creek Trib 1 Base Level Engineering
Current Plan=p01
Default Exp/Contr=0.3,0.1
English Units
Geom File=g01
Flow File=f01
Plan File=p01
BEGIN DESCRIPTION:
Little Brushy Creek Trib 1
END DESCRIPTION:

--- Little Brushy Creek Trib 1.p01 (plan) ---

Plan Title=Multiple Run
Short Identifier=Multiple
Geom File=g01
Flow File=f01
Subcritical Flow
K Sum by GR= 0
Std Step Tol= 0.01
Critical Tol= 0.01
Num of Std Step Trials= 20
Max Error Tol= 0.3
Flow Tol Ratio= 0.001
Split Flow NTrial= 30
Split Flow Tol= 0.02
Split Flow Ratio= 0.02
Log Output Level= 0
Friction Slope Method= 1
Unsteady Friction Slope Method= 2
Unsteady Bridges Friction Slope Method= 1
Parabolic Critical Depth
Global Vel Dist=  1 , 1 , 1
Global Log Level= 0
CheckData=True
Encroach Param= -1, 0, 0, 0
BEGIN DESCRIPTION:
Multiple Run
END DESCRIPTION:

--- Little Brushy Creek Trib 1.f01 (steady flow) ---

Flow Title=Multiple
Number of Profiles=7
Profile Names=10-year,25-year,50-year,1pct_min,100-year,1pct_plu,500-year
River Rch & RM= Little Brushy Cr,Reach-1,1014
     333     425     495     286     570    1138     757
Boundary for River Rch & Prof#=Little Brushy Cr,Reach-1,1
Up Type=0
Dn Type=3
Dn Slope=0.005
Boundary for River Rch & Prof#=Little Brushy Cr,Reach-1,2
Up Type=0
Dn Type=3
Dn Slope=0.005
Boundary for River Rch & Prof#=Little Brushy Cr,Reach-1,3
Up Type=0
Dn Type=3
Dn Slope=0.005
Boundary for River Rch & Prof#=Little Brushy Cr,Reach-1,4
Up Type=0
Dn Type=3
Dn Slope=0.005
Boundary for River Rch & Prof#=Little Brushy Cr,Reach-1,5
Up Type=0
Dn Type=3
Dn Slope=0.005
Boundary for River Rch & Prof#=Little Brushy Cr,Reach-1,6
Up Type=0
Dn Type=3
Dn Slope=0.005
Boundary for River Rch & Prof#=Little Brushy Cr,Reach-1,7
Up Type=0
Dn Type=3
Dn Slope=0.005

--- Little Brushy Creek Trib 1.g01 (geometry) ---

Geom Title=Existing Conditions

River Reach=Little Brushy Cr,Reach-1
Reach XY= 30
      2636226.00      6950411.00      2636192.92      6950377.42
      2636178.35      6950366.70      2636165.31      6950362.65
      2636131.97      6950358.64      2636119.91      6950352.91
      2636046.01      6950280.34      2636029.40      6950268.83
      2636022.77      6950268.92      2636016.13      6950272.39
      2635985.68      6950300.07      2635969.95      6950309.01
      2635941.36      6950310.99      2635927.65      6950307.84
      2635919.95      6950303.50      2635899.18      6950284.96
      2635786.76      6950170.68      2635778.49      6950154.97
      2635774.26      6950121.70      2635769.82      6950108.81
      2635736.49      6950070.55      2635729.31      6950059.26
      2635726.01      6950045.59      2635725.95      6950026.34
      2635729.12      6950012.63      2635733.48      6950004.94
      2635915.48      6949820.79      2635922.73      6949809.64
      2635925.41      6949799.16      2635926.00      6949761.00

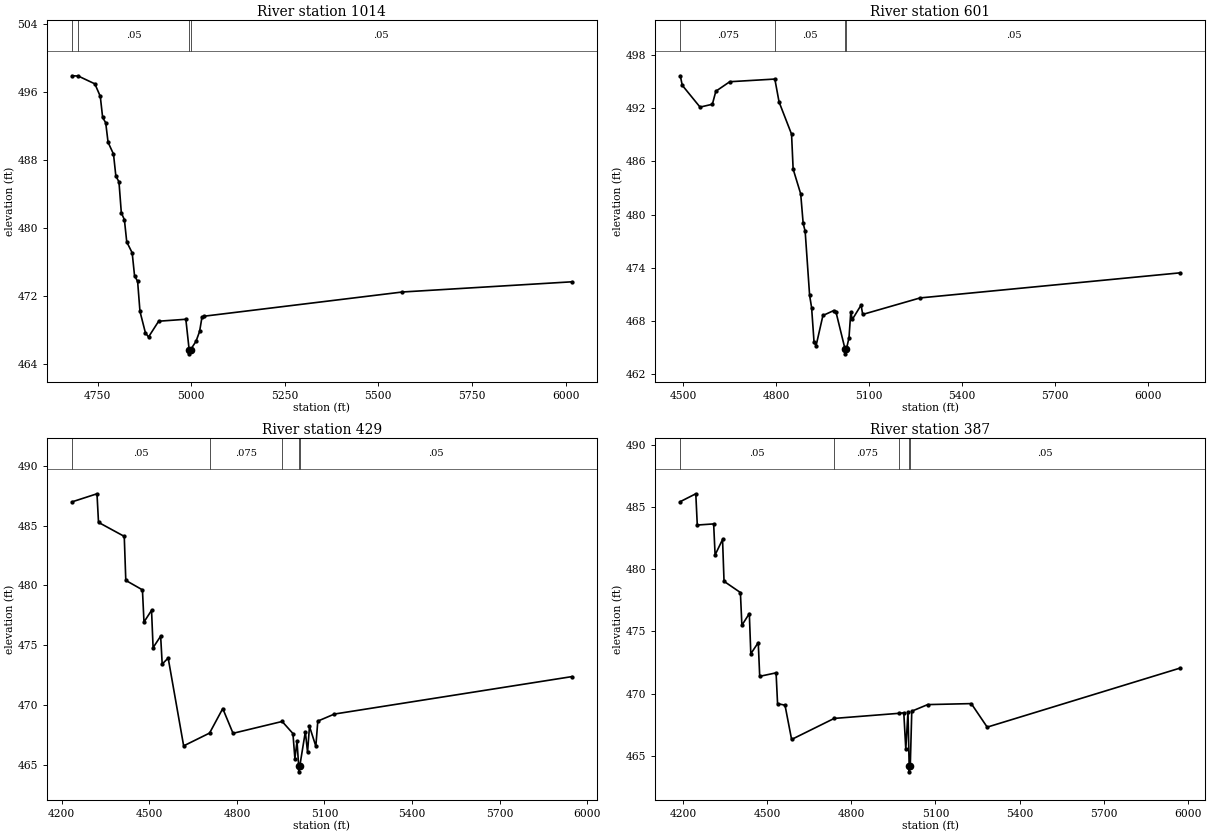
Type RM Length L Ch R = 1,1014,413,413,413
BEGIN DESCRIPTION:
Little Brushy Creek Trib 1 3.0
END DESCRIPTION:
XS GIS Cut Line= 4
      2636438.70      6950177.91      2636185.79      6950371.50
      2636022.06      6950651.85      2635976.92      6951342.82
#Sta/Elev= 30
  4681.5  497.87  4698.5  497.84  4742.9  496.92  4757.4  495.45  4763.7  492.96
  4771.9  492.34  4778.2  490.04  4792.7  488.65  4799.0  486.06  4807.3  485.39
  4813.6  481.74  4821.8  480.93  4828.1  478.31  4842.6  477.03  4848.9  474.33
  4857.1  473.68  4863.4  470.13  4877.9  467.62  4886.2  467.12  4913.3  468.98
  4985.9  469.21  4994.7  465.64  4995.0  465.14  4998.7  465.64  5013.1  466.62
  5022.6  467.77  5028.9  469.43  5034.6  469.57  5564.3  472.42  6017.1  473.62
#Mann=4,-1,0
  4681.5   0.075       0  4698.5    0.05       0  4994.7    0.03       0
  4998.7    0.05       0
Bank Sta=4994.7,4998.7
Exp/Cntr=0.3,0.1

Type RM Length L Ch R = 1,601,172,172,172
BEGIN DESCRIPTION:
Little Brushy Creek Trib 1 4.0
END DESCRIPTION:
XS GIS Cut Line= 5
      2636308.51      6950065.04      2635933.52      6950139.70
      2635852.59      6950237.76      2635714.77      6950703.93
      2635794.58      6951316.44
#Sta/Elev= 30
  4490.5  495.65  4496.8  494.58  4554.2  492.12  4593.9  492.44  4605.2  493.91
  4650.1  494.98  4795.5  495.28  4809.1  492.70  4849.4  489.07  4854.5  485.14
  4878.9  482.34  4886.8  479.04  4893.3  478.12  4907.6  470.93  4914.1  469.52
  4921.9  465.66  4928.4  465.22  4950.6  468.64  4985.8  469.20  4992.3  469.09
  5022.2  464.82  5022.5  464.32  5026.2  464.82  5034.7  466.14  5040.4  468.99
  5045.6  468.21  5073.7  469.81  5078.9  468.76  5264.1  470.62  6103.8  473.45
#Mann=4,-1,0
  4490.5   0.075       0  4795.5    0.05       0  5022.2    0.03       0
  5026.2    0.05       0
Bank Sta=5022.2,5026.2
Exp/Cntr=0.3,0.1

Type RM Length L Ch R = 1,429,42,42,42
BEGIN DESCRIPTION:
Little Brushy Creek Trib 1 1.0
END DESCRIPTION:
XS GIS Cut Line= 5
      2636387.94      6949955.67      2636015.55      6949826.76
      2635761.87      6950097.94      2635580.65      6950304.63
      2635610.55      6950977.08
#Sta/Elev= 30
  4234.6  486.98  4320.7  487.66  4325.9  485.27  4414.1  484.10  4419.4  480.42
  4476.4  479.63  4481.7  476.94  4507.6  477.92  4512.9  474.80  4538.8  475.76
  4544.1  473.43  4564.6  473.93  4617.6  466.59  4706.4  467.66  4751.6  469.71
  4786.8  467.64  4955.1  468.63  4992.0  467.62  4998.7  465.53  5006.0  466.97
  5011.6  464.92  5011.9  464.42  5015.6  464.92  5034.5  467.77  5042.1  466.06
  5048.7  468.22  5070.5  466.56  5077.2  468.66  5134.1  469.25  5948.0  472.38
#Mann=5,-1,0
  4234.6    0.05       0  4706.4   0.075       0  4955.1    0.05       0
  5011.6    0.05       0  5015.6    0.05       0
Bank Sta=5011.6,5015.6
Exp/Cntr=0.3,0.1

Type RM Length L Ch R = 1,387,0,0,0
BEGIN DESCRIPTION:
Little Brushy Creek Trib 1 2.0
END DESCRIPTION:
XS GIS Cut Line= 5
      2636412.66      6949943.51      2635994.72      6949805.93
      2635733.74      6950066.93      2635531.17      6950282.49
      2635577.51      6950957.60
#Sta/Elev= 30
  4190.9  485.42  4246.1  486.05  4251.4  483.54  4309.7  483.63  4314.9  481.14
  4341.4  482.38  4346.7  479.02  4405.0  478.12  4410.3  475.49  4436.8  476.43
  4442.1  473.20  4468.6  474.10  4473.8  471.39  4532.1  471.67  4537.4  469.20
  4563.9  469.07  4587.4  466.32  4739.1  468.01  4969.9  468.42  4987.1  468.46
  4994.2  465.55  5002.0  468.52  5006.2  464.22  5006.5  463.72  5010.2  464.22
  5015.5  468.59  5072.2  469.12  5227.5  469.20  5284.2  467.31  5972.5  472.06
#Mann=5,-1,0
  4190.9    0.05       0  4739.1   0.075       0  4969.9    0.05       0
  5006.2    0.05       0  5010.2    0.05       0
Bank Sta=5006.2,5010.2
Exp/Cntr=0.3,0.1

Chan Stop Cuts=-1