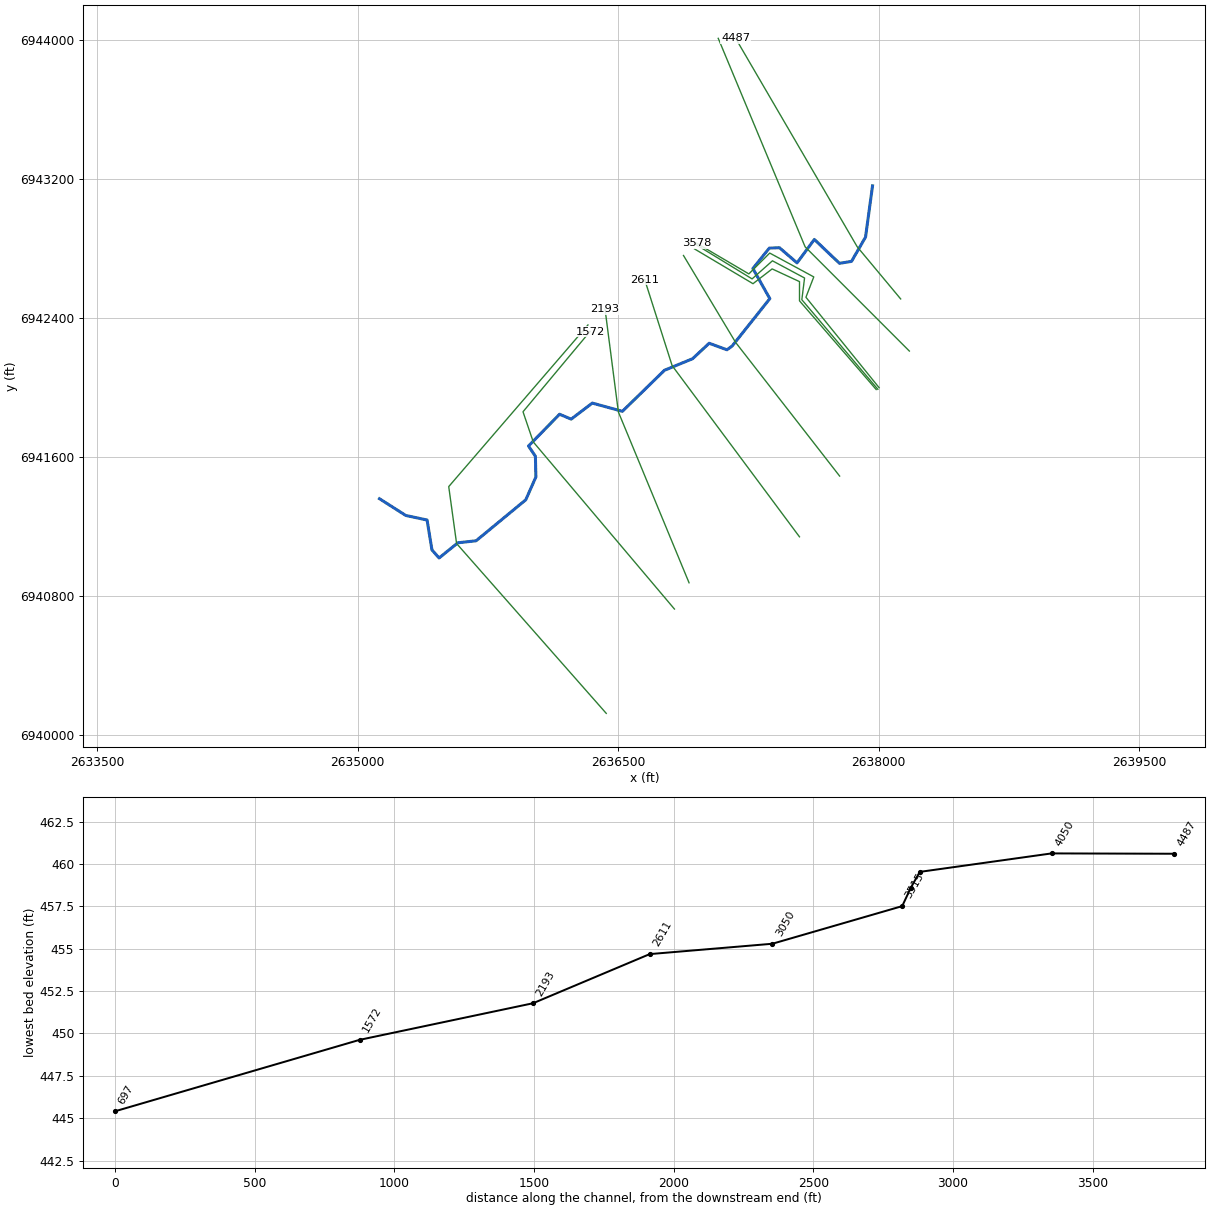
--- Little Brushy Creek Trib 2.prj (project) ---

Proj Title=Little Brushy Creek Trib 2 Base Level Engineering
Current Plan=p01
Default Exp/Contr=0.3,0.1
English Units
Geom File=g01
Flow File=f01
Plan File=p01
BEGIN DESCRIPTION:
Little Brushy Creek Trib 2
END DESCRIPTION:

--- Little Brushy Creek Trib 2.p01 (plan) ---

Plan Title=Multiple Run
Short Identifier=Multiple
Geom File=g01
Flow File=f01
Subcritical Flow
K Sum by GR= 0
Std Step Tol= 0.01
Critical Tol= 0.01
Num of Std Step Trials= 20
Max Error Tol= 0.3
Flow Tol Ratio= 0.001
Split Flow NTrial= 30
Split Flow Tol= 0.02
Split Flow Ratio= 0.02
Log Output Level= 0
Friction Slope Method= 1
Unsteady Friction Slope Method= 2
Unsteady Bridges Friction Slope Method= 1
Parabolic Critical Depth
Global Vel Dist=  1 , 1 , 1
Global Log Level= 0
CheckData=True
Encroach Param= -1, 0, 0, 0
BEGIN DESCRIPTION:
Multiple Run
END DESCRIPTION:

--- Little Brushy Creek Trib 2.f01 (steady flow) ---

Flow Title=Multiple
Number of Profiles=7
Profile Names=10-year,25-year,50-year,1pct_min,100-year,1pct_plu,500-year
River Rch & RM= Little Brushy Cr,Reach-1,4487
     473     623     741     438     873    1743    1212
Boundary for River Rch & Prof#=Little Brushy Cr,Reach-1,1
Up Type=0
Dn Type=3
Dn Slope=0.005
Boundary for River Rch & Prof#=Little Brushy Cr,Reach-1,2
Up Type=0
Dn Type=3
Dn Slope=0.005
Boundary for River Rch & Prof#=Little Brushy Cr,Reach-1,3
Up Type=0
Dn Type=3
Dn Slope=0.005
Boundary for River Rch & Prof#=Little Brushy Cr,Reach-1,4
Up Type=0
Dn Type=3
Dn Slope=0.005
Boundary for River Rch & Prof#=Little Brushy Cr,Reach-1,5
Up Type=0
Dn Type=3
Dn Slope=0.005
Boundary for River Rch & Prof#=Little Brushy Cr,Reach-1,6
Up Type=0
Dn Type=3
Dn Slope=0.005
Boundary for River Rch & Prof#=Little Brushy Cr,Reach-1,7
Up Type=0
Dn Type=3
Dn Slope=0.005

--- Little Brushy Creek Trib 2.g01 (geometry) ---

Geom Title=Existing Conditions

River Reach=Little Brushy Cr,Reach-1
Reach XY= 30
      2637964.04      6943161.98      2637923.81      6942866.91
      2637843.05      6942727.05      2637773.73      6942716.06
      2637629.15      6942853.49      2637529.58      6942718.50
      2637428.29      6942805.91      2637369.93      6942803.55
      2637275.41      6942686.01      2637372.90      6942512.65
      2637156.09      6942240.03      2637126.10      6942218.34
      2637023.72      6942255.87      2636928.29      6942166.85
      2636766.32      6942100.24      2636524.37      6941864.13
      2636350.96      6941911.49      2636229.33      6941819.02
      2636162.67      6941847.35      2635983.79      6941664.42
      2636023.54      6941605.14      2636026.24      6941485.92
      2635967.98      6941354.66      2635682.17      6941118.86
      2635577.50      6941107.36      2635469.00      6941019.82
      2635428.07      6941066.44      2635400.02      6941238.33
      2635277.50      6941264.62      2635126.00      6941361.00

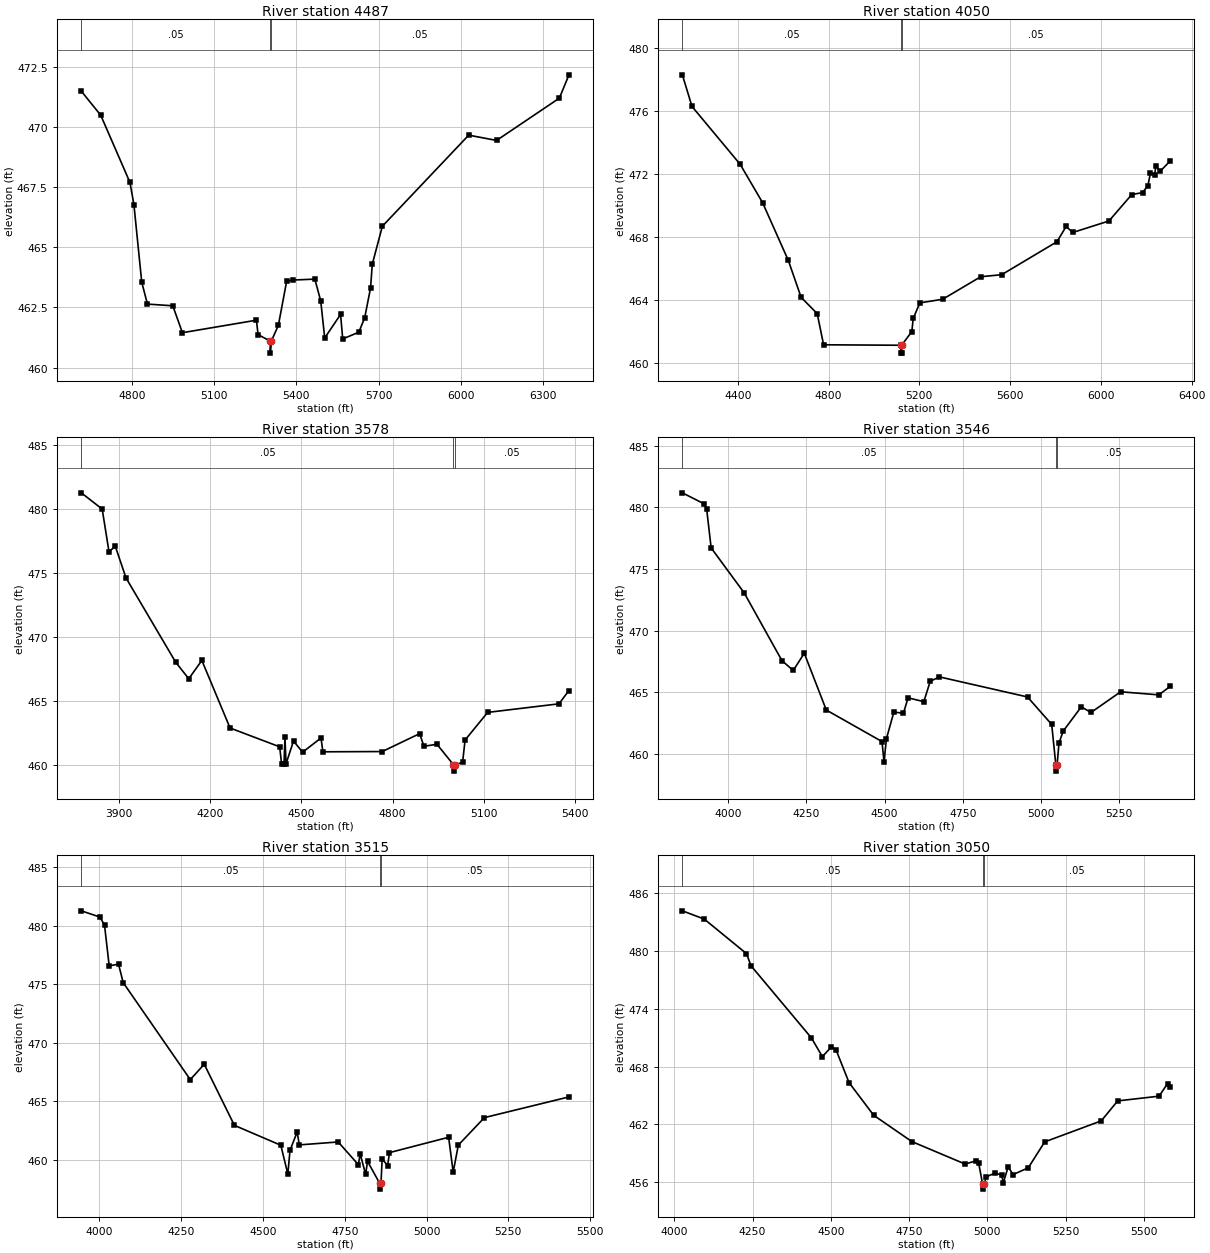
Type RM Length L Ch R = 1,4487,437,437,437
BEGIN DESCRIPTION:
Little Brushy Creek Trib 2 6.0
END DESCRIPTION:
XS GIS Cut Line= 3
      2638125.98      6942511.03      2637876.00      6942811.00
      2637176.01      6944010.98
#Sta/Elev= 30
  4614.9  471.50  4685.8  470.50  4792.5  467.70  4806.9  466.78  4835.5  463.55
  4856.3  462.64  4948.8  462.57  4983.9  461.45  5253.9  461.97  5260.1  461.37
  5304.4  461.10  5304.6  460.60  5308.4  461.10  5334.1  461.76  5364.3  463.59
  5387.0  463.64  5467.2  463.68  5488.7  462.77  5503.2  461.23  5561.1  462.21
  5568.9  461.19  5627.6  461.47  5649.1  462.07  5670.6  463.32  5676.8  464.30
  5713.6  465.88  6028.7  469.67  6130.4  469.45  6359.5  471.21  6394.6  472.18
#Mann=3,-1,0
  4614.9    0.05       0  5304.4    0.03       0  5308.4    0.05       0
Bank Sta=5304.4,5308.4
Exp/Cntr=0.3,0.1

Type RM Length L Ch R = 1,4050,472,472,472
BEGIN DESCRIPTION:
Little Brushy Creek Trib 2 5.0
END DESCRIPTION:
XS GIS Cut Line= 3
      2638176.03      6942210.97      2637576.00      6942811.00
      2637075.99      6944011.02
#Sta/Elev= 30
  4156.1  478.29  4198.6  476.28  4410.7  472.61  4509.7  470.17  4622.8  466.51
  4679.4  464.16  4750.1  463.13  4778.4  461.15  5118.1  461.12  5118.3  460.62
  5121.8  460.62  5122.1  461.12  5167.2  461.99  5173.1  462.82  5202.4  463.81
  5303.1  464.04  5470.5  465.47  5563.1  465.60  5806.3  467.69  5847.0  468.66
  5876.2  468.28  6035.5  469.01  6136.2  470.69  6183.9  470.81  6207.2  471.26
  6218.6  472.06  6237.0  471.94  6242.4  472.52  6260.8  472.16  6304.7  472.81
#Mann=3,-1,0
  4156.1    0.05       0  5118.1    0.03       0  5122.1    0.05       0
Bank Sta=5118.1,5122.1
Exp/Cntr=0.3,0.1

Type RM Length L Ch R = 1,3578,32,32,32
BEGIN DESCRIPTION:
Mapping XS 1a1c1a97
END DESCRIPTION:
XS GIS Cut Line= 6
      2638002.08      6941999.99      2637580.71      6942520.64
      2637625.85      6942637.82      2637372.37      6942774.98
      2637252.15      6942655.05      2636951.32      6942832.01
#Sta/Elev= 30
  3776.5  481.28  3845.2  480.01  3867.5  476.68  3888.3  477.10  3923.5  474.63
  4086.6  468.05  4129.8  466.75  4172.9  468.18  4265.6  462.90  4428.7  461.43
  4435.1  460.07  4443.1  460.10  4446.1  462.17  4449.6  460.10  4474.2  461.88
  4504.2  461.01  4564.6  462.12  4570.9  461.04  4765.9  461.06  4888.9  462.46
  4903.0  461.47  4945.8  461.63  5000.2  460.03  5000.4  459.53  5004.2  460.03
  5030.1  460.21  5038.3  461.96  5112.5  464.12  5346.9  464.79  5379.9  465.83
#Mann=3,-1,0
  3776.5    0.05       0  5000.2    0.03       0  5004.2    0.05       0
Bank Sta=5000.2,5004.2
Exp/Cntr=0.3,0.1

Type RM Length L Ch R = 1,3546,31,31,31
BEGIN DESCRIPTION:
Mapping XS 0632d66e
END DESCRIPTION:
XS GIS Cut Line= 6
      2637994.72      6941990.86      2637557.20      6942506.50
      2637572.82      6942631.50      2637387.93      6942730.46
      2637270.74      6942626.29      2636943.28      6942826.41
#Sta/Elev= 30
  3853.6  481.19  3923.5  480.29  3931.3  479.86  3945.6  476.72  4050.9  473.08
  4171.8  467.57  4207.9  466.77  4243.2  468.17  4313.5  463.56  4491.5  461.00
  4498.0  459.35  4505.7  461.23  4529.5  463.40  4560.0  463.29  4574.7  464.55
  4625.1  464.24  4645.7  465.89  4674.9  466.25  4956.5  464.62  5033.8  462.39
  5047.0  459.10  5047.3  458.60  5051.0  459.10  5057.1  460.88  5070.3  461.84
  5128.4  463.82  5159.3  463.36  5254.1  465.04  5376.1  464.79  5411.9  465.47
#Mann=3,-1,0
  3853.6    0.05       0  5047.0    0.03       0  5051.0    0.05       0
Bank Sta=5047,5051
Exp/Cntr=0.3,0.1

Type RM Length L Ch R = 1,3515,465,465,465
BEGIN DESCRIPTION:
Mapping XS d38be57b
END DESCRIPTION:
XS GIS Cut Line= 6
      2637985.13      6941989.60      2637543.74      6942499.99
      2637543.74      6942610.67      2637386.26      6942683.83
      2637276.02      6942598.76      2636939.66      6942798.65
#Sta/Elev= 30
  3944.5  481.29  4001.3  480.76  4015.5  480.07  4029.8  476.58  4058.3  476.74
  4072.5  475.16  4277.7  466.87  4320.4  468.18  4412.6  462.96  4554.5  461.26
  4576.0  458.80  4582.6  460.82  4604.5  462.39  4611.1  461.29  4730.0  461.54
  4791.6  459.60  4797.2  460.51  4814.0  458.77  4819.6  459.89  4856.8  458.01
  4857.1  457.51  4860.8  458.01  4864.4  460.09  4881.2  459.52  4886.8  460.63
  5067.6  461.94  5081.6  458.96  5097.2  461.27  5177.0  463.62  5435.6  465.39
#Mann=3,-1,0
  3944.5    0.05       0  4856.8    0.03       0  4860.8    0.05       0
Bank Sta=4856.8,4860.8
Exp/Cntr=0.3,0.1

Type RM Length L Ch R = 1,3050,439,439,439
BEGIN DESCRIPTION:
Little Brushy Creek Trib 2 3.0
END DESCRIPTION:
XS GIS Cut Line= 3
      2637774.62      6941491.43      2637176.22      6942260.43
      2636876.00      6942761.01
#Sta/Elev= 30
  4025.6  484.15  4095.7  483.29  4230.5  479.71  4245.0  478.45  4437.7  470.98
  4473.0  469.03  4502.0  470.05  4516.4  469.75  4558.1  466.34  4636.8  462.95
  4758.9  460.22  4929.1  457.89  4964.3  458.23  4972.5  457.96  4985.0  455.79
  4985.2  455.29  4989.0  455.79  4997.2  456.58  5023.9  456.94  5045.3  456.78
  5051.1  455.97  5066.6  457.60  5082.2  456.80  5130.8  457.50  5183.3  460.19
  5364.0  462.37  5416.5  464.44  5548.7  464.93  5575.9  466.24  5583.7  465.86
#Mann=3,-1,0
  4025.6    0.05       0  4985.0    0.04       0  4989.0    0.05       0
Bank Sta=4985,4989
Exp/Cntr=0.3,0.1

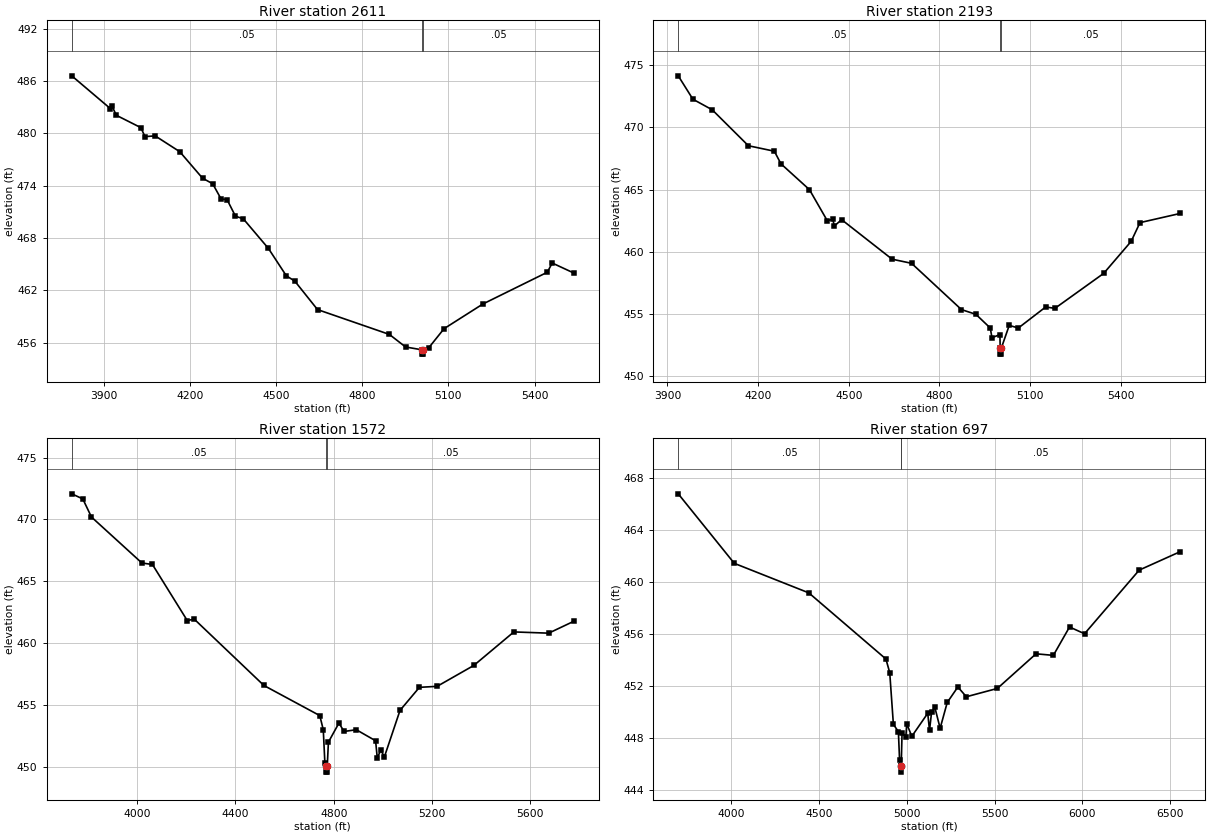
Type RM Length L Ch R = 1,2611,418,418,418
BEGIN DESCRIPTION:
Mapping XS 471716b0
END DESCRIPTION:
XS GIS Cut Line= 3
      2637543.48      6941141.73      2636810.60      6942127.01
      2636652.46      6942622.73
#Sta/Elev= 30
  3788.4  486.60  3922.5  482.85  3928.7  483.13  3943.3  482.08  4028.8  480.66
  4043.4  479.63  4078.9  479.71  4164.4  477.90  4243.7  474.86  4279.1  474.22
  4308.3  472.48  4329.2  472.40  4358.4  470.50  4385.7  470.20  4473.0  466.81
  4535.6  463.66  4564.9  463.06  4644.1  459.79  4894.4  456.94  4950.7  455.50
  5006.9  455.18  5007.1  454.68  5010.6  454.68  5010.9  455.18  5031.0  455.39
  5084.8  457.60  5220.0  460.43  5444.2  464.07  5461.4  465.13  5536.7  463.98
#Mann=3,-1,0
  3788.4    0.05       0  5006.9    0.03       0  5010.9    0.05       0
Bank Sta=5006.9,5010.9
Exp/Cntr=0.3,0.1

Type RM Length L Ch R = 1,2193,621,621,621
BEGIN DESCRIPTION:
Little Brushy Creek Trib 2 2.0
END DESCRIPTION:
XS GIS Cut Line= 3
      2636907.91      6940877.15      2636501.04      6941860.50
      2636424.39      6942452.36
#Sta/Elev= 30
  3935.8  474.15  3984.3  472.27  4048.2  471.42  4167.9  468.53  4253.8  468.09
  4275.5  467.08  4369.9  465.00  4428.5  462.52  4447.0  462.61  4452.4  462.08
  4476.3  462.59  4643.4  459.41  4707.7  459.08  4872.7  455.36  4920.5  454.98
  4968.1  453.88  4973.7  453.10  5000.0  453.35  5000.9  452.28  5001.2  451.78
  5004.7  451.78  5004.9  452.28  5030.8  454.09  5061.0  453.88  5151.4  455.57
  5182.0  455.46  5343.3  458.27  5434.1  460.84  5463.4  462.35  5596.8  463.09
#Mann=3,-1,0
  3935.8    0.05       0  5000.9    0.03       0  5004.9    0.05       0
Bank Sta=5000.9,5004.9
Exp/Cntr=0.3,0.1

Type RM Length L Ch R = 1,1572,875,875,875
BEGIN DESCRIPTION:
Mapping XS 0df745a8
END DESCRIPTION:
XS GIS Cut Line= 4
      2636823.72      6940726.09      2636011.19      6941687.93
      2635952.16      6941861.54      2636337.60      6942323.36
#Sta/Elev= 30
  3733.7  472.07  3778.6  471.66  3813.8  470.20  4019.2  466.49  4062.1  466.37
  4203.8  461.85  4232.4  461.96  4515.9  456.61  4743.4  454.18  4757.6  453.04
  4764.2  450.33  4769.9  450.12  4770.2  449.62  4773.7  449.62  4773.9  450.12
  4778.5  452.04  4821.4  453.58  4842.2  452.90  4892.1  453.04  4970.6  452.15
  4977.4  450.76  4991.5  451.39  5006.6  450.86  5070.0  454.60  5149.0  456.46
  5221.1  456.54  5370.8  458.23  5533.5  460.93  5675.3  460.83  5777.7  461.79
#Mann=3,-1,0
  3733.7    0.05       0  4769.9    0.04       0  4773.9    0.05       0
Bank Sta=4769.9,4773.9
Exp/Cntr=0.3,0.1

Type RM Length L Ch R = 1,697,0,0,0
BEGIN DESCRIPTION:
Little Brushy Creek Trib 2 1.0
END DESCRIPTION:
XS GIS Cut Line= 4
      2636431.34      6940125.42      2635569.83      6941103.10
      2635524.64      6941430.76      2636326.02      6942361.02
#Sta/Elev= 30
  3696.9  466.79  4016.3  461.45  4441.3  459.18  4880.6  454.10  4902.4  453.05
  4923.2  449.08  4951.7  448.52  4958.4  446.35  4963.9  445.91  4964.2  445.41
  4967.9  445.91  4972.6  448.43  4994.4  448.14  4999.1  449.13  5028.2  448.16
  5119.0  449.93  5129.1  448.62  5141.0  450.02  5159.4  450.39  5189.7  448.78
  5230.1  450.76  5290.6  451.95  5339.1  451.20  5515.9  451.84  5736.3  454.50
  5835.0  454.38  5927.2  456.56  6012.7  456.04  6324.3  460.93  6558.6  462.35
#Mann=3,-1,0
  3696.9    0.05       0  4963.9    0.03       0  4967.9    0.05       0
Bank Sta=4963.9,4967.9
Exp/Cntr=0.3,0.1

Chan Stop Cuts=-1