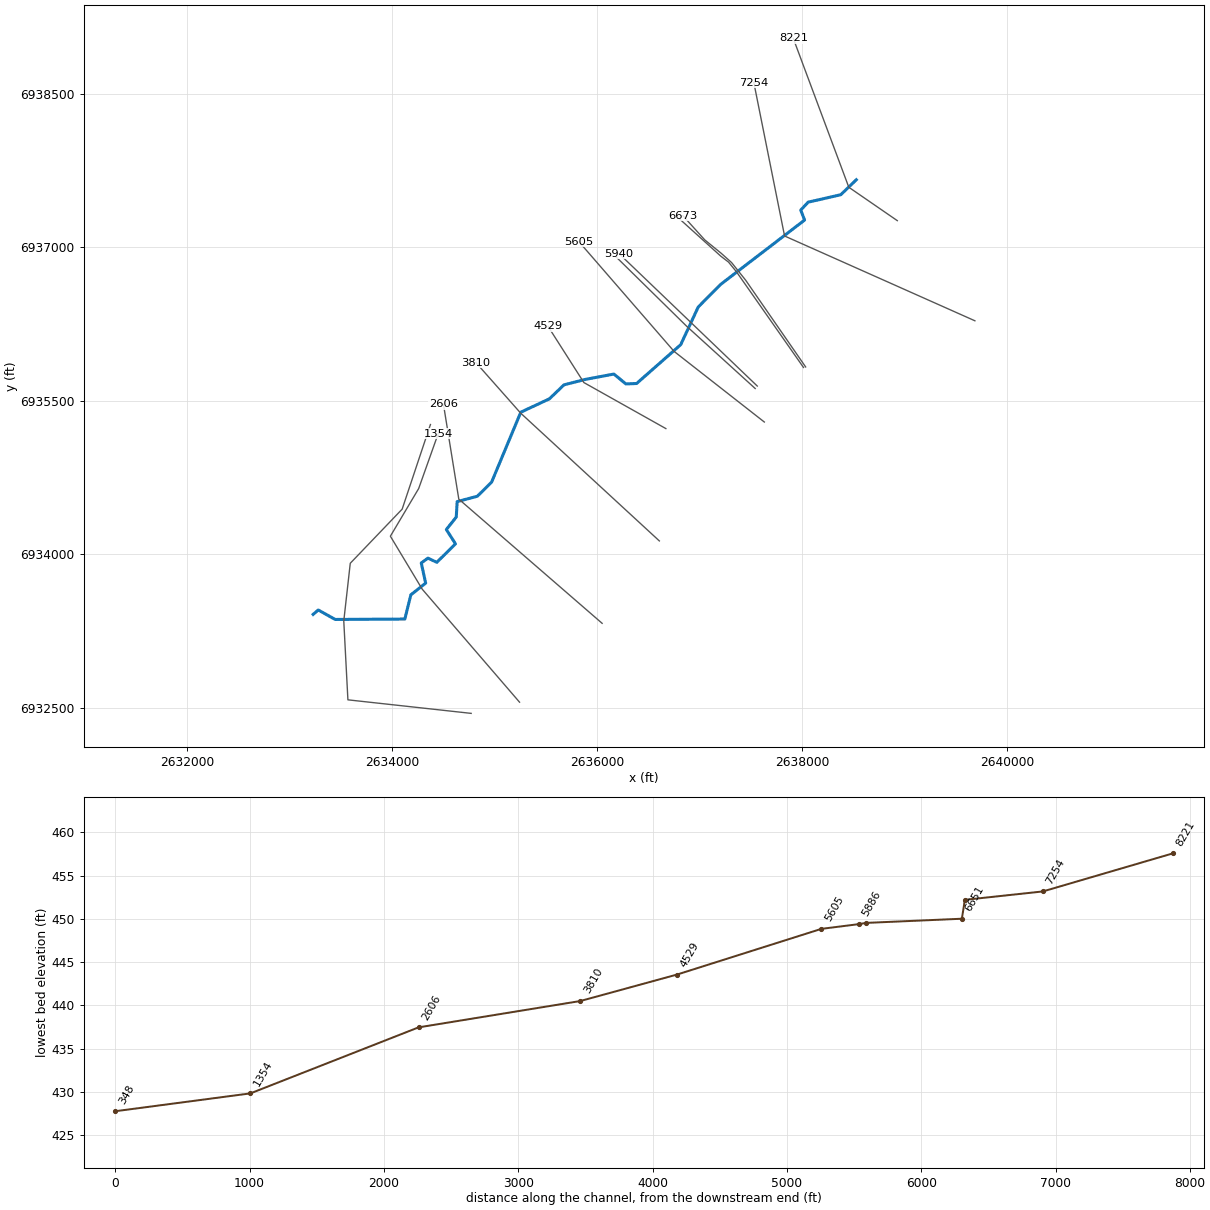
--- Little Brushy Creek Trib 3.prj (project) ---

Proj Title=Little Brushy Creek Trib 3 Base Level Engineering
Current Plan=p01
Default Exp/Contr=0.3,0.1
English Units
Geom File=g01
Flow File=f01
Plan File=p01
BEGIN DESCRIPTION:
Little Brushy Creek Trib 3
END DESCRIPTION:

--- Little Brushy Creek Trib 3.p01 (plan) ---

Plan Title=Multiple Run
Short Identifier=Multiple
Geom File=g01
Flow File=f01
Subcritical Flow
K Sum by GR= 0
Std Step Tol= 0.01
Critical Tol= 0.01
Num of Std Step Trials= 20
Max Error Tol= 0.3
Flow Tol Ratio= 0.001
Split Flow NTrial= 30
Split Flow Tol= 0.02
Split Flow Ratio= 0.02
Log Output Level= 0
Friction Slope Method= 1
Unsteady Friction Slope Method= 2
Unsteady Bridges Friction Slope Method= 1
Parabolic Critical Depth
Global Vel Dist=  1 , 1 , 1
Global Log Level= 0
CheckData=True
Encroach Param= -1, 0, 0, 0
BEGIN DESCRIPTION:
Multiple Run
END DESCRIPTION:

--- Little Brushy Creek Trib 3.f01 (steady flow) ---

Flow Title=Multiple
Number of Profiles=7
Profile Names=10-year,25-year,50-year,1pct_min,100-year,1pct_plu,500-year
River Rch & RM= Little Brushy Cr,Reach-1,8221
     386     501     592     347     692    1380     945
River Rch & RM= Little Brushy Cr,Reach-1,7254
     632     849    1023     612    1220    2435    1735
River Rch & RM= Little Brushy Cr,Reach-1,6673
     885    1208    1473     889    1775    3541    2576
Boundary for River Rch & Prof#=Little Brushy Cr,Reach-1,1
Up Type=0
Dn Type=3
Dn Slope=0.005
Boundary for River Rch & Prof#=Little Brushy Cr,Reach-1,2
Up Type=0
Dn Type=3
Dn Slope=0.005
Boundary for River Rch & Prof#=Little Brushy Cr,Reach-1,3
Up Type=0
Dn Type=3
Dn Slope=0.005
Boundary for River Rch & Prof#=Little Brushy Cr,Reach-1,4
Up Type=0
Dn Type=3
Dn Slope=0.005
Boundary for River Rch & Prof#=Little Brushy Cr,Reach-1,5
Up Type=0
Dn Type=3
Dn Slope=0.005
Boundary for River Rch & Prof#=Little Brushy Cr,Reach-1,6
Up Type=0
Dn Type=3
Dn Slope=0.005
Boundary for River Rch & Prof#=Little Brushy Cr,Reach-1,7
Up Type=0
Dn Type=3
Dn Slope=0.005

--- Little Brushy Creek Trib 3.g01 (geometry) ---

Geom Title=Existing Conditions

River Reach=Little Brushy Cr,Reach-1
Reach XY= 30
      2638526.00      6937661.00      2638374.53      6937514.54
      2638055.91      6937441.63      2637983.83      6937364.41
      2638021.20      6937266.59      2637202.54      6936637.98
      2636983.86      6936417.17      2636812.38      6936047.78
      2636382.17      6935668.76      2636277.50      6935664.47
      2636160.66      6935761.04      2635881.94      6935708.74
      2635673.55      6935655.53      2635532.06      6935519.14
      2635252.19      6935388.03      2634967.84      6934704.95
      2634828.45      6934566.47      2634631.35      6934513.74
      2634622.44      6934362.47      2634525.54      6934240.84
      2634615.12      6934100.70      2634432.75      6933920.14
      2634346.03      6933961.36      2634280.99      6933913.62
      2634324.04      6933716.88      2634179.51      6933602.52
      2634120.81      6933365.63      2633441.21      6933361.51
      2633275.88      6933454.13      2633226.00      6933411.00

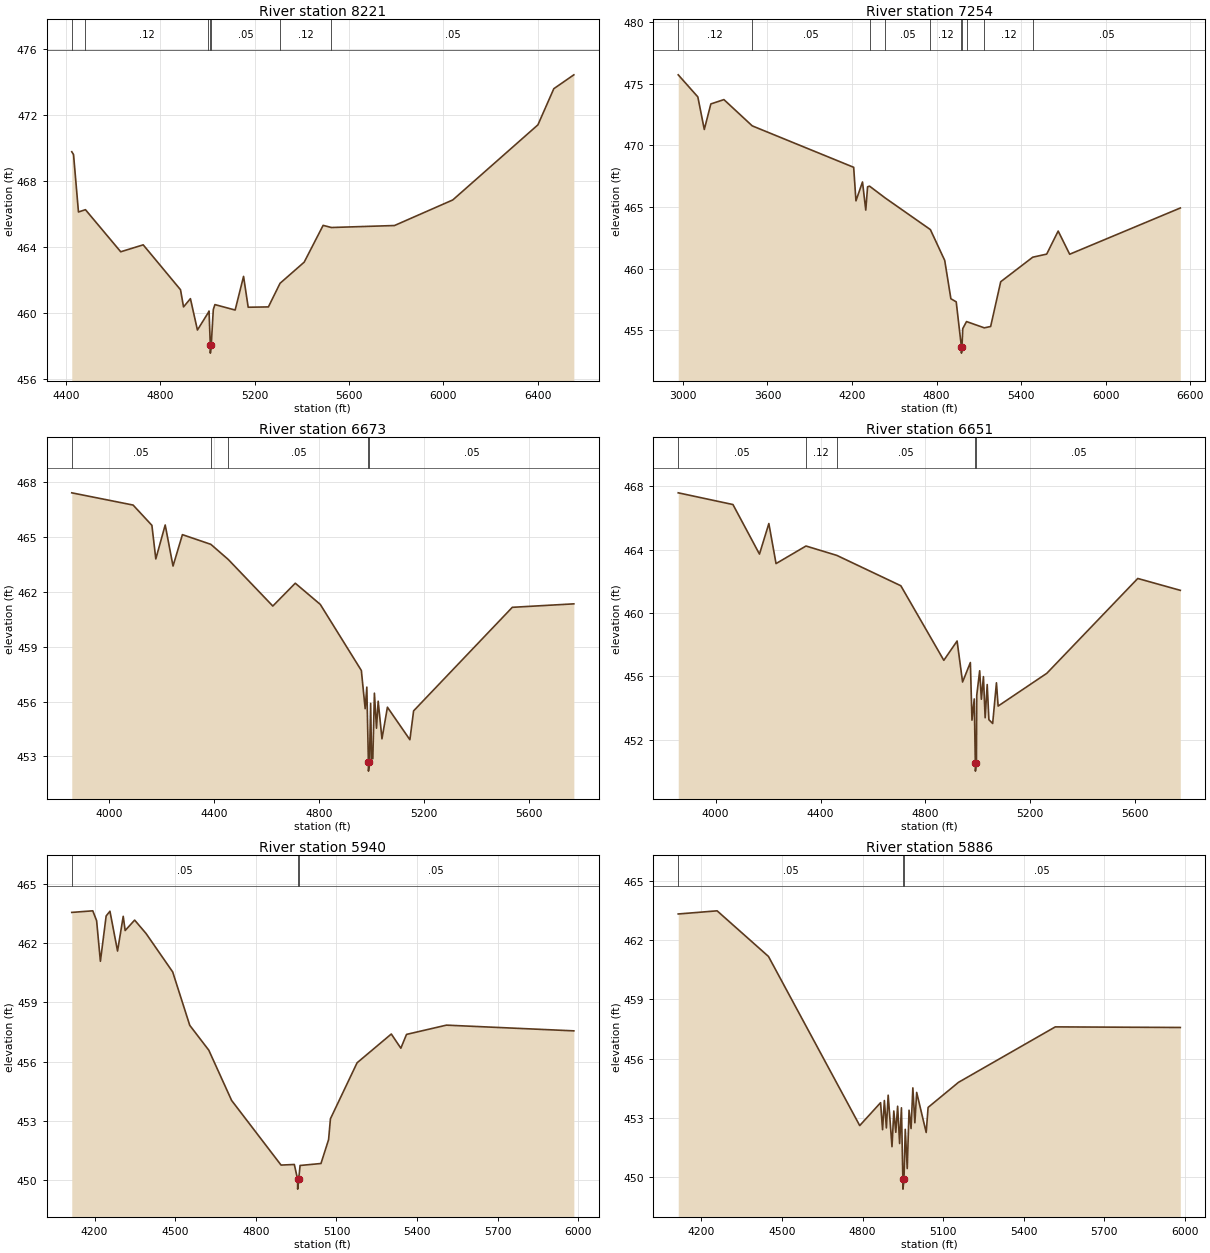
Type RM Length L Ch R = 1,8221,967,967,967
BEGIN DESCRIPTION:
Little Brushy Creek Trib 3 8.0
END DESCRIPTION:
XS GIS Cut Line= 3
      2638926.04      6937260.98      2638452.69      6937587.60
      2637910.72      6939043.71
#Sta/Elev= 30
  4424.9  469.75  4432.4  469.58  4453.3  466.10  4482.9  466.24  4632.5  463.69
  4727.8  464.11  4886.0  461.39  4898.8  460.35  4928.0  460.85  4957.7  458.95
  5002.6  459.98  5006.9  460.10  5012.3  458.05  5012.5  457.55  5016.3  458.05
  5025.0  460.19  5031.9  460.49  5117.6  460.16  5153.3  462.20  5172.9  460.33
  5258.6  460.35  5308.0  461.78  5410.3  463.06  5490.7  465.29  5525.7  465.16
  5793.2  465.28  6040.4  466.83  6401.4  471.38  6468.8  473.57  6553.7  474.41
#Mann=7,-1,0
  4424.9    0.05       0  4482.9    0.12       0  5002.6    0.05       0
  5012.3    0.07       0  5016.3    0.05       0  5308.0    0.12       0
  5525.7    0.05       0
Bank Sta=5012.3,5016.3
Exp/Cntr=0.3,0.1

Type RM Length L Ch R = 1,7254,581,581,581
BEGIN DESCRIPTION:
Little Brushy Creek Trib 3 6.0
END DESCRIPTION:
XS GIS Cut Line= 3
      2639683.04      6936281.94      2637826.00      6937111.00
      2637526.00      6938610.99
#Sta/Elev= 30
  2966.5  475.73  3105.6  473.94  3151.5  471.30  3198.0  473.37  3290.8  473.72
  3491.8  471.59  4211.7  468.23  4227.8  465.51  4274.3  467.04  4297.5  464.76
  4310.3  466.65  4324.5  466.70  4435.9  465.74  4756.0  463.18  4857.8  460.68
  4901.6  457.57  4939.4  457.32  4976.3  453.66  4976.6  453.16  4980.3  453.66
  4985.9  455.15  5012.6  455.72  5138.9  455.21  5183.8  455.32  5255.2  458.95
  5482.6  460.94  5581.5  461.19  5663.1  463.06  5744.7  461.18  6529.9  464.93
#Mann=10,-1,0
  2966.5    0.12       0  3491.8    0.05       0  4324.5    0.12       0
  4435.9    0.05       0  4756.0    0.12       0  4976.3    0.07       0
  4980.3    0.12       0  5012.6    0.05       0  5138.9    0.12       0
  5482.6    0.05       0
Bank Sta=4976.3,4980.3
Exp/Cntr=0.3,0.1

Type RM Length L Ch R = 1,6673,22,22,22
BEGIN DESCRIPTION:
Mapping XS 9dae7544
END DESCRIPTION:
XS GIS Cut Line= 6
      2638031.59      6935830.61      2637445.64      6936679.59
      2637309.00      6936851.20      2637208.31      6936941.48
      2637047.20      6937072.82      2636833.67      6937309.79
#Sta/Elev= 30
  3857.3  467.43  4091.0  466.76  4162.6  465.65  4177.5  463.81  4213.3  465.67
  4243.1  463.42  4278.9  465.14  4387.1  464.61  4453.6  463.78  4623.3  461.23
  4708.9  462.48  4804.2  461.32  4960.7  457.70  4975.2  455.61  4981.5  456.79
  4987.5  452.69  4987.8  452.19  4991.6  452.69  4996.0  455.90  4999.7  452.87
  5004.4  452.87  5010.4  456.46  5018.4  454.54  5024.8  456.02  5039.2  453.96
  5060.0  455.69  5145.6  453.91  5159.8  455.49  5535.8  461.16  5770.3  461.35
#Mann=5,-1,0
  3857.3    0.05       0  4387.1    0.12       0  4453.6    0.05       0
  4987.5    0.04       0  4991.6    0.05       0
Bank Sta=4987.5,4991.6
Exp/Cntr=0.3,0.1

Type RM Length L Ch R = 1,6651,711,711,711
BEGIN DESCRIPTION:
Mapping XS 701626b8
END DESCRIPTION:
XS GIS Cut Line= 5
      2638010.76      6935825.40      2637357.09      6936760.32
      2637279.49      6936855.54      2637203.45      6936913.96
      2636792.18      6937286.19
#Sta/Elev= 30
  3857.5  467.59  4066.1  466.85  4167.2  463.72  4203.0  465.65  4230.4  463.12
  4344.6  464.23  4461.8  463.64  4706.2  461.72  4870.1  457.01  4920.7  458.23
  4941.6  455.64  4971.3  456.87  4977.4  453.23  4986.1  454.57  4990.2  450.51
  4990.5  450.01  4994.3  450.51  4995.6  454.80  5006.8  456.35  5013.2  454.55
  5021.1  455.98  5027.6  453.38  5035.5  455.48  5041.9  453.26  5056.3  453.02
  5070.7  455.59  5077.1  454.12  5262.8  456.19  5609.5  462.18  5771.7  461.43
#Mann=5,-1,0
  3857.5    0.05       0  4344.6    0.12       0  4461.8    0.05       0
  4990.2    0.04       0  4994.3    0.05       0
Bank Sta=4990.2,4994.3
Exp/Cntr=0.3,0.1

Type RM Length L Ch R = 1,5940,54,54,54
BEGIN DESCRIPTION:
Mapping XS 4d378fde
END DESCRIPTION:
XS GIS Cut Line= 2
      2637559.46      6935643.80      2636212.26      6936937.23
#Sta/Elev= 30
  4115.4  463.57  4193.6  463.65  4207.8  463.15  4221.9  461.09  4243.3  463.39
  4257.4  463.63  4285.7  461.61  4306.8  463.37  4314.0  462.65  4349.3  463.18
  4391.7  462.50  4490.8  460.55  4554.3  457.84  4625.1  456.58  4710.0  454.03
  4893.9  450.75  4943.3  450.78  4955.4  450.03  4955.7  449.53  4959.6  450.03
  4964.7  450.73  5042.4  450.83  5070.7  452.04  5077.6  453.10  5176.7  455.94
  5304.0  457.40  5339.5  456.68  5360.6  457.38  5509.1  457.85  5983.0  457.56
#Mann=3,-1,0
  4115.4    0.05       0  4955.4    0.04       0  4959.6    0.05       0
Bank Sta=4955.4,4959.6
Exp/Cntr=0.3,0.1

Type RM Length L Ch R = 1,5886,281,281,281
BEGIN DESCRIPTION:
Mapping XS 78899b86
END DESCRIPTION:
XS GIS Cut Line= 3
      2637539.35      6935619.72      2636870.12      6936229.07
      2636182.70      6936906.07
#Sta/Elev= 30
  4113.5  463.33  4258.3  463.49  4449.5  461.18  4789.4  452.61  4867.1  453.77
  4874.5  452.40  4881.2  453.88  4888.7  452.49  4895.4  454.15  4909.6  451.54
  4916.4  453.35  4923.8  452.27  4930.6  453.59  4938.0  451.70  4944.8  453.51
  4950.1  449.89  4950.4  449.39  4954.3  449.89  4959.0  452.42  4966.4  450.43
  4973.1  453.39  4980.6  452.46  4987.3  454.52  4994.8  452.75  5001.5  454.29
  5037.0  452.26  5044.1  453.53  5157.2  454.80  5517.8  457.61  5983.4  457.58
#Mann=3,-1,0
  4113.5    0.05       0  4950.1    0.04       0  4954.3    0.05       0
Bank Sta=4950.1,4954.3
Exp/Cntr=0.3,0.1

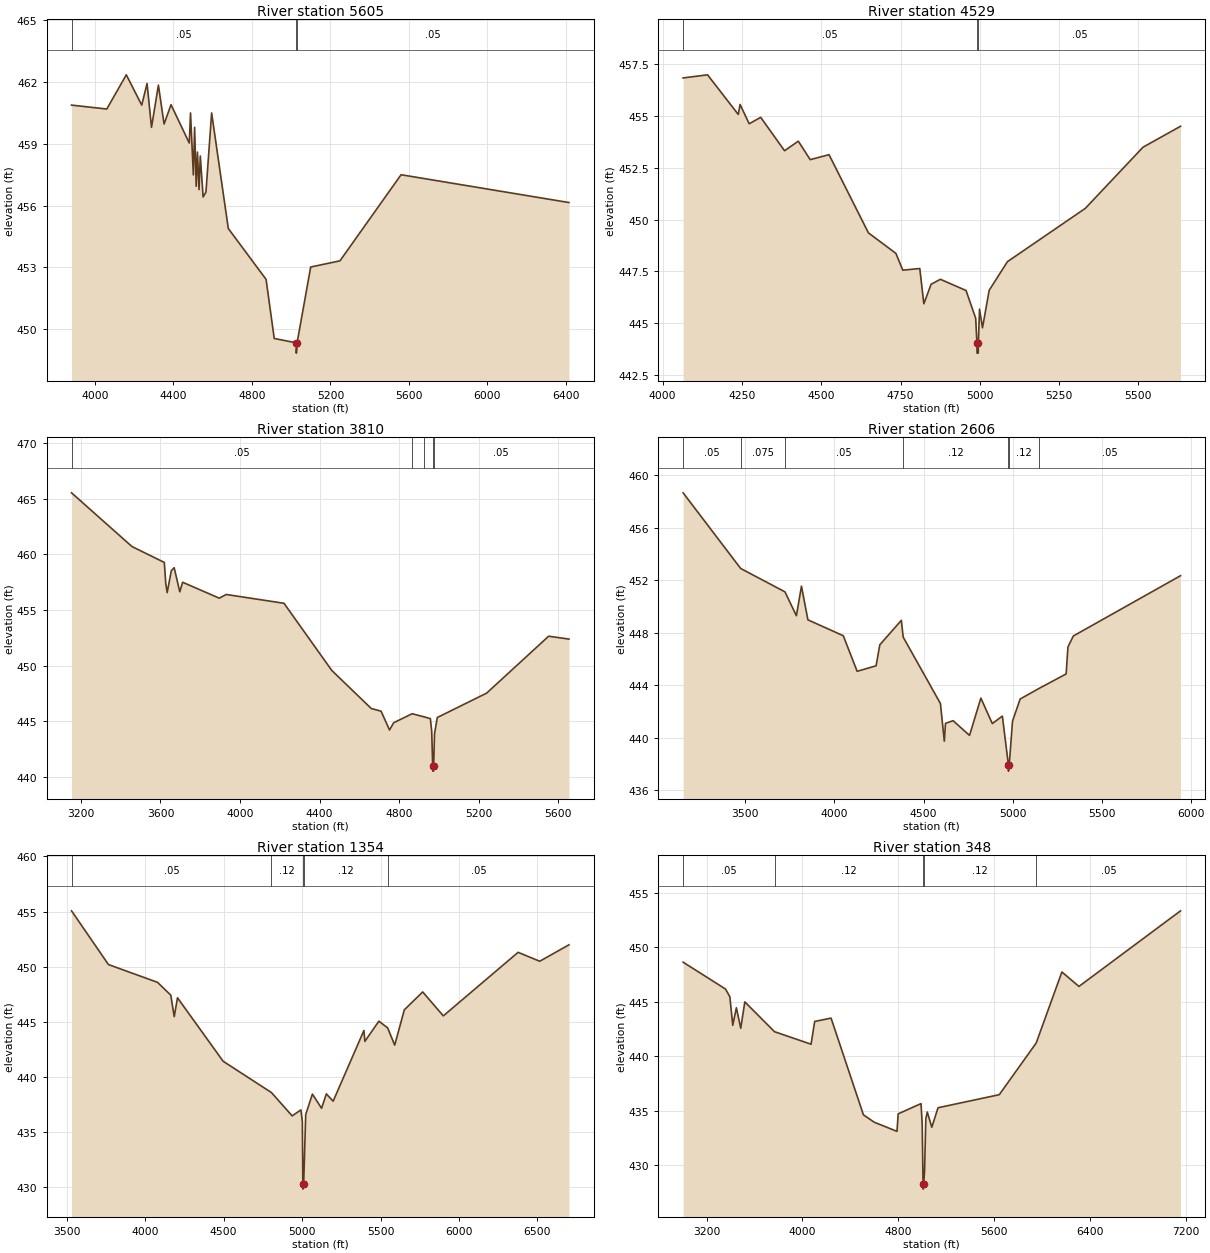
Type RM Length L Ch R = 1,5605,1076,1076,1076
BEGIN DESCRIPTION:
Mapping XS 52ed7c2b
END DESCRIPTION:
XS GIS Cut Line= 3
      2637628.43      6935292.05      2636747.91      6935982.66
      2635821.35      6937053.10
#Sta/Elev= 30
  3880.9  460.88  4060.5  460.69  4160.0  462.35  4238.6  460.88  4265.8  461.93
  4288.4  459.80  4323.6  461.85  4352.5  459.96  4387.8  460.90  4480.9  459.04
  4487.2  460.50  4501.7  457.49  4508.1  459.80  4516.2  456.94  4522.5  458.60
  4530.6  456.78  4537.0  458.41  4551.4  456.42  4565.9  456.66  4594.8  460.50
  4679.8  454.89  4872.3  452.42  4913.9  449.55  5026.2  449.34  5026.5  448.84
  5030.4  449.34  5099.6  453.02  5248.7  453.32  5560.2  457.50  6415.7  456.15
#Mann=3,-1,0
  3880.9    0.05       0  5026.2    0.03       0  5030.4    0.05       0
Bank Sta=5026.2,5030.4
Exp/Cntr=0.3,0.1

Type RM Length L Ch R = 1,4529,719,719,719
BEGIN DESCRIPTION:
Little Brushy Creek Trib 3 2.0
END DESCRIPTION:
XS GIS Cut Line= 3
      2636667.59      6935227.99      2635867.61      6935677.98
      2635518.24      6936226.99
#Sta/Elev= 30
  4064.5  456.83  4141.5  456.98  4238.4  455.07  4244.1  455.55  4272.8  454.62
  4309.1  454.93  4384.3  453.32  4427.7  453.78  4465.3  452.89  4524.6  453.13
  4648.8  449.36  4735.5  448.37  4757.2  447.56  4810.8  447.64  4823.6  445.94
  4846.5  446.88  4875.8  447.12  4956.7  446.58  4987.1  445.24  4991.0  444.06
  4991.4  443.56  4995.1  443.56  4995.6  444.06  4999.2  445.68  5008.5  444.78
  5029.7  446.59  5087.2  447.97  5332.8  450.54  5514.8  453.49  5633.1  454.50
#Mann=3,-1,0
  4064.5    0.05       0  4991.0    0.04       0  4995.6    0.05       0
Bank Sta=4991,4995.6
Exp/Cntr=0.3,0.1

Type RM Length L Ch R = 1,3810,1204,1204,1204
BEGIN DESCRIPTION:
Mapping XS d47810b8
END DESCRIPTION:
XS GIS Cut Line= 3
      2636604.04      6934129.48      2635251.56      6935378.37
      2634814.18      6935873.30
#Sta/Elev= 30
  3152.8  465.53  3456.8  460.70  3619.5  459.27  3626.5  457.42  3633.7  456.56
  3654.7  458.53  3668.9  458.80  3697.2  456.63  3711.4  457.49  3895.7  456.06
  3930.8  456.39  4221.2  455.60  4461.6  449.56  4660.1  446.14  4709.4  445.90
  4751.9  444.21  4772.9  444.86  4865.5  445.67  4925.5  445.39  4957.2  445.23
  4964.0  444.10  4969.0  441.01  4969.5  440.51  4973.2  440.51  4973.8  441.01
  4978.2  443.86  4992.0  445.33  5240.1  447.52  5552.2  452.64  5654.2  452.38
#Mann=5,-1,0
  3152.8    0.05       0  4865.5    0.12       0  4925.5    0.05       0
  4969.0    0.03       0  4973.8    0.05       0
Bank Sta=4969,4973.8
Exp/Cntr=0.3,0.1

Type RM Length L Ch R = 1,2606,1252,1252,1252
BEGIN DESCRIPTION:
Mapping XS e6dc89da
END DESCRIPTION:
XS GIS Cut Line= 3
      2636045.81      6933323.74      2634647.27      6934538.11
      2634497.63      6935464.71
#Sta/Elev= 30
  3151.0  458.66  3473.8  452.90  3722.4  451.12  3786.5  449.30  3814.9  451.55
  3851.1  448.99  4049.5  447.78  4127.4  445.07  4233.7  445.49  4254.6  447.09
  4375.2  448.95  4385.8  447.67  4594.6  442.62  4616.4  439.75  4623.1  441.11
  4665.8  441.31  4757.9  440.19  4821.5  443.03  4885.7  441.09  4942.1  441.66
  4975.8  437.97  4976.4  437.47  4980.7  437.97  4999.1  441.28  5042.0  442.96
  5148.4  443.77  5299.9  444.87  5310.0  446.92  5340.4  447.76  5941.8  452.35
#Mann=7,-1,0
  3151.0    0.05       0  3473.8   0.075       0  3722.4    0.05       0
  4385.8    0.12       0  4975.8    0.07       0  4980.7    0.12       0
  5148.4    0.05       0
Bank Sta=4975.8,4980.7
Exp/Cntr=0.3,0.1

Type RM Length L Ch R = 1,1354,1006,1006,1006
BEGIN DESCRIPTION:
Mapping XS a6c9c641
END DESCRIPTION:
XS GIS Cut Line= 5
      2635240.06      6932552.57      2634290.45      6933657.57
      2633979.67      6934175.53      2634255.92      6934641.70
      2634445.66      6935176.44
#Sta/Elev= 30
  3530.5  455.07  3765.8  450.20  4078.5  448.59  4163.0  447.43  4185.0  445.48
  4205.8  447.19  4496.6  441.44  4804.7  438.60  4936.6  436.49  4992.4  437.03
  5001.6  435.96  5004.8  430.35  5005.5  429.85  5010.1  430.35  5023.0  436.61
  5065.7  438.46  5124.0  437.18  5154.7  438.48  5197.9  437.82  5394.2  444.23
  5400.0  443.24  5489.4  445.07  5545.4  444.46  5590.2  442.90  5651.6  446.10
  5768.6  447.72  5900.1  445.55  6376.7  451.31  6514.6  450.50  6700.8  451.99
#Mann=5,-1,0
  3530.5    0.05       0  4804.7    0.12       0  5004.8    0.07       0
  5010.1    0.12       0  5545.4    0.05       0
Bank Sta=5004.8,5010.1
Exp/Cntr=0.3,0.1

Type RM Length L Ch R = 1,348,0,0,0
BEGIN DESCRIPTION:
Mapping XS eebc9a4d
END DESCRIPTION:
XS GIS Cut Line= 6
      2634768.16      6932443.22      2633565.29      6932575.59
      2633525.01      6933346.79      2633588.31      6933910.80
      2634094.77      6934440.27      2634370.52      6935267.51
#Sta/Elev= 30
  3003.4  448.65  3357.7  446.18  3393.7  445.47  3418.0  442.85  3448.2  444.46
  3484.7  442.58  3518.7  445.00  3766.7  442.26  4072.0  441.11  4102.2  443.20
  4239.0  443.51  4509.3  434.62  4599.5  433.94  4789.7  433.10  4799.7  434.71
  4990.4  435.65  5000.1  433.81  5007.4  428.29  5008.2  427.79  5012.8  428.29
  5020.2  429.51  5030.3  434.24  5042.4  434.88  5080.6  433.48  5132.5  435.27
  5643.8  436.47  5952.3  441.22  6167.1  447.75  6309.4  446.42  7158.0  453.37
#Mann=5,-1,0
  3003.4    0.05       0  3766.7    0.12       0  5007.4    0.07       0
  5012.8    0.12       0  5952.3    0.05       0
Bank Sta=5007.4,5012.8
Exp/Cntr=0.3,0.1

Chan Stop Cuts=-1