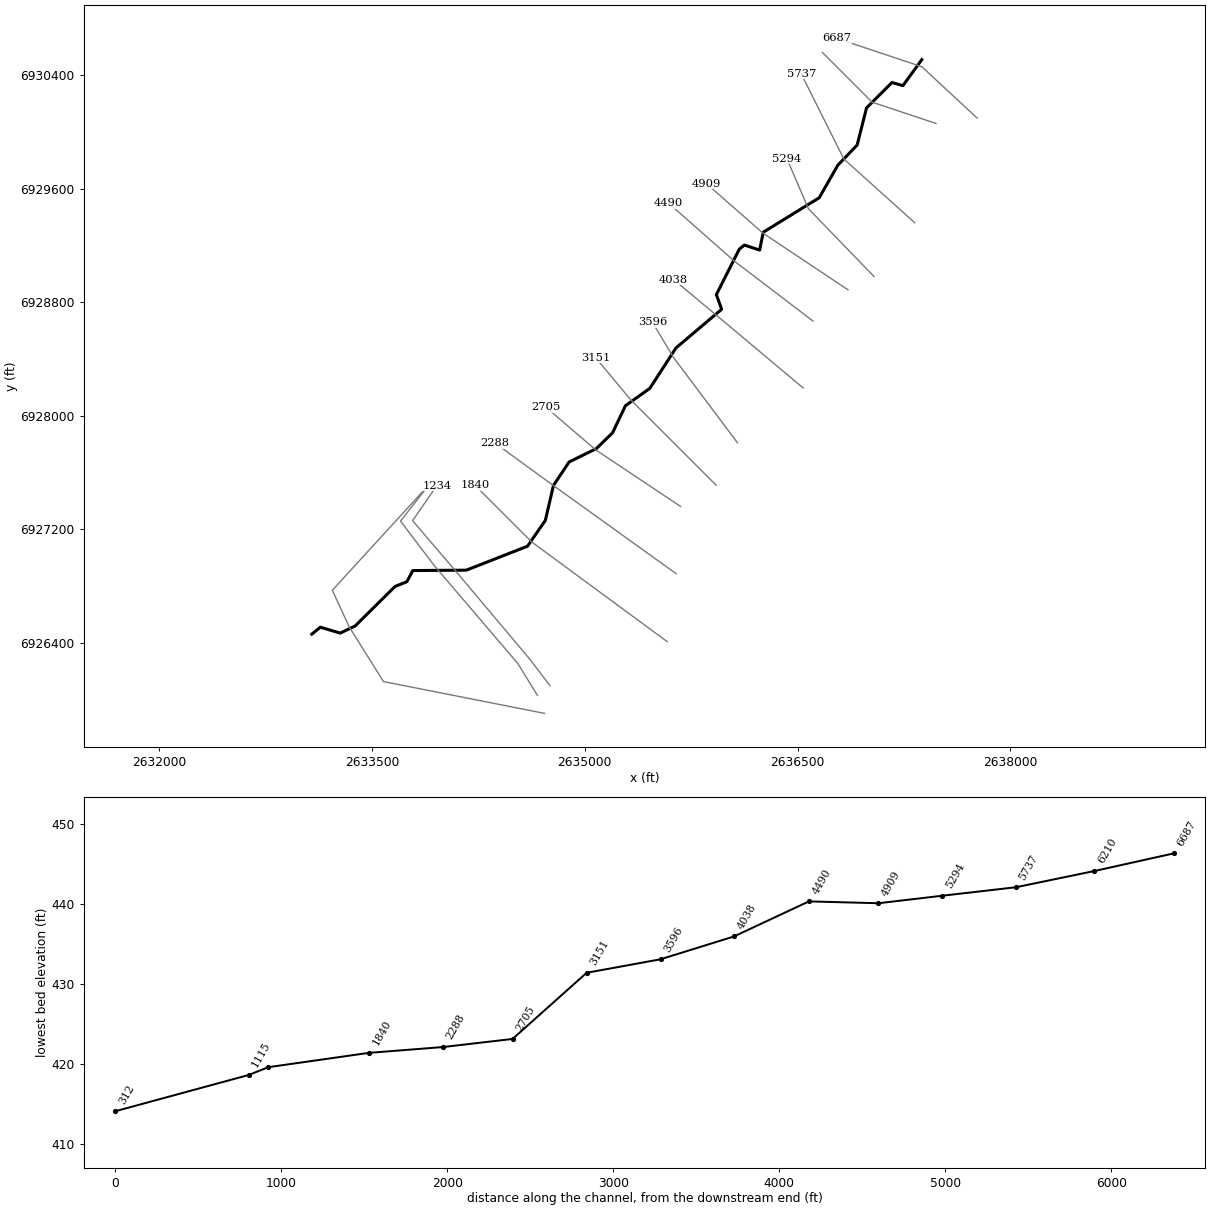
--- Little Brushy Creek Trib 4.prj (project) ---

Proj Title=Little Brushy Creek Trib 4 Base Level Engineering
Current Plan=p01
Default Exp/Contr=0.3,0.1
English Units
Geom File=g01
Flow File=f01
Plan File=p01
BEGIN DESCRIPTION:
Little Brushy Creek Trib 4
END DESCRIPTION:

--- Little Brushy Creek Trib 4.p01 (plan) ---

Plan Title=Multiple Run
Short Identifier=Multiple
Geom File=g01
Flow File=f01
Subcritical Flow
K Sum by GR= 0
Std Step Tol= 0.01
Critical Tol= 0.01
Num of Std Step Trials= 20
Max Error Tol= 0.3
Flow Tol Ratio= 0.001
Split Flow NTrial= 30
Split Flow Tol= 0.02
Split Flow Ratio= 0.02
Log Output Level= 0
Friction Slope Method= 1
Unsteady Friction Slope Method= 2
Unsteady Bridges Friction Slope Method= 1
Parabolic Critical Depth
Global Vel Dist=  1 , 1 , 1
Global Log Level= 0
CheckData=True
Encroach Param= -1, 0, 0, 0
BEGIN DESCRIPTION:
Multiple Run
END DESCRIPTION:

--- Little Brushy Creek Trib 4.f01 (steady flow) ---

Flow Title=Multiple
Number of Profiles=7
Profile Names=10-year,25-year,50-year,1pct_min,100-year,1pct_plu,500-year
River Rch & RM= Little Brushy Cr,Reach-1,6687
     481     636     759     450     898    1791    1254
River Rch & RM= Little Brushy Cr,Reach-1,4909
     650     877    1061     637    1270    2535    1820
River Rch & RM= Little Brushy Cr,Reach-1,1234
     650     877    1060     635    1268    2530    1814
Boundary for River Rch & Prof#=Little Brushy Cr,Reach-1,1
Up Type=0
Dn Type=3
Dn Slope=0.005
Boundary for River Rch & Prof#=Little Brushy Cr,Reach-1,2
Up Type=0
Dn Type=3
Dn Slope=0.005
Boundary for River Rch & Prof#=Little Brushy Cr,Reach-1,3
Up Type=0
Dn Type=3
Dn Slope=0.005
Boundary for River Rch & Prof#=Little Brushy Cr,Reach-1,4
Up Type=0
Dn Type=3
Dn Slope=0.005
Boundary for River Rch & Prof#=Little Brushy Cr,Reach-1,5
Up Type=0
Dn Type=3
Dn Slope=0.005
Boundary for River Rch & Prof#=Little Brushy Cr,Reach-1,6
Up Type=0
Dn Type=3
Dn Slope=0.005
Boundary for River Rch & Prof#=Little Brushy Cr,Reach-1,7
Up Type=0
Dn Type=3
Dn Slope=0.005

--- Little Brushy Creek Trib 4.g01 (geometry) ---

Geom Title=Existing Conditions

River Reach=Little Brushy Cr,Reach-1
Reach XY= 30
      2637376.00      6930511.00      2637242.67      6930327.39
      2637166.00      6930349.76      2636986.48      6930170.80
      2636920.17      6929908.70      2636784.16      6929767.05
      2636653.01      6929537.48      2636258.47      6929294.35
      2636232.67      6929168.50      2636125.70      6929203.74
      2636089.61      6929175.03      2635927.84      6928854.87
      2635964.89      6928750.95      2635642.50      6928478.05
      2635459.36      6928194.29      2635286.63      6928071.00
      2635196.39      6927880.84      2635082.06      6927769.14
      2634889.48      6927674.56      2634779.62      6927509.50
      2634722.18      6927262.58      2634596.13      6927080.77
      2634165.50      6926912.22      2633787.83      6926909.36
      2633746.43      6926830.74      2633662.80      6926797.36
      2633382.05      6926519.12      2633276.01      6926468.53
      2633136.46      6926510.18      2633076.00      6926461.00

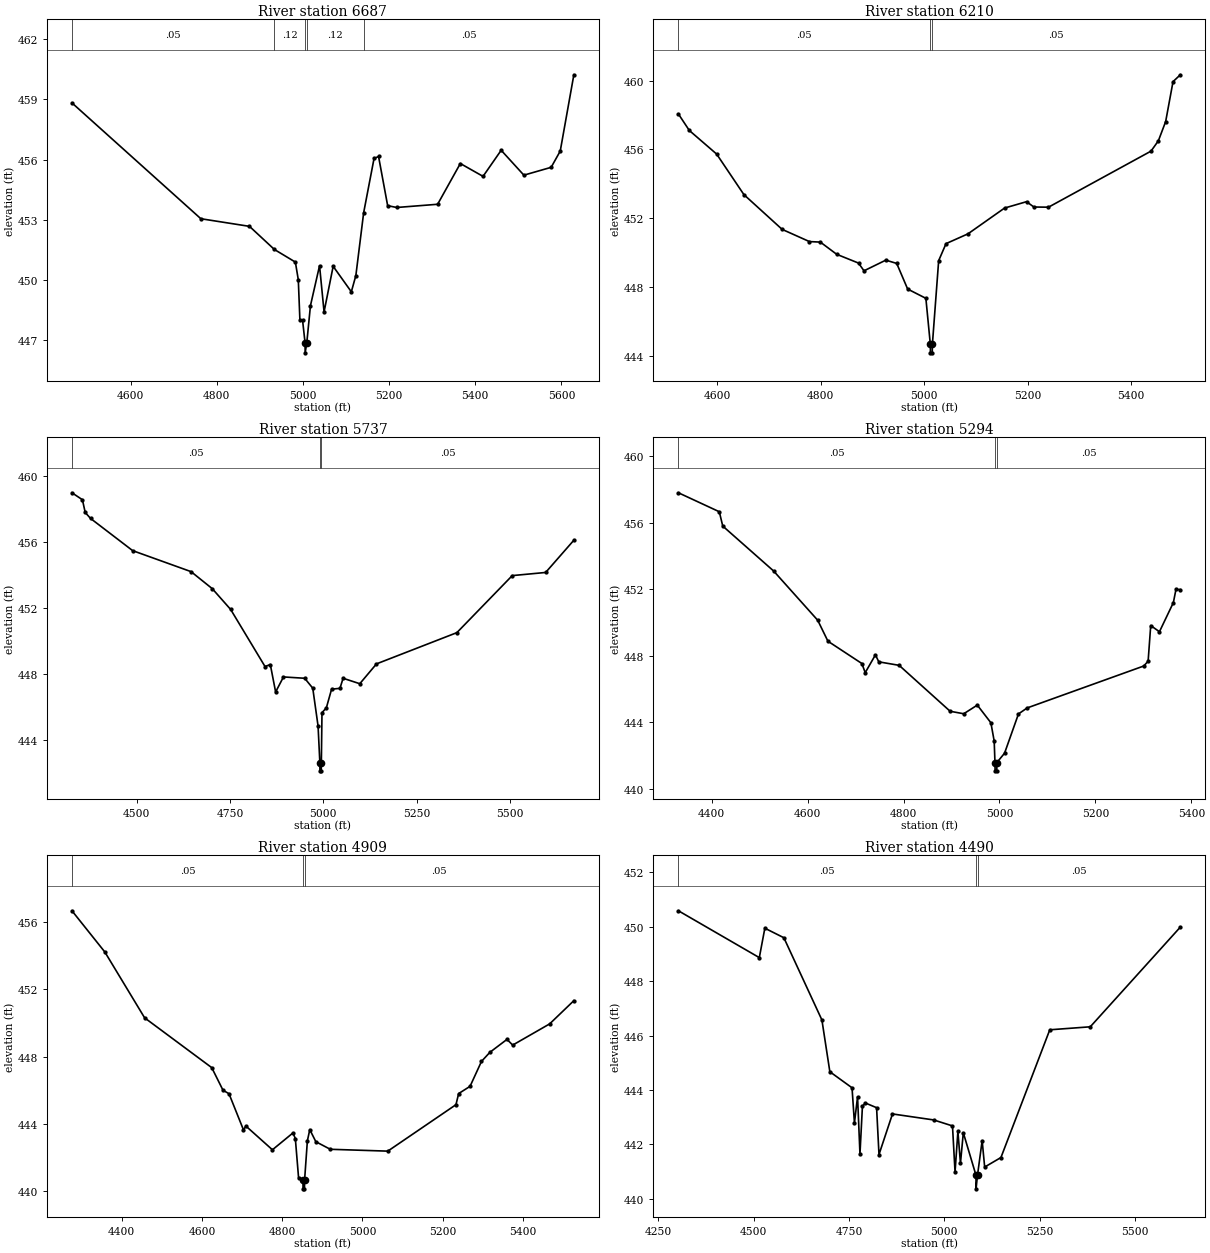
Type RM Length L Ch R = 1,6687,477,477,477
BEGIN DESCRIPTION:
Little Brushy Creek Trib 4 14.0
END DESCRIPTION:
XS GIS Cut Line= 3
      2637766.22      6930098.63      2637376.00      6930461.00
      2636775.98      6930661.01
#Sta/Elev= 30
  4463.9  458.82  4763.1  453.05  4876.0  452.67  4933.7  451.52  4982.5  450.89
  4989.3  450.01  4993.0  448.01  4999.1  448.01  5005.0  446.87  5005.2  446.37
  5009.0  446.87  5017.5  448.72  5038.6  450.71  5049.1  448.41  5070.2  450.68
  5112.4  449.41  5122.9  450.22  5141.0  453.35  5165.1  456.05  5175.6  456.15
  5196.7  453.70  5217.8  453.61  5312.7  453.77  5365.4  455.80  5418.1  455.16
  5460.2  456.46  5512.9  455.22  5576.2  455.61  5597.3  456.42  5628.9  460.22
#Mann=5,-1,0
  4463.9    0.05       0  4933.7    0.12       0  5005.0    0.07       0
  5009.0    0.12       0  5141.0    0.05       0
Bank Sta=5005,5009
Exp/Cntr=0.3,0.1

Type RM Length L Ch R = 1,6210,473,473,473
BEGIN DESCRIPTION:
Little Brushy Creek Trib 4 13.0
END DESCRIPTION:
XS GIS Cut Line= 3
      2637475.99      6930061.00      2637026.00      6930211.00
      2636676.01      6930560.99
#Sta/Elev= 30
  4525.4  458.06  4546.5  457.10  4599.2  455.73  4651.9  453.37  4725.7  451.35
  4778.4  450.64  4799.5  450.61  4831.1  449.90  4873.2  449.39  4883.8  448.94
  4925.9  449.56  4947.0  449.37  4968.1  447.88  5003.3  447.34  5011.9  444.67
  5012.1  444.17  5015.6  444.17  5015.9  444.67  5028.0  449.53  5042.2  450.52
  5084.6  451.09  5155.3  452.59  5197.7  452.96  5211.9  452.65  5240.1  452.64
  5438.1  455.90  5452.3  456.50  5466.4  457.62  5480.6  459.94  5494.7  460.34
#Mann=3,-1,0
  4525.4    0.05       0  5011.9    0.04       0  5015.9    0.05       0
Bank Sta=5011.9,5015.9
Exp/Cntr=0.3,0.1

Type RM Length L Ch R = 1,5737,443,443,443
BEGIN DESCRIPTION:
Little Brushy Creek Trib 4 12.0
END DESCRIPTION:
XS GIS Cut Line= 3
      2637325.99      6929361.01      2636826.00      6929811.00
      2636525.99      6930411.01
#Sta/Elev= 30
  4327.1  458.96  4355.1  458.54  4362.6  457.77  4376.8  457.41  4489.6  455.46
  4645.9  454.19  4702.7  453.16  4752.0  451.90  4843.9  448.45  4858.1  448.57
  4872.3  446.91  4893.3  447.82  4950.1  447.74  4971.7  447.14  4985.9  444.85
  4990.7  442.64  4990.9  442.14  4994.4  442.14  4994.7  442.64  4996.4  445.66
  5008.1  445.95  5022.1  447.08  5044.5  447.13  5052.9  447.74  5097.6  447.41
  5142.3  448.61  5357.5  450.50  5505.7  453.95  5595.1  454.14  5670.6  456.09
#Mann=3,-1,0
  4327.1    0.05       0  4990.7    0.04       0  4994.7    0.05       0
Bank Sta=4990.7,4994.7
Exp/Cntr=0.3,0.1

Type RM Length L Ch R = 1,5294,385,385,385
BEGIN DESCRIPTION:
Little Brushy Creek Trib 4 11.0
END DESCRIPTION:
XS GIS Cut Line= 3
      2637038.34      6928982.75      2636576.00      6929461.00
      2636425.99      6929811.02
#Sta/Elev= 30
  4330.9  457.79  4416.1  456.65  4423.3  455.79  4529.3  453.09  4621.2  450.13
  4642.5  448.87  4713.2  447.53  4720.2  446.98  4741.5  448.05  4748.5  447.63
  4790.9  447.42  4897.2  444.66  4925.5  444.51  4953.8  445.03  4982.1  443.97
  4989.0  442.87  4990.6  441.58  4990.9  441.08  4994.4  441.08  4994.6  441.58
  5010.6  442.14  5039.6  444.50  5057.7  444.86  5300.7  447.38  5309.8  447.67
  5315.2  449.81  5333.4  449.44  5362.4  451.19  5367.8  451.98  5376.9  451.97
#Mann=3,-1,0
  4330.9    0.05       0  4990.6    0.04       0  4994.6    0.05       0
Bank Sta=4990.6,4994.6
Exp/Cntr=0.3,0.1

Type RM Length L Ch R = 1,4909,419,419,419
BEGIN DESCRIPTION:
Little Brushy Creek Trib 4 10.0
END DESCRIPTION:
XS GIS Cut Line= 3
      2636855.92      6928888.36      2636255.95      6929288.34
      2635857.29      6929637.17
#Sta/Elev= 30
  4276.2  456.66  4358.2  454.21  4457.3  450.30  4624.6  447.34  4652.6  446.00
  4667.6  445.79  4703.7  443.64  4709.7  443.87  4775.8  442.46  4826.9  443.46
  4832.9  443.13  4841.0  440.79  4851.9  440.64  4852.2  440.14  4855.7  440.14
  4855.9  440.64  4862.9  442.99  4868.9  443.66  4884.0  442.94  4920.0  442.49
  5063.3  442.38  5233.2  445.14  5239.9  445.80  5268.3  446.23  5296.8  447.71
  5317.7  448.25  5360.4  449.02  5374.6  448.68  5466.7  449.94  5527.0  451.32
#Mann=3,-1,0
  4276.2    0.05       0  4851.9    0.03       0  4855.9    0.05       0
Bank Sta=4851.9,4855.9
Exp/Cntr=0.3,0.1

Type RM Length L Ch R = 1,4490,452,452,452
BEGIN DESCRIPTION:
Mapping XS 5ad356e9
END DESCRIPTION:
XS GIS Cut Line= 3
      2636610.02      6928667.59      2636052.69      6929092.10
      2635590.70      6929499.43
#Sta/Elev= 30
  4302.4  450.58  4514.6  448.86  4529.1  449.94  4579.0  449.59  4678.8  446.57
  4699.6  444.67  4757.8  444.08  4764.1  442.79  4772.3  443.75  4778.6  441.65
  4785.1  443.41  4793.1  443.52  4822.2  443.35  4828.5  441.63  4863.9  443.12
  4971.9  442.90  5021.3  442.68  5028.0  440.99  5035.5  442.48  5042.2  441.31
  5049.7  442.43  5082.9  440.87  5083.1  440.37  5086.9  440.87  5099.1  442.14
  5105.7  441.17  5148.4  441.52  5276.5  446.21  5382.7  446.32  5618.9  449.98
#Mann=3,-1,0
  4302.4    0.05       0  5082.9    0.03       0  5086.9    0.05       0
Bank Sta=5082.9,5086.9
Exp/Cntr=0.3,0.1

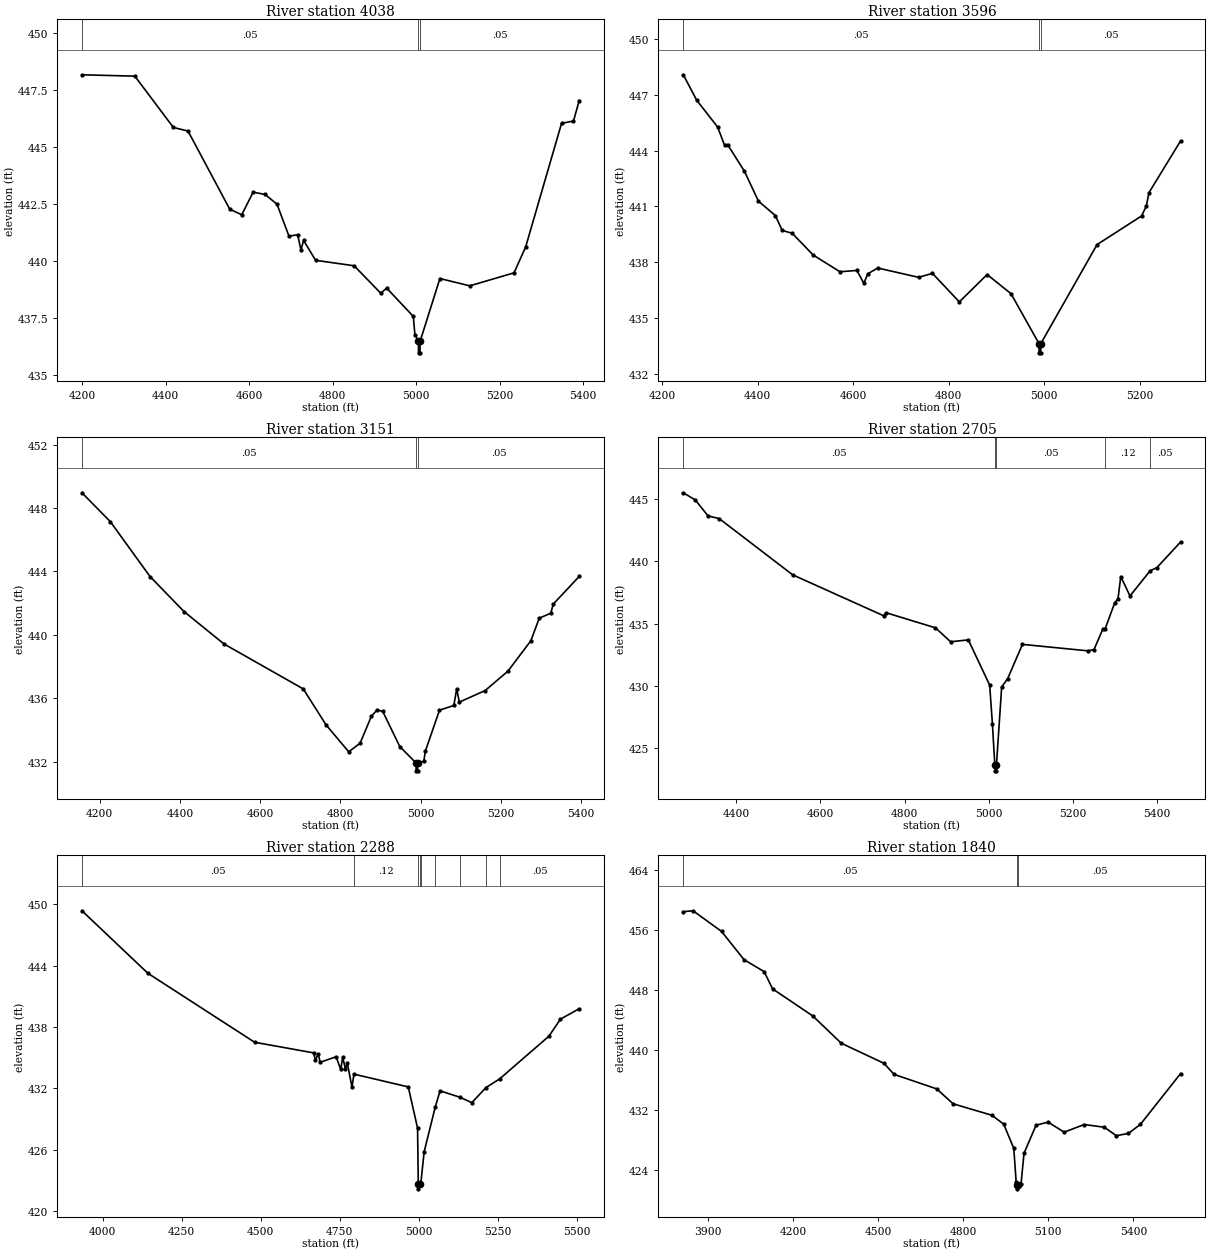
Type RM Length L Ch R = 1,4038,442,442,442
BEGIN DESCRIPTION:
Little Brushy Creek Trib 4 8.0
END DESCRIPTION:
XS GIS Cut Line= 3
      2636540.07      6928196.29      2635926.00      6928711.00
      2635625.97      6928961.02
#Sta/Elev= 30
  4199.1  448.18  4325.8  448.12  4418.1  445.87  4453.3  445.71  4553.4  442.28
  4582.1  442.04  4609.4  443.03  4638.0  442.93  4666.6  442.50  4695.3  441.10
  4716.1  441.16  4723.9  440.50  4730.4  440.91  4759.0  440.04  4851.4  439.80
  4915.1  438.60  4929.4  438.82  4993.2  437.58  4997.1  436.78  5005.5  436.48
  5005.8  435.98  5009.3  435.98  5009.5  436.48  5057.0  439.24  5128.6  438.92
  5234.7  439.49  5262.6  440.63  5348.6  446.05  5377.2  446.15  5390.9  447.05
#Mann=3,-1,0
  4199.1    0.05       0  5005.5    0.04       0  5009.5    0.05       0
Bank Sta=5005.5,5009.5
Exp/Cntr=0.3,0.1

Type RM Length L Ch R = 1,3596,445,445,445
BEGIN DESCRIPTION:
Little Brushy Creek Trib 4 7.0
END DESCRIPTION:
XS GIS Cut Line= 3
      2636075.99      6927811.01      2635626.00      6928411.00
      2635476.02      6928660.97
#Sta/Elev= 30
  4244.3  448.08  4272.4  446.71  4316.2  445.27  4330.7  444.29  4337.0  444.33
  4372.4  442.89  4401.6  441.29  4437.0  440.51  4451.6  439.71  4472.4  439.56
  4516.2  438.39  4572.4  437.49  4607.8  437.56  4622.4  436.87  4630.7  437.38
  4651.6  437.69  4737.0  437.19  4766.2  437.40  4822.4  435.87  4880.7  437.34
  4930.7  436.31  4989.2  433.63  4989.4  433.13  4992.9  433.13  4993.2  433.63
  5110.9  438.95  5204.2  440.49  5213.9  441.01  5219.8  441.75  5285.8  444.52
#Mann=3,-1,0
  4244.3    0.05       0  4989.2    0.04       0  4993.2    0.05       0
Bank Sta=4989.2,4993.2
Exp/Cntr=0.3,0.1

Type RM Length L Ch R = 1,3151,446,446,446
BEGIN DESCRIPTION:
Little Brushy Creek Trib 4 6.0
END DESCRIPTION:
XS GIS Cut Line= 3
      2635926.02      6927510.98      2635326.00      6928111.00
      2635075.98      6928411.03
#Sta/Elev= 30
  4156.1  448.96  4226.8  447.14  4325.8  443.68  4410.7  441.47  4509.7  439.44
  4707.7  436.60  4764.2  434.34  4820.8  432.64  4849.1  433.18  4877.4  434.88
  4891.5  435.28  4905.7  435.18  4948.1  432.97  4988.5  431.94  4988.8  431.44
  4992.3  431.44  4992.5  431.94  5007.9  432.04  5011.8  432.68  5047.0  435.26
  5082.8  435.56  5089.9  436.61  5096.4  435.77  5160.9  436.50  5217.5  437.72
  5274.8  439.64  5295.6  441.06  5324.2  441.37  5330.7  441.95  5395.2  443.69
#Mann=3,-1,0
  4156.1    0.05       0  4988.5    0.04       0  4992.5    0.05       0
Bank Sta=4988.5,4992.5
Exp/Cntr=0.3,0.1

Type RM Length L Ch R = 1,2705,417,417,417
BEGIN DESCRIPTION:
Little Brushy Creek Trib 4 5.0
END DESCRIPTION:
XS GIS Cut Line= 3
      2635676.01      6927360.99      2635076.00      6927761.00
      2634726.00      6928061.00
#Sta/Elev= 30
  4273.9  445.51  4302.5  444.93  4332.5  443.66  4359.5  443.43  4533.8  438.92
  4750.1  435.63  4756.2  435.87  4873.3  434.66  4909.4  433.54  4951.5  433.69
  5002.2  430.06  5008.7  426.96  5014.4  423.67  5014.7  423.17  5018.2  423.17
  5018.4  423.67  5030.7  429.90  5045.0  430.58  5080.1  433.33  5235.9  432.81
  5250.2  432.91  5271.6  434.59  5276.4  434.55  5299.6  436.68  5307.3  436.99
  5313.9  438.78  5335.8  437.22  5383.6  439.24  5399.5  439.49  5456.0  441.55
#Mann=5,-1,0
  4273.9    0.05       0  5014.4    0.04       0  5018.4    0.05       0
  5276.4    0.12       0  5383.6    0.05       0
Bank Sta=5014.4,5018.4
Exp/Cntr=0.3,0.1

Type RM Length L Ch R = 1,2288,448,448,448
BEGIN DESCRIPTION:
Little Brushy Creek Trib 4 4.0
END DESCRIPTION:
XS GIS Cut Line= 3
      2635644.27      6926887.24      2634776.00      6927511.00
      2634368.48      6927807.56
#Sta/Elev= 30
  3935.0  449.36  4143.4  443.25  4481.1  436.50  4667.7  435.46  4673.8  434.76
  4682.4  435.36  4688.6  434.54  4738.9  435.08  4753.6  433.85  4759.8  435.02
  4768.4  433.91  4774.5  434.44  4789.2  432.11  4795.4  433.38  4967.3  432.13
  4996.7  428.10  4999.0  422.66  4999.3  422.16  5003.0  422.66  5006.9  422.66
  5017.6  425.79  5052.3  430.12  5067.8  431.75  5131.5  431.11  5168.3  430.59
  5213.3  432.07  5256.2  432.91  5412.2  437.09  5448.8  438.76  5508.1  439.78
#Mann=9,-1,0
  3935.0    0.05       0  4795.4    0.12       0  4999.0    0.07       0
  5003.0    0.12       0  5006.9    0.05       0  5052.3    0.12       0
  5131.5    0.05       0  5213.3    0.12       0  5256.2    0.05       0
Bank Sta=4999,5003
Exp/Cntr=0.3,0.1

Type RM Length L Ch R = 1,1840,606,606,606
BEGIN DESCRIPTION:
Little Brushy Creek Trib 4 3.0
END DESCRIPTION:
XS GIS Cut Line= 3
      2635581.81      6926408.05      2634626.00      6927111.00
      2634225.97      6927511.03
#Sta/Elev= 30
  3814.0  458.45  3848.3  458.57  3948.6  455.82  4028.0  452.04  4099.0  450.44
  4128.3  448.15  4270.3  444.52  4370.6  440.88  4521.0  438.20  4556.5  436.72
  4706.9  434.78  4764.6  432.79  4901.2  431.26  4943.0  430.07  4978.5  426.84
  4986.9  422.36  4991.1  421.93  4991.4  421.43  4995.1  421.93  5004.0  422.05
  5014.6  426.18  5057.0  429.93  5099.5  430.34  5156.0  429.00  5226.7  430.02
  5297.5  429.66  5339.9  428.53  5382.3  428.83  5424.7  430.04  5566.2  436.82
#Mann=3,-1,0
  3814.0    0.05       0  4991.1    0.03       0  4995.1    0.05       0
Bank Sta=4991.1,4995.1
Exp/Cntr=0.3,0.1

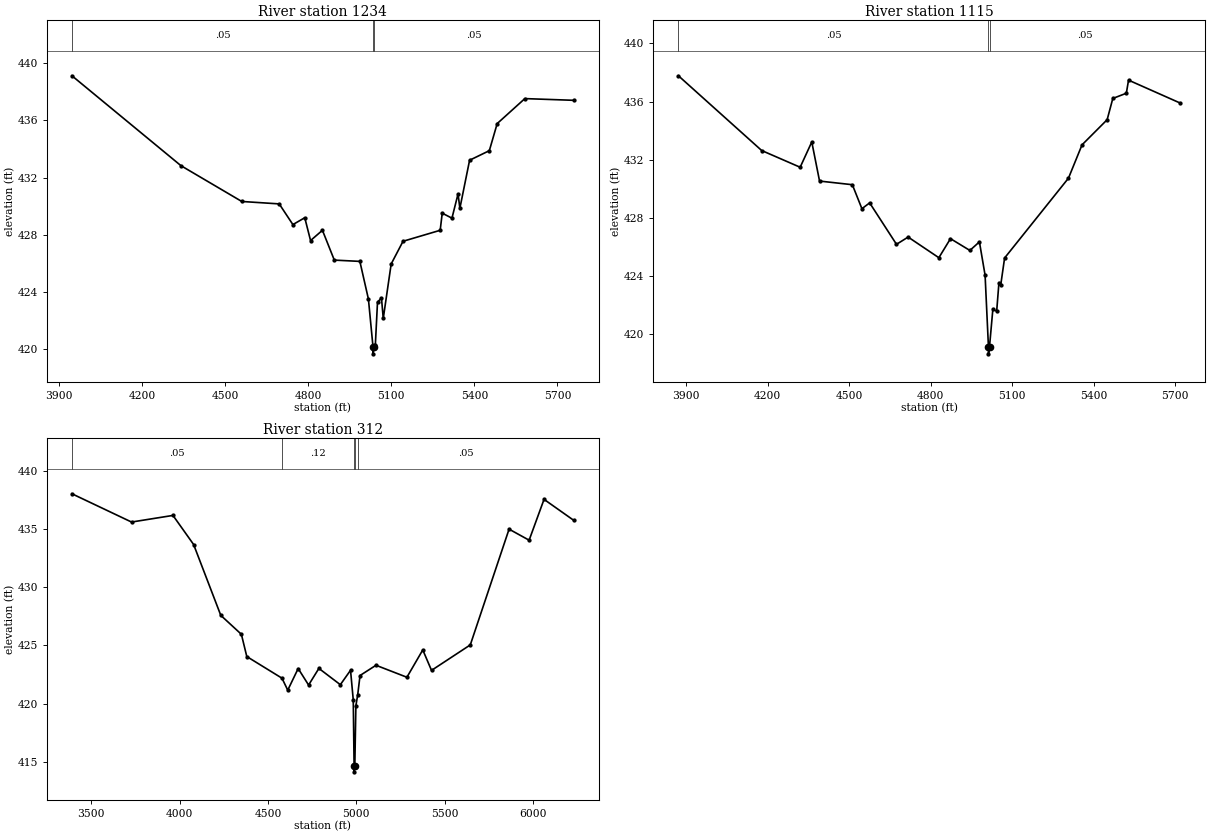
Type RM Length L Ch R = 1,1234,119,119,119
BEGIN DESCRIPTION:
Mapping XS 5a43cb9c
END DESCRIPTION:
XS GIS Cut Line= 5
      2634755.41      6926097.62      2634609.55      6926288.63
      2634074.83      6926924.04      2633786.63      6927260.85
      2633956.31      6927506.70
#Sta/Elev= 30
  3946.4  439.13  4340.0  432.83  4559.8  430.32  4695.0  430.15  4744.4  428.70
  4787.3  429.18  4808.2  427.58  4851.1  428.30  4894.0  426.21  4986.3  426.12
  5017.2  423.48  5033.7  420.14  5034.0  419.64  5037.7  420.14  5042.3  420.29
  5050.0  423.26  5064.3  423.56  5070.8  422.12  5099.4  425.94  5142.2  427.53
  5276.4  428.30  5283.8  429.50  5318.9  429.15  5340.9  430.85  5347.5  429.84
  5382.6  433.21  5453.9  433.88  5482.3  435.78  5582.2  437.53  5759.2  437.41
#Mann=3,-1,0
  3946.4    0.05       0  5033.7    0.03       0  5037.7    0.05       0
Bank Sta=5033.7,5037.7
Exp/Cntr=0.3,0.1

Type RM Length L Ch R = 1,1115,803,803,803
BEGIN DESCRIPTION:
Mapping XS 633b9557
END DESCRIPTION:
XS GIS Cut Line= 5
      2634666.86      6926028.84      2634527.97      6926254.54
      2633941.17      6926942.04      2633701.58      6927258.01
      2633875.18      6927480.22
#Sta/Elev= 30
  3871.9  437.78  4178.4  432.64  4320.0  431.49  4362.8  433.23  4391.4  430.54
  4512.1  430.29  4547.3  428.64  4575.8  429.04  4674.6  426.19  4717.4  426.69
  4830.5  425.27  4873.3  426.58  4944.7  425.77  4979.8  426.36  5000.7  424.07
  5013.0  419.16  5013.2  418.66  5017.0  419.16  5029.2  421.71  5043.4  421.60
  5051.7  423.56  5058.0  423.36  5072.5  425.25  5307.6  430.74  5357.5  433.03
  5450.0  434.76  5470.8  436.22  5520.6  436.58  5528.7  437.48  5719.3  435.90
#Mann=3,-1,0
  3871.9    0.05       0  5013.0    0.03       0  5017.0    0.05       0
Bank Sta=5013,5017
Exp/Cntr=0.3,0.1

Type RM Length L Ch R = 1,312,0,0,0
BEGIN DESCRIPTION:
Little Brushy Creek Trib 4 1.0
END DESCRIPTION:
XS GIS Cut Line= 5
      2634716.93      6925902.68      2633581.21      6926126.90
      2633341.36      6926509.85      2633220.52      6926770.29
      2633858.45      6927466.65
#Sta/Elev= 30
  3390.5  438.03  3727.8  435.60  3962.3  436.17  4079.2  433.67  4233.0  427.58
  4349.6  425.95  4380.2  424.04  4579.3  422.18  4612.0  421.15  4671.0  423.01
  4730.0  421.59  4788.3  423.02  4909.7  421.62  4967.4  422.86  4982.8  420.32
  4987.6  414.63  4987.8  414.13  4991.6  414.63  4997.7  419.81  5007.9  420.74
  5021.2  422.41  5111.5  423.29  5286.5  422.26  5376.4  424.61  5425.8  422.85
  5645.3  425.04  5864.8  434.99  5978.3  434.04  6062.7  437.55  6231.5  435.74
#Mann=5,-1,0
  3390.5    0.05       0  4579.3    0.12       0  4987.6    0.07       0
  4991.6    0.12       0  5007.9    0.05       0
Bank Sta=4987.6,4991.6
Exp/Cntr=0.3,0.1

Chan Stop Cuts=-1