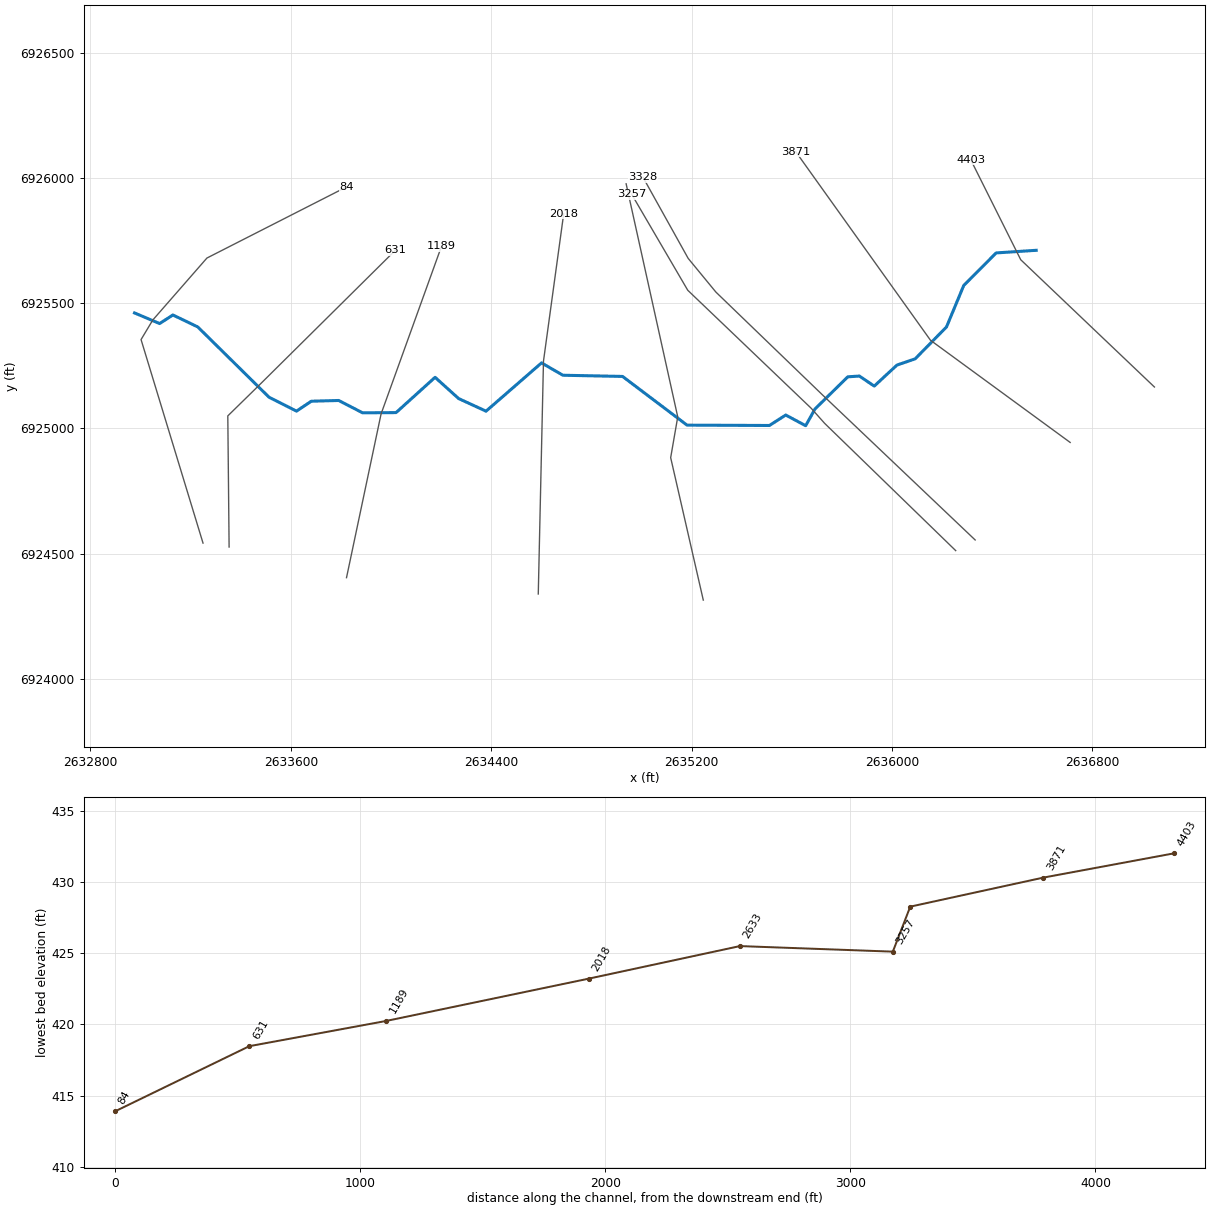
--- Little Brushy Creek Trib 5.prj (project) ---

Proj Title=Little Brushy Creek Trib 5 Base Level Engineering
Current Plan=p01
Default Exp/Contr=0.3,0.1
English Units
Geom File=g01
Flow File=f01
Plan File=p01
BEGIN DESCRIPTION:
Little Brushy Creek Trib 5
END DESCRIPTION:

--- Little Brushy Creek Trib 5.p01 (plan) ---

Plan Title=Multiple Run
Short Identifier=Multiple
Geom File=g01
Flow File=f01
Subcritical Flow
K Sum by GR= 0
Std Step Tol= 0.01
Critical Tol= 0.01
Num of Std Step Trials= 20
Max Error Tol= 0.3
Flow Tol Ratio= 0.001
Split Flow NTrial= 30
Split Flow Tol= 0.02
Split Flow Ratio= 0.02
Log Output Level= 0
Friction Slope Method= 1
Unsteady Friction Slope Method= 2
Unsteady Bridges Friction Slope Method= 1
Parabolic Critical Depth
Global Vel Dist=  1 , 1 , 1
Global Log Level= 0
CheckData=True
Encroach Param= -1, 0, 0, 0
BEGIN DESCRIPTION:
Multiple Run
END DESCRIPTION:

--- Little Brushy Creek Trib 5.f01 (steady flow) ---

Flow Title=Multiple
Number of Profiles=7
Profile Names=10-year,25-year,50-year,1pct_min,100-year,1pct_plu,500-year
River Rch & RM= Little Brushy Cr,Reach-1,4403
     470     620     738     437     872    1739    1214
River Rch & RM= Little Brushy Cr,Reach-1,84
    2323    3251    4028    2459    4907    9790    7290
Boundary for River Rch & Prof#=Little Brushy Cr,Reach-1,1
Up Type=0
Dn Type=3
Dn Slope=0.005
Boundary for River Rch & Prof#=Little Brushy Cr,Reach-1,2
Up Type=0
Dn Type=3
Dn Slope=0.005
Boundary for River Rch & Prof#=Little Brushy Cr,Reach-1,3
Up Type=0
Dn Type=3
Dn Slope=0.005
Boundary for River Rch & Prof#=Little Brushy Cr,Reach-1,4
Up Type=0
Dn Type=3
Dn Slope=0.005
Boundary for River Rch & Prof#=Little Brushy Cr,Reach-1,5
Up Type=0
Dn Type=3
Dn Slope=0.005
Boundary for River Rch & Prof#=Little Brushy Cr,Reach-1,6
Up Type=0
Dn Type=3
Dn Slope=0.005
Boundary for River Rch & Prof#=Little Brushy Cr,Reach-1,7
Up Type=0
Dn Type=3
Dn Slope=0.005

--- Little Brushy Creek Trib 5.g01 (geometry) ---

Geom Title=Existing Conditions

River Reach=Little Brushy Cr,Reach-1
Reach XY= 30
      2636576.00      6925711.00      2636416.19      6925700.54
      2636286.76      6925570.68      2636217.86      6925404.94
      2636092.67      6925277.65      2636019.95      6925252.80
      2635929.40      6925168.83      2635869.95      6925209.01
      2635823.71      6925205.88      2635692.73      6925077.43
      2635655.63      6925010.76      2635576.04      6925053.39
      2635510.84      6925011.66      2635181.86      6925013.06
      2634924.53      6925207.45      2634686.50      6925212.24
      2634600.96      6925261.50      2634379.41      6925068.77
      2634269.95      6925119.16      2634176.00      6925203.92
      2634020.14      6925063.05      2633886.51      6925062.21
      2633791.16      6925111.47      2633681.86      6925108.55
      2633622.68      6925069.04      2633512.79      6925124.61
      2633228.29      6925405.19      2633129.23      6925452.78
      2633076.06      6925418.57      2632976.00      6925461.00

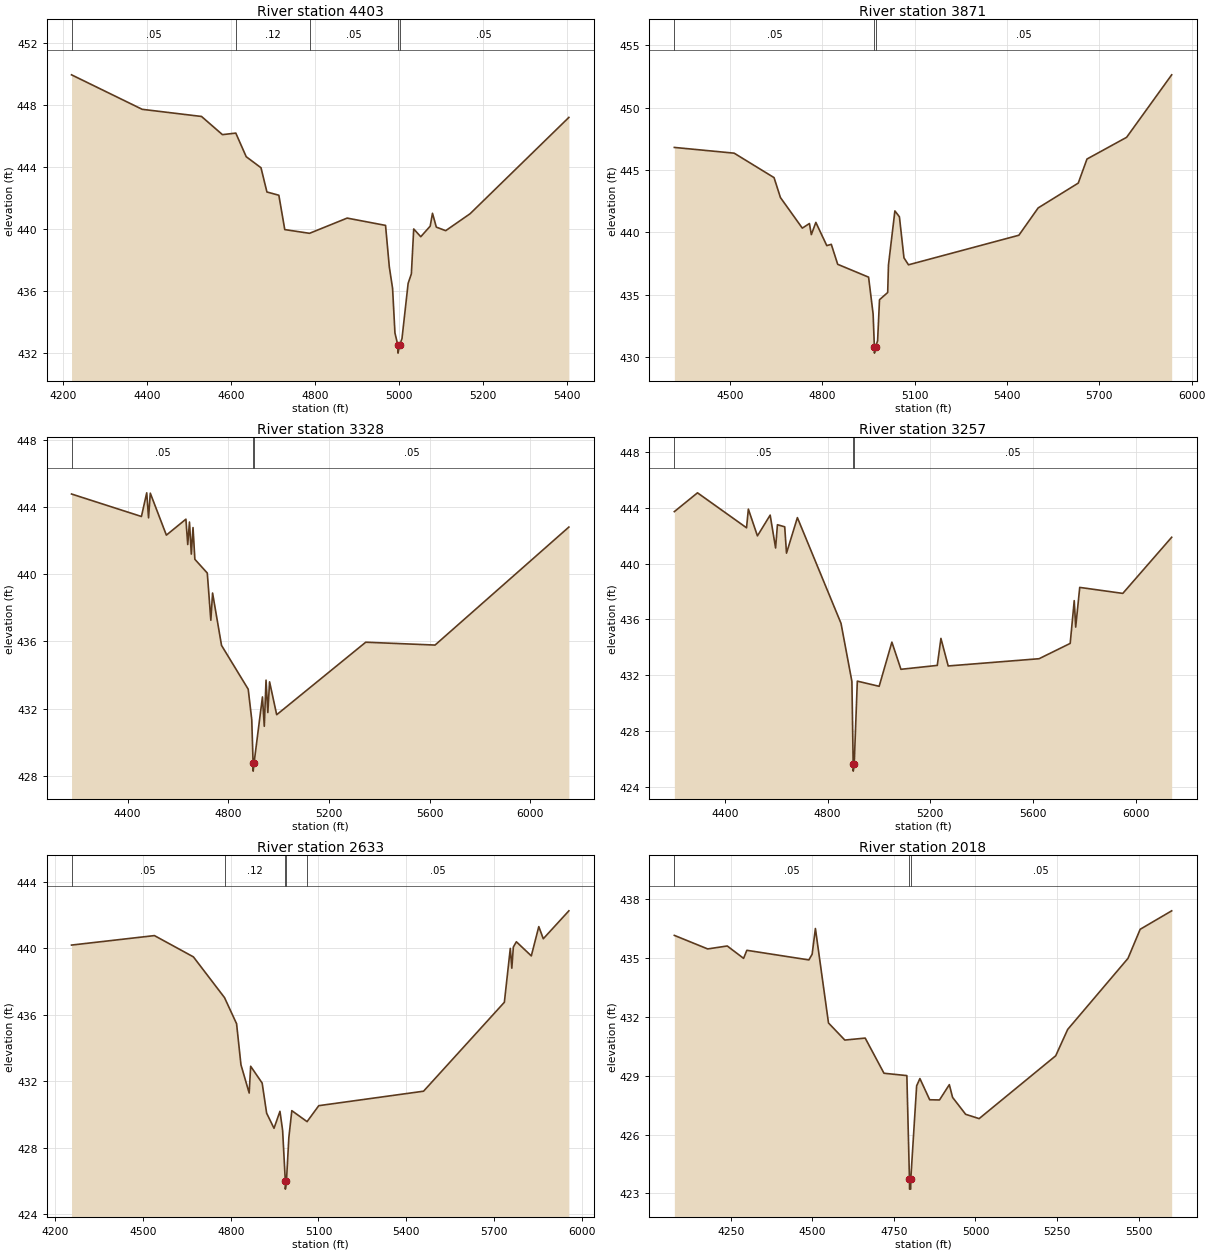
Type RM Length L Ch R = 1,4403,532,532,532
BEGIN DESCRIPTION:
Little Brushy Creek Trib 5 3.0
END DESCRIPTION:
XS GIS Cut Line= 3
      2637048.04      6925165.29      2636514.28      6925673.33
      2636314.28      6926073.32
#Sta/Elev= 30
  4220.6  449.92  4388.9  447.70  4530.1  447.24  4579.9  446.07  4611.7  446.17
  4636.5  444.65  4671.7  443.94  4685.8  442.38  4714.2  442.17  4728.3  439.96
  4787.2  439.72  4876.8  440.70  4968.2  440.23  4977.2  437.56  4985.0  436.17
  4990.6  433.31  4997.6  432.51  4997.9  432.01  5001.6  432.51  5007.4  432.95
  5022.0  436.50  5029.7  437.11  5035.3  440.00  5052.1  439.50  5074.5  440.18
  5080.0  441.01  5089.1  440.12  5111.4  439.89  5169.5  440.98  5404.7  447.18
#Mann=5,-1,0
  4220.6    0.05       0  4611.7    0.12       0  4787.2    0.05       0
  4997.6    0.04       0  5001.6    0.05       0
Bank Sta=4997.6,5001.6
Exp/Cntr=0.3,0.1

Type RM Length L Ch R = 1,3871,543,543,543
BEGIN DESCRIPTION:
Mapping XS 51763045
END DESCRIPTION:
XS GIS Cut Line= 3
      2636711.63      6924943.97      2636153.93      6925351.94
      2635615.72      6926105.00
#Sta/Elev= 30
  4318.5  446.80  4512.9  446.34  4642.6  444.38  4663.4  442.78  4734.5  440.33
  4757.6  440.70  4763.8  439.81  4778.5  440.79  4814.0  438.93  4828.7  439.03
  4849.5  437.43  4949.9  436.40  4964.6  433.45  4968.7  430.81  4969.0  430.31
  4972.7  430.81  4979.2  431.30  4985.4  434.59  5012.0  435.17  5014.5  437.37
  5035.4  441.71  5050.1  441.24  5064.9  437.95  5079.6  437.39  5438.4  439.76
  5501.1  441.95  5631.4  443.94  5659.8  445.87  5788.6  447.61  5935.1  452.62
#Mann=3,-1,0
  4318.5    0.05       0  4968.7    0.03       0  4972.7    0.05       0
Bank Sta=4968.7,4972.7
Exp/Cntr=0.3,0.1

Type RM Length L Ch R = 1,3328,71,71,71
BEGIN DESCRIPTION:
Mapping XS 1328c22d
END DESCRIPTION:
XS GIS Cut Line= 5
      2636332.32      6924554.63      2635724.68      6925131.88
      2635297.16      6925544.21      2635186.48      6925678.76
      2635006.38      6926002.08
#Sta/Elev= 30
  4177.4  444.78  4455.2  443.44  4476.2  444.85  4483.5  443.36  4490.4  444.83
  4554.3  442.33  4631.9  443.28  4639.2  441.77  4646.1  443.11  4653.4  441.20
  4660.2  442.78  4667.5  440.89  4716.9  440.07  4731.0  437.26  4737.9  438.88
  4773.5  435.76  4879.5  433.15  4893.6  431.34  4898.9  428.77  4899.2  428.27
  4902.9  428.77  4936.1  432.69  4943.4  430.94  4950.3  433.69  4957.5  431.76
  4964.4  433.59  4992.7  431.63  5346.5  435.95  5622.0  435.78  6153.8  442.81
#Mann=3,-1,0
  4177.4    0.05       0  4898.9    0.03       0  4902.9    0.05       0
Bank Sta=4898.9,4902.9
Exp/Cntr=0.3,0.1

Type RM Length L Ch R = 1,3257,624,624,624
BEGIN DESCRIPTION:
Mapping XS a50e5236
END DESCRIPTION:
XS GIS Cut Line= 5
      2636254.60      6924512.12      2635731.62      6925019.90
      2635677.37      6925080.67      2635184.75      6925551.59
      2634960.56      6925935.30
#Sta/Elev= 30
  4203.7  443.74  4293.9  445.09  4484.8  442.58  4491.9  443.92  4527.2  442.00
  4576.8  443.49  4597.9  441.13  4605.1  442.80  4633.4  442.65  4640.4  440.76
  4682.8  443.31  4852.6  435.72  4895.0  431.55  4900.0  425.61  4900.2  425.11
  4904.0  425.61  4916.1  431.57  5001.1  431.20  5050.7  434.37  5085.9  432.42
  5227.4  432.70  5241.6  434.64  5269.9  432.66  5623.7  433.18  5744.9  434.28
  5760.6  437.35  5766.3  435.45  5782.0  438.30  5949.7  437.87  6140.0  441.90
#Mann=3,-1,0
  4203.7    0.05       0  4900.0    0.03       0  4904.0    0.05       0
Bank Sta=4900,4904
Exp/Cntr=0.3,0.1

Type RM Length L Ch R = 1,2633,615,615,615
BEGIN DESCRIPTION:
Mapping XS 2867b9c1
END DESCRIPTION:
XS GIS Cut Line= 4
      2635246.82      6924314.56      2635116.61      6924883.19
      2635144.82      6925045.95      2634938.76      6925976.48
#Sta/Elev= 30
  4255.2  440.18  4538.8  440.75  4672.2  439.47  4778.6  437.02  4819.9  435.45
  4834.9  432.98  4863.0  431.28  4868.1  432.89  4907.4  431.88  4922.7  430.07
  4948.0  429.16  4968.3  430.18  4977.4  429.04  4986.6  426.00  4986.8  425.50
  4990.6  426.00  4998.7  428.60  5008.9  430.22  5061.1  429.56  5101.1  430.52
  5459.6  431.39  5736.1  436.74  5756.4  439.98  5761.6  438.79  5766.8  440.06
  5777.1  440.38  5828.3  439.53  5853.9  441.29  5869.3  440.56  5956.8  442.24
#Mann=5,-1,0
  4255.2    0.05       0  4778.6    0.12       0  4986.6    0.07       0
  4990.6    0.12       0  5061.1    0.05       0
Bank Sta=4986.6,4990.6
Exp/Cntr=0.3,0.1

Type RM Length L Ch R = 1,2018,829,829,829
BEGIN DESCRIPTION:
Mapping XS 7a1cb87b
END DESCRIPTION:
XS GIS Cut Line= 3
      2634587.96      6924338.96      2634608.79      6925268.67
      2634689.44      6925856.62
#Sta/Elev= 30
  4077.6  436.14  4179.7  435.45  4239.7  435.60  4289.7  434.97  4299.7  435.38
  4489.7  434.89  4499.7  435.18  4509.7  436.49  4549.8  431.68  4599.8  430.81
  4662.2  430.91  4719.8  429.12  4789.8  429.00  4797.8  423.72  4798.1  423.22
  4801.6  423.22  4801.8  423.72  4819.8  428.48  4829.8  428.85  4859.8  427.77
  4889.8  427.76  4919.9  428.54  4929.9  427.89  4969.9  427.03  5011.2  426.81
  5245.8  430.01  5282.4  431.35  5467.2  434.97  5504.5  436.45  5601.0  437.39
#Mann=3,-1,0
  4077.6    0.05       0  4797.8    0.04       0  4801.8    0.05       0
Bank Sta=4797.8,4801.8
Exp/Cntr=0.3,0.1

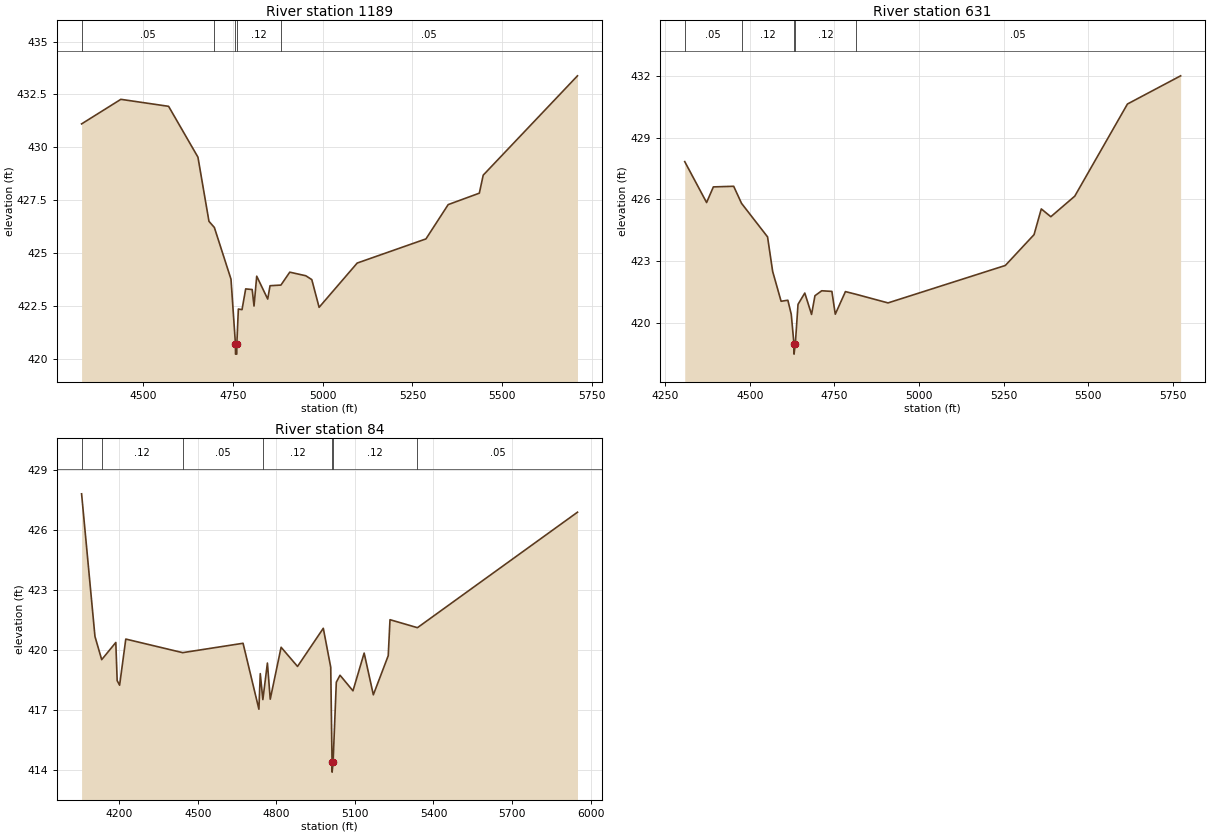
Type RM Length L Ch R = 1,1189,558,558,558
BEGIN DESCRIPTION:
Mapping XS ceee76dd
END DESCRIPTION:
XS GIS Cut Line= 3
      2633822.33      6924404.05      2633960.36      6925057.74
      2634201.90      6925727.83
#Sta/Elev= 30
  4328.9  431.11  4438.2  432.27  4571.1  431.94  4652.8  429.54  4683.5  426.51
  4698.5  426.22  4744.8  423.78  4757.1  420.74  4757.4  420.24  4760.9  420.24
  4761.1  420.74  4765.3  422.37  4775.5  422.34  4785.7  423.32  4803.8  423.29
  4808.9  422.51  4816.4  423.92  4847.0  422.84  4853.5  423.47  4883.8  423.50
  4908.4  424.11  4953.0  423.94  4969.7  423.76  4990.1  422.45  5096.1  424.54
  5287.5  425.68  5349.4  427.30  5436.1  427.84  5446.9  428.69  5709.3  433.38
#Mann=5,-1,0
  4328.9    0.05       0  4698.5    0.12       0  4757.1    0.03       0
  4761.1    0.12       0  4883.8    0.05       0
Bank Sta=4757.1,4761.1
Exp/Cntr=0.3,0.1

Type RM Length L Ch R = 1,631,547,547,547
BEGIN DESCRIPTION:
Mapping XS f7b592df
END DESCRIPTION:
XS GIS Cut Line= 4
      2633353.59      6924526.45      2633348.38      6925049.92
      2633473.38      6925172.32      2634017.66      6925711.39
#Sta/Elev= 30
  4307.9  427.83  4372.5  425.84  4392.5  426.60  4452.5  426.63  4475.7  425.80
  4552.5  424.17  4567.6  422.49  4592.5  421.04  4612.5  421.09  4622.5  420.41
  4630.5  418.97  4630.7  418.47  4634.5  418.97  4642.5  420.89  4662.5  421.44
  4682.5  420.40  4692.5  421.31  4712.5  421.55  4742.5  421.52  4752.5  420.41
  4782.5  421.51  4813.7  421.38  4908.3  420.96  5254.7  422.78  5339.6  424.28
  5360.9  425.53  5389.1  425.15  5459.8  426.15  5615.4  430.63  5772.4  432.00
#Mann=5,-1,0
  4307.9    0.05       0  4475.7    0.12       0  4630.5    0.03       0
  4634.5    0.12       0  4813.7    0.05       0
Bank Sta=4630.5,4634.5
Exp/Cntr=0.3,0.1

Type RM Length L Ch R = 1,84,0,0,0
BEGIN DESCRIPTION:
Mapping XS bbcc400b
END DESCRIPTION:
XS GIS Cut Line= 5
      2633249.41      6924542.13      2633002.02      6925354.61
      2633048.90      6925432.74      2633265.04      6925680.13
      2633821.66      6925963.64
#Sta/Elev= 30
  4056.3  427.83  4107.4  420.69  4133.1  419.53  4187.0  420.39  4192.2  418.48
  4201.5  418.25  4225.1  420.56  4442.3  419.88  4672.9  420.35  4733.4  417.05
  4738.6  418.83  4748.5  417.53  4765.9  419.36  4776.7  417.55  4818.2  420.15
  4880.9  419.19  4979.3  421.10  5007.7  419.15  5012.7  414.40  5013.0  413.90
  5016.7  414.40  5029.0  418.40  5043.2  418.75  5092.6  417.97  5135.3  419.86
  5170.4  417.77  5227.3  419.73  5234.0  421.53  5338.8  421.13  5949.9  426.91
#Mann=7,-1,0
  4056.3    0.05       0  4133.1    0.12       0  4442.3    0.05       0
  4748.5    0.12       0  5012.7    0.07       0  5016.7    0.12       0
  5338.8    0.05       0
Bank Sta=5012.7,5016.7
Exp/Cntr=0.3,0.1

Chan Stop Cuts=-1