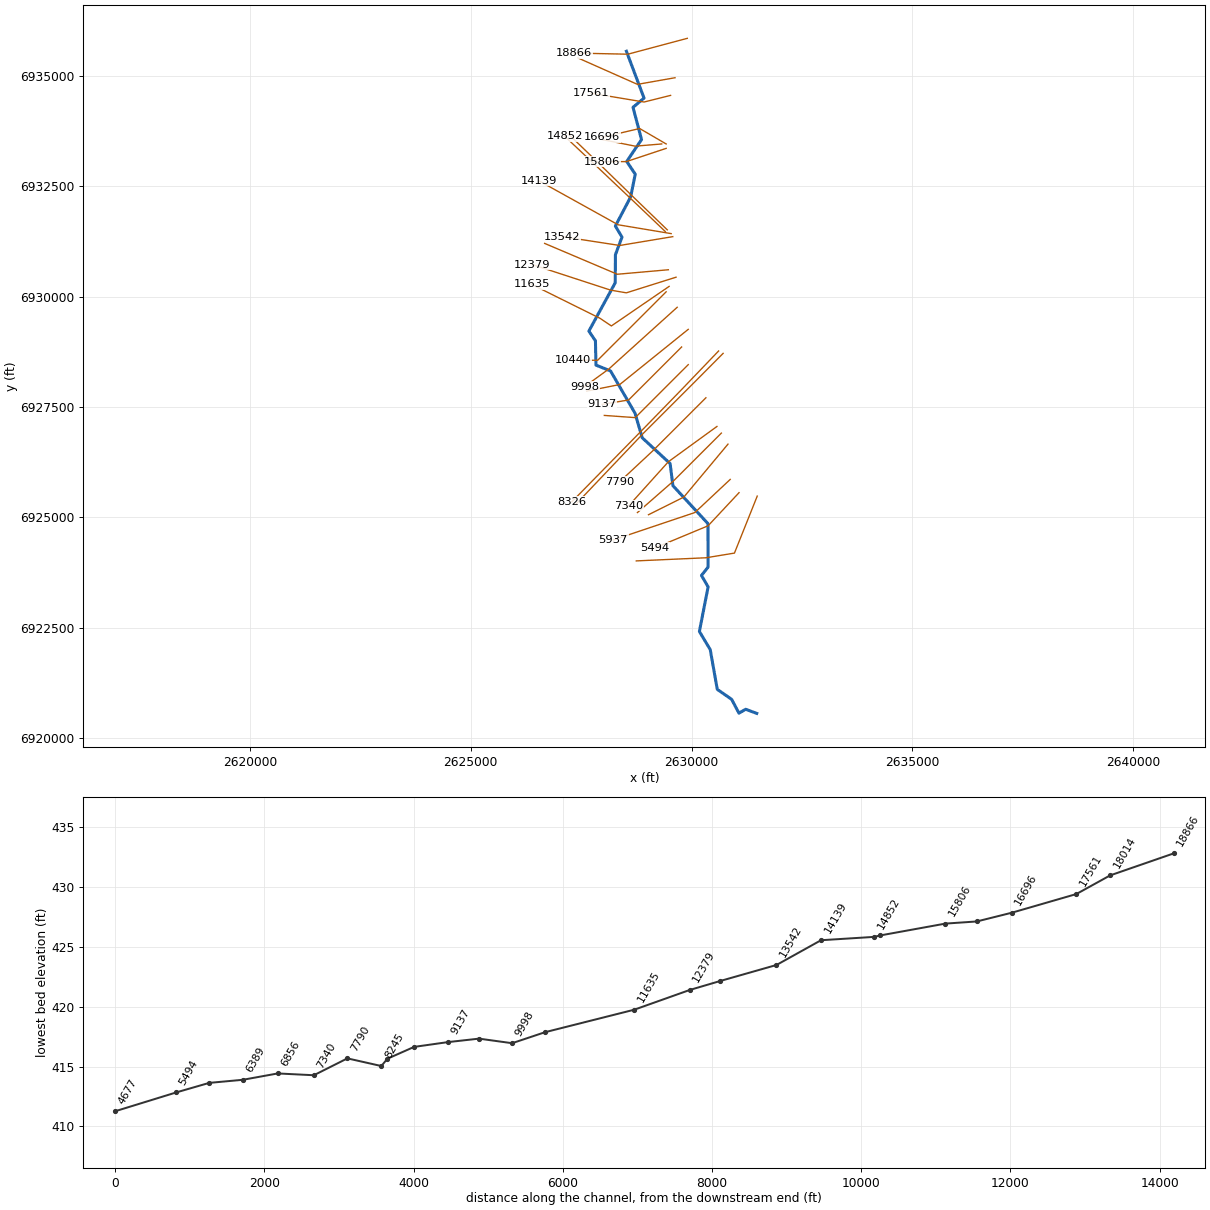
--- Little Brushy Creek Trib 6.prj (project) ---

Proj Title=Little Brushy Creek Trib 6 Base Level Engineering
Current Plan=p01
Default Exp/Contr=0.3,0.1
English Units
Geom File=g01
Flow File=f01
Plan File=p01
BEGIN DESCRIPTION:
Little Brushy Creek Trib 6
END DESCRIPTION:

--- Little Brushy Creek Trib 6.p01 (plan) ---

Plan Title=Multiple Run
Short Identifier=Multiple
Geom File=g01
Flow File=f01
Subcritical Flow
K Sum by GR= 0
Std Step Tol= 0.01
Critical Tol= 0.01
Num of Std Step Trials= 20
Max Error Tol= 0.3
Flow Tol Ratio= 0.001
Split Flow NTrial= 30
Split Flow Tol= 0.02
Split Flow Ratio= 0.02
Log Output Level= 0
Friction Slope Method= 1
Unsteady Friction Slope Method= 2
Unsteady Bridges Friction Slope Method= 1
Parabolic Critical Depth
Global Vel Dist=  1 , 1 , 1
Global Log Level= 0
CheckData=True
Encroach Param= -1, 0, 0, 0
BEGIN DESCRIPTION:
Multiple Run
END DESCRIPTION:

--- Little Brushy Creek Trib 6.f01 (steady flow) ---

Flow Title=Multiple
Number of Profiles=7
Profile Names=10-year,25-year,50-year,1pct_min,100-year,1pct_plu,500-year
River Rch & RM= Little Brushy Cr,Reach-1,18866
     461     607     724     428     855    1706    1191
River Rch & RM= Little Brushy Cr,Reach-1,17561
     633     850    1024     612    1221    2436    1736
River Rch & RM= Little Brushy Cr,Reach-1,14932
     833    1124    1359     813    1622    3235    2310
River Rch & RM= Little Brushy Cr,Reach-1,5494
     872    1183    1435     861    1717    3427    2463
Boundary for River Rch & Prof#=Little Brushy Cr,Reach-1,1
Up Type=0
Dn Type=3
Dn Slope=0.005
Boundary for River Rch & Prof#=Little Brushy Cr,Reach-1,2
Up Type=0
Dn Type=3
Dn Slope=0.005
Boundary for River Rch & Prof#=Little Brushy Cr,Reach-1,3
Up Type=0
Dn Type=3
Dn Slope=0.005
Boundary for River Rch & Prof#=Little Brushy Cr,Reach-1,4
Up Type=0
Dn Type=3
Dn Slope=0.005
Boundary for River Rch & Prof#=Little Brushy Cr,Reach-1,5
Up Type=0
Dn Type=3
Dn Slope=0.005
Boundary for River Rch & Prof#=Little Brushy Cr,Reach-1,6
Up Type=0
Dn Type=3
Dn Slope=0.005
Boundary for River Rch & Prof#=Little Brushy Cr,Reach-1,7
Up Type=0
Dn Type=3
Dn Slope=0.005

--- Little Brushy Creek Trib 6.g01 (geometry) ---

Geom Title=Existing Conditions

River Reach=Little Brushy Cr,Reach-1
Reach XY= 30
      2628526.00      6935561.00      2628925.06      6934500.51
      2628675.56      6934291.00      2628868.68      6933560.90
      2628533.81      6933064.41      2628726.11      6932776.77
      2628622.46      6932262.46      2628276.54      6931600.31
      2628426.50      6931350.84      2628277.04      6930950.56
      2628273.75      6930316.93      2627676.55      6929221.64
      2627825.25      6929000.32      2627836.96      6928450.62
      2628167.98      6928317.38      2628722.24      6927359.44
      2628883.86      6926804.83      2629515.53      6926220.83
      2629579.07      6925719.30      2630372.54      6924859.50
      2630376.05      6923876.34      2630225.49      6923686.03
      2630376.10      6923426.36      2630178.14      6922416.97
      2630423.93      6922005.14      2630583.48      6921104.93
      2630909.57      6920877.77      2631073.71      6920566.07
      2631226.20      6920653.97      2631476.00      6920561.00

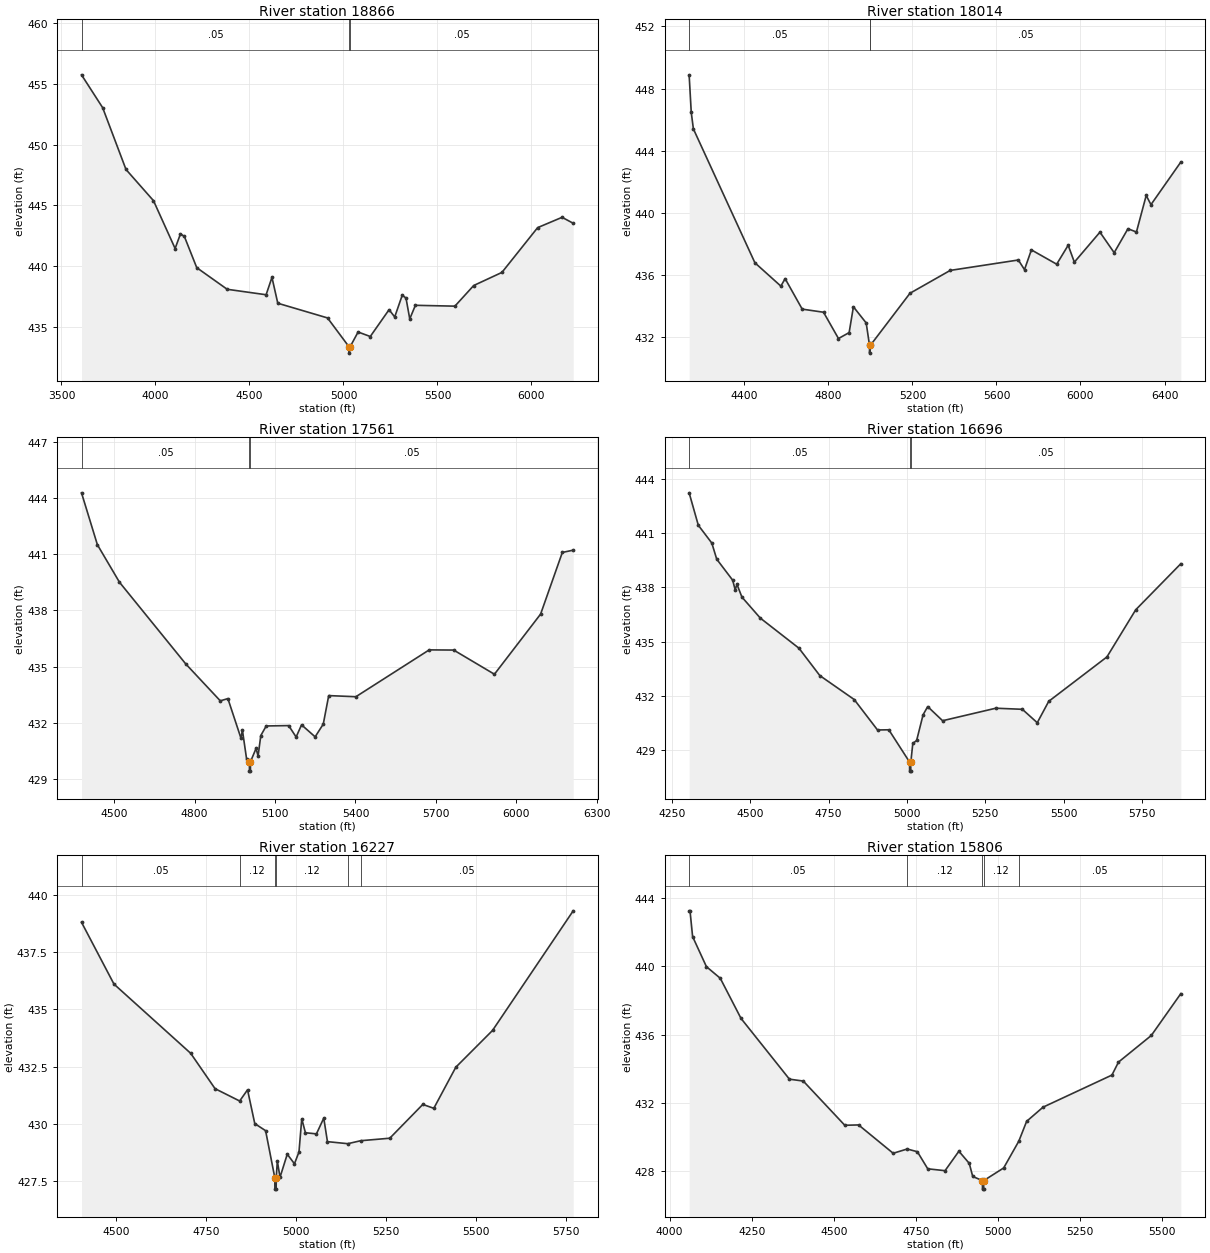
Type RM Length L Ch R = 1,18866,852,852,852
BEGIN DESCRIPTION:
Little Brushy Creek Trib 6 30.0
END DESCRIPTION:
XS GIS Cut Line= 3
      2629904.71      6935853.75      2628558.56      6935494.33
      2627336.94      6935520.41
#Sta/Elev= 30
  3606.7  455.75  3719.3  453.04  3843.4  447.95  3989.6  445.38  4104.6  441.44
  4133.2  442.65  4153.9  442.43  4219.7  439.86  4381.6  438.08  4588.6  437.63
  4619.7  439.06  4650.7  436.93  4915.3  435.72  5030.6  433.32  5030.8  432.82
  5034.6  433.32  5077.8  434.56  5142.6  434.19  5242.6  436.40  5272.6  435.80
  5312.6  437.59  5332.6  437.36  5352.6  435.64  5382.6  436.76  5592.7  436.69
  5692.7  438.39  5842.8  439.47  6032.8  443.16  6162.8  444.01  6221.9  443.52
#Mann=3,-1,0
  3606.7    0.05       0  5030.6    0.03       0  5034.6    0.05       0
Bank Sta=5030.6,5034.6
Exp/Cntr=0.3,0.1

Type RM Length L Ch R = 1,18014,453,453,453
BEGIN DESCRIPTION:
Little Brushy Creek Trib 6 29.0
END DESCRIPTION:
XS GIS Cut Line= 3
      2629625.98      6934961.00      2628776.00      6934811.00
      2627426.04      6935410.98
#Sta/Elev= 30
  4137.2  448.88  4147.3  446.46  4157.5  445.40  4450.3  436.79  4573.8  435.29
  4594.1  435.77  4675.4  433.81  4776.9  433.61  4848.0  431.92  4898.8  432.30
  4919.1  433.96  4980.0  432.92  4995.8  431.48  4996.0  430.98  4999.8  431.48
  5188.4  434.83  5379.9  436.30  5704.1  436.97  5733.5  436.35  5766.3  437.62
  5886.7  436.70  5941.4  437.92  5970.8  436.83  6092.6  438.76  6160.3  437.44
  6225.9  438.98  6266.3  438.77  6312.8  441.12  6335.4  440.53  6477.6  443.27
#Mann=3,-1,0
  4137.2    0.05       0  4995.8    0.03       0  4999.8    0.05       0
Bank Sta=4995.8,4999.8
Exp/Cntr=0.3,0.1

Type RM Length L Ch R = 1,17561,865,865,865
BEGIN DESCRIPTION:
Little Brushy Creek Trib 6 28.0
END DESCRIPTION:
XS GIS Cut Line= 3
      2629526.01      6934561.00      2628926.00      6934411.00
      2627726.03      6934610.99
#Sta/Elev= 30
  4377.6  444.27  4436.9  441.50  4519.3  439.50  4766.7  435.14  4895.6  433.17
  4923.9  433.29  4972.9  431.17  4978.0  431.62  4993.5  430.09  5004.2  429.92
  5004.5  429.42  5008.0  429.42  5008.2  429.92  5029.0  430.63  5036.6  430.23
  5046.8  431.32  5067.0  431.83  5150.7  431.85  5178.6  431.24  5198.8  431.89
  5249.5  431.25  5279.9  431.93  5300.2  433.45  5401.6  433.39  5675.3  435.89
  5766.6  435.88  5918.6  434.59  6091.0  437.80  6172.1  441.09  6212.6  441.21
#Mann=3,-1,0
  4377.6    0.05       0  5004.2    0.05       0  5008.2    0.05       0
Bank Sta=5004.2,5008.2
Exp/Cntr=0.3,0.1

Type RM Length L Ch R = 1,16696,469,469,469
BEGIN DESCRIPTION:
Little Brushy Creek Trib 6 26.0
END DESCRIPTION:
XS GIS Cut Line= 3
      2629425.98      6933461.01      2628826.00      6933811.00
      2627976.01      6933611.00
#Sta/Elev= 30
  4305.5  443.21  4334.8  441.42  4377.8  440.44  4393.5  439.55  4444.4  438.39
  4452.3  437.86  4458.0  438.16  4473.8  437.46  4532.5  436.30  4655.7  434.64
  4722.2  433.13  4831.8  431.81  4906.2  430.13  4942.2  430.14  5008.4  428.36
  5008.6  427.86  5012.1  427.86  5012.4  428.36  5018.7  429.39  5030.9  429.55
  5051.5  430.97  5066.2  431.42  5113.7  430.64  5283.3  431.33  5368.0  431.27
  5415.5  430.53  5452.1  431.71  5637.7  434.16  5729.5  436.76  5873.3  439.30
#Mann=3,-1,0
  4305.5    0.05       0  5008.4    0.03       0  5012.4    0.05       0
Bank Sta=5008.4,5012.4
Exp/Cntr=0.3,0.1

Type RM Length L Ch R = 1,16227,421,421,421
BEGIN DESCRIPTION:
Little Brushy Creek Trib 6 25.0
END DESCRIPTION:
XS GIS Cut Line= 3
      2629326.00      6933461.00      2628726.00      6933411.00
      2627976.03      6933560.99
#Sta/Elev= 30
  4402.9  438.82  4493.2  436.11  4706.4  433.08  4774.2  431.53  4842.6  430.99
  4864.5  431.48  4884.6  430.00  4914.7  429.69  4940.3  427.63  4940.5  427.13
  4944.0  427.13  4944.3  427.63  4947.3  428.36  4954.8  427.65  4974.9  428.66
  4994.9  428.24  5007.5  428.76  5015.2  430.21  5025.4  429.60  5056.0  429.55
  5076.4  430.24  5086.6  429.21  5143.2  429.12  5178.9  429.25  5259.9  429.36
  5351.7  430.84  5382.3  430.67  5443.5  432.47  5545.5  434.08  5769.8  439.32
#Mann=6,-1,0
  4402.9    0.05       0  4842.6    0.12       0  4940.3    0.05       0
  4944.3    0.12       0  5143.2    0.12       0  5178.9    0.05       0
Bank Sta=4940.3,4944.3
Exp/Cntr=0.3,0.1

Type RM Length L Ch R = 1,15806,874,874,874
BEGIN DESCRIPTION:
Little Brushy Creek Trib 6 24.0
END DESCRIPTION:
XS GIS Cut Line= 3
      2629426.02      6933361.01      2628526.00      6933061.00
      2627976.00      6933061.00
#Sta/Elev= 30
  4059.4  443.25  4062.1  443.25  4070.0  441.74  4112.1  439.98  4154.3  439.30
  4217.5  436.95  4365.1  433.39  4407.3  433.28  4533.8  430.69  4575.9  430.71
  4681.3  429.05  4724.1  429.30  4755.1  429.14  4786.7  428.14  4839.4  428.03
  4881.6  429.17  4913.2  428.46  4923.8  427.69  4953.4  427.45  4953.6  426.95
  4957.1  426.95  4957.4  427.45  5018.1  428.19  5064.3  429.76  5088.1  430.92
  5138.1  431.75  5348.1  433.63  5368.1  434.39  5468.1  435.95  5558.1  438.40
#Mann=5,-1,0
  4059.4    0.05       0  4724.1    0.12       0  4953.4    0.07       0
  4957.4    0.12       0  5064.3    0.05       0
Bank Sta=4953.4,4957.4
Exp/Cntr=0.3,0.1

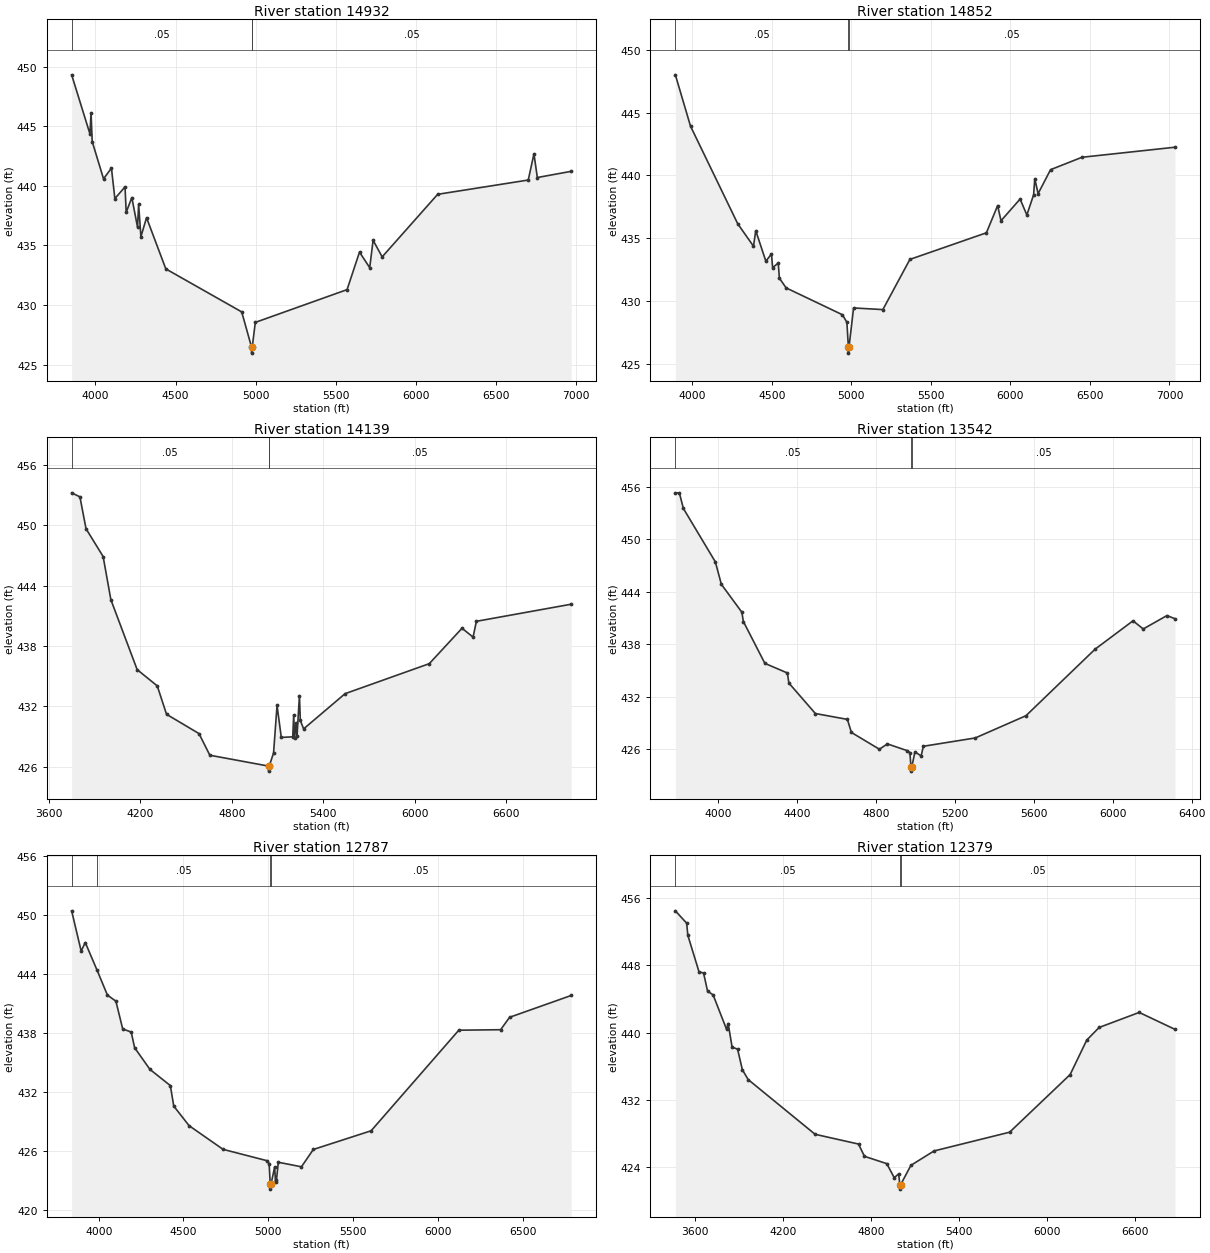
Type RM Length L Ch R = 1,14932,80,80,80
BEGIN DESCRIPTION:
Mapping XS 522c41e8
END DESCRIPTION:
XS GIS Cut Line= 4
      2629451.58      6931515.18      2628639.06      6932301.66
      2627774.48      6933145.41      2627212.54      6933686.54
#Sta/Elev= 30
  3851.5  449.32  3965.7  444.36  3972.6  446.13  3979.8  443.72  4050.6  440.59
  4100.0  441.49  4121.3  438.93  4184.8  439.92  4192.0  437.78  4227.3  439.02
  4262.8  436.53  4269.7  438.45  4283.9  435.73  4319.1  437.33  4439.5  433.03
  4913.3  429.42  4974.8  426.46  4975.1  425.96  4978.9  426.46  4998.2  428.54
  5571.0  431.29  5648.7  434.44  5712.5  433.13  5733.6  435.43  5790.2  434.04
  6136.6  439.29  6702.3  440.49  6737.8  442.69  6758.9  440.70  6970.5  441.22
#Mann=3,-1,0
  3851.5    0.05       0  4974.8    0.03       0  4978.9    0.05       0
Bank Sta=4974.8,4978.9
Exp/Cntr=0.3,0.1

Type RM Length L Ch R = 1,14852,713,713,713
BEGIN DESCRIPTION:
Mapping XS d17ca9c5
END DESCRIPTION:
XS GIS Cut Line= 4
      2629406.46      6931476.97      2628614.76      6932232.22
      2627916.84      6932893.67      2627126.47      6933637.25
#Sta/Elev= 30
  3893.8  448.02  3989.0  443.93  4285.9  436.15  4385.0  434.36  4399.2  435.60
  4462.7  433.17  4498.2  433.74  4505.2  432.65  4540.7  433.02  4547.6  431.82
  4590.1  431.04  4943.9  428.90  4972.2  428.30  4981.5  426.34  4981.9  425.84
  4985.7  426.34  5014.3  429.44  5198.4  429.31  5368.3  433.31  5849.3  435.43
  5920.0  437.60  5941.1  436.39  6061.2  438.12  6103.7  436.85  6146.2  438.46
  6153.5  439.74  6174.5  438.55  6252.6  440.46  6450.5  441.45  7034.7  442.25
#Mann=3,-1,0
  3893.8    0.05       0  4981.5    0.03       0  4985.7    0.05       0
Bank Sta=4981.5,4985.7
Exp/Cntr=0.3,0.1

Type RM Length L Ch R = 1,14139,597,597,597
BEGIN DESCRIPTION:
Little Brushy Creek Trib 6 21.0
END DESCRIPTION:
XS GIS Cut Line= 3
      2629539.57      6931429.74      2628339.54      6931629.75
      2626540.25      6932629.36
#Sta/Elev= 30
  3750.1  453.22  3804.4  452.82  3844.4  449.65  3956.5  446.89  4007.2  442.60
  4179.5  435.65  4311.3  434.03  4372.1  431.21  4585.0  429.29  4656.0  427.14
  5041.1  426.06  5041.4  425.56  5045.3  426.06  5073.7  427.36  5096.6  432.09
  5124.4  428.91  5199.5  428.97  5205.7  431.16  5211.4  428.84  5221.7  430.33
  5227.4  429.04  5243.4  433.06  5249.1  430.60  5270.9  429.76  5542.7  433.26
  6094.5  436.24  6309.2  439.76  6381.6  438.88  6403.4  440.45  7025.0  442.15
#Mann=3,-1,0
  3750.1    0.05       0  5041.1    0.03       0  5045.3    0.05       0
Bank Sta=5041.1,5045.3
Exp/Cntr=0.3,0.1

Type RM Length L Ch R = 1,13542,755,755,755
BEGIN DESCRIPTION:
Little Brushy Creek Trib 6 19.0
END DESCRIPTION:
XS GIS Cut Line= 3
      2629575.96      6931360.99      2628376.00      6931161.00
      2627076.01      6931361.00
#Sta/Elev= 30
  3783.5  455.26  3803.7  455.28  3824.0  453.50  3986.2  447.39  4016.6  444.83
  4120.5  441.64  4128.2  440.58  4237.1  435.80  4351.2  434.70  4358.8  433.55
  4493.1  430.07  4655.3  429.40  4675.6  427.91  4817.5  425.99  4858.1  426.60
  4959.5  425.82  4972.1  425.61  4977.5  423.99  4977.9  423.49  4982.0  423.99
  4997.5  425.69  5029.1  425.23  5040.5  426.33  5303.5  427.28  5560.3  429.82
  5910.6  437.42  6102.8  440.66  6154.7  439.73  6274.8  441.26  6315.3  440.90
#Mann=3,-1,0
  3783.5    0.05       0  4977.5    0.03       0  4982.0    0.05       0
Bank Sta=4977.5,4982
Exp/Cntr=0.3,0.1

Type RM Length L Ch R = 1,12787,408,408,408
BEGIN DESCRIPTION:
Little Brushy Creek Trib 6 17.0
END DESCRIPTION:
XS GIS Cut Line= 3
      2629476.04      6930611.00      2628320.72      6930509.14
      2626675.57      6931207.89
#Sta/Elev= 30
  3840.2  450.43  3896.3  446.34  3920.6  447.21  3990.6  444.38  4051.1  441.87
  4101.2  441.25  4141.4  438.43  4191.6  438.11  4211.7  436.52  4302.0  434.32
  4422.5  432.67  4442.6  430.59  4532.9  428.60  4733.7  426.19  4994.7  425.03
  5005.3  424.73  5011.7  422.65  5012.2  422.15  5016.4  422.65  5037.7  424.40
  5043.1  422.88  5048.6  423.09  5059.5  424.88  5195.9  424.42  5265.9  426.18
  5607.0  428.08  6124.2  438.30  6371.0  438.35  6423.7  439.61  6787.4  441.83
#Mann=4,-1,0
  3840.2   0.075       0  3990.6    0.05       0  5011.7    0.04       0
  5016.4    0.05       0
Bank Sta=5011.7,5016.4
Exp/Cntr=0.3,0.1

Type RM Length L Ch R = 1,12379,744,744,744
BEGIN DESCRIPTION:
Mapping XS c74407b4
END DESCRIPTION:
XS GIS Cut Line= 4
      2629649.50      6930442.29      2628524.48      6930088.12
      2628165.11      6930150.62      2626394.30      6930728.73
#Sta/Elev= 30
  3467.9  454.49  3545.0  453.02  3552.8  451.59  3628.8  447.26  3660.4  447.08
  3687.6  444.94  3725.2  444.50  3817.1  440.40  3828.0  441.09  3854.7  438.29
  3892.3  438.04  3924.7  435.60  3964.3  434.43  4420.8  427.92  4716.9  426.76
  4757.5  425.30  4909.7  424.43  4960.5  422.76  4990.9  423.21  4998.7  421.90
  4999.2  421.40  5003.4  421.90  5074.3  424.23  5232.1  425.94  5747.5  428.17
  6160.1  435.02  6273.5  439.12  6357.7  440.62  6631.2  442.41  6874.9  440.40
#Mann=3,-1,0
  3467.9    0.05       0  4998.7    0.03       0  5003.4    0.05       0
Bank Sta=4998.7,5003.4
Exp/Cntr=0.3,0.1

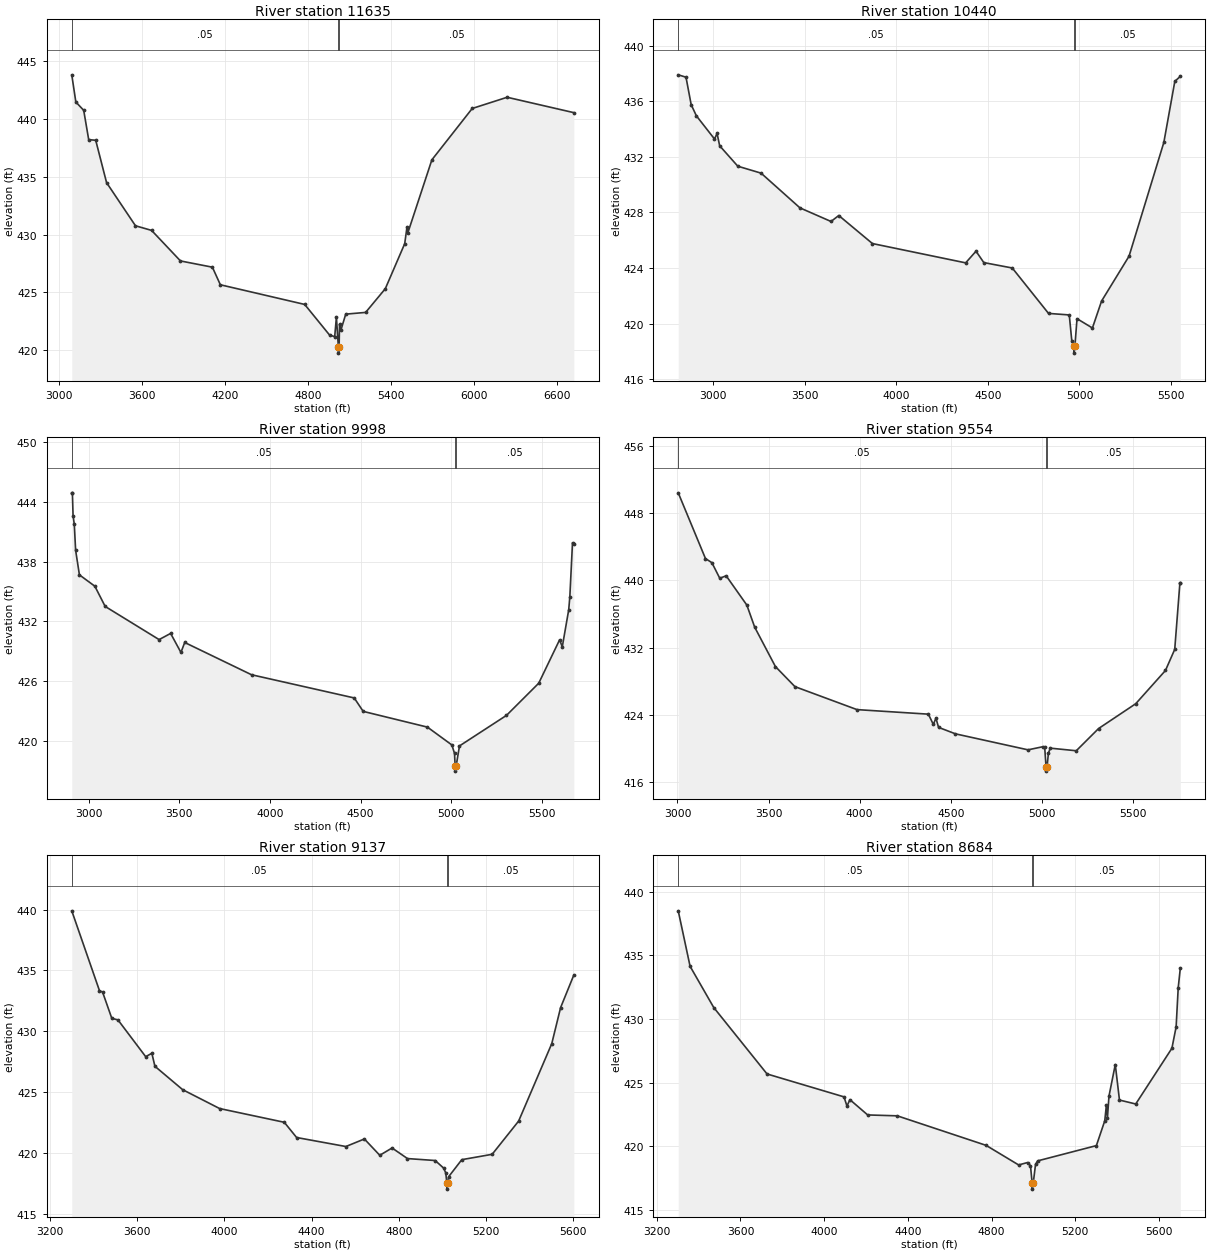
Type RM Length L Ch R = 1,11635,1195,1195,1195
BEGIN DESCRIPTION:
Mapping XS 965f7ff3
END DESCRIPTION:
XS GIS Cut Line= 4
      2629493.24      6930233.96      2628185.94      6929338.12
      2627930.73      6929509.99      2626379.85      6930280.23
#Sta/Elev= 30
  3095.0  443.81  3124.4  441.46  3181.2  440.74  3217.1  438.21  3267.9  438.15
  3346.2  434.49  3554.9  430.76  3671.3  430.36  3879.6  427.72  4110.0  427.18
  4167.5  425.66  4776.2  423.96  4956.7  421.30  4992.9  421.18  5005.2  422.85
  5019.6  420.25  5020.2  419.75  5024.6  420.25  5027.7  422.24  5037.4  421.73
  5072.5  423.12  5216.1  423.27  5358.2  425.32  5498.2  429.21  5515.0  430.67
  5520.6  430.14  5694.3  436.46  5985.5  440.90  6237.6  441.87  6719.1  440.54
#Mann=3,-1,0
  3095.0    0.05       0  5019.6    0.03       0  5024.6    0.05       0
Bank Sta=5019.6,5024.6
Exp/Cntr=0.3,0.1

Type RM Length L Ch R = 1,10440,442,442,442
BEGIN DESCRIPTION:
Little Brushy Creek Trib 6 15.0
END DESCRIPTION:
XS GIS Cut Line= 3
      2629425.99      6930110.99      2627876.00      6928561.00
      2627326.02      6928561.00
#Sta/Elev= 30
  2808.6  437.91  2851.0  437.74  2879.3  435.76  2907.6  434.96  3006.6  433.29
  3020.7  433.69  3034.9  432.80  3133.9  431.33  3261.1  430.83  3473.3  428.33
  3643.0  427.35  3685.4  427.78  3869.2  425.76  4378.4  424.37  4434.9  425.21
  4477.4  424.39  4632.9  424.00  4830.9  420.73  4944.1  420.62  4958.2  418.72
  4969.8  418.37  4970.4  417.87  4974.9  418.37  4986.5  420.35  5070.6  419.68
  5120.6  421.62  5270.6  424.85  5460.6  433.04  5520.6  437.44  5550.6  437.80
#Mann=3,-1,0
  2808.6    0.05       0  4969.8    0.03       0  4974.9    0.05       0
Bank Sta=4969.8,4974.9
Exp/Cntr=0.3,0.1

Type RM Length L Ch R = 1,9998,444,444,444
BEGIN DESCRIPTION:
Little Brushy Creek Trib 6 14.0
END DESCRIPTION:
XS GIS Cut Line= 3
      2629676.01      6929761.01      2628126.00      6928361.00
      2627575.96      6927960.97
#Sta/Elev= 30
  2906.8  444.90  2910.2  444.90  2913.9  442.62  2920.7  441.74  2928.1  439.12
  2949.0  436.66  3034.2  435.52  3091.0  433.49  3388.4  430.16  3452.0  430.78
  3508.8  428.87  3529.7  429.87  3898.1  426.63  4464.5  424.30  4513.9  422.95
  4868.1  421.37  5002.8  419.58  5017.5  418.74  5021.1  417.45  5021.8  416.95
  5026.3  417.45  5044.9  419.48  5304.2  422.55  5482.0  425.78  5597.1  430.14
  5611.8  429.43  5647.3  433.15  5653.5  434.46  5668.2  439.89  5675.6  439.74
#Mann=3,-1,0
  2906.8    0.05       0  5021.1    0.04       0  5026.3    0.05       0
Bank Sta=5021.1,5026.3
Exp/Cntr=0.3,0.1

Type RM Length L Ch R = 1,9554,417,417,417
BEGIN DESCRIPTION:
Little Brushy Creek Trib 6 13.0
END DESCRIPTION:
XS GIS Cut Line= 3
      2629925.96      6929260.97      2628376.00      6928011.00
      2627626.04      6927861.01
#Sta/Elev= 30
  3004.4  450.40  3153.9  442.59  3189.1  442.10  3232.3  440.25  3267.5  440.54
  3381.0  437.06  3424.2  434.43  3537.7  429.76  3644.9  427.37  3985.6  424.64
  4377.4  424.10  4404.6  422.88  4419.0  423.62  4433.4  422.53  4526.2  421.76
  4924.4  419.86  5005.8  420.23  5016.0  420.15  5023.5  417.83  5024.3  417.33
  5028.8  417.83  5036.4  419.46  5046.6  420.06  5189.3  419.75  5311.7  422.39
  5515.7  425.34  5678.9  429.29  5729.8  431.80  5757.9  439.63  5760.4  439.63
#Mann=3,-1,0
  3004.4    0.05       0  5023.5    0.04       0  5028.8    0.05       0
Bank Sta=5023.5,5028.8
Exp/Cntr=0.3,0.1

Type RM Length L Ch R = 1,9137,453,453,453
BEGIN DESCRIPTION:
Little Brushy Creek Trib 6 12.0
END DESCRIPTION:
XS GIS Cut Line= 3
      2629775.97      6928860.97      2628576.00      6927661.00
      2627975.99      6927561.00
#Sta/Elev= 30
  3298.9  439.90  3426.1  433.34  3440.3  433.23  3482.7  431.07  3511.0  430.94
  3638.3  427.92  3666.6  428.20  3680.7  427.13  3808.0  425.21  3977.7  423.66
  4274.7  422.53  4331.2  421.28  4557.5  420.54  4642.4  421.16  4713.1  419.82
  4769.6  420.42  4840.4  419.55  4967.6  419.39  5006.1  418.77  5016.2  418.37
  5021.0  417.54  5021.8  417.04  5026.5  417.54  5028.9  418.05  5089.7  419.46
  5229.1  419.90  5350.7  422.63  5502.8  428.99  5543.4  431.95  5604.2  434.63
#Mann=3,-1,0
  3298.9    0.05       0  5021.0    0.03       0  5026.5    0.05       0
Bank Sta=5021,5026.5
Exp/Cntr=0.3,0.1

Type RM Length L Ch R = 1,8684,358,358,358
BEGIN DESCRIPTION:
Little Brushy Creek Trib 6 11.0
END DESCRIPTION:
XS GIS Cut Line= 3
      2629926.01      6928461.01      2628726.00      6927261.00
      2628026.05      6927311.00
#Sta/Elev= 30
  3302.6  438.51  3359.2  434.15  3472.3  430.91  3726.9  425.69  4094.6  423.89
  4108.7  423.17  4122.9  423.67  4207.7  422.47  4349.1  422.40  4773.4  420.08
  4929.0  418.54  4971.4  418.73  4985.5  418.48  4993.4  417.14  4994.2  416.64
  4998.9  417.14  5009.7  418.58  5019.7  418.86  5300.4  420.06  5340.5  422.01
  5348.1  423.23  5353.1  422.21  5360.6  423.95  5390.7  426.43  5410.7  423.64
  5488.4  423.33  5661.3  427.71  5681.4  429.39  5691.4  432.47  5701.4  434.00
#Mann=3,-1,0
  3302.6    0.05       0  4993.4    0.04       0  4998.9    0.05       0
Bank Sta=4993.4,4998.9
Exp/Cntr=0.3,0.1

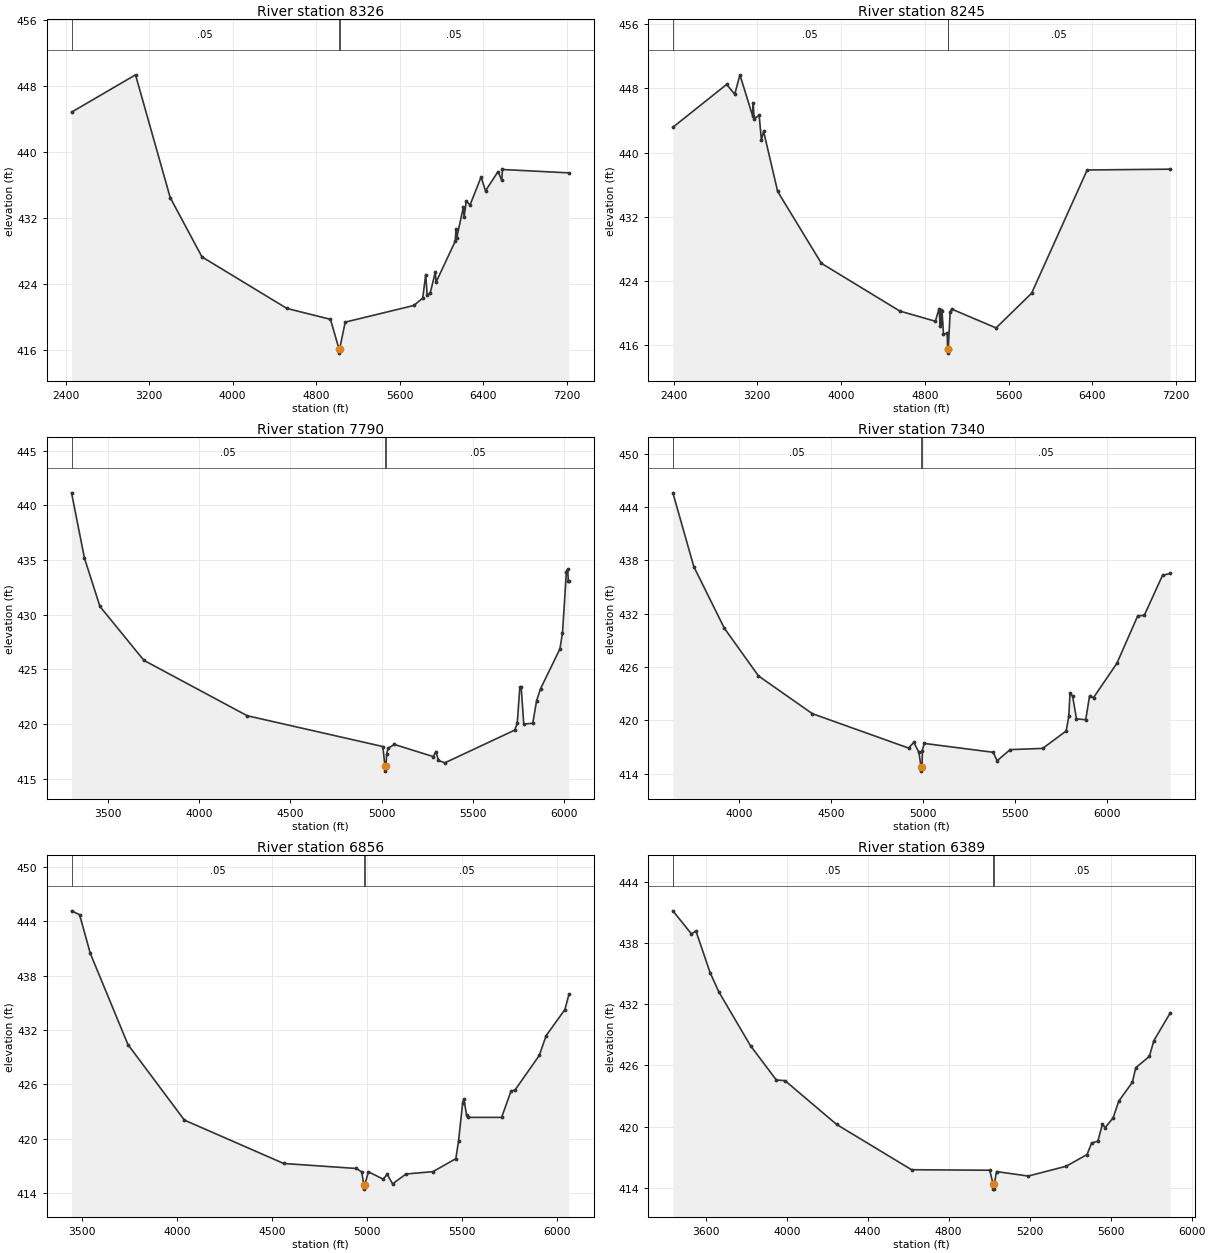
Type RM Length L Ch R = 1,8326,81,81,81
BEGIN DESCRIPTION:
Mapping XS 153d0426
END DESCRIPTION:
XS GIS Cut Line= 4
      2630613.01      6928770.40      2629764.06      6927884.99
      2628842.19      6926937.08      2627291.65      6925355.32
#Sta/Elev= 30
  2456.7  444.87  3069.4  449.40  3401.8  434.51  3706.0  427.32  4519.3  421.07
  4936.5  419.75  5018.6  416.15  5019.4  415.65  5024.1  416.15  5077.9  419.41
  5735.6  421.43  5820.4  422.33  5848.7  425.17  5862.9  422.71  5891.2  422.89
  5940.6  425.49  5947.7  424.25  6131.6  429.22  6138.6  430.70  6145.8  429.63
  6209.3  433.36  6216.5  432.16  6237.6  434.10  6273.1  433.61  6379.1  437.01
  6421.5  435.33  6541.7  437.67  6577.1  436.61  6584.1  437.92  7220.6  437.51
#Mann=3,-1,0
  2456.7    0.05       0  5018.6    0.03       0  5024.1    0.05       0
Bank Sta=5018.6,5024.1
Exp/Cntr=0.3,0.1

Type RM Length L Ch R = 1,8245,455,455,455
BEGIN DESCRIPTION:
Mapping XS c94d26c2
END DESCRIPTION:
XS GIS Cut Line= 4
      2630715.89      6928717.03      2629981.51      6927977.44
      2628913.80      6926909.73      2627398.17      6925315.97
#Sta/Elev= 30
  2393.0  443.17  2906.3  448.50  2984.1  447.29  3033.6  449.70  3153.8  444.62
  3160.9  446.23  3167.9  444.19  3217.5  444.65  3238.6  441.61  3259.9  442.66
  3394.2  435.17  3811.4  426.23  4560.9  420.28  4900.4  419.01  4935.7  420.56
  4947.3  418.45  4949.8  420.37  4957.1  418.78  4964.0  420.32  4978.1  417.41
  5013.4  417.51  5017.8  415.54  5018.7  415.04  5023.4  415.54  5041.7  420.11
  5055.8  420.53  5480.5  418.18  5819.9  422.50  6350.5  437.85  7144.6  437.95
#Mann=3,-1,0
  2393.0    0.05       0  5017.8    0.03       0  5023.4    0.05       0
Bank Sta=5017.8,5023.4
Exp/Cntr=0.3,0.1

Type RM Length L Ch R = 1,7790,450,450,450
BEGIN DESCRIPTION:
Little Brushy Creek Trib 6 9.0
END DESCRIPTION:
XS GIS Cut Line= 3
      2630326.02      6927711.02      2629126.00      6926511.00
      2628376.00      6925811.00
#Sta/Elev= 30
  3302.7  441.15  3373.4  435.18  3458.3  430.75  3698.7  425.82  4264.4  420.75
  5006.9  417.93  5018.2  416.18  5019.1  415.68  5023.8  416.18  5027.9  417.25
  5035.2  417.77  5070.4  418.12  5282.9  417.01  5297.1  417.47  5311.2  416.66
  5346.4  416.44  5728.4  419.43  5742.6  420.04  5756.8  423.36  5764.1  423.40
  5778.3  419.99  5827.6  420.06  5848.6  422.12  5870.1  423.22  5976.1  426.86
  5990.3  428.31  6011.8  433.93  6018.6  434.16  6022.3  433.06  6025.7  433.06
#Mann=3,-1,0
  3302.7    0.05       0  5018.2    0.03       0  5023.8    0.05       0
Bank Sta=5018.2,5023.8
Exp/Cntr=0.3,0.1

Type RM Length L Ch R = 1,7340,484,484,484
BEGIN DESCRIPTION:
Little Brushy Creek Trib 6 8.0
END DESCRIPTION:
XS GIS Cut Line= 3
      2630575.98      6927060.99      2629476.00      6926261.00
      2628575.99      6925260.99
#Sta/Elev= 30
  3640.4  445.60  3754.4  437.29  3919.8  430.38  4106.0  424.99  4398.9  420.74
  4922.1  416.87  4951.1  417.51  4978.5  416.39  4990.3  414.77  4991.2  414.27
  4996.0  414.77  4997.4  416.58  5007.6  417.39  5382.8  416.39  5404.1  415.44
  5474.8  416.69  5651.9  416.83  5779.7  418.79  5793.9  420.45  5800.6  423.10
  5814.8  422.68  5835.8  420.16  5885.9  420.05  5906.8  422.72  5928.5  422.55
  6055.5  426.41  6169.1  431.76  6204.3  431.80  6303.7  436.31  6345.9  436.53
#Mann=3,-1,0
  3640.4    0.05       0  4990.3    0.03       0  4996.0    0.05       0
Bank Sta=4990.3,4996
Exp/Cntr=0.3,0.1

Type RM Length L Ch R = 1,6856,467,467,467
BEGIN DESCRIPTION:
Little Brushy Creek Trib 6 7.0
END DESCRIPTION:
XS GIS Cut Line= 3
      2630676.01      6926911.01      2629576.00      6925811.00
      2628775.98      6925110.98
#Sta/Elev= 30
  3444.2  445.14  3486.6  444.71  3543.2  440.43  3741.2  430.38  4038.2  422.04
  4561.4  417.25  4943.3  416.70  4971.6  416.32  4982.9  414.92  4983.8  414.42
  4988.6  414.92  5007.0  416.34  5084.8  415.52  5106.2  416.06  5134.2  415.00
  5205.3  416.09  5346.8  416.35  5467.3  417.78  5481.5  419.71  5503.4  423.95
  5510.0  424.38  5524.2  422.55  5531.4  422.34  5708.4  422.34  5757.7  425.22
  5779.6  425.38  5906.7  429.18  5942.8  431.36  6041.5  434.24  6062.9  435.92
#Mann=3,-1,0
  3444.2    0.05       0  4982.9    0.03       0  4988.6    0.05       0
Bank Sta=4982.9,4988.6
Exp/Cntr=0.3,0.1

Type RM Length L Ch R = 1,6389,452,452,452
BEGIN DESCRIPTION:
Little Brushy Creek Trib 6 6.0
END DESCRIPTION:
XS GIS Cut Line= 3
      2630826.02      6926661.02      2629826.00      6925461.00
      2629026.00      6925061.00
#Sta/Elev= 30
  3437.9  441.14  3529.7  438.88  3551.8  439.17  3622.1  435.07  3665.1  433.20
  3821.3  427.93  3948.8  424.58  3991.8  424.51  4246.9  420.22  4616.6  415.79
  5002.8  415.74  5019.3  414.39  5020.3  413.89  5024.3  413.89  5025.3  414.39
  5036.3  415.61  5192.8  415.17  5380.1  416.13  5483.5  417.28  5505.9  418.41
  5536.6  418.58  5559.0  420.22  5573.0  419.92  5612.1  420.87  5640.1  422.51
  5707.1  424.35  5723.9  425.78  5791.0  426.88  5813.3  428.43  5894.4  431.15
#Mann=3,-1,0
  3437.9    0.05       0  5019.3    0.03       0  5025.3    0.05       0
Bank Sta=5019.3,5025.3
Exp/Cntr=0.3,0.1

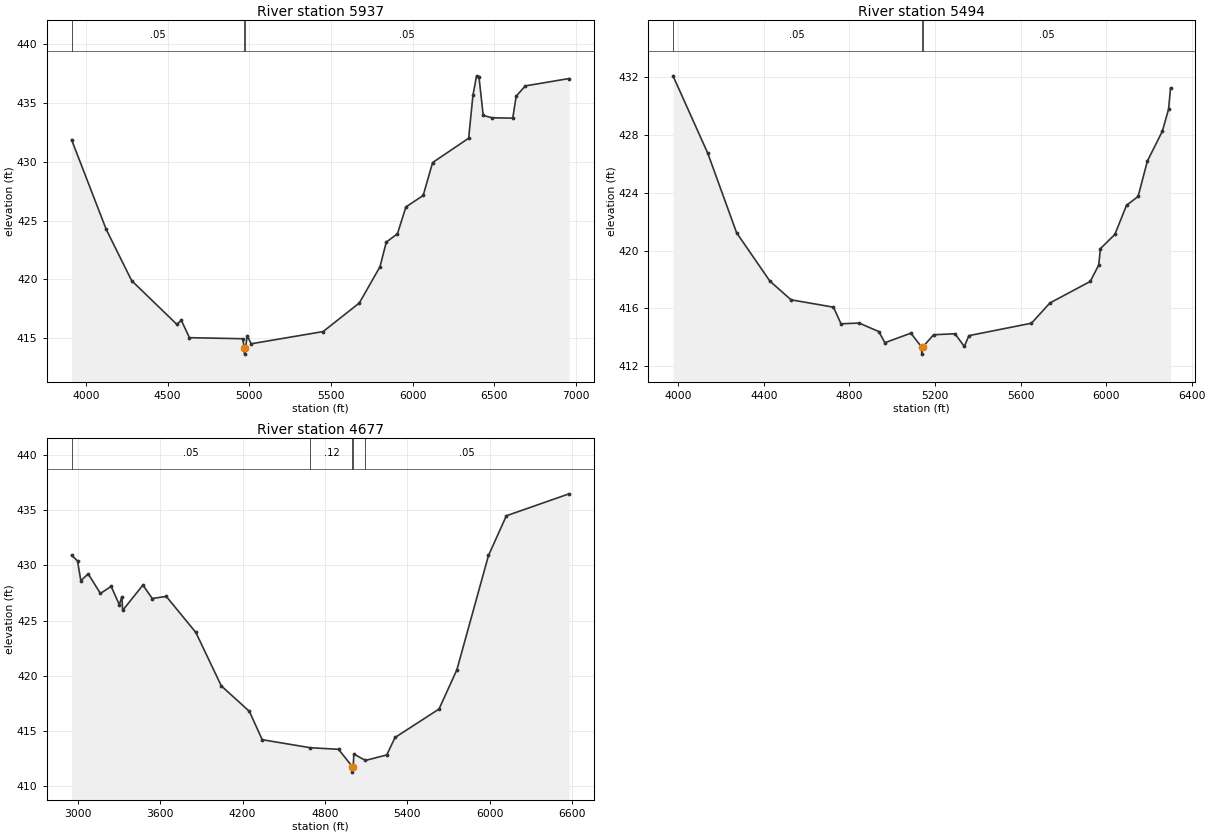
Type RM Length L Ch R = 1,5937,443,443,443
BEGIN DESCRIPTION:
Little Brushy Creek Trib 6 5.0
END DESCRIPTION:
XS GIS Cut Line= 3
      2630876.02      6925861.02      2630076.00      6925111.00
      2628229.32      6924489.74
#Sta/Elev= 30
  3911.7  431.88  4124.0  424.24  4279.8  419.88  4555.7  416.17  4583.6  416.50
  4633.4  415.03  4958.7  414.94  4969.9  414.13  4970.9  413.63  4975.9  414.13
  4987.1  415.20  5011.0  414.51  5451.4  415.55  5673.0  417.98  5799.6  421.07
  5838.0  423.16  5906.3  423.87  5957.9  426.15  6063.8  427.13  6121.5  429.93
  6342.1  432.00  6368.3  435.64  6390.5  437.31  6405.1  437.24  6431.3  433.94
  6485.4  433.74  6612.0  433.71  6633.1  435.58  6688.7  436.45  6956.7  437.08
#Mann=3,-1,0
  3911.7    0.05       0  4969.9    0.03       0  4975.9    0.05       0
Bank Sta=4969.9,4975.9
Exp/Cntr=0.3,0.1

Type RM Length L Ch R = 1,5494,817,817,817
BEGIN DESCRIPTION:
Little Brushy Creek Trib 6 4.0
END DESCRIPTION:
XS GIS Cut Line= 3
      2631076.00      6925561.00      2630376.00      6924811.00
      2629176.02      6924311.01
#Sta/Elev= 30
  3975.3  432.09  4138.2  426.72  4272.6  421.23  4427.9  417.89  4527.1  416.59
  4725.4  416.08  4760.6  414.93  4845.6  414.98  4937.5  414.39  4965.8  413.62
  5087.3  414.28  5137.3  413.33  5138.3  412.83  5143.5  413.33  5193.5  414.17
  5293.7  414.24  5337.1  413.36  5358.7  414.11  5651.2  414.97  5737.3  416.37
  5925.8  417.86  5965.4  418.99  5973.5  420.13  6041.2  421.12  6095.4  423.13
  6149.6  423.74  6192.9  426.19  6262.8  428.25  6292.0  429.78  6301.2  431.23
#Mann=3,-1,0
  3975.3    0.05       0  5137.3    0.03       0  5143.5    0.05       0
Bank Sta=5137.3,5143.5
Exp/Cntr=0.3,0.1

Type RM Length L Ch R = 1,4677,0,0,0
BEGIN DESCRIPTION:
Little Brushy Creek Trib 6 3.0
END DESCRIPTION:
XS GIS Cut Line= 4
      2631488.02      6925483.94      2630972.40      6924192.29
      2630325.95      6924086.00      2628749.74      6924015.26
#Sta/Elev= 30
  2954.1  430.93  2997.5  430.41  3021.7  428.62  3075.6  429.23  3164.5  427.46
  3242.7  428.10  3302.0  426.44  3320.8  427.17  3326.2  425.92  3474.1  428.22
  3541.8  427.00  3644.2  427.19  3859.7  423.92  4044.8  419.08  4249.3  416.77
  4342.9  414.20  4694.0  413.47  4898.6  413.33  4999.3  411.76  5000.3  411.26
  5005.7  411.76  5010.0  412.90  5094.9  412.32  5250.2  412.82  5310.3  414.40
  5630.6  416.98  5760.7  420.54  5990.9  430.90  6121.1  434.50  6577.8  436.49
#Mann=5,-1,0
  2954.1    0.05       0  4694.0    0.12       0  4999.3    0.07       0
  5005.7    0.12       0  5094.9    0.05       0
Bank Sta=4999.3,5005.7
Exp/Cntr=0.3,0.1

Chan Stop Cuts=-1