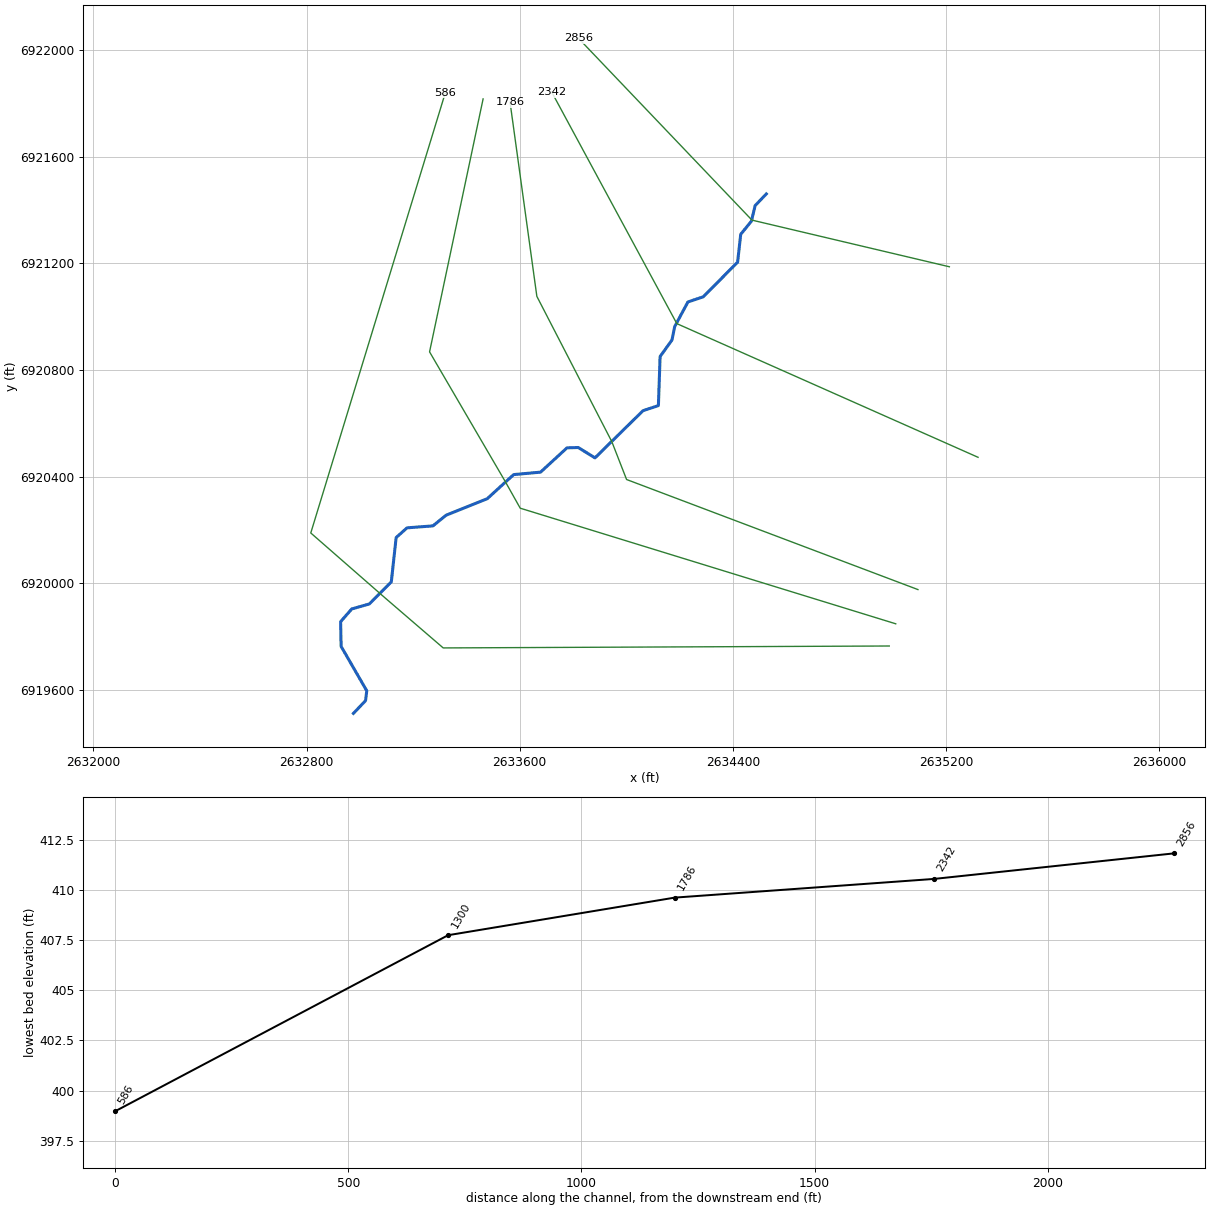
--- Little Brushy Creek Trib 7.prj (project) ---

Proj Title=Little Brushy Creek Trib 7 Base Level Engineering
Current Plan=p01
Default Exp/Contr=0.3,0.1
English Units
Geom File=g01
Flow File=f01
Plan File=p01
BEGIN DESCRIPTION:
Little Brushy Creek Trib 7
END DESCRIPTION:

--- Little Brushy Creek Trib 7.p01 (plan) ---

Plan Title=Multiple Run
Short Identifier=Multiple
Geom File=g01
Flow File=f01
Subcritical Flow
K Sum by GR= 0
Std Step Tol= 0.01
Critical Tol= 0.01
Num of Std Step Trials= 20
Max Error Tol= 0.3
Flow Tol Ratio= 0.001
Split Flow NTrial= 30
Split Flow Tol= 0.02
Split Flow Ratio= 0.02
Log Output Level= 0
Friction Slope Method= 1
Unsteady Friction Slope Method= 2
Unsteady Bridges Friction Slope Method= 1
Parabolic Critical Depth
Global Vel Dist=  1 , 1 , 1
Global Log Level= 0
CheckData=True
Encroach Param= -1, 0, 0, 0
BEGIN DESCRIPTION:
Multiple Run
END DESCRIPTION:

--- Little Brushy Creek Trib 7.f01 (steady flow) ---

Flow Title=Multiple
Number of Profiles=7
Profile Names=10-year,25-year,50-year,1pct_min,100-year,1pct_plu,500-year
River Rch & RM= Little Brushy Cr,Reach-1,2856
     530     708     852     509    1015    2025    1440
Boundary for River Rch & Prof#=Little Brushy Cr,Reach-1,1
Up Type=0
Dn Type=3
Dn Slope=0.005
Boundary for River Rch & Prof#=Little Brushy Cr,Reach-1,2
Up Type=0
Dn Type=3
Dn Slope=0.005
Boundary for River Rch & Prof#=Little Brushy Cr,Reach-1,3
Up Type=0
Dn Type=3
Dn Slope=0.005
Boundary for River Rch & Prof#=Little Brushy Cr,Reach-1,4
Up Type=0
Dn Type=3
Dn Slope=0.005
Boundary for River Rch & Prof#=Little Brushy Cr,Reach-1,5
Up Type=0
Dn Type=3
Dn Slope=0.005
Boundary for River Rch & Prof#=Little Brushy Cr,Reach-1,6
Up Type=0
Dn Type=3
Dn Slope=0.005
Boundary for River Rch & Prof#=Little Brushy Cr,Reach-1,7
Up Type=0
Dn Type=3
Dn Slope=0.005

--- Little Brushy Creek Trib 7.g01 (geometry) ---

Geom Title=Existing Conditions

River Reach=Little Brushy Cr,Reach-1
Reach XY= 30
      2634526.00      6921461.00      2634483.91      6921417.15
      2634469.97      6921358.78      2634429.82      6921309.42
      2634418.14      6921204.83      2634288.98      6921074.73
      2634231.59      6921055.39      2634182.06      6920963.23
      2634171.81      6920912.74      2634127.20      6920850.50
      2634120.82      6920666.44      2634063.05      6920647.26
      2633882.73      6920470.15      2633819.95      6920509.01
      2633777.65      6920507.83      2633678.42      6920416.54
      2633577.50      6920407.37      2633478.29      6920316.85
      2633323.82      6920254.88      2633274.41      6920214.83
      2633177.25      6920207.49      2633136.33      6920171.17
      2633118.19      6920004.79      2633035.68      6919921.78
      2632969.62      6919902.98      2632927.89      6919855.29
      2632929.67      6919762.59      2633026.04      6919595.68
      2633021.40      6919558.64      2632976.00      6919511.00

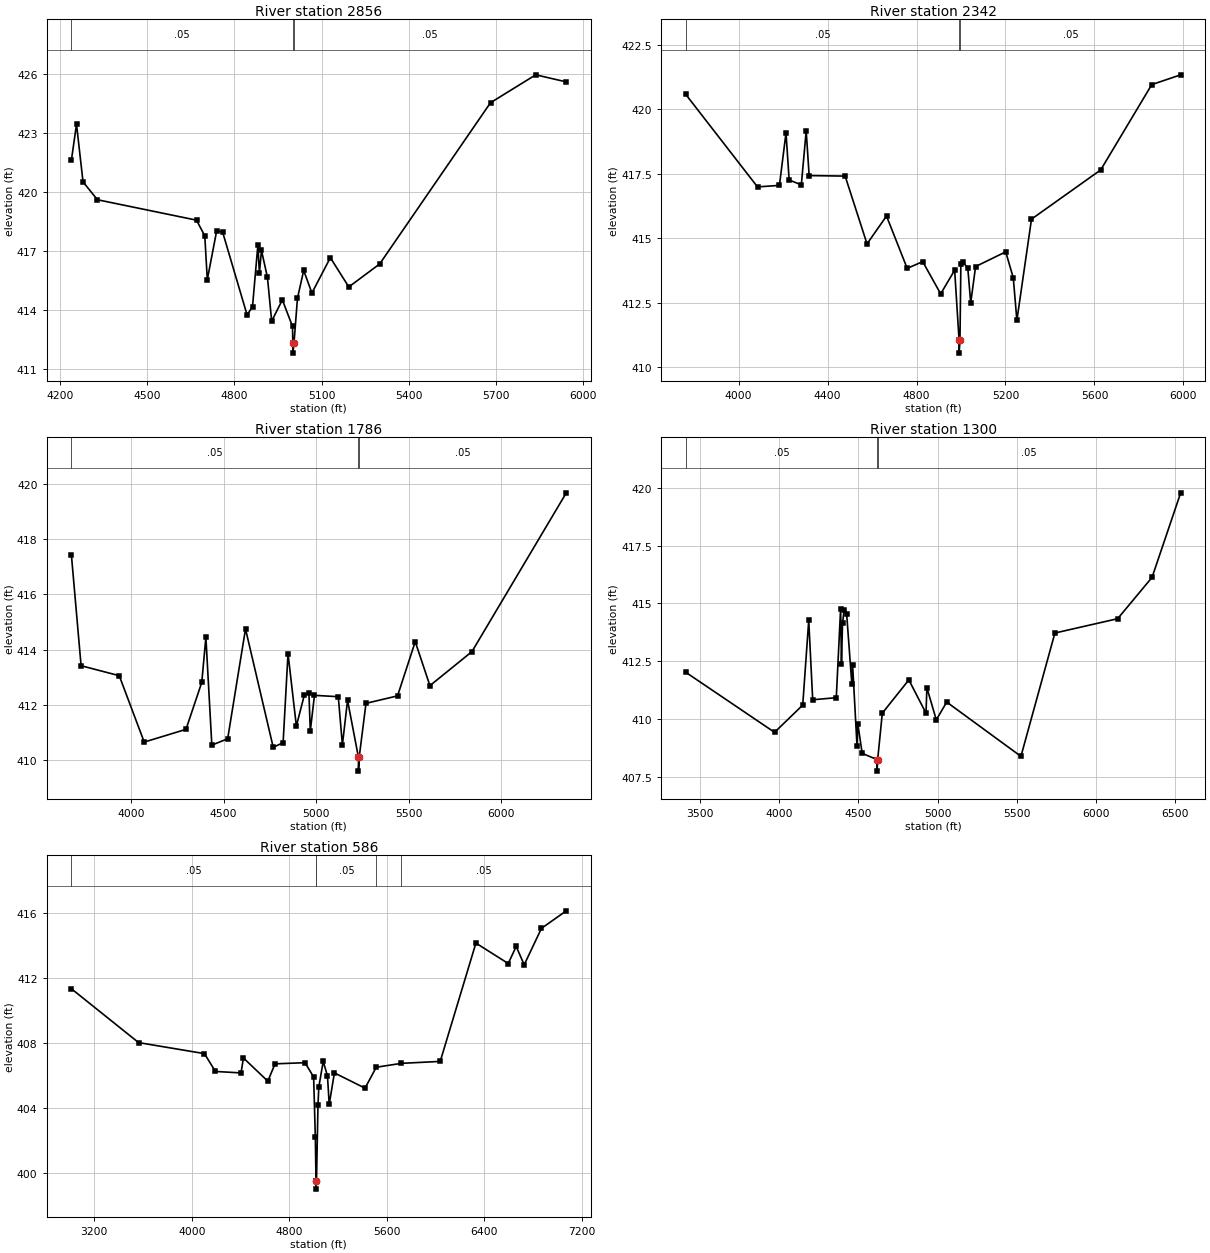
Type RM Length L Ch R = 1,2856,514,514,514
BEGIN DESCRIPTION:
Little Brushy Creek Trib 7 3.0
END DESCRIPTION:
XS GIS Cut Line= 3
      2635213.11      6921187.54      2634471.93      6921362.69
      2633820.91      6922045.05
#Sta/Elev= 30
  4238.4  421.64  4256.0  423.46  4278.4  420.53  4327.9  419.62  4669.3  418.58
  4697.8  417.78  4706.5  415.55  4738.9  418.05  4759.5  417.96  4843.6  413.75
  4862.2  414.18  4880.8  417.33  4885.9  415.88  4893.1  417.04  4913.6  415.67
  4928.2  413.44  4965.0  414.52  5000.0  413.17  5001.0  412.31  5001.2  411.81
  5005.0  412.31  5017.1  414.61  5038.5  416.02  5066.8  414.87  5130.3  416.67
  5193.9  415.18  5300.2  416.35  5682.0  424.56  5837.7  425.98  5943.1  425.62
#Mann=3,-1,0
  4238.4    0.05       0  5001.0    0.03       0  5005.0    0.05       0
Bank Sta=5001,5005
Exp/Cntr=0.3,0.1

Type RM Length L Ch R = 1,2342,556,556,556
BEGIN DESCRIPTION:
Little Brushy Creek Trib 7 4.0
END DESCRIPTION:
XS GIS Cut Line= 3
      2635320.78      6920472.26      2634189.94      6920974.14
      2633720.55      6921842.94
#Sta/Elev= 30
  3762.8  420.58  4085.3  416.99  4183.8  417.05  4213.4  419.09  4227.5  417.26
  4282.2  417.07  4304.1  419.16  4317.4  417.43  4479.2  417.41  4577.6  414.78
  4665.2  415.86  4758.1  413.83  4827.9  414.09  4908.7  412.84  4971.5  413.76
  4991.4  411.04  4991.6  410.54  4995.4  411.04  4999.4  413.98  5007.8  414.07
  5030.5  413.85  5043.7  412.49  5065.6  413.90  5201.0  414.47  5235.1  413.46
  5251.2  411.81  5316.9  415.74  5628.1  417.65  5857.5  420.96  5987.5  421.34
#Mann=3,-1,0
  3762.8    0.05       0  4991.4    0.03       0  4995.4    0.05       0
Bank Sta=4991.4,4995.4
Exp/Cntr=0.3,0.1

Type RM Length L Ch R = 1,1786,486,486,486
BEGIN DESCRIPTION:
Little Brushy Creek Trib 7 2.0
END DESCRIPTION:
XS GIS Cut Line= 5
      2635095.07      6919975.74      2634001.35      6920388.92
      2633946.00      6920530.84      2633664.54      6921076.42
      2633563.85      6921805.60
#Sta/Elev= 30
  3678.5  417.42  3730.7  413.42  3936.7  413.06  4071.5  410.66  4297.0  411.12
  4382.2  412.82  4404.4  414.45  4436.5  410.55  4522.0  410.78  4618.3  414.75
  4767.9  410.47  4821.3  410.64  4847.7  413.86  4892.8  411.24  4936.2  412.37
  4960.7  412.42  4968.0  411.06  4990.5  412.35  5119.1  412.30  5141.3  410.56
  5169.1  412.17  5227.9  410.11  5228.2  409.61  5231.9  410.11  5268.6  412.06
  5439.0  412.33  5534.5  414.29  5613.7  412.70  5840.6  413.93  6350.0  419.67
#Mann=3,-1,0
  3678.5    0.05       0  5227.9    0.03       0  5231.9    0.05       0
Bank Sta=5227.9,5231.9
Exp/Cntr=0.3,0.1

Type RM Length L Ch R = 1,1300,714,714,714
BEGIN DESCRIPTION:
Little Brushy Creek Trib 7 5.0
END DESCRIPTION:
XS GIS Cut Line= 5
      2635011.72      6919847.27      2633602.04      6920281.28
      2633545.83      6920381.41      2633261.76      6920868.09
      2633462.78      6921817.73
#Sta/Elev= 30
  3410.2  412.02  3970.7  409.42  4148.5  410.60  4186.4  414.27  4211.4  410.83
  4360.3  410.92  4387.7  414.78  4393.0  412.39  4399.7  414.15  4410.2  414.72
  4425.7  414.55  4458.3  411.52  4463.6  412.32  4491.0  408.84  4496.3  409.79
  4523.7  408.51  4617.5  408.24  4617.7  407.74  4621.5  408.24  4650.8  410.25
  4818.3  411.69  4926.6  410.25  4932.3  411.35  4991.6  409.96  5057.4  410.73
  5525.9  408.38  5740.3  413.72  6136.5  414.34  6353.6  416.13  6534.2  419.79
#Mann=3,-1,0
  3410.2    0.05       0  4617.5    0.04       0  4621.5    0.05       0
Bank Sta=4617.5,4621.5
Exp/Cntr=0.3,0.1

Type RM Length L Ch R = 1,586,0,0,0
BEGIN DESCRIPTION:
Little Brushy Creek Trib 7 1.0
END DESCRIPTION:
XS GIS Cut Line= 5
      2634987.43      6919763.92      2633312.98      6919756.70
      2633095.96      6919943.44      2632815.84      6920188.22
      2633320.79      6921840.31
#Sta/Elev= 30
  3013.1  411.34  3564.5  408.02  4104.5  407.34  4194.5  406.24  4404.5  406.15
  4424.5  407.07  4624.5  405.64  4683.6  406.71  4929.7  406.78  5000.4  405.90
  5014.2  402.19  5019.8  399.48  5020.1  398.98  5023.8  399.48  5036.1  404.16
  5042.7  405.27  5078.8  406.86  5113.9  405.97  5128.1  404.21  5170.8  406.15
  5422.0  405.21  5514.2  406.50  5720.4  406.74  6038.9  406.86  6331.7  414.16
  6596.7  412.90  6662.3  413.95  6727.9  412.82  6869.5  415.07  7073.4  416.15
#Mann=5,-1,0
  3013.1    0.05       0  5019.8    0.04       0  5023.8    0.05       0
  5514.2    0.12       0  5720.4    0.05       0
Bank Sta=5019.8,5023.8
Exp/Cntr=0.3,0.1

Chan Stop Cuts=-1