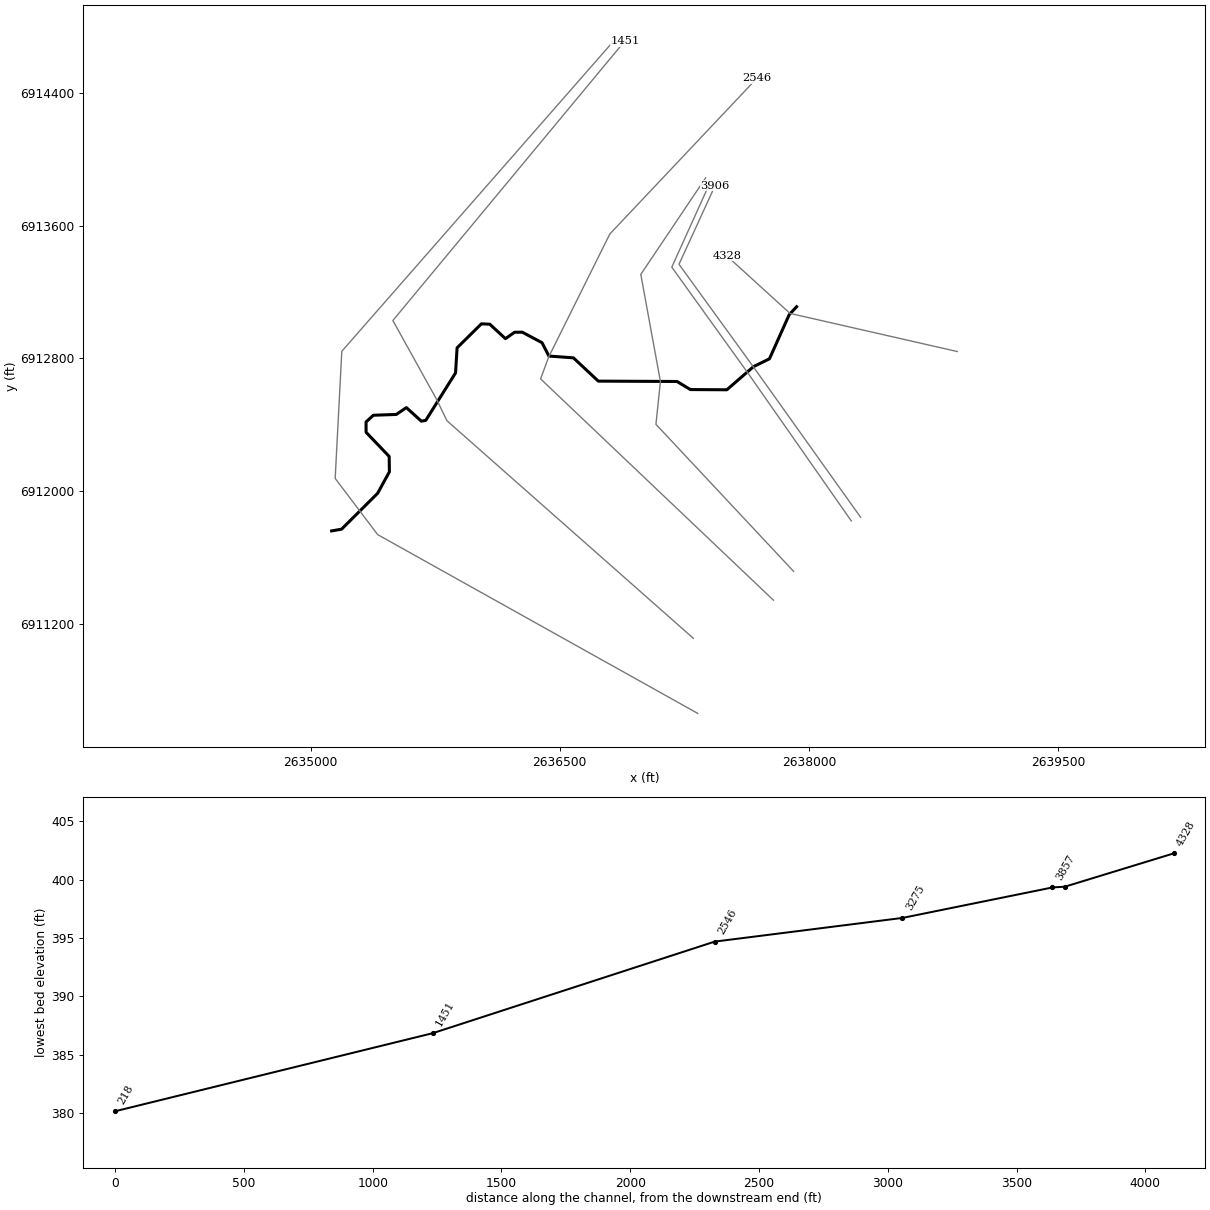
--- Little Brushy Creek Trib 8.prj (project) ---

Proj Title=Little Brushy Creek Trib 8 Base Level Engineering
Current Plan=p01
Default Exp/Contr=0.3,0.1
English Units
Geom File=g01
Flow File=f01
Plan File=p01
BEGIN DESCRIPTION:
Little Brushy Creek Trib 8
END DESCRIPTION:

--- Little Brushy Creek Trib 8.p01 (plan) ---

Plan Title=Multiple Run
Short Identifier=Multiple
Geom File=g01
Flow File=f01
Subcritical Flow
K Sum by GR= 0
Std Step Tol= 0.01
Critical Tol= 0.01
Num of Std Step Trials= 20
Max Error Tol= 0.3
Flow Tol Ratio= 0.001
Split Flow NTrial= 30
Split Flow Tol= 0.02
Split Flow Ratio= 0.02
Log Output Level= 0
Friction Slope Method= 1
Unsteady Friction Slope Method= 2
Unsteady Bridges Friction Slope Method= 1
Parabolic Critical Depth
Global Vel Dist=  1 , 1 , 1
Global Log Level= 0
CheckData=True
Encroach Param= -1, 0, 0, 0
BEGIN DESCRIPTION:
Multiple Run
END DESCRIPTION:

--- Little Brushy Creek Trib 8.f01 (steady flow) ---

Flow Title=Multiple
Number of Profiles=7
Profile Names=10-year,25-year,50-year,1pct_min,100-year,1pct_plu,500-year
River Rch & RM= Little Brushy Cr,Reach-1,4328
     538     720     865     516    1030    2054    1458
Boundary for River Rch & Prof#=Little Brushy Cr,Reach-1,1
Up Type=0
Dn Type=3
Dn Slope=0.005
Boundary for River Rch & Prof#=Little Brushy Cr,Reach-1,2
Up Type=0
Dn Type=3
Dn Slope=0.005
Boundary for River Rch & Prof#=Little Brushy Cr,Reach-1,3
Up Type=0
Dn Type=3
Dn Slope=0.005
Boundary for River Rch & Prof#=Little Brushy Cr,Reach-1,4
Up Type=0
Dn Type=3
Dn Slope=0.005
Boundary for River Rch & Prof#=Little Brushy Cr,Reach-1,5
Up Type=0
Dn Type=3
Dn Slope=0.005
Boundary for River Rch & Prof#=Little Brushy Cr,Reach-1,6
Up Type=0
Dn Type=3
Dn Slope=0.005
Boundary for River Rch & Prof#=Little Brushy Cr,Reach-1,7
Up Type=0
Dn Type=3
Dn Slope=0.005

--- Little Brushy Creek Trib 8.g01 (geometry) ---

Geom Title=Existing Conditions

River Reach=Little Brushy Cr,Reach-1
Reach XY= 30
      2637926.00      6913111.00      2637881.67      6913063.36
      2637762.53      6912797.43      2637666.34      6912750.21
      2637506.02      6912610.96      2637286.50      6912612.22
      2637205.97      6912660.93      2636731.85      6912663.06
      2636582.19      6912803.18      2636434.31      6912814.10
      2636393.01      6912894.43      2636274.27      6912957.63
      2636227.64      6912957.39      2636172.60      6912918.84
      2636078.29      6913005.91      2636027.65      6913007.90
      2635881.47      6912863.45      2635872.24      6912712.56
      2635693.04      6912427.04      2635666.13      6912421.94
      2635576.10      6912503.66      2635515.56      6912462.40
      2635377.19      6912457.55      2635333.32      6912417.38
      2635333.45      6912354.97      2635472.54      6912209.50
      2635473.86      6912116.97      2635402.99      6911987.53
      2635185.79      6911771.51      2635126.00      6911761.00

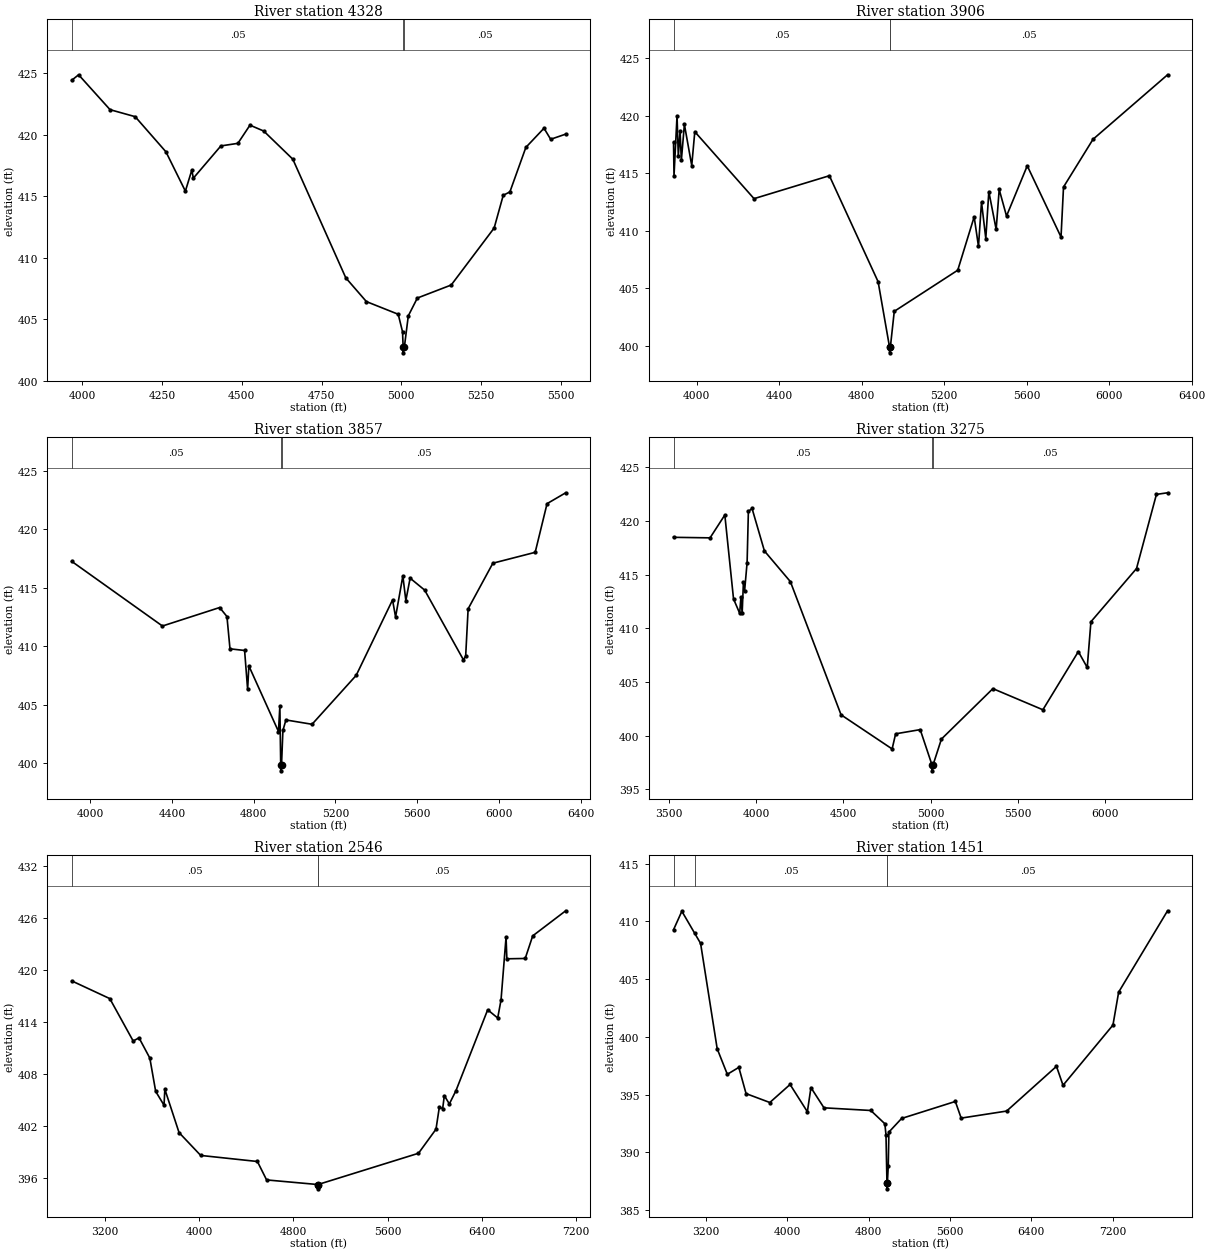
Type RM Length L Ch R = 1,4328,422,422,422
BEGIN DESCRIPTION:
Little Brushy Creek Trib 8 3.0
END DESCRIPTION:
XS GIS Cut Line= 3
      2638893.17      6912841.40      2637886.48      6913070.80
      2637505.76      6913417.31
#Sta/Elev= 30
  3967.5  424.44  3989.2  424.89  4087.7  422.05  4166.4  421.48  4262.7  418.62
  4323.6  415.42  4343.6  417.12  4348.7  416.48  4434.8  419.10  4488.1  419.31
  4525.9  420.79  4569.0  420.31  4660.1  418.02  4826.1  408.36  4890.6  406.43
  4990.2  405.40  5003.7  403.98  5005.6  402.76  5005.8  402.26  5009.6  402.76
  5021.8  405.27  5050.1  406.72  5156.2  407.78  5290.7  412.42  5319.1  415.08
  5340.0  415.36  5390.0  418.98  5446.8  420.54  5467.7  419.64  5514.8  420.06
#Mann=3,-1,0
  3967.5    0.05       0  5005.6    0.04       0  5009.6    0.05       0
Bank Sta=5005.6,5009.6
Exp/Cntr=0.3,0.1

Type RM Length L Ch R = 1,3906,49,49,49
BEGIN DESCRIPTION:
Mapping XS abea90d6
END DESCRIPTION:
XS GIS Cut Line= 4
      2638311.58      6911843.13      2637664.88      6912750.25
      2637217.83      6913366.57      2637434.84      6913839.64
#Sta/Elev= 30
  3886.9  417.67  3889.2  414.77  3903.9  419.99  3910.1  416.47  3918.7  418.64
  3924.8  416.11  3939.6  419.23  3975.2  415.66  3990.0  418.60  4277.3  412.79
  4642.7  414.78  4879.1  405.58  4934.5  399.91  4934.8  399.41  4938.5  399.91
  4957.4  403.01  5265.2  406.58  5344.9  411.21  5365.8  408.65  5380.5  412.49
  5401.3  409.33  5416.0  413.40  5451.6  410.12  5466.3  413.59  5501.8  411.28
  5602.3  415.64  5766.1  409.46  5778.2  413.80  5921.2  417.94  6282.8  423.54
#Mann=3,-1,0
  3886.9    0.05       0  4934.5    0.03       0  4938.5    0.05       0
Bank Sta=4934.5,4938.5
Exp/Cntr=0.3,0.1

Type RM Length L Ch R = 1,3857,582,582,582
BEGIN DESCRIPTION:
Mapping XS ae77311e
END DESCRIPTION:
XS GIS Cut Line= 4
      2638255.16      6911821.42      2637630.16      6912715.53
      2637174.43      6913349.21      2637399.58      6913847.13
#Sta/Elev= 30
  3909.1  417.25  4353.3  411.72  4633.3  413.30  4669.0  412.53  4683.9  409.77
  4755.4  409.63  4770.2  406.30  4776.3  408.31  4921.3  402.70  4928.0  404.90
  4932.1  399.84  4932.4  399.34  4936.1  399.84  4942.9  402.79  4957.7  403.69
  5085.5  403.32  5301.5  407.50  5479.5  413.95  5494.3  412.49  5529.9  416.00
  5544.6  413.90  5565.5  415.81  5636.7  414.79  5826.4  408.83  5837.4  409.15
  5849.4  413.19  5970.5  417.09  6177.6  418.02  6235.7  422.18  6327.0  423.11
#Mann=3,-1,0
  3909.1    0.05       0  4932.1    0.03       0  4936.1    0.05       0
Bank Sta=4932.1,4936.1
Exp/Cntr=0.3,0.1

Type RM Length L Ch R = 1,3275,729,729,729
BEGIN DESCRIPTION:
Mapping XS b6be039a
END DESCRIPTION:
XS GIS Cut Line= 5
      2637907.90      6911517.65      2637078.94      6912403.03
      2637106.01      6912661.03      2636987.79      6913305.81
      2637377.96      6913886.72
#Sta/Elev= 30
  3527.7  418.49  3736.8  418.44  3821.3  420.57  3871.1  412.75  3906.3  411.41
  3913.6  412.93  3920.5  411.40  3927.8  414.33  3934.6  413.52  3948.8  416.14
  3956.1  420.90  3977.1  421.18  4047.9  417.22  4196.5  414.36  4486.6  401.95
  4778.8  398.77  4798.9  400.18  4939.6  400.57  5008.1  397.23  5008.4  396.73
  5012.1  397.23  5061.0  399.69  5355.6  404.39  5641.7  402.42  5844.6  407.84
  5895.6  406.36  5916.6  410.62  6177.6  415.58  6291.6  422.49  6355.3  422.64
#Mann=3,-1,0
  3527.7    0.05       0  5008.1    0.03       0  5012.1    0.05       0
Bank Sta=5008.1,5012.1
Exp/Cntr=0.3,0.1

Type RM Length L Ch R = 1,2546,1095,1095,1095
BEGIN DESCRIPTION:
Mapping XS 5c98c1ca
END DESCRIPTION:
XS GIS Cut Line= 5
      2637786.42      6911343.99      2636384.50      6912676.46
      2636432.24      6912806.67      2636801.16      6913548.86
      2637686.40      6914486.17
#Sta/Elev= 30
  2919.5  418.73  3243.0  416.68  3441.2  411.78  3490.6  412.15  3582.4  409.81
  3632.1  405.96  3702.9  404.36  3709.8  406.21  3830.3  401.20  4014.0  398.56
  4494.9  397.86  4573.0  395.73  5005.4  395.20  5005.6  394.70  5009.4  395.20
  5861.5  398.81  6010.0  401.59  6038.3  404.13  6066.6  403.97  6080.8  405.47
  6123.3  404.51  6179.9  406.06  6448.5  415.39  6533.5  414.44  6561.8  416.54
  6604.3  423.79  6611.2  421.28  6766.9  421.32  6830.4  423.93  7110.4  426.83
#Mann=3,-1,0
  2919.5    0.05       0  5005.4    0.03       0  5009.4    0.05       0
Bank Sta=5005.4,5009.4
Exp/Cntr=0.3,0.1

Type RM Length L Ch R = 1,1451,1233,1233,1233
BEGIN DESCRIPTION:
Mapping XS 39bbc2c6
END DESCRIPTION:
XS GIS Cut Line= 5
      2637304.62      6911113.98      2635820.26      6912424.73
      2635759.50      6912550.60      2635494.74      6913028.03
      2636891.64      6914711.24
#Sta/Elev= 30
  2884.3  409.27  2966.0  410.87  3093.0  408.95  3150.1  408.09  3313.2  398.97
  3412.8  396.76  3525.7  397.36  3596.8  395.09  3830.2  394.32  4029.3  395.88
  4199.1  393.52  4234.2  395.61  4362.3  393.86  4822.3  393.63  4960.4  392.48
  4971.4  391.52  4981.0  387.35  4981.2  386.85  4985.0  387.35  4993.7  388.81
  5000.0  391.76  5124.9  392.94  5652.8  394.41  5710.0  392.97  6156.7  393.58
  6646.3  397.45  6710.7  395.81  7201.1  401.02  7257.1  403.87  7737.6  410.91
#Mann=4,-1,0
  2884.3    0.12       0  3093.0    0.05       0  4981.0    0.04       0
  4985.0    0.05       0
Bank Sta=4981,4985
Exp/Cntr=0.3,0.1

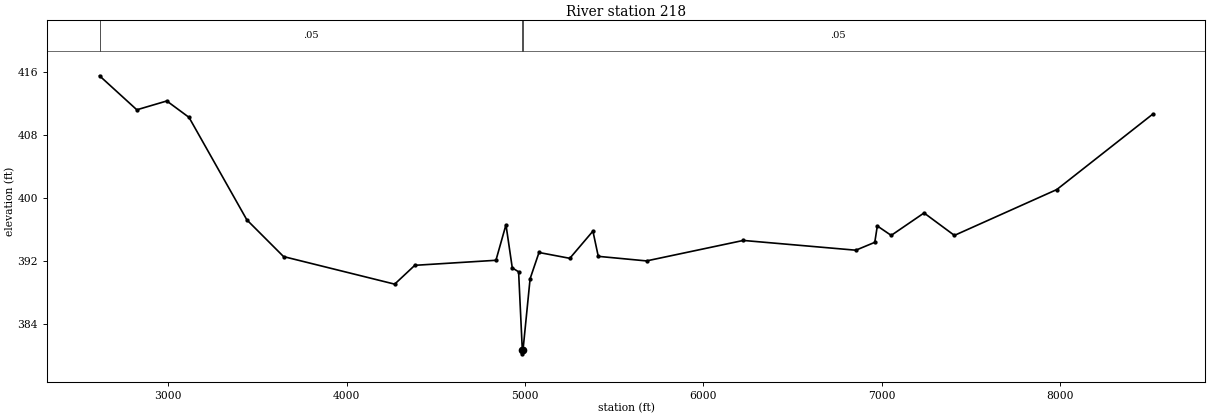
Type RM Length L Ch R = 1,218,0,0,0
BEGIN DESCRIPTION:
Little Brushy Creek Trib 8 1.0
END DESCRIPTION:
XS GIS Cut Line= 5
      2637330.46      6910662.24      2635403.41      6911738.61
      2635147.34      6912077.15      2635187.27      6912842.77
      2636838.42      6914727.33
#Sta/Elev= 30
  2614.4  415.47  2823.6  411.15  2991.5  412.27  3116.0  410.19  3440.4  397.17
  3646.1  392.51  4268.9  389.01  4381.7  391.40  4836.6  392.04  4892.8  396.55
  4928.2  391.07  4963.6  390.58  4984.4  380.66  4984.7  380.16  4988.4  380.66
  5028.1  389.70  5078.0  393.03  5250.6  392.29  5380.2  395.74  5410.2  392.54
  5680.6  391.96  6223.2  394.56  6853.9  393.32  6960.2  394.32  6974.4  396.40
  7052.3  395.20  7236.4  398.05  7406.5  395.20  7980.4  401.02  8518.4  410.60
#Mann=3,-1,0
  2614.4    0.05       0  4984.4    0.03       0  4988.4    0.05       0
Bank Sta=4984.4,4988.4
Exp/Cntr=0.3,0.1

Chan Stop Cuts=-1