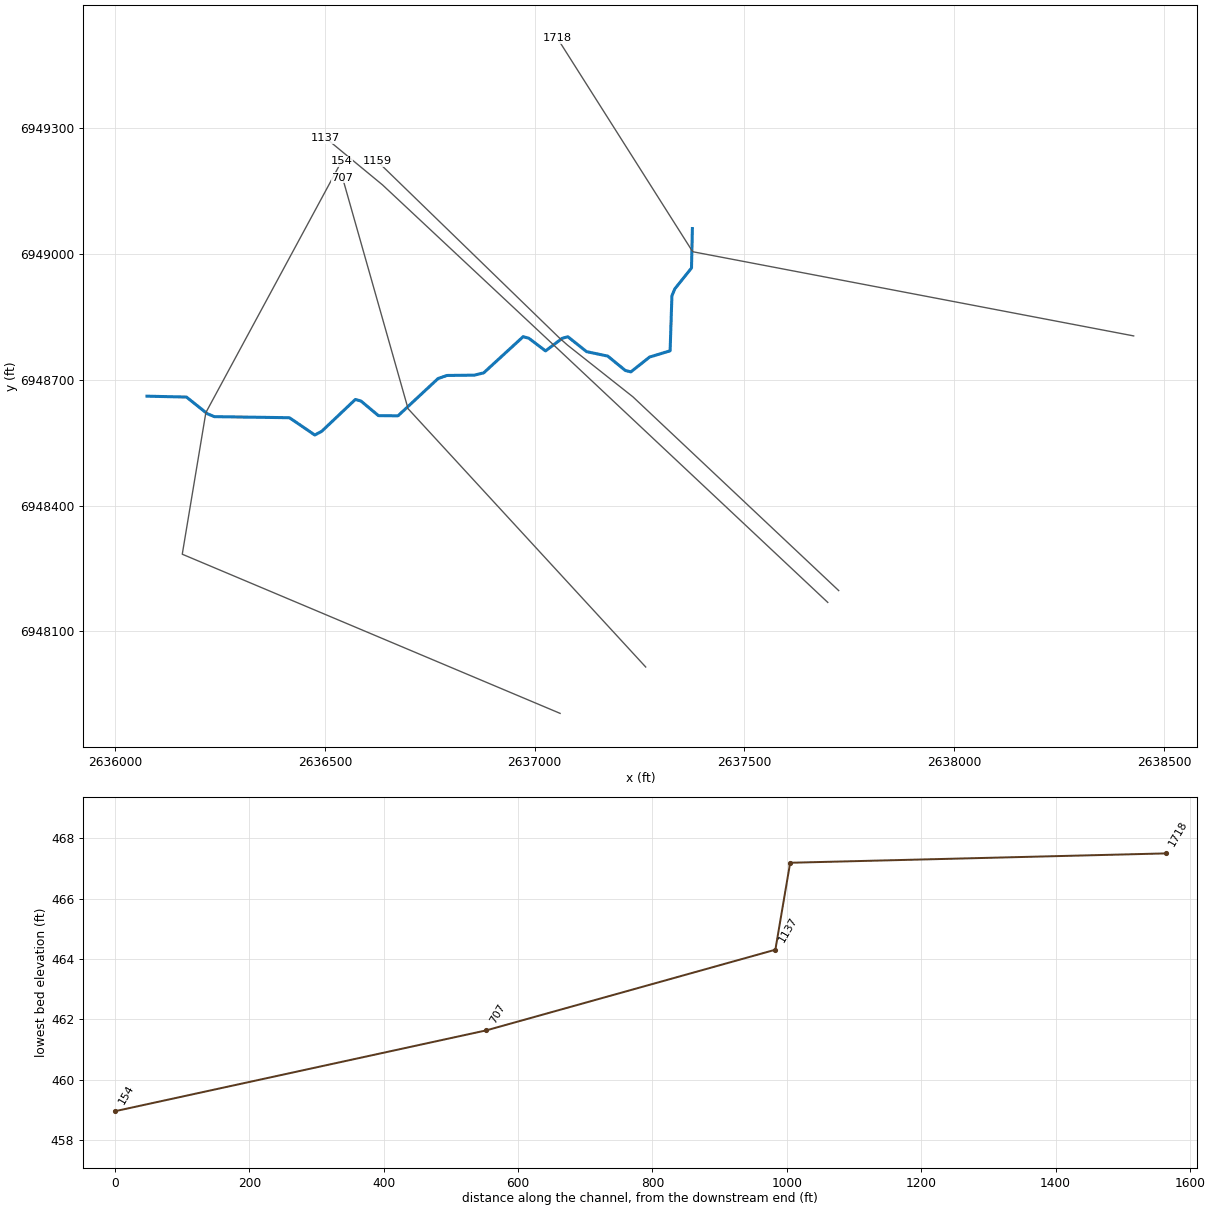
--- Little Brushy Creek Trib 9.prj (project) ---

Proj Title=Little Brushy Creek Trib 9 Base Level Engineering
Current Plan=p01
Default Exp/Contr=0.3,0.1
English Units
Geom File=g01
Flow File=f01
Plan File=p01
BEGIN DESCRIPTION:
Little Brushy Creek Trib 9
END DESCRIPTION:

--- Little Brushy Creek Trib 9.p01 (plan) ---

Plan Title=Multiple Run
Short Identifier=Multiple
Geom File=g01
Flow File=f01
Subcritical Flow
K Sum by GR= 0
Std Step Tol= 0.01
Critical Tol= 0.01
Num of Std Step Trials= 20
Max Error Tol= 0.3
Flow Tol Ratio= 0.001
Split Flow NTrial= 30
Split Flow Tol= 0.02
Split Flow Ratio= 0.02
Log Output Level= 0
Friction Slope Method= 1
Unsteady Friction Slope Method= 2
Unsteady Bridges Friction Slope Method= 1
Parabolic Critical Depth
Global Vel Dist=  1 , 1 , 1
Global Log Level= 0
CheckData=True
Encroach Param= -1, 0, 0, 0
BEGIN DESCRIPTION:
Multiple Run
END DESCRIPTION:

--- Little Brushy Creek Trib 9.f01 (steady flow) ---

Flow Title=Multiple
Number of Profiles=7
Profile Names=10-year,25-year,50-year,1pct_min,100-year,1pct_plu,500-year
River Rch & RM= Little Brushy Cr,Reach-1,1718
     276     352     410     238     475     947     633
Boundary for River Rch & Prof#=Little Brushy Cr,Reach-1,1
Up Type=0
Dn Type=3
Dn Slope=0.005
Boundary for River Rch & Prof#=Little Brushy Cr,Reach-1,2
Up Type=0
Dn Type=3
Dn Slope=0.005
Boundary for River Rch & Prof#=Little Brushy Cr,Reach-1,3
Up Type=0
Dn Type=3
Dn Slope=0.005
Boundary for River Rch & Prof#=Little Brushy Cr,Reach-1,4
Up Type=0
Dn Type=3
Dn Slope=0.005
Boundary for River Rch & Prof#=Little Brushy Cr,Reach-1,5
Up Type=0
Dn Type=3
Dn Slope=0.005
Boundary for River Rch & Prof#=Little Brushy Cr,Reach-1,6
Up Type=0
Dn Type=3
Dn Slope=0.005
Boundary for River Rch & Prof#=Little Brushy Cr,Reach-1,7
Up Type=0
Dn Type=3
Dn Slope=0.005

--- Little Brushy Creek Trib 9.g01 (geometry) ---

Geom Title=Existing Conditions

River Reach=Little Brushy Cr,Reach-1
Reach XY= 30
      2637376.00      6949061.00      2637373.90      6948966.87
      2637334.10      6948917.07      2637327.22      6948900.49
      2637322.92      6948769.26      2637274.11      6948754.42
      2637229.35      6948719.00      2637216.09      6948722.40
      2637174.35      6948756.61      2637123.71      6948767.35
      2637079.23      6948802.77      2637065.95      6948799.21
      2637026.00      6948769.04      2636986.00      6948799.33
      2636972.67      6948803.00      2636878.43      6948716.55
      2636855.94      6948711.14      2636791.22      6948710.47
      2636769.84      6948703.12      2636674.35      6948614.17
      2636627.65      6948614.59      2636585.87      6948649.60
      2636572.59      6948653.15      2636492.71      6948577.36
      2636476.10      6948568.34      2636415.57      6948609.61
      2636236.50      6948612.20      2636219.93      6948619.10
      2636170.13      6948658.90      2636076.00      6948661.00

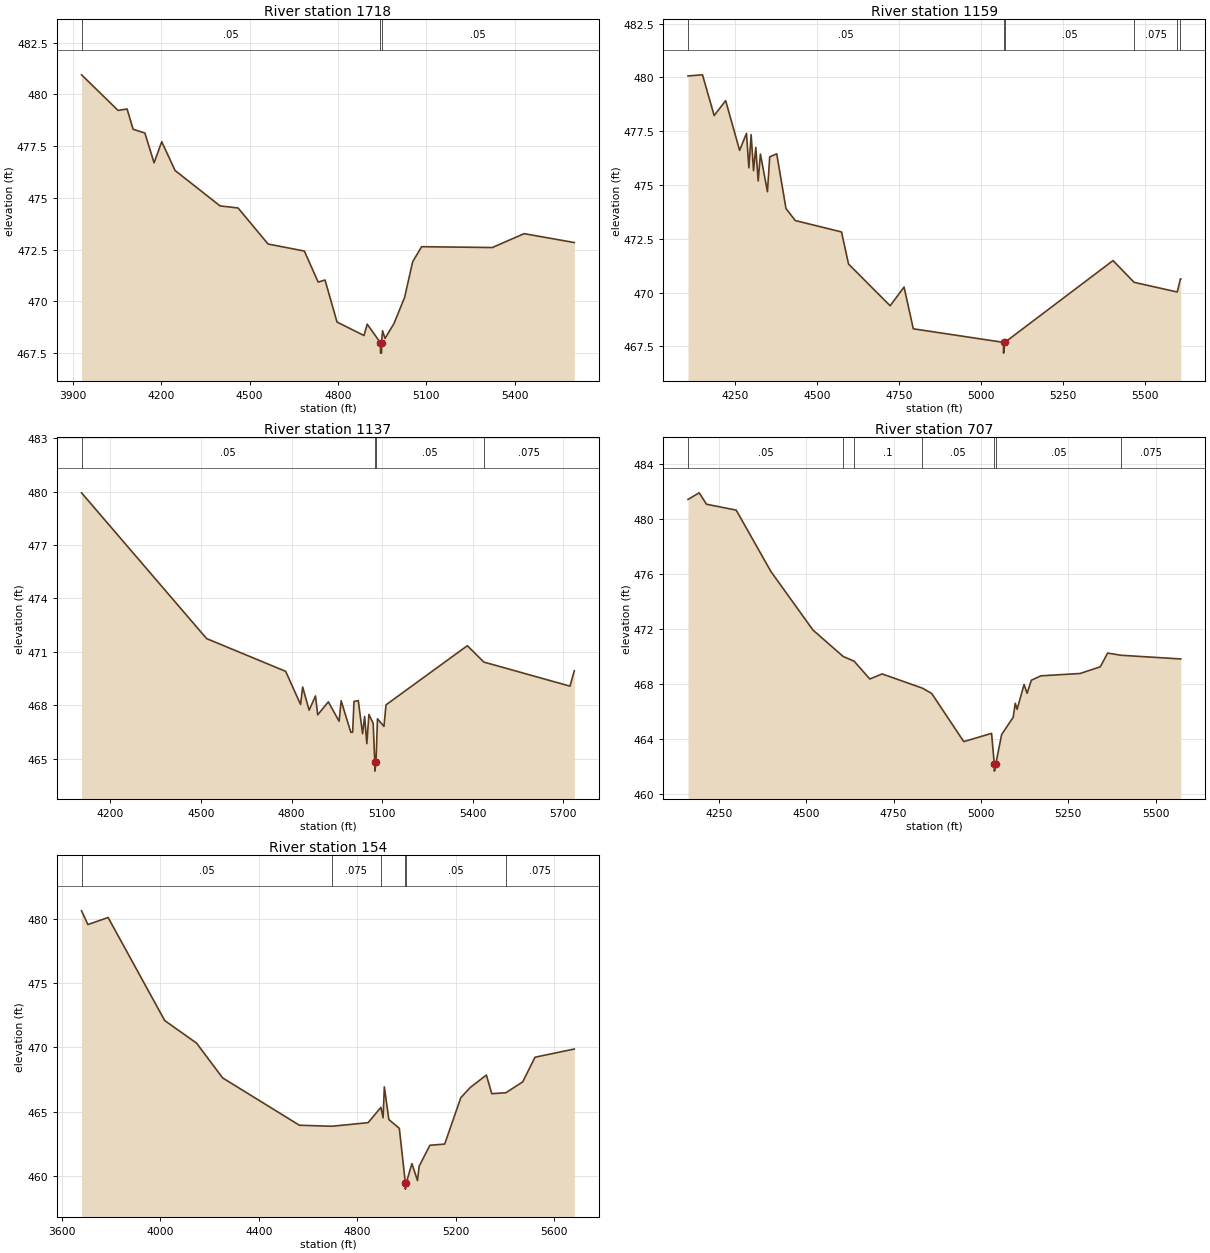
Type RM Length L Ch R = 1,1718,559,559,559
BEGIN DESCRIPTION:
Little Brushy Creek Trib 9 3.0
END DESCRIPTION:
XS GIS Cut Line= 3
      2638427.87      6948804.80      2637376.70      6949005.71
      2637054.35      6949514.84
#Sta/Elev= 30
  3929.8  480.94  4053.9  479.22  4084.4  479.29  4104.8  478.31  4144.8  478.13
  4176.0  476.69  4202.0  477.71  4247.3  476.32  4400.0  474.61  4461.1  474.51
  4562.9  472.77  4686.1  472.43  4733.1  470.93  4756.4  471.03  4797.1  469.00
  4888.7  468.35  4899.5  468.90  4944.5  468.00  4944.7  467.50  4948.2  467.50
  4948.5  468.00  4951.6  468.58  4960.0  468.21  4990.5  468.93  5026.7  470.20
  5053.8  471.91  5084.3  472.64  5324.2  472.60  5432.4  473.27  5602.6  472.84
#Mann=3,-1,0
  3929.8    0.05       0  4944.5    0.04       0  4948.5    0.05       0
Bank Sta=4944.5,4948.5
Exp/Cntr=0.3,0.1

Type RM Length L Ch R = 1,1159,22,22,22
BEGIN DESCRIPTION:
Mapping XS 8829df1e
END DESCRIPTION:
XS GIS Cut Line= 5
      2637724.77      6948197.15      2637234.32      6948659.39
      2637078.07      6948783.09      2637058.54      6948800.45
      2636624.61      6949222.08
#Sta/Elev= 30
  4106.2  480.07  4150.4  480.12  4186.0  478.23  4221.2  478.92  4263.7  476.61
  4284.7  477.40  4292.0  475.80  4298.9  477.34  4306.2  475.67  4313.1  476.75
  4320.4  475.19  4327.2  476.44  4348.7  474.69  4355.6  476.31  4377.0  476.45
  4405.3  473.91  4433.6  473.35  4574.8  472.82  4596.3  471.33  4723.3  469.39
  4765.8  470.26  4794.0  468.32  5069.4  467.69  5069.6  467.19  5073.4  467.69
  5403.7  471.49  5468.1  470.48  5599.8  470.03  5609.5  470.64  5610.6  470.64
#Mann=6,-1,0
  4106.2    0.05       0  5069.4    0.05       0  5073.4    0.05       0
  5468.1   0.075       0  5599.8    0.05       0  5609.5   0.075       0
Bank Sta=5069.4,5073.4
Exp/Cntr=0.3,0.1

Type RM Length L Ch R = 1,1137,430,430,430
BEGIN DESCRIPTION:
Mapping XS 7e40b260
END DESCRIPTION:
XS GIS Cut Line= 4
      2637698.74      6948168.93      2637047.69      6948780.92
      2636637.53      6949165.04      2636502.08      6949276.83
#Sta/Elev= 30
  4105.0  479.93  4518.9  471.75  4780.7  469.91  4830.0  468.05  4836.9  469.03
  4858.3  467.73  4879.4  468.53  4886.7  467.47  4921.9  468.20  4957.5  467.11
  4964.3  468.26  4996.3  466.49  5002.3  466.49  5006.8  468.22  5021.0  468.27
  5035.2  466.41  5042.0  467.38  5049.3  465.85  5056.2  467.49  5070.3  466.99
  5075.7  464.81  5075.9  464.31  5079.7  464.81  5084.5  467.25  5106.0  466.82
  5112.8  468.03  5382.0  471.35  5436.8  470.43  5721.8  469.08  5736.1  469.94
#Mann=4,-1,0
  4105.0    0.05       0  5075.7    0.03       0  5079.7    0.05       0
  5436.8   0.075       0
Bank Sta=5075.7,5079.7
Exp/Cntr=0.3,0.1

Type RM Length L Ch R = 1,707,553,553,553
BEGIN DESCRIPTION:
Mapping XS a48bb39a
END DESCRIPTION:
XS GIS Cut Line= 3
      2637264.72      6948014.84      2636698.29      6948631.18
      2636542.05      6949182.38
#Sta/Elev= 30
  4161.7  481.43  4193.6  481.91  4214.6  481.08  4299.6  480.65  4398.9  476.18
  4519.1  471.92  4605.7  469.99  4636.9  469.65  4681.9  468.35  4717.1  468.72
  4831.8  467.69  4858.9  467.30  4950.7  463.79  5030.3  464.39  5038.2  462.14
  5038.4  461.64  5042.2  462.14  5059.0  464.30  5092.1  465.56  5098.1  466.58
  5103.3  466.14  5123.3  467.95  5132.0  467.31  5144.1  468.26  5171.1  468.58
  5283.3  468.75  5341.6  469.24  5362.4  470.24  5400.6  470.08  5571.7  469.81
#Mann=7,-1,0
  4161.7    0.05       0  4605.7   0.075       0  4636.9     0.1       0
  4831.8    0.05       0  5038.2    0.03       0  5042.2    0.05       0
  5400.6   0.075       0
Bank Sta=5038.2,5042.2
Exp/Cntr=0.3,0.1

Type RM Length L Ch R = 1,154,0,0,0
BEGIN DESCRIPTION:
Little Brushy Creek Trib 9 2.0
END DESCRIPTION:
XS GIS Cut Line= 4
      2637060.71      6947904.18      2636160.10      6948283.96
      2636216.33      6948621.80      2636539.89      6949221.48
#Sta/Elev= 30
  3680.1  480.65  3706.0  479.58  3788.0  480.13  4017.8  472.10  4147.2  470.34
  4253.0  467.63  4564.8  463.94  4696.6  463.86  4843.9  464.14  4895.9  465.33
  4904.8  464.52  4909.8  466.93  4928.2  464.38  4970.7  463.70  4995.1  459.46
  4995.3  458.96  4999.1  459.46  5021.8  460.95  5044.5  459.63  5051.1  460.74
  5094.9  462.38  5154.9  462.47  5220.5  466.09  5258.6  466.88  5324.3  467.85
  5346.2  466.40  5403.3  466.47  5471.9  467.32  5521.8  469.24  5681.4  469.88
#Mann=6,-1,0
  3680.1    0.05       0  4696.6   0.075       0  4895.9    0.05       0
  4995.1    0.03       0  4999.1    0.05       0  5403.3   0.075       0
Bank Sta=4995.1,4999.1
Exp/Cntr=0.3,0.1

Chan Stop Cuts=-1