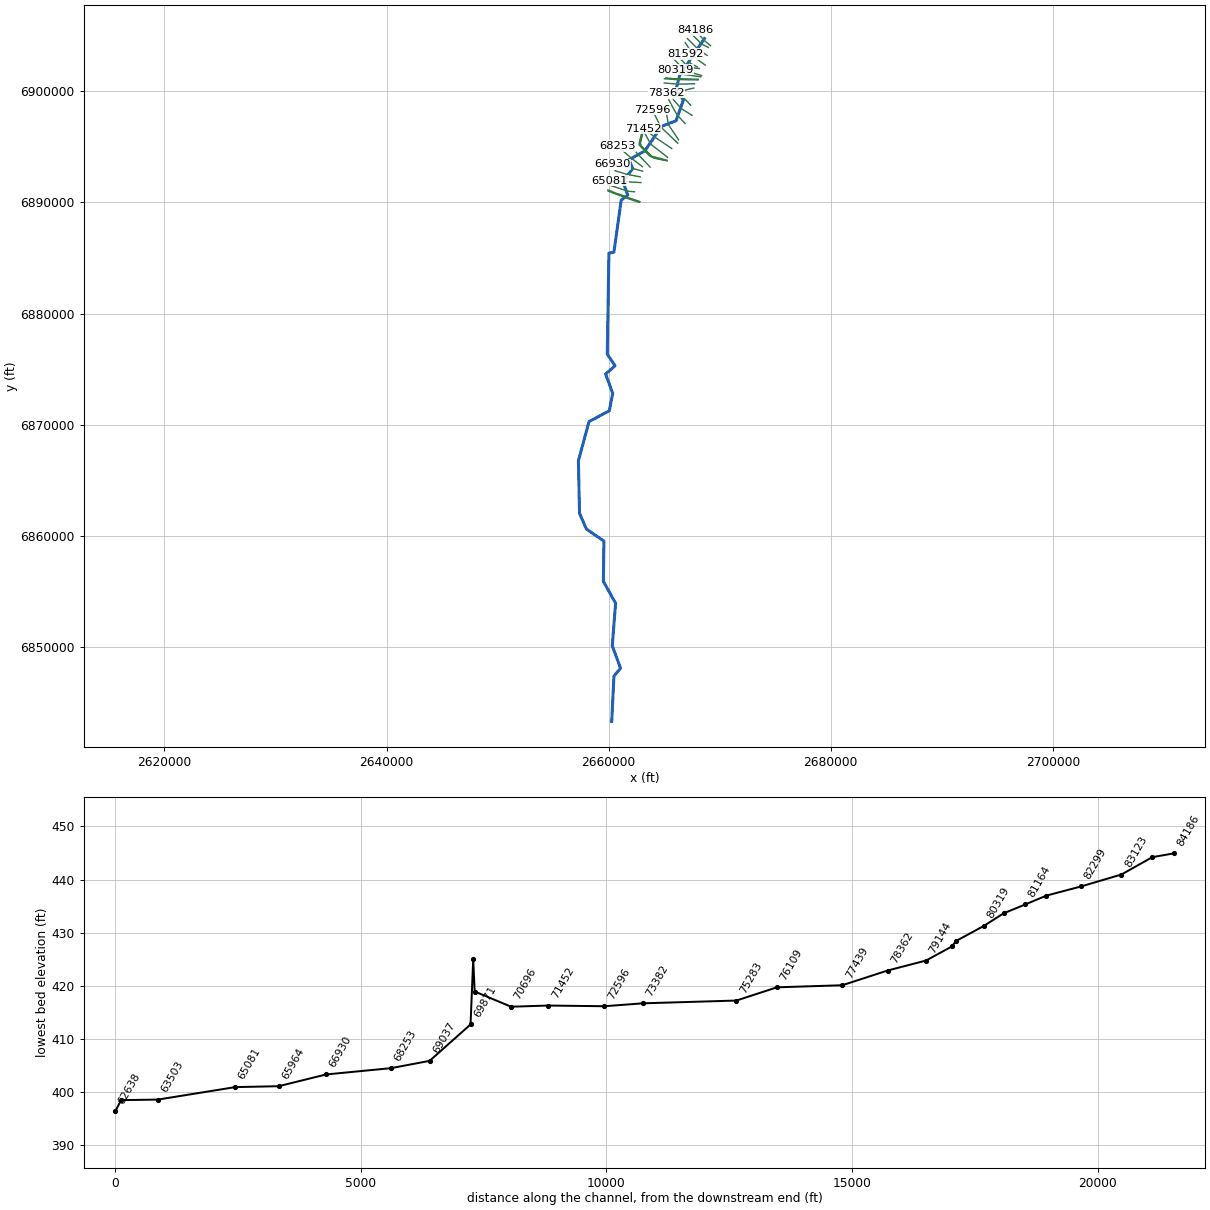
--- Little Cottonwood Creek.prj (project) ---

Proj Title=Little Cottonwood Creek Base Level Engineering
Current Plan=p01
Default Exp/Contr=0.3,0.1
English Units
Geom File=g01
Flow File=f01
Plan File=p01
Y Axis Title=Elevation
X Axis Title(PF)=Main Channel Distance
X Axis Title(XS)=Station
BEGIN DESCRIPTION:
Little Cottonwood Creek
END DESCRIPTION:
DSS Export Rating Curves= 0
DSS Export Rating Curve Sorted= 0
DSS Export Volume Flow Curves= 0
DXF OffsetX= 0
DXF OffsetY= 0
DXF ScaleX= 1
DXF ScaleY= 10

--- Little Cottonwood Creek.p01 (plan) ---

Plan Title=Multiple Run
Short Identifier=Multiple
Geom File=g01
Flow File=f01
Subcritical Flow
K Sum by GR= 0
Std Step Tol= 0.01
Critical Tol= 0.01
Num of Std Step Trials= 20
Max Error Tol= 0.3
Flow Tol Ratio= 0.001
Split Flow NTrial= 30
Split Flow Tol= 0.02
Split Flow Ratio= 0.02
Log Output Level= 0
Friction Slope Method= 1
Unsteady Friction Slope Method= 2
Unsteady Bridges Friction Slope Method= 1
Parabolic Critical Depth
Global Vel Dist=  1 , 1 , 1
Global Log Level= 0
CheckData=True
Encroach Param= -1, 0, 0, 0
BEGIN DESCRIPTION:
Multiple Run
END DESCRIPTION:

--- Little Cottonwood Creek.f01 (steady flow) ---

Flow Title=Multiple
Program Version=4.10
Number of Profiles= 7
Profile Names=10-year,25-year,50-year,1pct_min,100-year,1pct_plu,500-year
River Rch & RM=Little Cottonwoo,Reach-1         ,84186
     511     676     807     478     954    1903    1331
River Rch & RM=Little Cottonwoo,Reach-1         ,82299
     737     998    1210     727    1450    2893    2082
River Rch & RM=Little Cottonwoo,Reach-1         ,77439
    1284    1780    2190    1332    2658    5303    3919
River Rch & RM=Little Cottonwoo,Reach-1         ,70696
    1323    1834    2258    1373    2740    5467    4039
River Rch & RM=Little Cottonwoo,Reach-1         ,69037
    1491    2076    2564    1563    3119    6223    4623
River Rch & RM=Little Cottonwoo,Reach-1         ,61954
    1632    2275    2810    1713    3418    6819    5064
River Rch & RM=Little Cottonwoo,Reach-1         ,50851
    1682    2347    2900    1769    3529    7042    5235
River Rch & RM=Little Cottonwoo,Reach-1         ,50110
    2501    3546    4430    2728    5443   10860    8231
River Rch & RM=Little Cottonwoo,Reach-1         ,43804
    2912    4150    5205    3216    6417   12804    9770
River Rch & RM=Little Cottonwoo,Reach-1         ,39843
    2932    4176    5235    3233    6451   12871    9811
River Rch & RM=Little Cottonwoo,Reach-1         ,37549
    2937    4183    5242    3237    6459   12888    9821
River Rch & RM=Little Cottonwoo,Reach-1         ,35676
    3188    4553    5717    3536    7055   14076   10761
River Rch & RM=Little Cottonwoo,Reach-1         ,34900
    3206    4581    5754    3561    7104   14175   10845
River Rch & RM=Little Cottonwoo,Reach-1         ,33589
    3313    4739    5956    3687    7358   14680   11244
River Rch & RM=Little Cottonwoo,Reach-1         ,31845
    3969    5699    7184    4457    8893   17745   13650
River Rch & RM=Little Cottonwoo,Reach-1         ,24387
    4097    5877    7404    4590    9159   18275   14036
River Rch & RM=Little Cottonwoo,Reach-1         ,14679
    4322    6181    7772    4809    9595   19144   14637
Boundary for River Rch & Prof#=Little Cottonwoo,Reach-1         , 1
Up Type= 0
Dn Type= 3
Dn Slope=0.00107
Boundary for River Rch & Prof#=Little Cottonwoo,Reach-1         , 2
Up Type= 0
Dn Type= 3
Dn Slope=0.00107
Boundary for River Rch & Prof#=Little Cottonwoo,Reach-1         , 3
Up Type= 0
Dn Type= 3
Dn Slope=0.00107
Boundary for River Rch & Prof#=Little Cottonwoo,Reach-1         , 4
Up Type= 0
Dn Type= 3
Dn Slope=0.00107
Boundary for River Rch & Prof#=Little Cottonwoo,Reach-1         , 5
Up Type= 0
Dn Type= 3
Dn Slope=0.00107
Boundary for River Rch & Prof#=Little Cottonwoo,Reach-1         , 6
Up Type= 0
Dn Type= 3
Dn Slope=0.00107
Boundary for River Rch & Prof#=Little Cottonwoo,Reach-1         , 7
Up Type= 0
Dn Type= 3
Dn Slope=0.00107
DSS Import GetInterval= 0
DSS Import GetPeak= 0
DSS Import FillOption= 0

--- Little Cottonwood Creek.g01 (geometry) ---

Geom Title=Existing Conditions
Program Version=4.10

River Reach=Little Cottonwoo,Reach-1
Reach XY= 30
        2668626.        6904761.      2666379.55      6901409.53
      2666077.05      6900221.43        2666726.        6899211.
      2666070.88      6897358.71      2664762.66      6896847.64
      2663249.73      6894634.12      2661827.49      6893849.56
      2662168.53      6893057.38       2661275.2      6891880.93
      2661725.07      6890671.49      2661128.05      6890205.16
      2660473.95      6885516.84      2660025.76      6885440.64
      2659875.57      6876335.62      2660576.79      6875295.62
      2659725.16       6874546.2      2660368.21      6872807.57
      2660063.02      6871247.43      2658231.46      6870263.45
      2657276.02      6866745.19      2657378.06      6862016.85
      2657992.04      6860593.96      2659572.46      6859509.54
      2659526.74      6855871.66        2660626.        6853911.
       2660325.7      6850081.18      2661068.83       6848061.3
      2660477.05      6847350.57        2660276.        6843261.

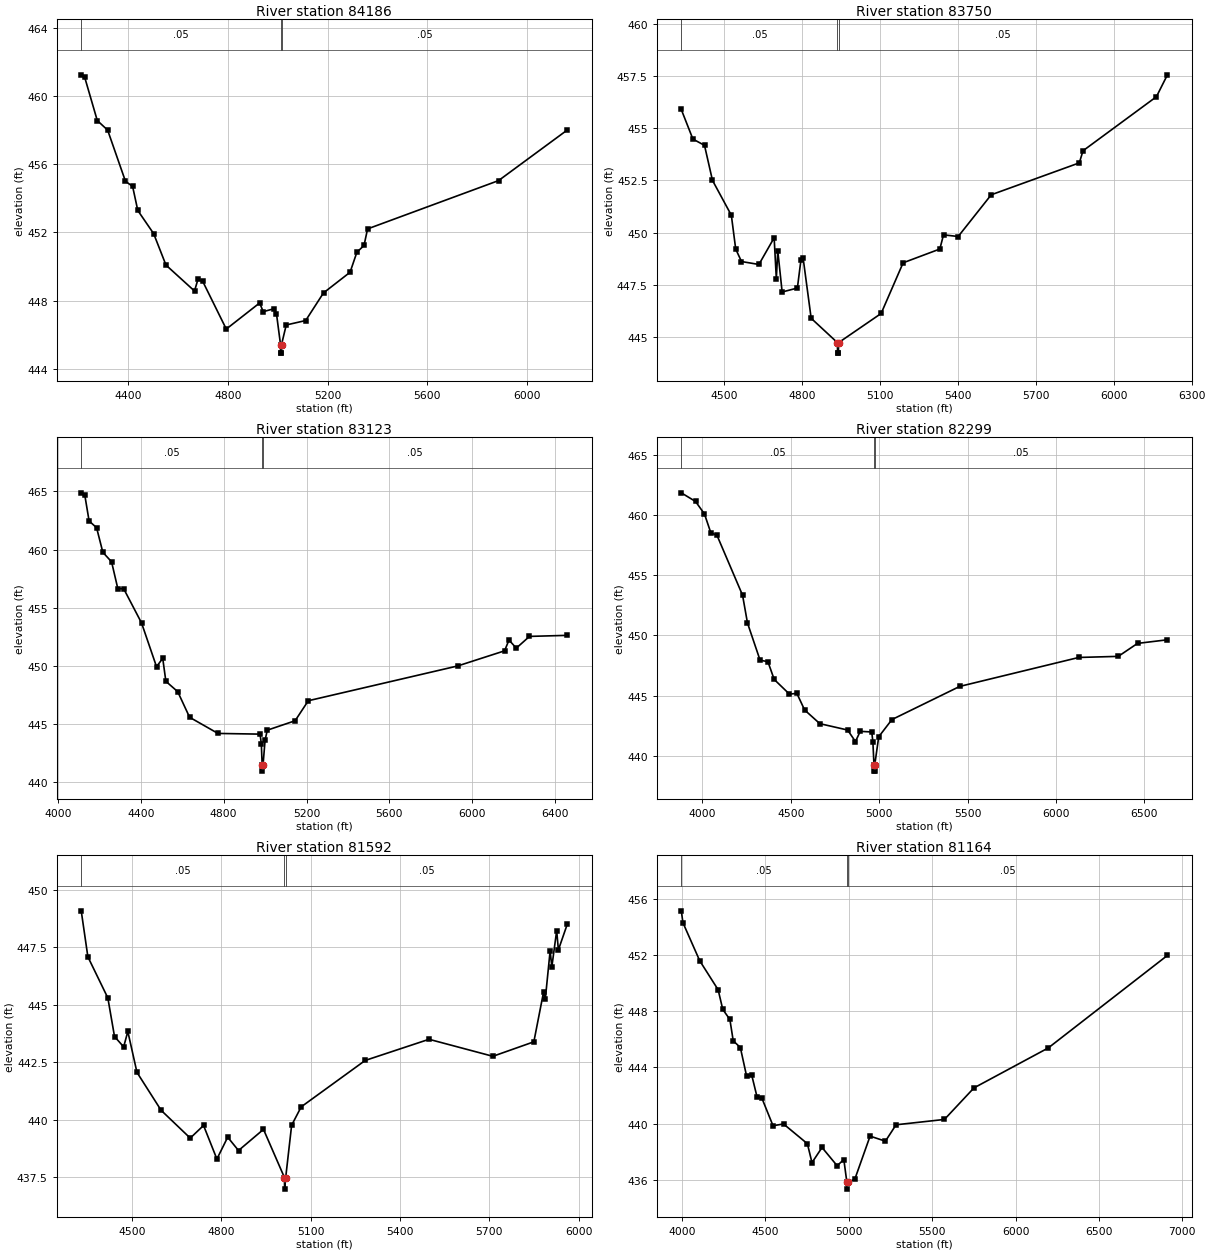
Type RM Length L Ch R = 1 ,84186   ,436,436,436
BEGIN DESCRIPTION:
Little Cottonwood Creek 123.0
END DESCRIPTION:
XS GIS Cut Line= 3
      2669176.04      6904110.97        2668576.        6904611.
      2667826.01      6905510.99
#Sta/Elev= 30
  4210.5  461.24  4224.2  461.11    4275  458.56  4316.6     458  4388.2     455
  4416.9   454.7  4437.7  453.29  4501.5  451.93  4550.9  450.09  4665.5  448.57
  4679.2  449.25  4698.7  449.13  4793.1  446.34  4927.1  447.87  4941.5  447.36
  4984.4  447.53  4994.8  447.23    5011  445.43  5011.3  444.93  5014.8  444.93
    5015  445.43  5033.9  446.58    5112  446.84  5183.6  448.46  5290.3  449.67
  5317.6  450.84  5346.3  451.24  5360.6  452.21  5886.5  455.04  6163.1  458.01
#Mann= 3 ,-1 , 0
  4210.5     .05       0    5011     .04       0    5015     .05       0
Bank Sta=5011,5015
XS Rating Curve= 0 ,0
Exp/Cntr=0.3,0.1

Type RM Length L Ch R = 1 ,83750   ,627,627,627
BEGIN DESCRIPTION:
Little Cottonwood Creek 122.0
END DESCRIPTION:
XS GIS Cut Line= 3
      2668976.04      6903960.98        2668376.        6904261.
      2667526.03      6905110.97
#Sta/Elev= 30
  4333.7   455.9  4378.5  454.48  4423.2  454.18  4453.9   452.5  4526.6  450.83
  4543.4  449.21  4565.7  448.61  4632.8  448.47  4691.5  449.75  4699.9  447.79
  4705.5  449.12  4722.3  447.15    4781  447.34  4794.9   448.7  4803.3  448.76
  4834.1  445.89  4935.5  444.72  4935.7  444.22  4939.2  444.22  4939.5  444.72
  5103.6  446.12  5188.4  448.55  5329.8  449.21    5344  449.89  5400.5  449.81
  5527.8  451.81  5867.2  453.34  5881.4  453.92  6164.2  456.51  6206.6  457.56
#Mann= 3 ,-1 , 0
  4333.7     .05       0  4935.5     .04       0  4939.5     .05       0
Bank Sta=4935.5,4939.5
XS Rating Curve= 0 ,0
Exp/Cntr=0.3,0.1

Type RM Length L Ch R = 1 ,83123   ,824,824,824
BEGIN DESCRIPTION:
Little Cottonwood Creek 120.0
END DESCRIPTION:
XS GIS Cut Line= 3
      2668867.44      6903238.17      2668125.84      6903726.06
      2667092.92      6904756.62
#Sta/Elev= 30
  4112.3  464.88  4129.3  464.71  4150.3  462.46  4186.5  461.88  4216.6  459.77
  4258.8  458.95  4288.9  456.65  4317.5  456.63  4403.4   453.7  4475.7  449.94
  4505.8  450.65  4520.9  448.68  4578.1  447.79  4635.4  445.59  4772.4   444.2
  4975.8  444.14  4981.8  443.28  4985.8  441.46  4986.1  440.96  4989.8  441.46
  4999.9  443.63  5010.5  444.48  5144.8  445.29  5208.4  447.01  5929.7     450
    6156   451.3  6177.2  452.23  6212.5  451.53  6276.2  452.54  6459.1  452.63
#Mann= 3 ,-1 , 0
  4112.3     .05       0  4985.8     .04       0  4989.8     .05       0
Bank Sta=4985.8,4989.8
XS Rating Curve= 0 ,0
Exp/Cntr=0.3,0.1

Type RM Length L Ch R = 1 ,82299   ,707,707,707
BEGIN DESCRIPTION:
Little Cottonwood Creek 118.0
END DESCRIPTION:
XS GIS Cut Line= 3
      2668698.18       6902370.1      2667787.14      6903020.53
      2666899.19      6904388.28
#Sta/Elev= 30
  3880.6  461.87  3961.4  461.15  4011.8  460.11  4047.4  458.56    4083  458.32
  4227.3  453.35  4255.1  451.04  4326.4  447.94  4370.6  447.82  4406.3  446.34
  4492.3  445.12  4534.5  445.18  4578.3   443.8  4664.4  442.66  4821.7  442.13
  4865.9  441.17  4892.9  442.02  4958.1  441.97  4964.5  441.15  4970.8  439.21
  4971.1  438.71  4974.6  438.71  4974.8  439.21  4997.6  441.57  5072.2     443
  5455.8  445.76  6129.4  448.17  6352.8  448.26  6461.6  449.34  6630.7  449.64
#Mann= 3 ,-1 , 0
  3880.6     .05       0  4970.8     .03       0  4974.8     .05       0
Bank Sta=4970.8,4974.8
XS Rating Curve= 0 ,0
Exp/Cntr=0.3,0.1

Type RM Length L Ch R = 1 ,81592   ,428,428,428
BEGIN DESCRIPTION:
Little Cottonwood Creek 117.0
END DESCRIPTION:
XS GIS Cut Line= 3
      2667975.97      6902211.02        2667376.        6902511.
      2666925.98      6903361.04
#Sta/Elev= 30
  4329.2  449.09  4351.5  447.09  4418.6   445.3    4441  443.62  4471.7  443.17
  4485.7  443.84  4516.4  442.06  4597.5  440.41  4695.3   439.2    4740  439.75
  4784.8  438.29  4821.1  439.24  4857.4  438.66  4941.3  439.58  5011.8  437.48
  5012.1  436.98  5015.8  437.48  5035.8  439.76  5067.9  440.56  5282.9  442.58
  5497.2   443.5  5711.6  442.76  5849.2  443.39  5881.9  445.56  5887.6  445.24
  5903.9  447.35  5909.6  446.65  5925.9  448.23  5931.6  447.39  5961.8  448.52
#Mann= 3 ,-1 , 0
  4329.2     .05       0  5011.8     .04       0  5015.8     .05       0
Bank Sta=5011.8,5015.8
XS Rating Curve= 0 ,0
Exp/Cntr=0.3,0.1

Type RM Length L Ch R = 1 ,81164   ,441,441,441
BEGIN DESCRIPTION:
Little Cottonwood Creek 116.0
END DESCRIPTION:
XS GIS Cut Line= 3
      2668176.04        6902061.        2667176.        6902161.
      2665876.02      6903560.98
#Sta/Elev= 30
  3995.3  455.17  4005.4  454.32  4105.9  451.61  4216.4  449.54  4244.1  448.14
  4286.8  447.42  4306.9   445.9  4349.6  445.42  4387.3  443.37  4417.4  443.47
  4450.1  441.88  4477.7  441.84  4545.6  439.84  4608.4  439.97  4751.6  438.56
  4779.2  437.21  4839.5  438.29    4930  436.99  4970.2  437.43  4988.3  435.82
  4988.5  435.32  4992.3  435.82  5035.8  436.02  5127.6   439.1  5219.5  438.74
  5283.5  439.91  5573.5  440.29  5750.6  442.54  6196.2  445.39  6910.8  451.99
#Mann= 3 ,-1 , 0
  3995.3     .05       0  4988.3     .04       0  4992.3     .05       0
Bank Sta=4988.3,4992.3
XS Rating Curve= 0 ,0
Exp/Cntr=0.3,0.1

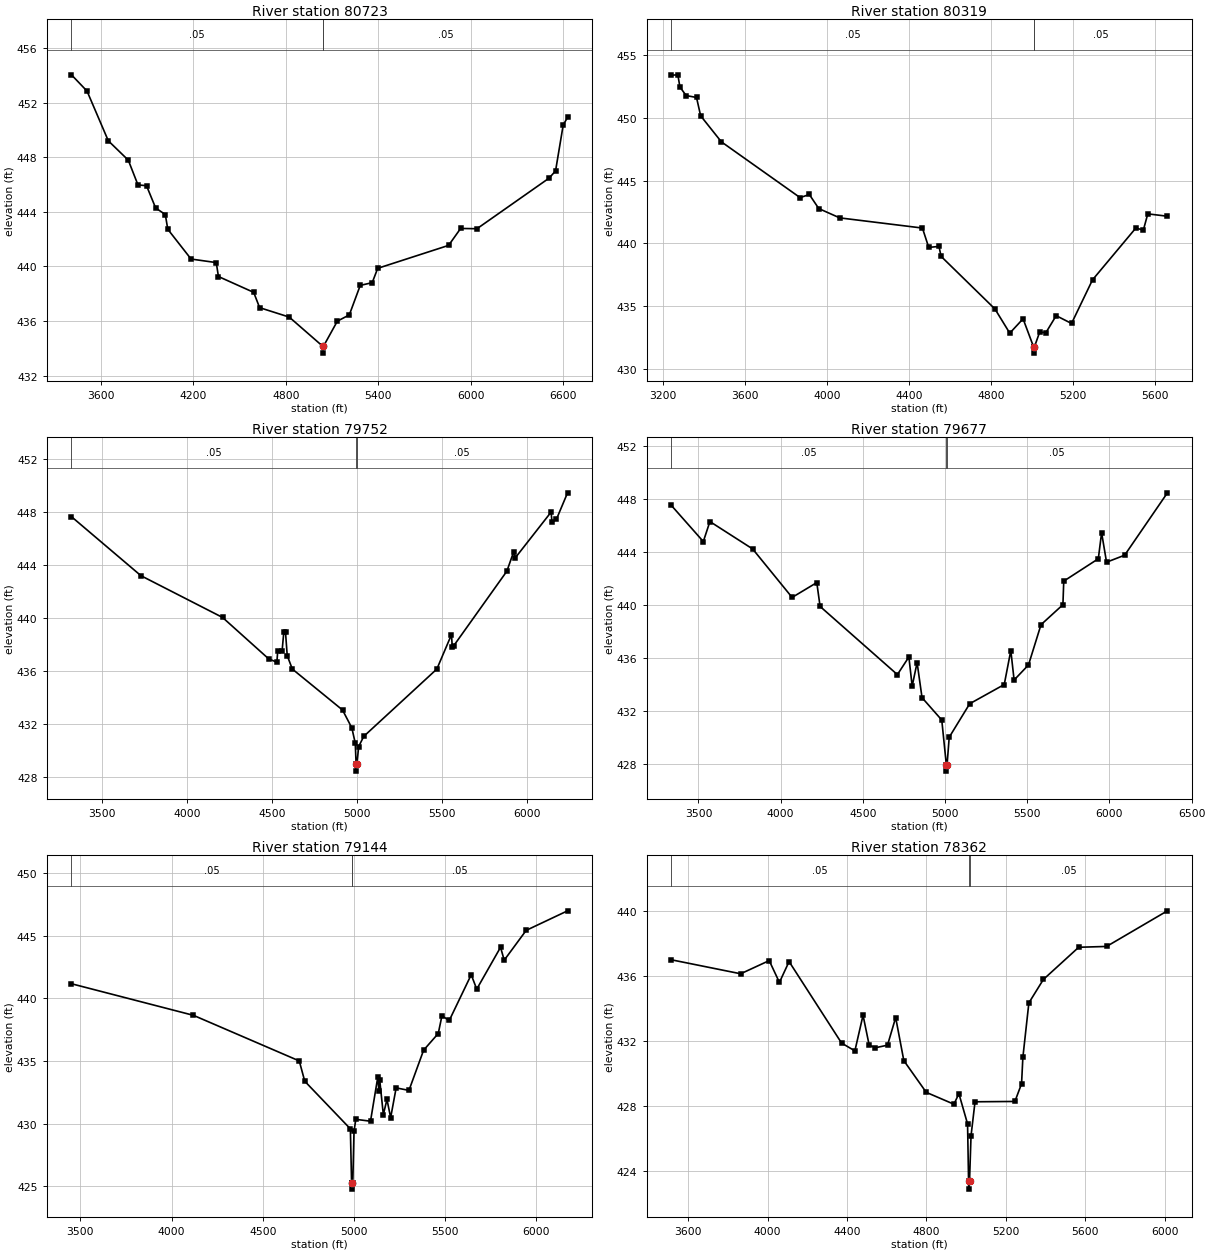
Type RM Length L Ch R = 1 ,80723   ,404,404,404
BEGIN DESCRIPTION:
Little Cottonwood Creek 115.0
END DESCRIPTION:
XS GIS Cut Line= 3
      2668369.04      6901427.67      2666845.92      6901881.18
      2665726.01      6903060.99
#Sta/Elev= 30
  3410.8  454.03  3511.6  452.84  3649.5   449.2  3779.2  447.78  3841.8  445.97
  3897.3  445.91  3956.5  444.28  4019.1   443.8  4035.2  442.72  4186.1  440.54
  4349.4  440.28  4363.5  439.26  4592.1   438.1  4630.5  436.98  4822.5  436.29
    5040  434.15  5040.3  433.65  5044.3  434.15  5134.3  435.99    5212  436.45
  5282.8  438.61  5360.4  438.81    5396  439.86  5855.6  441.54  5933.6  442.78
  6039.6  442.76  6506.4  446.46  6548.9  446.99  6598.6  450.36  6626.7  450.91
#Mann= 3 ,-1 , 0
  3410.8     .05       0    5040     .04       0  5044.3     .05       0
Bank Sta=5040,5044.3
XS Rating Curve= 0 ,0
Exp/Cntr=0.3,0.1

Type RM Length L Ch R = 1 ,80319   ,567,567,567
BEGIN DESCRIPTION:
Little Cottonwood Creek 113.0
END DESCRIPTION:
XS GIS Cut Line= 3
      2668297.38      6901313.03      2666702.39        6901536.
      2666002.42      6901935.98
#Sta/Elev= 30
  3242.1  453.38  3273.8  453.41  3283.9  452.44  3314.2  451.76  3364.7  451.61
  3384.9  450.15  3485.8  448.08  3869.5  443.64  3914.3  443.89  3960.4  442.77
  4062.3  442.03  4465.3  441.22    4496  439.68    4546  439.76  4556.1  438.97
  4818.7  434.78  4890.8  432.86  4955.6     434  5006.7  431.77  5007.1  431.27
    5011  431.77  5036.2  432.93  5067.3  432.91  5116.9  434.25  5191.7  433.63
  5293.9   437.1  5504.9  441.22  5541.6  441.06  5563.2  442.35  5658.8  442.16
#Mann= 3 ,-1 , 0
  3242.1     .05       0  5006.7     .04       0    5011     .05       0
Bank Sta=5006.7,5011
XS Rating Curve= 0 ,0
Exp/Cntr=0.3,0.1

Type RM Length L Ch R = 1 ,79752   ,75,75,75
BEGIN DESCRIPTION:
Mapping XS 6d39a71a
END DESCRIPTION:
XS GIS Cut Line= 4
      2668054.42      6901094.27      2666375.99      6901138.21
      2665793.96      6901146.36      2665141.13      6901215.81
#Sta/Elev= 30
    3321  447.62  3729.6  443.17  4209.7  440.02  4479.8  436.91  4529.1  436.64
  4534.1   437.5  4559.8   437.5  4569.8  438.92  4579.8  438.91  4589.9  437.14
  4619.9  436.13  4915.2  433.04    4970  431.69    4990  430.54  4995.2  428.93
  4995.6  428.43  4999.8  428.93    5010  430.28    5040  431.05    5470  436.13
  5555.8  438.72  5560.8  437.79    5570   437.9  5881.7  443.51    5922  444.98
    5932  444.53    6142  447.97  6147.1   447.2  6173.4  447.43  6238.6  449.42
#Mann= 3 ,-1 , 0
    3321     .05       0  4995.2     .04       0  4999.8     .05       0
Bank Sta=4995.2,4999.8
XS Rating Curve= 0 ,0
Exp/Cntr=0.3,0.1

Type RM Length L Ch R = 1 ,79677   ,533,533,533
BEGIN DESCRIPTION:
Mapping XS 7c6becb2
END DESCRIPTION:
XS GIS Cut Line= 5
      2668040.51      6901031.77      2666350.45      6901063.56
      2665918.16      6901068.77      2665787.01      6901087.33
      2665026.63      6901139.41
#Sta/Elev= 30
  3335.2  447.52  3529.7  444.79  3569.8   446.3  3829.8  444.23  4069.8  440.57
  4219.9  441.69  4239.9  439.89    4710  434.74    4780  436.07    4800  433.87
    4830  435.65    4860     433    4980  431.31  5007.7  427.95  5008.2  427.45
  5012.4  427.95  5025.3  430.01    5150  432.54    5360  433.99    5400  436.56
    5420  434.33  5507.5  435.47  5583.6  438.51  5716.9  440.02    5722   441.8
  5932.2  443.49  5952.2  445.46  5982.3  443.23  6092.5  443.76  6352.5  448.47
#Mann= 3 ,-1 , 0
  3335.2     .05       0  5007.7     .03       0  5012.4     .05       0
Bank Sta=5007.7,5012.4
XS Rating Curve= 0 ,0
Exp/Cntr=0.3,0.1

Type RM Length L Ch R = 1 ,79144   ,782,782,782
BEGIN DESCRIPTION:
Mapping XS f97c5b50
END DESCRIPTION:
XS GIS Cut Line= 3
      2667724.49      6900684.55      2666182.85       6900653.3
      2665010.12      6900757.39
#Sta/Elev= 30
  3451.1  441.16  4119.7  438.64  4699.8     435  4729.9  433.38  4979.9  429.58
  4986.6  425.27  4987.1  424.77  4991.3  425.27  4993.1  425.27  4999.9   429.4
    5010  430.34  5090.3  430.19  5130.4  433.73  5136.1  432.59  5141.1  433.44
  5160.6  430.72  5180.6  431.93  5200.7  430.47  5230.8  432.85  5301.1  432.65
  5381.4  435.86  5461.7  437.19  5481.8   438.6    5522  438.23  5642.4  441.88
  5672.6  440.73  5803.1  444.07  5823.2  443.04  5943.6  445.42  6170.4  446.98
#Mann= 3 ,-1 , 0
  3451.1     .05       0  4986.6     .03       0  4991.3     .05       0
Bank Sta=4986.6,4991.3
XS Rating Curve= 0 ,0
Exp/Cntr=0.3,0.1

Type RM Length L Ch R = 1 ,78362   ,923,923,923
BEGIN DESCRIPTION:
Little Cottonwood Creek 111.0
END DESCRIPTION:
XS GIS Cut Line= 3
      2667675.87       6900302.6        2666226.        6899961.
      2665221.01      6899868.58
#Sta/Elev= 30
  3514.9  436.99  3864.1  436.13  4007.9  436.94  4059.3   435.6    4108  436.88
  4372.4  431.87  4439.4  431.39  4480.5  433.58  4511.3  431.75  4541.8  431.58
  4603.8  431.74  4644.9  433.44    4686  430.79    4799  428.84  4938.4  428.11
  4963.4  428.76    5007   426.9  5012.1  423.39  5012.7  422.89  5016.9  423.39
  5024.5  426.17  5044.6  428.26  5245.5  428.28    5279  429.37  5285.6  430.99
  5315.8  434.34  5388.9  435.78  5566.8  437.76  5707.4  437.81  6013.7     440
#Mann= 3 ,-1 , 0
  3514.9     .05       0  5012.1     .03       0  5016.9     .05       0
Bank Sta=5012.1,5016.9
XS Rating Curve= 0 ,0
Exp/Cntr=0.3,0.1

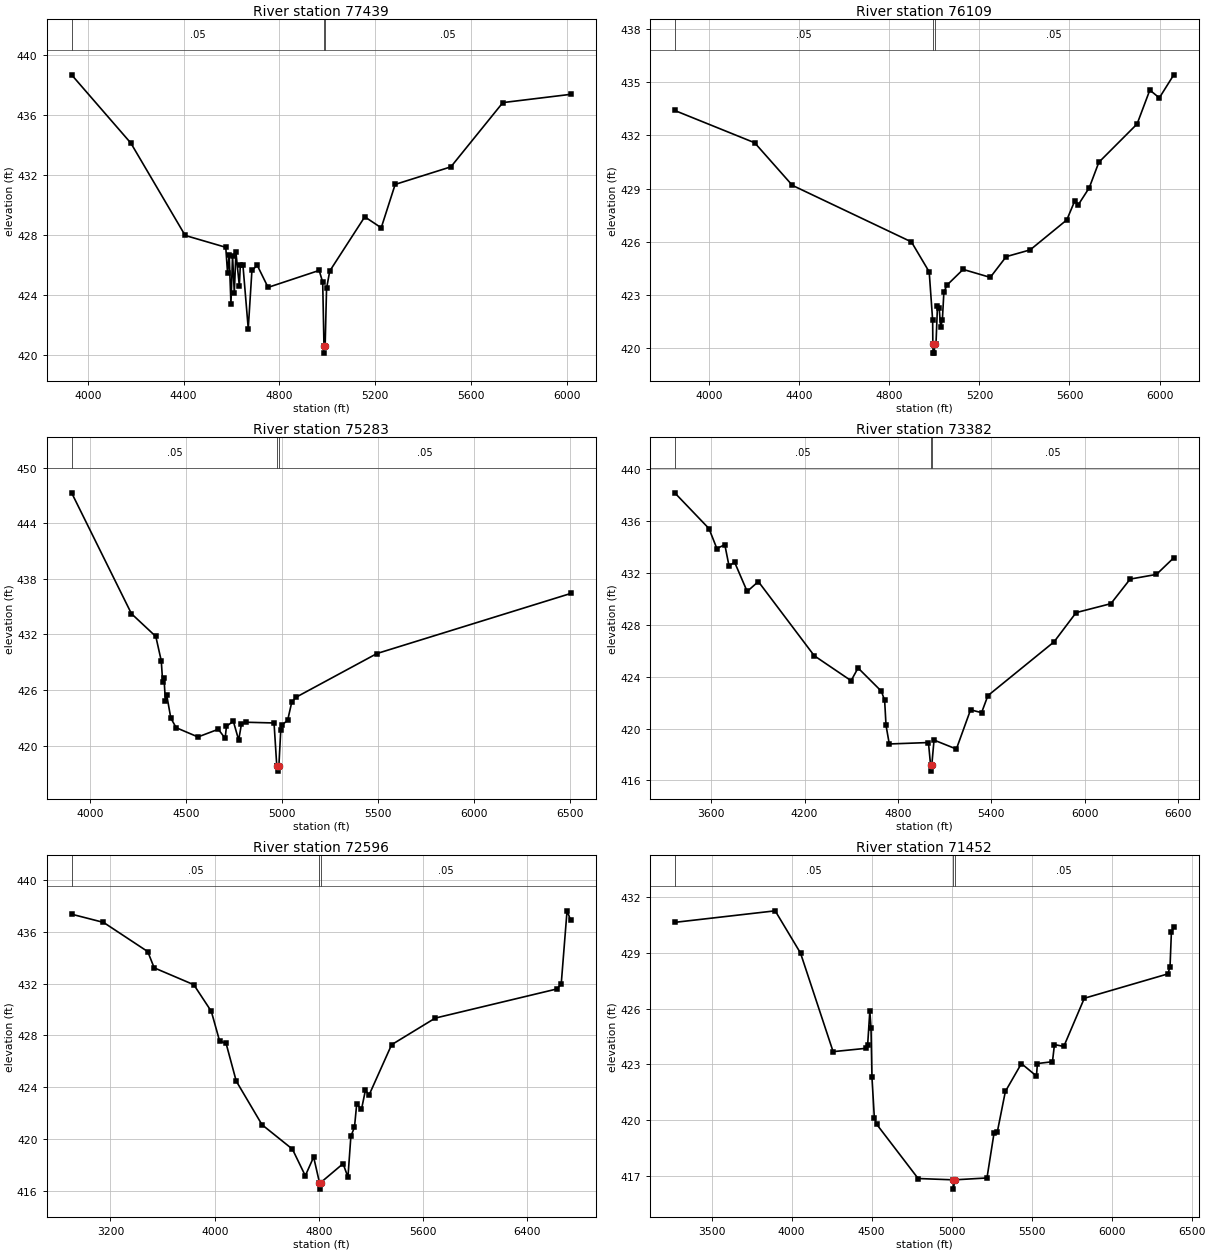
Type RM Length L Ch R = 1 ,77439   ,1330,1330,1330
BEGIN DESCRIPTION:
Little Cottonwood Creek 110.0
END DESCRIPTION:
XS GIS Cut Line= 4
      2667375.98      6898761.02      2666896.01      6899281.87
      2666576.05       6899445.6      2665610.47      6899764.23
#Sta/Elev= 30
  3932.3  438.66  4179.8  434.11  4406.6  427.96  4576.2  427.17  4583.6  425.47
  4590.4  426.68  4597.8  423.41  4604.6  426.59  4611.9  424.14  4618.7  426.83
  4632.9   424.6  4636.9  425.96  4647.9  425.98  4670.1  421.75  4685.5  425.64
    4708  425.96  4752.9   424.5  4966.4  425.63  4981.1  424.84  4986.4  420.62
    4987  420.12  4991.3  420.62  4997.2  424.43  5010.6  425.59  5156.8   429.2
  5225.6  428.47  5283.8  431.36  5516.6  432.53  5733.6  436.81  6016.8  437.36
#Mann= 3 ,-1 , 0
  3932.3     .05       0  4986.4     .03       0  4991.3     .05       0
Bank Sta=4986.4,4991.3
XS Rating Curve= 0 ,0
Exp/Cntr=0.3,0.1

Type RM Length L Ch R = 1 ,76109   ,826,826,826
BEGIN DESCRIPTION:
Little Cottonwood Creek 108.0
END DESCRIPTION:
XS GIS Cut Line= 3
      2667502.32      6897847.73        2666526.        6898461.
      2665825.98      6899261.02
#Sta/Elev= 30
  3847.1  433.41    4202  431.59  4369.3  429.19  4898.2     426  4977.1  424.31
  4992.4  421.58  4993.3  420.23  4994.4  419.73  4999.8  419.73    5001  420.23
  5007.2  420.24  5013.8  422.39  5021.4  422.28  5028.1  421.18  5035.6  421.62
  5042.3  423.17  5056.5  423.57  5127.7  424.45  5248.3     424    5319  425.17
  5425.3  425.55    5588  427.24  5624.1  428.33  5637.9  428.07  5687.7  429.05
  5730.4  430.49  5900.3  432.65  5956.8  434.56    5999  434.12  6063.1  435.42
#Mann= 3 ,-1 , 0
  3847.1     .05       0  4993.3     .04       0    5001     .05       0
Bank Sta=4993.3,5001
XS Rating Curve= 0 ,0
Exp/Cntr=0.3,0.1

Type RM Length L Ch R = 1 ,75283   ,1901,1901,1901
BEGIN DESCRIPTION:
Little Cottonwood Creek 106.0
END DESCRIPTION:
XS GIS Cut Line= 3
      2666875.98      6897111.03      2666132.47      6897917.77
      2665412.17      6899236.35
#Sta/Elev= 30
  3902.9  447.29  4214.5  434.24  4341.5  431.78  4369.9  429.15  4377.2  426.88
    4384  427.32  4391.4  424.85  4398.2  425.46  4419.6  422.97  4447.5  421.93
    4561  420.93    4667  421.76  4702.7  420.78  4709.5  422.08  4745.3  422.63
  4773.2  420.59  4787.2  422.28  4808.8  422.52  4957.4  422.44  4971.5  417.84
  4974.3  417.74  4975.5  417.24  4982.4  417.74  4992.5   421.7  4998.8  422.24
    5028  422.71  5049.9  424.71  5072.1  425.22  5493.7  429.94  6502.5  436.42
#Mann= 3 ,-1 , 0
  3902.9     .05       0  4974.3     .04       0  4982.4     .05       0
Bank Sta=4974.3,4982.4
XS Rating Curve= 0 ,0
Exp/Cntr=0.3,0.1

Type RM Length L Ch R = 1 ,73382   ,786,786,786
BEGIN DESCRIPTION:
Little Cottonwood Creek 104.0
END DESCRIPTION:
XS GIS Cut Line= 3
      2666293.98      6895653.26        2665376.        6897011.
        2665126.      6898561.02
#Sta/Elev= 30
  3364.8  438.14  3584.9  435.39  3635.8  433.85  3686.7  434.15  3713.8  432.52
  3749.7   432.8  3830.6  430.55  3902.5  431.31  4262.1   425.6  4498.9  423.68
  4543.7  424.66  4693.6  422.87  4714.6  422.16  4723.5  420.24  4744.5  418.81
  4996.3  418.92  5009.6  417.22  5010.9  416.72  5018.1  417.22  5032.1  419.11
  5175.9  418.42  5267.1  421.44    5338  421.22  5378.5  422.53    5804  426.67
  5945.8  428.92  6169.6  429.61  6293.2   431.5  6462.4  431.86  6573.8  433.14
#Mann= 3 ,-1 , 0
  3364.8     .05       0  5009.6     .03       0  5018.1     .05       0
Bank Sta=5009.6,5018.1
XS Rating Curve= 0 ,0
Exp/Cntr=0.3,0.1

Type RM Length L Ch R = 1 ,72596   ,1144,1144,1144
BEGIN DESCRIPTION:
Little Cottonwood Creek 101.0
END DESCRIPTION:
XS GIS Cut Line= 3
      2666222.02      6895340.95      2664702.26      6896787.89
      2663925.12      6898335.75
#Sta/Elev= 30
  2901.6  437.34  3146.2  436.71    3486  434.46  3535.3  433.21  3839.5  431.91
  3973.8  429.86  4037.7  427.57    4087   427.4  4165.1  424.49  4362.9  421.13
  4596.3  419.25  4695.3   417.2  4759.2  418.64  4804.1  416.67  4805.4  416.17
    4813  416.67  4985.3  418.13  5022.7  417.09    5045  420.23  5072.9  420.95
  5089.7  422.71  5126.6  422.32  5156.7  423.78  5184.6  423.41  5357.7  427.29
  5692.7  429.34  6625.1  431.58  6659.5  431.95  6704.3   437.6    6732  436.88
#Mann= 3 ,-1 , 0
  2901.6     .05       0  4804.1     .04       0    4813     .05       0
Bank Sta=4804.1,4813
XS Rating Curve= 0 ,0
Exp/Cntr=0.3,0.1

Type RM Length L Ch R = 1 ,71452   ,756,756,756
BEGIN DESCRIPTION:
Little Cottonwood Creek 99.0
END DESCRIPTION:
XS GIS Cut Line= 3
      2665675.89      6894858.17       2664242.7      6895827.65
      2663126.51      6896653.01
#Sta/Elev= 30
  3269.7  430.64  3897.4  431.26  4055.7  428.99  4259.4  423.69  4466.2  423.87
  4475.2  424.05  4488.9  425.87  4496.2  424.97  4502.2  422.31  4517.1  420.13
  4532.1  419.78  4790.8  416.87  5009.4   416.8  5010.7   416.3  5019.2   416.8
  5220.9   416.9  5264.8   419.3  5285.7  419.38  5335.8  421.55    5436  423.05
    5530  422.38  5536.2  423.05  5630.2  423.15  5642.6  424.07  5701.1  423.97
  5829.2  426.56  6351.5  427.87  6364.9  428.26  6373.3   430.1  6388.2  430.38
#Mann= 3 ,-1 , 0
  3269.7     .05       0  5009.4     .03       0  5019.2     .05       0
Bank Sta=5009.4,5019.2
XS Rating Curve= 0 ,0
Exp/Cntr=0.3,0.1

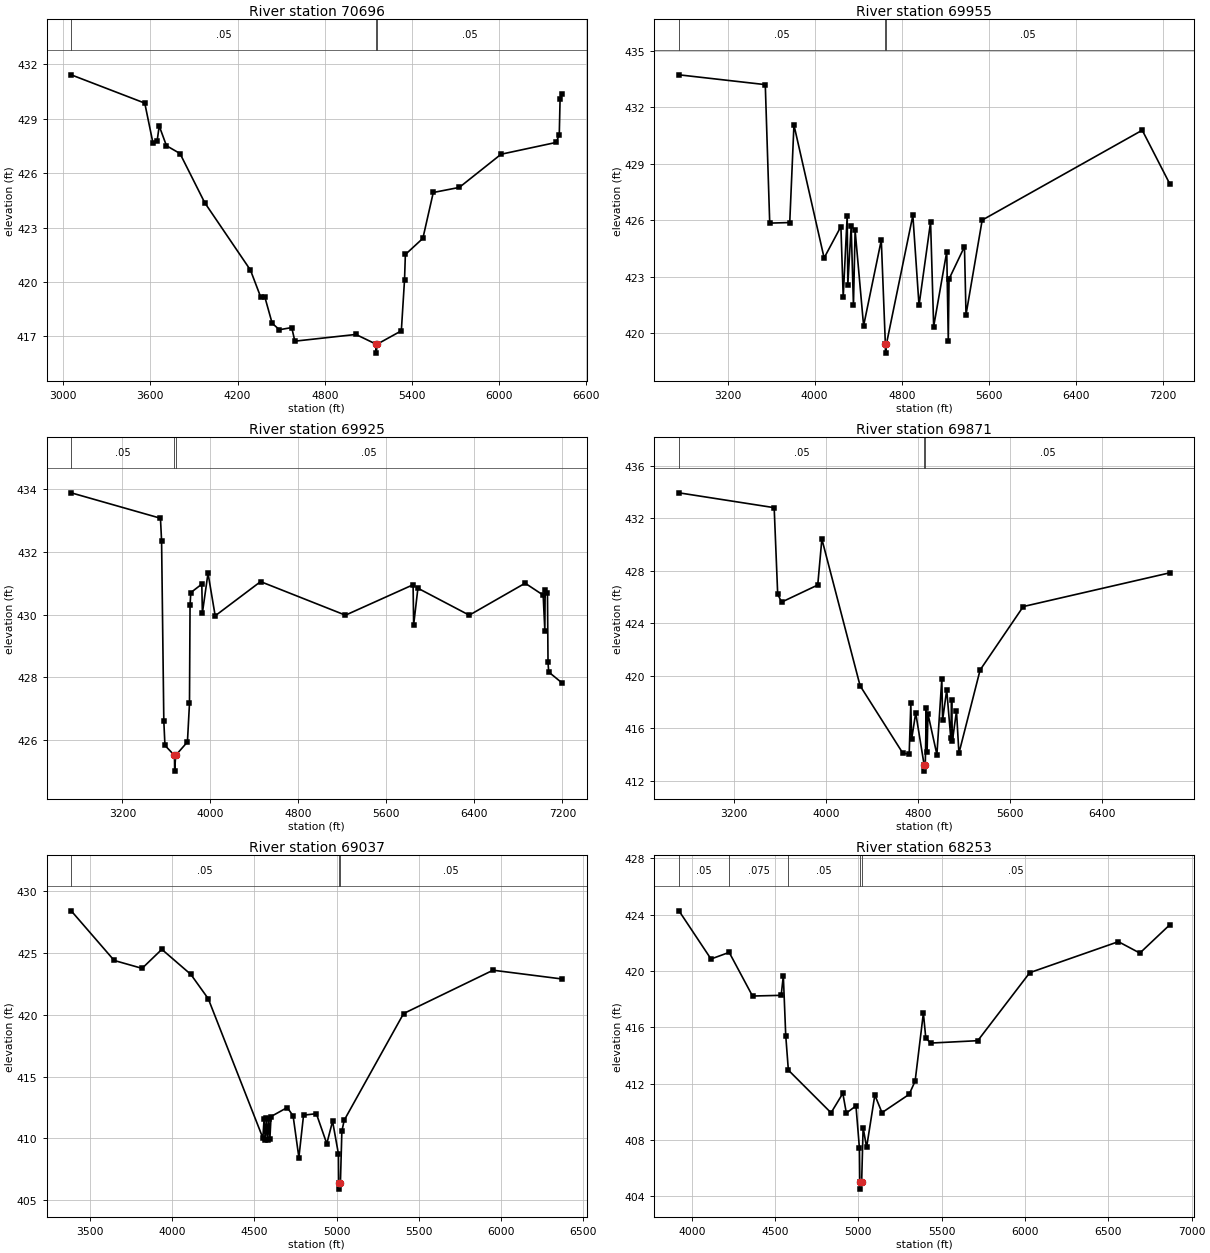
Type RM Length L Ch R = 1 ,70696   ,741,741,741
BEGIN DESCRIPTION:
Little Cottonwood Creek 98.0
END DESCRIPTION:
XS GIS Cut Line= 3
      2665307.88        6894063.        2663776.        6895261.
      2663102.97      6896524.86
#Sta/Elev= 30
  3055.3  431.43  3561.3  429.87  3617.4  427.68  3646.3  427.78  3660.7  428.61
  3710.5  427.52  3803.6  427.09  3973.6  424.38  4288.3  420.66  4358.9  419.17
  4387.8  419.16  4437.5  417.73  4487.3  417.37  4572.3  417.49  4593.8  416.74
  5013.8  417.11  5151.2  416.58  5152.6  416.08  5161.4  416.58  5326.3  417.31
  5348.3  420.13    5354  421.52  5474.4  422.41    5546  424.94  5725.1  425.22
  6012.3  427.05  6390.7   427.7  6412.7  428.11  6418.3  430.09  6431.9  430.36
#Mann= 3 ,-1 , 0
  3055.3     .05       0  5151.2     .03       0  5161.4     .05       0
Bank Sta=5151.2,5161.4
XS Rating Curve= 0 ,0
Exp/Cntr=0.3,0.1

Type RM Length L Ch R = 1 ,69955   ,30,30,30
BEGIN DESCRIPTION:
Mapping XS d842fb17
END DESCRIPTION:
XS GIS Cut Line= 6
      2665252.25      6893799.14      2663888.34      6894158.11
      2662900.49      6895137.71       2662864.9      6895390.75
      2663112.89      6896395.82      2663106.65      6896794.38
#Sta/Elev= 30
  2753.2  433.71  3546.2  433.19  3587.1  425.84    3771  425.87  3809.6  431.05
  4086.9  423.99  4241.1  425.66  4262.3  421.92  4298.8  426.23  4304.7  422.57
  4335.3  425.67  4356.4  421.47  4371.7  425.45  4449.6  420.39  4612.2  424.94
  4649.4  419.44  4650.9  418.94  4659.9  419.44  4902.2  426.25  4958.9  421.47
    5065   425.9  5093.4  420.35  5213.6  424.32  5227.8  419.61  5234.6  422.87
  5376.4  424.59  5390.6  420.98  5539.2     426  7009.8  430.77  7263.2  427.92
#Mann= 3 ,-1 , 0
  2753.2     .05       0  4649.4     .03       0  4659.9     .05       0
Bank Sta=4649.4,4659.9
XS Rating Curve= 0 ,0
Exp/Cntr=0.3,0.1

Type RM Length L Ch R = 1 ,69925   ,54,54,54
BEGIN DESCRIPTION:
Mapping XS 026c60ed
END DESCRIPTION:
XS GIS Cut Line= 6
      2665259.99      6893764.67      2664040.38      6894033.77
      2663671.46       6894263.8      2662881.53      6895118.84
       2662828.9      6895287.62      2663097.01      6896692.45
#Sta/Elev= 30
    2735  433.88  3546.3  433.07  3556.5  432.35  3576.9   426.6  3587.1  425.83
  3673.8  425.51  3675.3  425.01  3684.3  425.51  3791.5  425.94  3810.2  427.17
  3815.3   430.3  3822.1   430.7  3922.1  430.97  3927.4  430.05  3978.6  431.32
  4043.7  429.96  4456.6  431.05  5227.8  429.98  5842.7  430.95  5847.8  429.67
  5886.5  430.84  6353.4  429.98  6861.4     431  7025.2  430.62  7040.4  429.49
  7043.1  430.77  7064.3  430.68  7069.3  428.48  7075.4  428.17  7196.9  427.82
#Mann= 3 ,-1 , 0
    2735     .05       0  3673.8     .03       0  3684.3     .05       0
Bank Sta=3673.8,3684.3
XS Rating Curve= 0 ,0
Exp/Cntr=0.3,0.1

Type RM Length L Ch R = 1 ,69871   ,834,834,834
BEGIN DESCRIPTION:
Mapping XS 1a377d76
END DESCRIPTION:
XS GIS Cut Line= 6
      2665266.18      6893750.52      2664127.29      6893979.69
      2663697.36      6894184.15       2662761.6      6895156.38
      2662752.29      6895354.69      2663012.66      6896396.18
#Sta/Elev= 30
  2725.7  433.93  3552.1   432.8  3582.7  426.21  3616.8  425.61  3930.3  426.91
  3966.1  430.41    4298  419.24  4667.2  414.13    4724  414.02  4738.2  417.89
    4745  415.16  4780.8  417.17  4853.3  413.24  4854.8  412.74  4863.8  413.24
  4872.8  417.52  4879.5  414.22    4887   417.1  4964.7     414  5007.3  419.77
  5014.3  416.63  5049.8  418.93    5085  415.26  5092.2  418.19  5099.2  415.04
  5134.7  417.32  5155.8   414.1  5339.7  420.44  5714.2  425.27  6986.5  427.84
#Mann= 3 ,-1 , 0
  2725.7     .05       0  4853.3     .03       0  4863.8     .05       0
Bank Sta=4853.3,4863.8
XS Rating Curve= 0 ,0
Exp/Cntr=0.3,0.1

Type RM Length L Ch R = 1 ,69037   ,784,784,784
BEGIN DESCRIPTION:
Little Cottonwood Creek 95.0
END DESCRIPTION:
XS GIS Cut Line= 3
      2663732.23      6893187.41      2662620.19      6894358.69
      2661696.63      6895374.92
#Sta/Elev= 30
  3384.9  428.43  3646.5  424.41  3816.4  423.77  3936.6  425.31  4113.3  423.28
  4219.3  421.31  4551.8  410.03  4559.1  411.57    4566  409.89  4573.2  411.64
  4580.1  409.83  4587.4  411.58  4594.3  409.92  4601.5  411.77  4700.3   412.5
  4735.8  411.82    4771  408.45  4799.4  411.88  4877.4     412  4940.9  409.57
  4976.1  411.39  5011.8  408.74  5013.2  406.39  5014.7  405.89  5023.8  406.39
  5032.7  410.58  5046.9  411.47  5408.4  420.11  5953.1  423.62  6373.2  422.91
#Mann= 3 ,-1 , 0
  3384.9     .05       0  5013.2     .04       0  5023.8     .05       0
Bank Sta=5013.2,5023.8
XS Rating Curve= 0 ,0
Exp/Cntr=0.3,0.1

Type RM Length L Ch R = 1 ,68253   ,1323,1323,1323
BEGIN DESCRIPTION:
Mapping XS 3704ac36
END DESCRIPTION:
XS GIS Cut Line= 3
      2663042.09      6893217.82      2662195.76      6893868.84
      2660760.09      6895078.97
#Sta/Elev= 30
  3923.5  424.28  4115.7  420.86  4224.8  421.33  4364.9  418.23  4536.8  418.28
  4549.7  419.67  4564.2  415.42  4579.9  412.97  4836.1  409.94  4906.8  411.32
  4927.9  409.92  4985.6  410.43  5006.5  407.41  5008.8  405.02  5010.2  404.52
  5019.7  405.02  5028.5  408.89  5049.4  407.49  5098.8   411.2  5141.7  409.95
  5304.8  411.25  5340.6  412.19  5390.1  417.02  5404.4  415.27  5432.9  414.89
  5716.5  415.06  6028.6  419.89  6560.4  422.09  6689.1  421.28  6868.9  423.29
#Mann= 5 ,-1 , 0
  3923.5     .05       0  4224.8    .075       0  4579.9     .05       0
  5008.8     .04       0  5019.7     .05       0
Bank Sta=5008.8,5019.7
XS Rating Curve= 0 ,0
Exp/Cntr=0.3,0.1

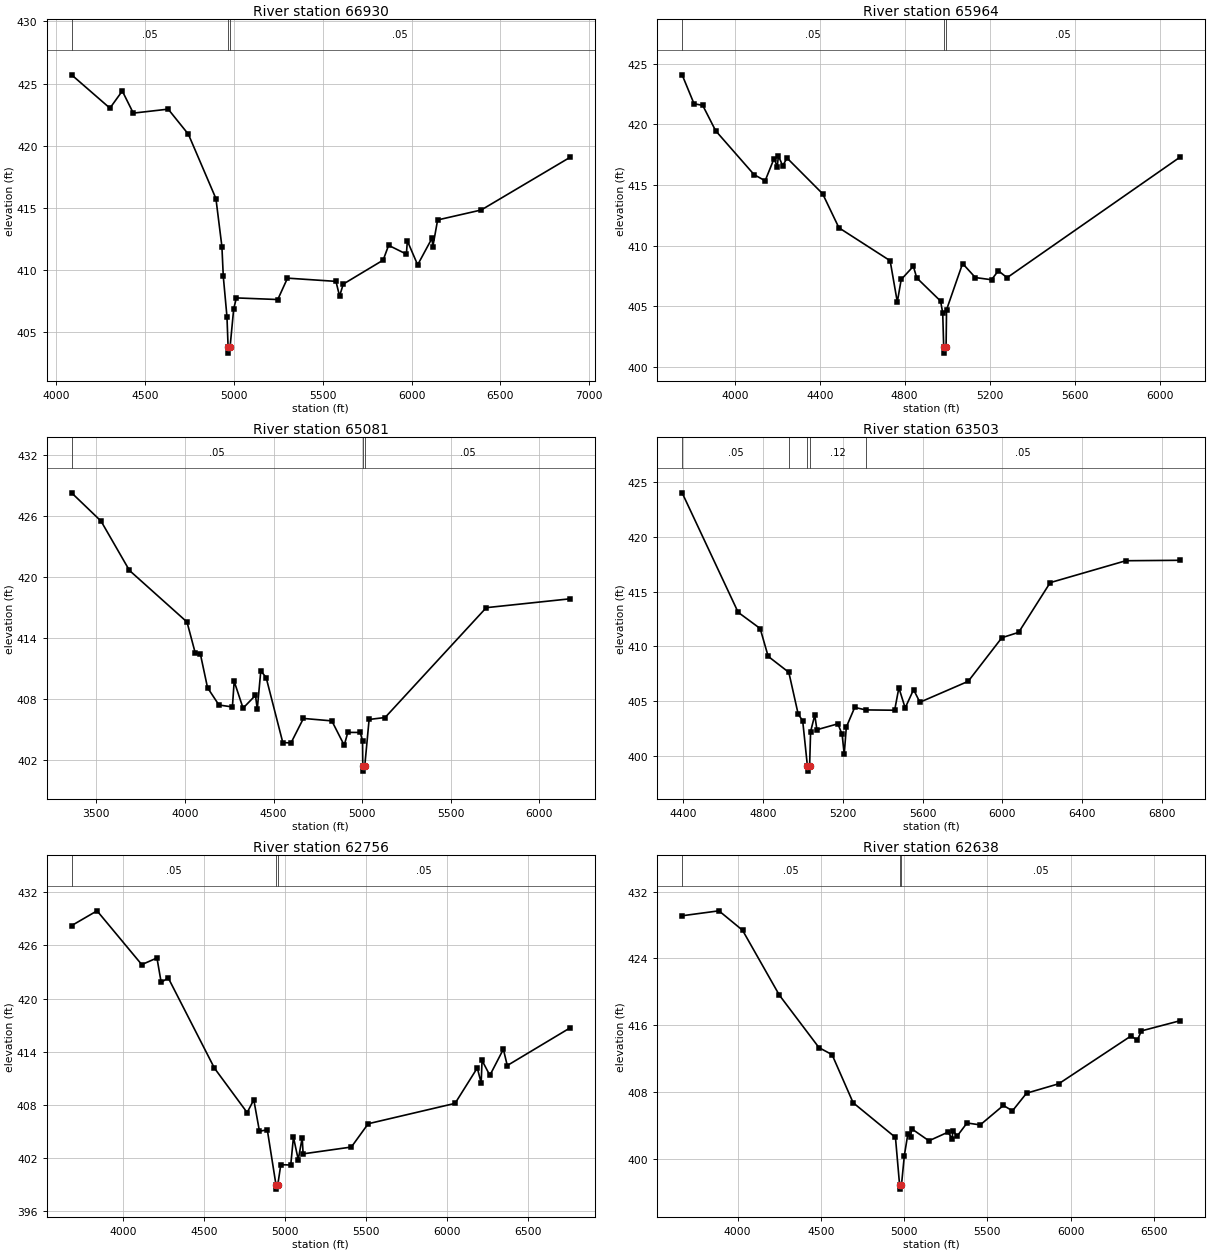
Type RM Length L Ch R = 1 ,66930   ,966,966,966
BEGIN DESCRIPTION:
Little Cottonwood Creek 93.0
END DESCRIPTION:
XS GIS Cut Line= 3
      2663052.13      6892821.83      2662167.18        6893054.
      2660317.14      6893446.41
#Sta/Elev= 30
  4085.1  425.71    4301  423.03  4370.6  424.41  4432.6  422.63    4629  422.95
  4742.8  420.93  4897.8  415.76  4931.5   411.9  4939.2  409.51  4959.9  406.27
  4966.4  403.83  4967.9  403.33  4977.5  403.83    4998   406.9  5013.1  407.77
    5246  407.64  5300.8  409.36  5573.7   409.1  5594.1  407.91  5614.6  408.88
  5839.5  410.81  5870.1     412  5970.4  411.29  5975.5  412.36  6033.7  410.43
  6114.2  412.56  6119.3   411.9  6146.1  414.04  6391.5  414.84  6891.2  419.07
#Mann= 3 ,-1 , 0
  4085.1     .05       0  4966.4     .04       0  4977.5     .05       0
Bank Sta=4966.4,4977.5
XS Rating Curve= 0 ,0
Exp/Cntr=0.3,0.1

Type RM Length L Ch R = 1 ,65964   ,883,883,883
BEGIN DESCRIPTION:
Little Cottonwood Creek 91.0
END DESCRIPTION:
XS GIS Cut Line= 3
      2662851.14        6892302.      2661625.58      6892536.01
      2660576.04      6892860.99
#Sta/Elev= 30
  3752.3   424.1  3808.4  421.71  3849.2  421.58  3910.2  419.48    4091  415.86
  4143.1  415.35  4185.1  417.18  4200.3  416.51  4205.5  417.41  4225.8  416.59
  4246.2  417.23  4413.8  414.28  4490.5  411.47  4731.6  408.75  4765.4  405.34
  4783.7   407.2  4840.9  408.29    4857  407.33    4969  405.42  4979.2  404.44
  4983.8  401.62  4985.3  401.12    4995  401.62  4997.2   404.7  5072.8  408.52
  5132.8  407.36  5208.9  407.18  5241.1  407.92  5282.2  407.35  6098.7  417.33
#Mann= 3 ,-1 , 0
  3752.3     .05       0  4983.8     .03       0    4995     .05       0
Bank Sta=4983.8,4995
XS Rating Curve= 0 ,0
Exp/Cntr=0.3,0.1

Type RM Length L Ch R = 1 ,65081   ,1578,1578,1578
BEGIN DESCRIPTION:
Little Cottonwood Creek 90.0
END DESCRIPTION:
XS GIS Cut Line= 3
      2662911.86      6891789.85       2661275.2      6891880.93
      2660104.61      6891946.05
#Sta/Elev= 30
  3360.8  428.31  3526.9  425.53  3687.2  420.68    4012  415.61  4057.7  412.61
  4087.8  412.43  4127.8  409.15  4192.2  407.45  4268.1  407.26  4278.1  409.78
  4328.2  407.14  4398.3   408.4  4408.3  407.03  4428.3  410.81  4458.4  410.15
  4552.4  403.76  4598.6  403.72  4668.7  406.13  4828.9  405.89    4899  403.49
  4919.1  404.76  4989.2  404.75  5002.1  403.95  5003.6  401.45  5005.2  400.95
  5014.8  401.45  5039.3  406.03  5129.4  406.22  5700.3  417.02  6172.4  417.89
#Mann= 3 ,-1 , 0
  3360.8     .05       0  5003.6     .03       0  5014.8     .05       0
Bank Sta=5003.6,5014.8
XS Rating Curve= 0 ,0
Exp/Cntr=0.3,0.1

Type RM Length L Ch R = 1 ,63503   ,747,747,747
BEGIN DESCRIPTION:
Little Cottonwood Creek 88.0
END DESCRIPTION:
XS GIS Cut Line= 3
      2662326.02        6890961.        2661726.        6891011.
      2659925.97      6891611.01
#Sta/Elev= 30
  4394.3  424.01  4675.3   413.1  4785.7  411.62  4825.8  409.08  4929.4  407.62
  4976.3  403.81    4999  403.19  5022.4   399.1  5023.9   398.6  5033.7   399.1
  5038.6  402.21  5059.6  403.72  5070.2  402.38  5175.6  402.92  5196.7  401.95
  5207.2  400.13  5217.8  402.62  5259.9  404.42  5314.4  404.19  5460.2  404.16
  5481.3  406.21  5512.9  404.37  5555.1  406.04  5586.7  404.89  5829.1   406.8
  5997.8  410.78  6082.1  411.27  6240.2  415.81  6619.7  417.81  6893.8  417.85
#Mann= 5 ,-1 , 0
  4394.3     .05       0  4929.4     .12       0  5022.4     .07       0
  5033.7     .12       0  5314.4     .05       0
Bank Sta=5022.4,5033.7
XS Rating Curve= 0 ,0
Exp/Cntr=0.3,0.1

Type RM Length L Ch R = 1 ,62756   ,118,118,118
BEGIN DESCRIPTION:
Mapping XS 7f2ada62
END DESCRIPTION:
XS GIS Cut Line= 6
       2662820.8      6890075.43      2661845.89       6890409.5
      2661488.25      6890552.73      2660925.75      6890752.38
       2660750.4      6890800.13      2659930.58      6891129.94
#Sta/Elev= 30
  3683.8  428.24    3841  429.91  4117.2  423.84  4211.1  424.59  4237.1  421.84
  4280.8  422.34  4566.3  412.15  4768.1  407.14  4809.2  408.58  4844.2  405.03
  4892.6   405.2  4946.1     399  4947.7   398.5  4957.5     399    4976  401.26
  5037.4  401.22  5054.1  404.37  5083.7  401.82  5108.3  404.32  5113.7  402.48
  5411.7  403.25  5515.8  405.88  6052.4  408.18  6189.4  412.17  6213.6   410.5
    6219  413.02  6267.3  411.34  6350.6  414.29  6374.8  412.45  6761.9  416.69
#Mann= 3 ,-1 , 0
  3683.8     .05       0  4946.1     .03       0  4957.5     .05       0
Bank Sta=4946.1,4957.5
XS Rating Curve= 0 ,0
Exp/Cntr=0.3,0.1

Type RM Length L Ch R = 1 ,62638   ,684,684,684
BEGIN DESCRIPTION:
Mapping XS c0b23fe6
END DESCRIPTION:
XS GIS Cut Line= 4
      2662760.04      6890005.98      2661653.61      6890374.78
      2661443.98       6890451.6      2659949.29      6891029.61
#Sta/Elev= 30
  3667.5   429.1  3888.4  429.69  4030.1  427.37  4251.5   419.6  4489.2  413.33
  4567.7  412.49  4694.2  406.74  4948.3  402.59  4973.1  396.91  4974.7  396.41
  4984.5  396.91  5001.6  400.43  5022.9  403.02  5039.8  402.68  5045.2  403.63
  5149.2  402.19  5263.6  403.22  5288.2  402.44  5293.6  403.41  5318.2  402.74
    5378  404.32  5457.2  404.09  5596.2  406.42  5650.7  405.77  5735.2  407.88
  5928.7  409.01  6362.9  414.73  6400.3  414.22  6424.8  415.33  6659.6  416.56
#Mann= 3 ,-1 , 0
  3667.5     .05       0  4973.1     .05       0  4984.5     .05       0
Bank Sta=4973.1,4984.5
XS Rating Curve= 0 ,0
Exp/Cntr=0.3,0.1