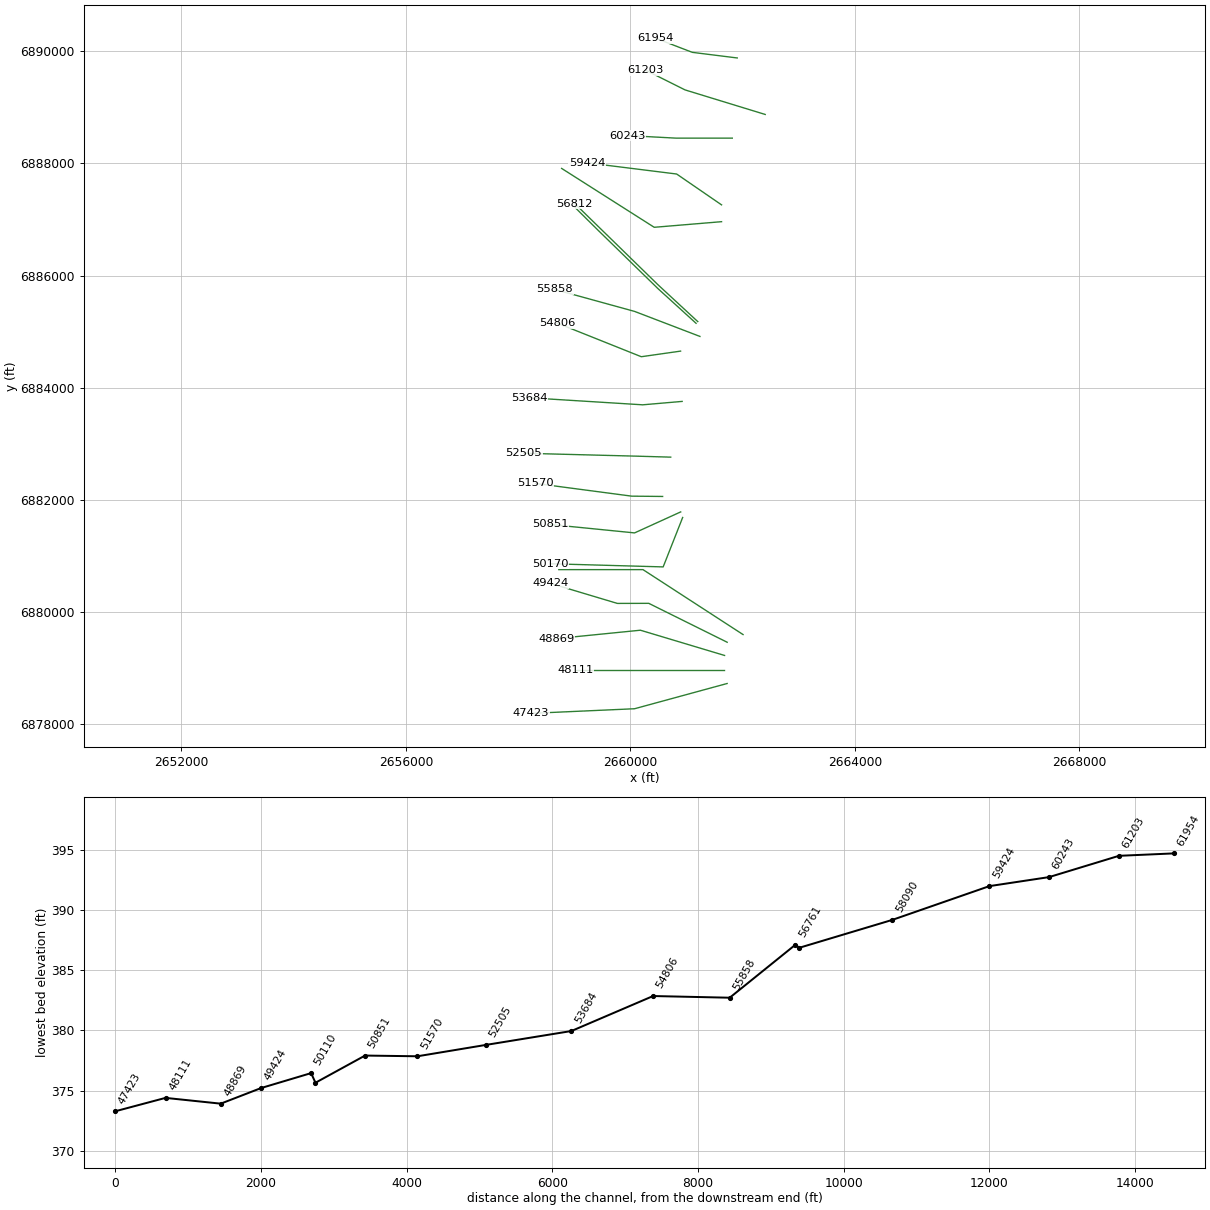
HEC-RAS study Little Cottonwood Creek.prj: Little Cottonwood Creek Base Level Engineering

--- Little Cottonwood Creek.g01 (geometry) --- (continued)

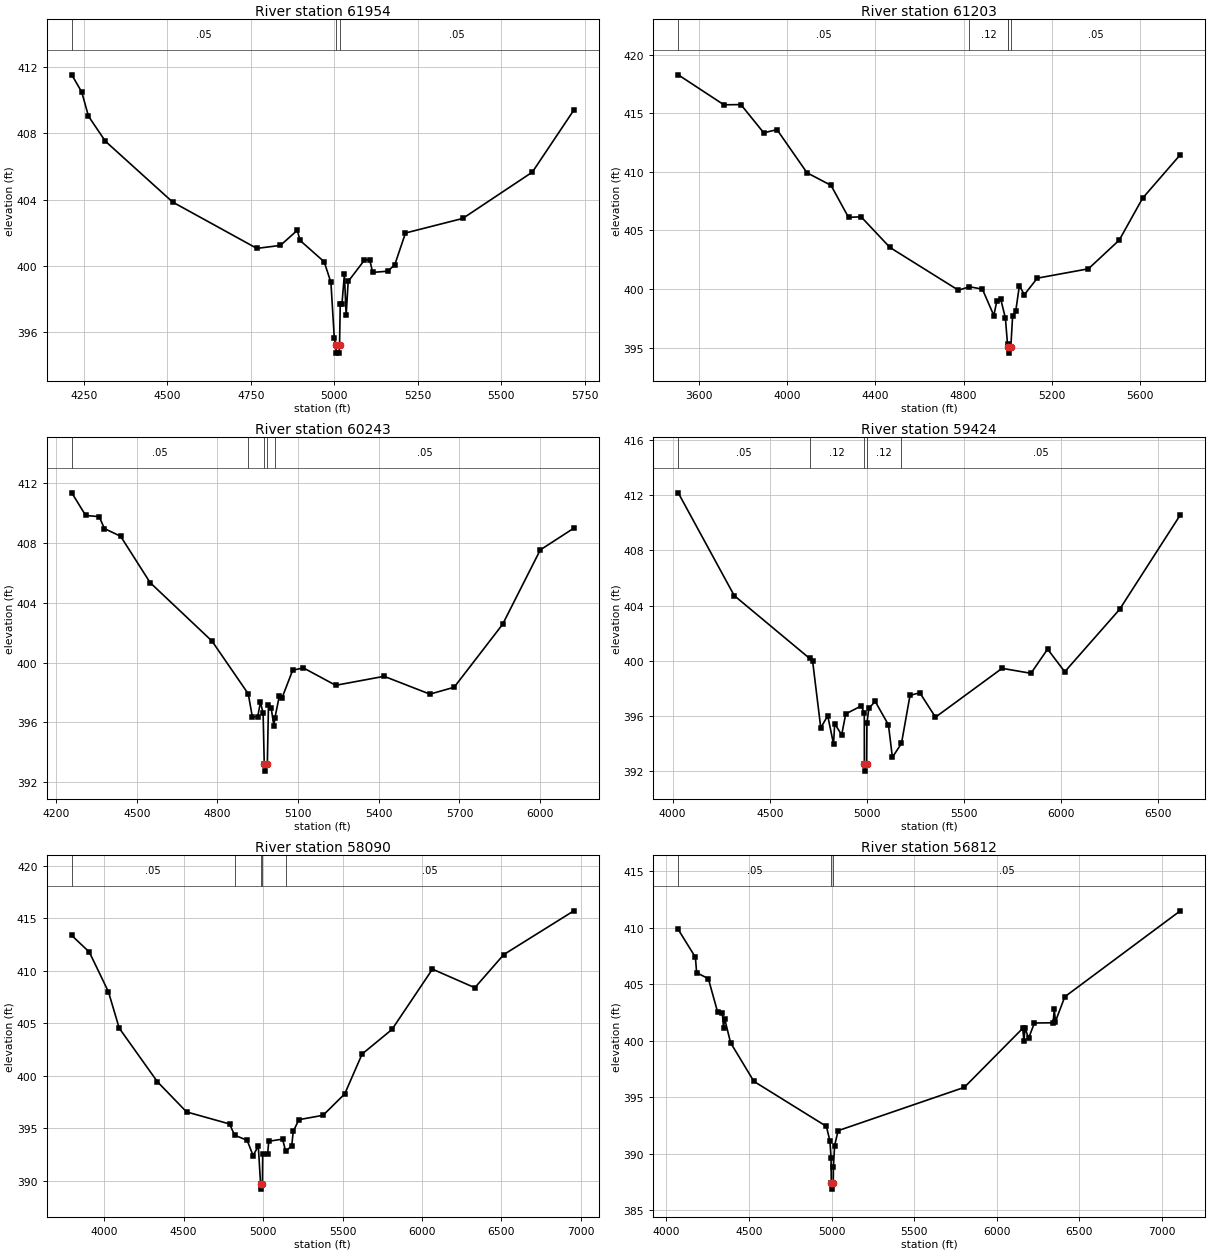
Type RM Length L Ch R = 1 ,61954   ,751,751,751
BEGIN DESCRIPTION:
Little Cottonwood Creek 85.0
END DESCRIPTION:
XS GIS Cut Line= 3
       2661905.6      6889880.82      2661105.65      6889980.82
      2660455.65      6890230.82
#Sta/Elev= 30
  4214.3  411.54  4244.1   410.5  4264.3  409.04  4314.7  407.53  4516.2  403.85
  4768.2  401.05  4838.7  401.23  4889.1  402.14  4897.6  401.53  4969.7  400.24
  4989.9  398.99    5000  395.61  5004.3  395.22  5005.9  394.72  5014.2  394.72
  5015.7  395.22  5017.8  397.71    5023  397.71  5030.2  399.48  5035.5  397.02
  5041.5  399.05  5090.2  400.34  5105.8  400.37  5114.8   399.6  5159.4  399.67
  5180.8  400.05    5213  401.98  5384.4  402.86  5592.7  405.66  5716.9  409.41
#Mann= 3 ,-1 , 0
  4214.3     .05       0  5004.3     .03       0  5015.7     .05       0
Bank Sta=5004.3,5015.7
XS Rating Curve= 0 ,0
Exp/Cntr=0.3,0.1

Type RM Length L Ch R = 1 ,61203   ,960,960,960
BEGIN DESCRIPTION:
Little Cottonwood Creek 83.0
END DESCRIPTION:
XS GIS Cut Line= 3
      2662404.12      6888873.17        2660976.        6889311.
      2660275.96      6889661.02
#Sta/Elev= 30
  3505.9  418.28  3713.1  415.72    3790  415.74  3893.5  413.33  3953.7   413.6
  4089.7  409.92  4198.7  408.84  4277.9  406.11  4334.9  406.16  4465.9  403.54
  4776.3  399.89  4826.3  400.19    4885  399.98  4936.9  397.73  4950.5  398.99
  4968.3  399.11  4989.2  397.52  4998.9  395.26  5002.3  395.02  5003.9  394.52
  5013.8  395.02    5022  397.71    5036  398.09  5052.7  400.28  5075.1  399.51
  5133.8  400.92  5365.8  401.72  5505.5  404.17  5611.8  407.76  5782.3  411.46
#Mann= 5 ,-1 , 0
  3505.9     .05       0  4826.3     .12       0  4998.9     .05       0
  5002.3     .03       0  5013.8     .05       0
Bank Sta=5002.3,5013.8
XS Rating Curve= 0 ,0
Exp/Cntr=0.3,0.1

Type RM Length L Ch R = 1 ,60243   ,819,819,819
BEGIN DESCRIPTION:
Little Cottonwood Creek 82.0
END DESCRIPTION:
XS GIS Cut Line= 3
      2661817.68      6888450.93      2660817.67      6888450.93
      2659951.39      6888496.74
#Sta/Elev= 30
    4258  411.33  4309.7  409.82  4359.7  409.74  4379.7  408.94  4439.7  408.43
  4549.7  405.33  4779.7  401.43  4914.4  397.91  4929.7  396.37  4949.7  396.39
  4959.7  397.35  4969.7  396.63  4973.9  393.25  4975.5  392.75  4985.4  393.25
  4989.7  397.19  4999.7  396.96  5009.7  395.79  5013.4  396.28  5029.7  397.74
  5039.7  397.62  5079.7  399.49  5119.7  399.64  5239.7  398.48  5419.9  399.08
  5590.1  397.89  5680.3  398.35  5860.5  402.55  6000.7  407.52  6125.5  408.97
#Mann= 5 ,-1 , 0
    4258     .05       0  4914.4     .12       0  4973.9     .07       0
  4985.4     .12       0  5013.4     .05       0
Bank Sta=4973.9,4985.4
XS Rating Curve= 0 ,0
Exp/Cntr=0.3,0.1

Type RM Length L Ch R = 1 ,59424   ,1334,1334,1334
BEGIN DESCRIPTION:
Little Cottonwood Creek 80.0
END DESCRIPTION:
XS GIS Cut Line= 3
      2661625.98      6887261.01        2660826.        6887811.
      2659225.96      6888011.01
#Sta/Elev= 30
  4029.2  412.17  4317.4  404.72  4705.1  400.17  4720.6  399.98  4762.5  395.14
  4798.4  396.01  4828.2  393.97  4834.2  395.43  4870.1  394.63  4891.1  396.15
  4971.6  396.73  4986.5  396.18  4986.8   392.5  4988.4     392  4998.3   392.5
    5000  395.47  5010.1  396.56  5042.8  397.05  5110.9  395.35    5131     393
  5177.8  394.01  5221.7  397.49  5272.1  397.68  5352.7  395.91  5695.4  399.45
    5844  399.09  5929.7  400.84  6017.9   399.2    6300  403.72  6612.5  410.57
#Mann= 5 ,-1 , 0
  4029.2     .05       0  4705.1     .12       0  4986.8     .07       0
  4998.3     .12       0  5177.8     .05       0
Bank Sta=4986.8,4998.3
XS Rating Curve= 0 ,0
Exp/Cntr=0.3,0.1

Type RM Length L Ch R = 1 ,58090   ,1278,1278,1278
BEGIN DESCRIPTION:
Little Cottonwood Creek 77.0
END DESCRIPTION:
XS GIS Cut Line= 3
      2661625.96        6886961.        2660426.        6886861.
      2658775.98      6887911.01
#Sta/Elev= 30
    3796  413.37  3906.3  411.79  4026.8     408  4094.5  404.54  4335.3  399.42
  4518.5  396.55  4789.4   395.4  4820.3  394.34  4899.8  393.84  4937.4  392.38
    4970  393.31  4984.2  389.69  4985.8  389.19    4996  389.69  4997.6  392.51
  5028.9  392.57  5035.7  393.75  5122.9  393.96  5141.8   392.8  5180.5  393.31
  5189.8  394.69  5225.3  395.81  5377.7  396.23    5514  398.27  5623.3  402.07
  5811.2  404.41    6066  410.16  6332.7  408.39  6514.8  411.55  6955.9  415.72
#Mann= 5 ,-1 , 0
    3796     .05       0  4820.3     .12       0  4984.2     .07       0
    4996     .12       0  5141.8     .05       0
Bank Sta=4984.2,4996
XS Rating Curve= 0 ,0
Exp/Cntr=0.3,0.1

Type RM Length L Ch R = 1 ,56812   ,51,51,51
BEGIN DESCRIPTION:
Mapping XS 7ac676cf
END DESCRIPTION:
XS GIS Cut Line= 3
      2661201.85      6885179.59      2660494.38      6885834.99
      2659010.51      6887284.14
#Sta/Elev= 30
  4071.9  409.83  4175.9  407.37  4183.2  406.01  4254.1  405.48  4310.8   402.5
  4338.9  402.44  4345.9  401.14  4352.8  401.94  4388.5  399.82  4529.7   396.4
  4968.5  392.42    4990  391.12  4996.8  389.63  4998.2  387.37  4999.9  386.87
  5010.1  387.37    5011  388.82  5018.4  390.72  5039.4  392.04  5803.1  395.87
  6156.7  401.09  6163.8  399.98  6170.8  401.11  6192.1  400.21  6227.4  401.56
  6340.6  401.58  6347.7  402.78  6354.7  401.69  6411.3  403.88  7110.4  411.48
#Mann= 3 ,-1 , 0
  4071.9     .05       0  4998.2     .04       0  5010.1     .05       0
Bank Sta=4998.2,5010.1
XS Rating Curve= 0 ,0
Exp/Cntr=0.3,0.1

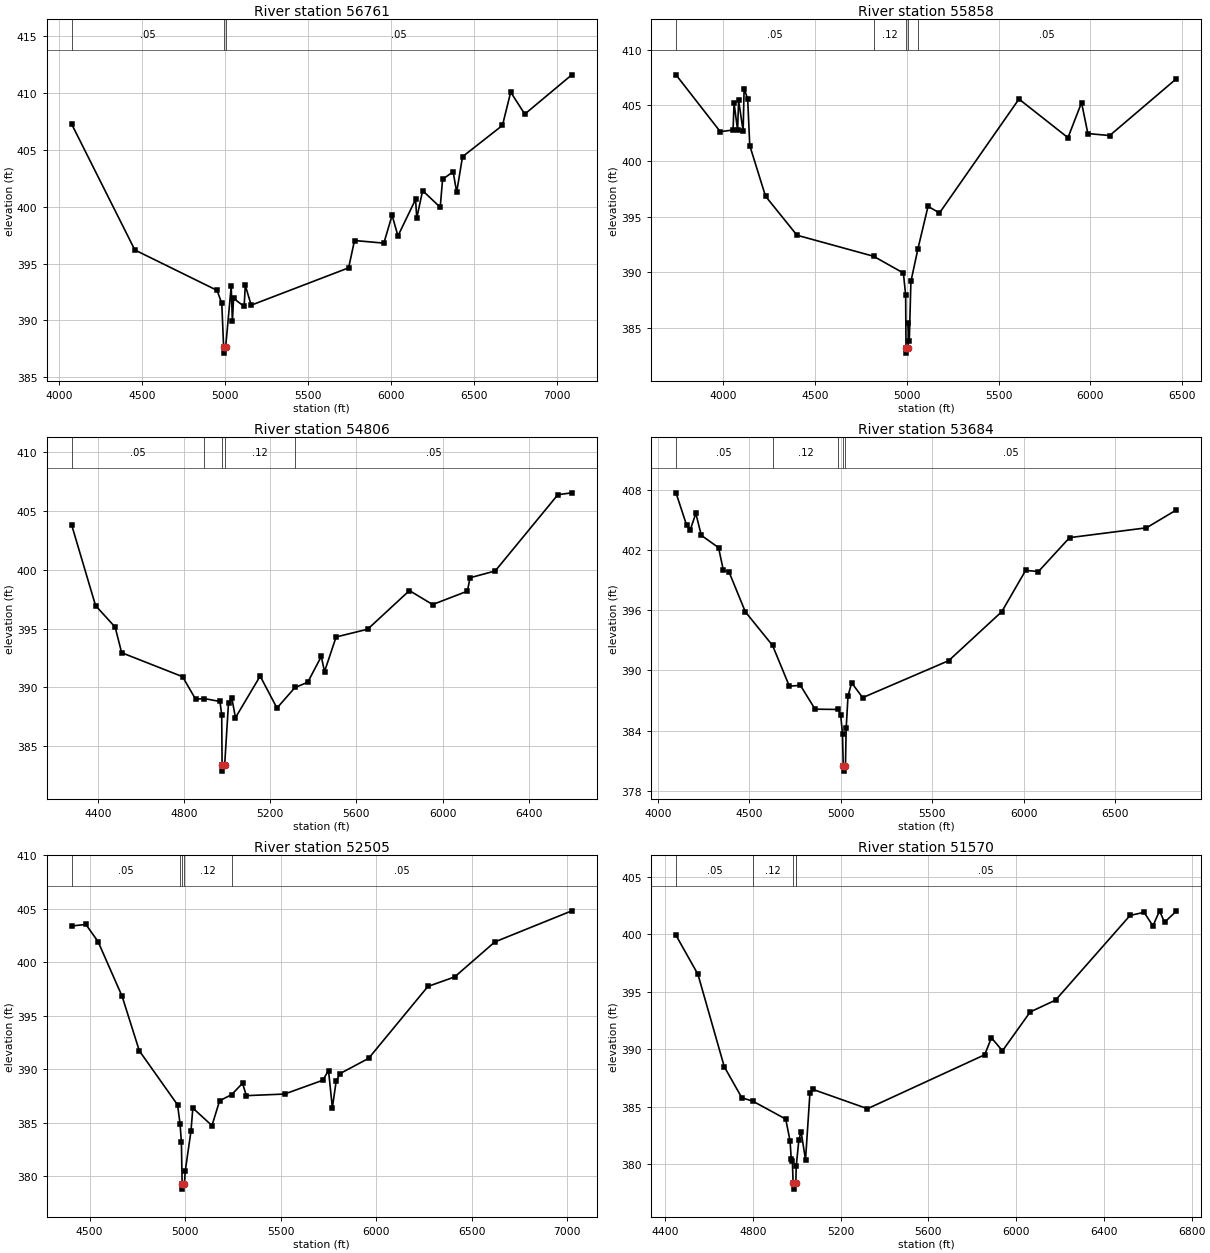
Type RM Length L Ch R = 1 ,56761   ,903,903,903
BEGIN DESCRIPTION:
Mapping XS 6f03c32c
END DESCRIPTION:
XS GIS Cut Line= 4
      2661171.49      6885149.19      2660490.04      6885769.88
      2659426.67      6886807.21      2658996.98      6887232.56
#Sta/Elev= 30
  4075.3  407.24  4455.7  396.19    4951  392.64  4979.3  391.49  4990.5  387.63
  4992.1  387.13  5002.4  387.63    5036  392.99  5043.2  389.92  5050.2  391.94
  5113.9  391.23  5120.9  393.08  5156.4  391.34  5743.1  394.62  5778.6  397.02
  5955.3  396.79  6004.9  399.24  6040.2  397.42  6146.4  400.63  6153.4  398.98
  6188.8   401.4  6294.8  399.94    6309  402.39  6372.5  403.06  6393.8  401.26
  6429.1  404.38  6669.6  407.13  6719.1  410.05    6804  408.12  7087.2  411.57
#Mann= 3 ,-1 , 0
  4075.3     .05       0  4990.5     .03       0  5002.4     .05       0
Bank Sta=4990.5,5002.4
XS Rating Curve= 0 ,0
Exp/Cntr=0.3,0.1

Type RM Length L Ch R = 1 ,55858   ,1052,1052,1052
BEGIN DESCRIPTION:
Little Cottonwood Creek 73.0
END DESCRIPTION:
XS GIS Cut Line= 3
      2661240.93      6884914.83        2660076.        6885361.
      2658654.07      6885752.53
#Sta/Elev= 30
  3744.3  407.74  3985.2  402.63  4054.9  402.78  4060.3   405.2  4079.6  402.76
    4085  405.45  4109.7  402.68    4115   406.5  4134.4  405.58  4145.8  401.38
  4231.5  396.83  4402.8  393.32  4819.4  391.43  4982.1  389.92  4994.3  387.93
  4996.2  383.22  4997.8  382.72  5008.1  383.22  5008.9   385.4  5014.1  383.79
  5022.9  389.16  5061.3  392.11  5116.2  395.92  5178.5  395.32  5611.1  405.56
  5877.8  402.09  5951.7  405.24  5986.1  402.46  6104.9  402.28  6466.6  407.37
#Mann= 5 ,-1 , 0
  3744.3     .05       0  4819.4     .12       0  4996.2     .07       0
  5008.1     .12       0  5061.3     .05       0
Bank Sta=4996.2,5008.1
XS Rating Curve= 0 ,0
Exp/Cntr=0.3,0.1

Type RM Length L Ch R = 1 ,54806   ,1122,1122,1122
BEGIN DESCRIPTION:
Little Cottonwood Creek 71.0
END DESCRIPTION:
XS GIS Cut Line= 3
      2660895.77      6884652.97      2660195.79      6884552.97
      2658695.83      6885152.95
#Sta/Elev= 30
  4277.8  403.81  4388.7  396.95  4479.6  395.12  4509.9  392.94  4792.7   390.9
  4853.4  388.98  4892.4  389.04  4966.5  388.79  4974.6  387.64  4976.3  383.36
    4978  382.86  4988.2  383.36  5006.2  388.68  5021.2   389.1  5038.5  387.41
  5153.1  390.95  5231.2  388.23  5314.9  389.98  5373.9  390.42    5437  392.62
    5452  391.33  5505.8  394.28  5652.4  394.94  5846.3  398.23    5954  397.04
  6115.5  398.18  6127.8  399.32  6244.8   399.9  6535.6  406.39  6600.4  406.55
#Mann= 5 ,-1 , 0
  4277.8     .05       0  4892.4     .12       0  4976.3     .07       0
  4988.2     .12       0  5314.9     .05       0
Bank Sta=4976.3,4988.2
XS Rating Curve= 0 ,0
Exp/Cntr=0.3,0.1

Type RM Length L Ch R = 1 ,53684   ,1179,1179,1179
BEGIN DESCRIPTION:
Mapping XS fe04d77d
END DESCRIPTION:
XS GIS Cut Line= 3
      2660924.03      6883755.99      2660220.94      6883695.23
      2658194.06      6883821.09
#Sta/Elev= 30
  4098.3  407.71  4156.5  404.47  4176.6  404.03  4206.7  405.66  4236.8  403.47
  4331.3  402.24  4357.3  399.98  4387.4  399.86  4477.7  395.84  4626.5  392.49
  4718.6  388.42  4778.9  388.51  4859.1  386.13  4986.7   386.1  4999.3  385.57
  5009.3  383.65  5013.3  380.45    5015  379.95  5025.4  380.45  5029.4  384.23
  5039.4  387.44  5059.4  388.76  5119.6  387.28  5590.5  390.97    5881  395.86
  6011.3  399.97  6081.4  399.86  6251.7  403.24  6672.5  404.22  6834.8  405.99
#Mann= 5 ,-1 , 0
  4098.3     .05       0  4626.5     .12       0  4986.7     .05       0
  5013.3     .05       0  5025.4     .05       0
Bank Sta=5013.3,5025.4
XS Rating Curve= 0 ,0
Exp/Cntr=0.3,0.1

Type RM Length L Ch R = 1 ,52505   ,935,935,935
BEGIN DESCRIPTION:
Mapping XS a7ca6850
END DESCRIPTION:
XS GIS Cut Line= 3
      2660720.08      6882762.07      2660116.77      6882779.43
      2658102.91      6882831.51
#Sta/Elev= 30
    4406  403.39  4480.1  403.54  4543.9  401.94  4670.2  396.81  4760.2  391.72
  4960.3  386.67  4973.4  384.88  4980.3  383.22  4984.3  379.29  4985.9  378.79
  4996.4  379.29  5000.3  380.46  5030.3  384.18  5040.3  386.37  5140.4  384.73
  5180.4  387.05  5243.6  387.63  5300.4  388.69  5320.4  387.53  5520.5  387.68
  5720.6  388.97  5750.6  389.88  5770.6   386.4  5790.6  388.88  5810.6  389.59
  5960.7  391.02  6270.8  397.74  6410.8  398.63  6620.9   401.9  7024.1  404.81
#Mann= 5 ,-1 , 0
    4406     .05       0  4973.4     .12       0  4984.3     .07       0
  4996.4     .12       0  5243.6     .05       0
Bank Sta=4984.3,4996.4
XS Rating Curve= 0 ,0
Exp/Cntr=0.3,0.1

Type RM Length L Ch R = 1 ,51570   ,719,719,719
BEGIN DESCRIPTION:
Little Cottonwood Creek 64.0
END DESCRIPTION:
XS GIS Cut Line= 3
      2660575.98        6882061.      2660025.51      6882066.23
      2658311.18      6882293.32
#Sta/Elev= 30
  4449.5  399.91  4549.5  396.52  4669.5  388.49  4749.5  385.79  4799.4   385.5
  4949.5  383.94  4969.5  382.04  4974.9  380.43  4979.9  380.29  4983.4  378.35
  4985.1  377.85  4995.6  378.35  4997.5  379.84  5009.6  382.14  5019.7  382.85
  5039.9   380.4    5060  386.19  5074.8  386.51  5322.3  384.84  5856.9  389.53
  5887.2  391.01  5937.6  389.87    6064  393.25  6179.7  394.28  6519.4  401.64
  6583.2  401.91  6623.6  400.73  6653.8  402.04  6676.3  401.04  6729.3     402
#Mann= 5 ,-1 , 0
  4449.5     .05       0  4799.4     .12       0  4983.4     .03       0
  4995.6     .12       0  4997.5     .05       0
Bank Sta=4983.4,4995.6
XS Rating Curve= 0 ,0
Exp/Cntr=0.3,0.1

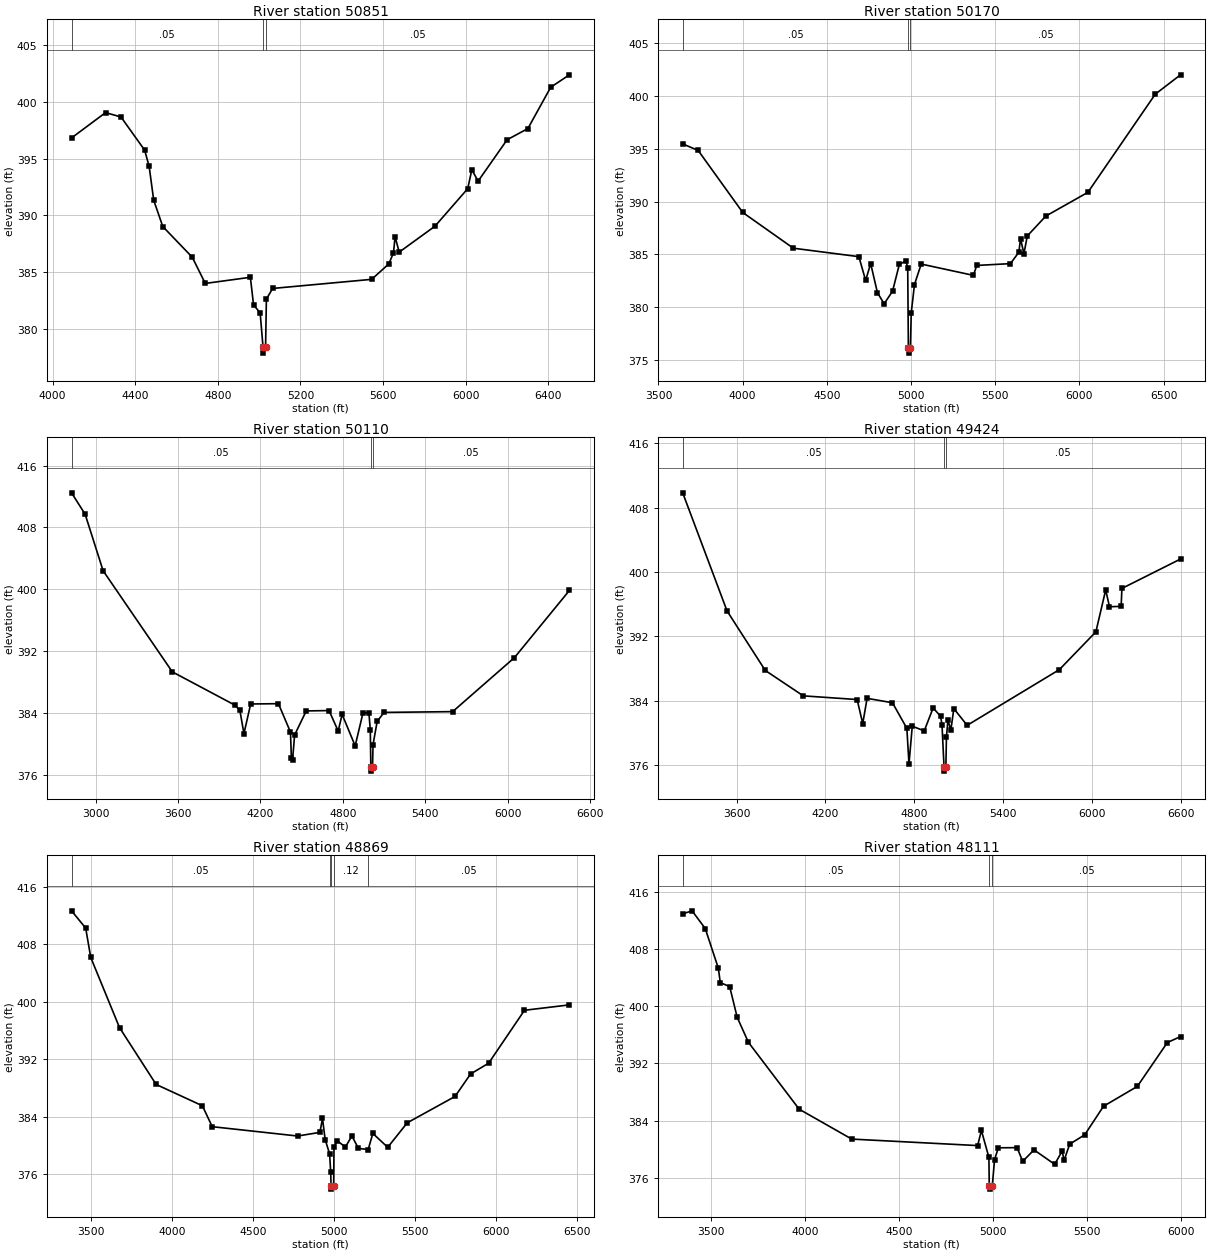
Type RM Length L Ch R = 1 ,50851   ,681,681,681
BEGIN DESCRIPTION:
Little Cottonwood Creek 63.0
END DESCRIPTION:
XS GIS Cut Line= 3
      2660897.98      6881785.49        2660076.        6881411.
      2658576.04        6881561.
#Sta/Elev= 30
  4091.9  396.81  4256.5  399.03  4331.1  398.65  4445.7  395.74  4467.7   394.3
  4489.7  391.34  4533.6  389.03  4676.5  386.33  4739.4  384.03  4957.8  384.57
  4973.2  382.15  5005.2  381.44  5019.2  378.41  5020.9  377.91  5031.4  378.41
  5035.4  382.65  5065.5  383.59  5545.4  384.39  5628.3  385.75  5650.9  386.72
  5658.5  388.13  5678.6  386.78  5851.9  389.06  6010.2  392.35  6030.3  394.02
  6060.5  393.01  6201.1  396.65  6301.6  397.63  6412.2  401.26  6502.6  402.35
#Mann= 3 ,-1 , 0
  4091.9     .05       0  5019.2     .05       0  5031.4     .05       0
Bank Sta=5019.2,5031.4
XS Rating Curve= 0 ,0
Exp/Cntr=0.3,0.1

Type RM Length L Ch R = 1 ,50170   ,60,60,60
BEGIN DESCRIPTION:
Little Cottonwood Creek 62.0
END DESCRIPTION:
XS GIS Cut Line= 3
      2660932.74      6881685.66      2660585.52       6880804.6
      2658576.02        6880861.
#Sta/Elev= 30
  3643.8  395.45  3735.3  394.84  4000.6  388.96  4301.1  385.58  4690.4  384.78
  4730.4  382.53  4760.4  384.13  4800.4  381.38  4840.4  380.32  4890.4  381.51
  4930.5  384.04  4970.5  384.39  4980.5  383.69  4984.4  376.15  4986.1  375.65
  4996.6  376.15  5001.3  379.43  5020.5  382.13  5060.5  384.08  5370.6  383.01
  5390.6  383.95  5590.7  384.12  5640.7   385.2  5650.7  386.48  5670.8  385.06
  5690.8  386.74  5800.8  388.62  6050.9  390.87  6451.1  400.16  6601.1  401.99
#Mann= 3 ,-1 , 0
  3643.8     .05       0  4984.4     .03       0  4996.6     .05       0
Bank Sta=4984.4,4996.6
XS Rating Curve= 0 ,0
Exp/Cntr=0.3,0.1

Type RM Length L Ch R = 1 ,50110   ,686,686,686
BEGIN DESCRIPTION:
Little Cottonwood Creek 61.0
END DESCRIPTION:
XS GIS Cut Line= 3
      2662009.15      6879597.99      2660225.76       6880756.1
      2658725.79       6880756.1
#Sta/Elev= 30
  2824.3  412.47  2923.4  409.69    3054  402.39  3558.2   389.3  4014.3  384.99
  4050.5  384.31    4080   381.3    4129  385.14  4331.3  385.18    4419   381.5
  4425.8  378.09  4434.1  377.88  4449.2  381.13  4533.7  384.24  4700.1  384.29
  4766.3  381.64  4795.4  383.79  4890.2  379.72  4947.5  384.01  4990.5  383.96
  5000.5  381.78  5004.4  376.95  5006.1  376.45  5016.6  376.95  5020.5  379.89
  5050.5  382.88  5100.5  384.05  5600.5  384.15  6050.5  391.14  6450.7  399.83
#Mann= 3 ,-1 , 0
  2824.3     .05       0  5004.4     .03       0  5016.6     .05       0
Bank Sta=5004.4,5016.6
XS Rating Curve= 0 ,0
Exp/Cntr=0.3,0.1

Type RM Length L Ch R = 1 ,49424   ,555,555,555
BEGIN DESCRIPTION:
Little Cottonwood Creek 60.0
END DESCRIPTION:
XS GIS Cut Line= 4
      2661725.99        6879461.      2660328.73      6880154.87
      2659769.55      6880153.56      2658575.97      6880511.01
#Sta/Elev= 30
  3234.8  409.85  3534.5  395.15    3793  387.74  4049.8  384.58  4413.9  384.12
  4451.8  381.13  4481.2  384.27  4652.8  383.72  4750.1  380.53  4764.4   376.1
  4786.7   380.8  4867.6  380.22  4927.6  383.08  4977.6  382.05  4987.6     381
  5001.4  375.71  5003.1  375.21  5013.8  375.71  5017.6  379.43  5027.6  381.53
  5047.6  380.34  5067.6  382.99  5157.6  380.91  5780.7  387.84  6027.9  392.55
  6094.1  397.77  6119.8  395.67  6198.6  395.72  6203.8  397.95    6600  401.61
#Mann= 3 ,-1 , 0
  3234.8     .05       0  5001.4     .03       0  5013.8     .05       0
Bank Sta=5001.4,5013.8
XS Rating Curve= 0 ,0
Exp/Cntr=0.3,0.1

Type RM Length L Ch R = 1 ,48869   ,758,758,758
BEGIN DESCRIPTION:
Little Cottonwood Creek 59.0
END DESCRIPTION:
XS GIS Cut Line= 3
      2661679.52      6879225.57      2660179.47      6879675.58
      2658680.24      6879525.66
#Sta/Elev= 30
  3379.8  412.64    3467  410.24  3498.3  406.15  3675.8  396.39  3901.8  388.48
  4187.4  385.51  4248.1   382.6  4775.3   381.3  4912.8  381.81  4928.6  383.74
  4945.1  380.81  4972.5  378.83  4979.5  376.25  4981.4  374.41  4983.4  373.91
  4997.7  374.41  4999.6  379.74  5019.7  380.63    5070  379.77  5110.2  381.31
  5150.4  379.58  5210.6  379.42  5239.5  381.66  5331.3  379.73  5451.9  383.14
    5747  386.81  5842.5  389.93  5954.4  391.44  6175.5   398.8  6452.6  399.55
#Mann= 5 ,-1 , 0
  3379.8     .05       0  4972.5     .12       0  4981.4     .07       0
  4997.7     .12       0  5210.6     .05       0
Bank Sta=4981.4,4997.7
XS Rating Curve= 0 ,0
Exp/Cntr=0.3,0.1

Type RM Length L Ch R = 1 ,48111   ,688,688,688
BEGIN DESCRIPTION:
Little Cottonwood Creek 57.0
END DESCRIPTION:
XS GIS Cut Line= 3
        2661676.        6878961.        2660026.        6878961.
        2659026.        6878961.
#Sta/Elev= 30
    3350  412.96    3400  413.38    3470   410.9    3540  405.31    3550  403.32
    3600  402.77    3640  398.46    3700  394.95    3970  385.59    4250   381.4
    4920  380.49    4940  382.61    4980  378.83  4981.8  374.89  4983.8  374.39
  4998.1  374.89    5010   378.5    5030  380.18    5130   380.2    5160  378.28
    5220  379.89    5330  377.87    5370  379.72    5380  378.41    5410  380.69
    5490     382    5590     386    5770  388.78    5930  394.93    6000  395.76
#Mann= 3 ,-1 , 0
    3350     .05       0  4981.8     .03       0  4998.1     .05       0
Bank Sta=4981.8,4998.1
XS Rating Curve= 0 ,0
Exp/Cntr=0.3,0.1

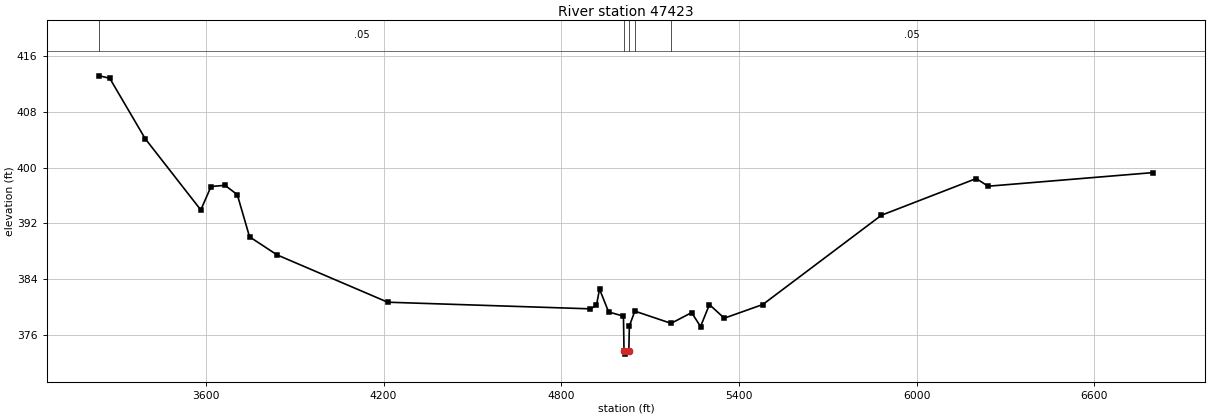
Type RM Length L Ch R = 1 ,47423   ,743,743,743
BEGIN DESCRIPTION:
Little Cottonwood Creek 56.0
END DESCRIPTION:
XS GIS Cut Line= 3
      2661725.29      6878725.14      2660075.31      6878275.15
       2658230.7      6878192.55
#Sta/Elev= 30
  3240.4  413.16  3275.5  412.81  3395.1  404.16    3583  393.94  3617.6   397.3
  3664.6  397.47  3706.1  396.14  3747.6  390.09  3840.5   387.5    4214  380.72
  4898.1  379.77  4918.8  380.26  4929.2   382.6    4960  379.32    5010  378.72
  5011.9  373.78  5013.9  373.28  5028.2  373.78    5030  377.33  5048.5  379.44
  5170.9  377.69  5240.2  379.23  5270.3  377.23  5300.3  380.38  5350.4  378.43
  5480.5  380.39  5880.9  393.18  6201.2  398.44  6241.2  397.34  6797.1  399.29
#Mann= 5 ,-1 , 0
  3240.4     .05       0  5011.9     .03       0  5028.2     .05       0
  5048.5     .12       0  5170.9     .05       0
Bank Sta=5011.9,5028.2
XS Rating Curve= 0 ,0
Exp/Cntr=0.3,0.1