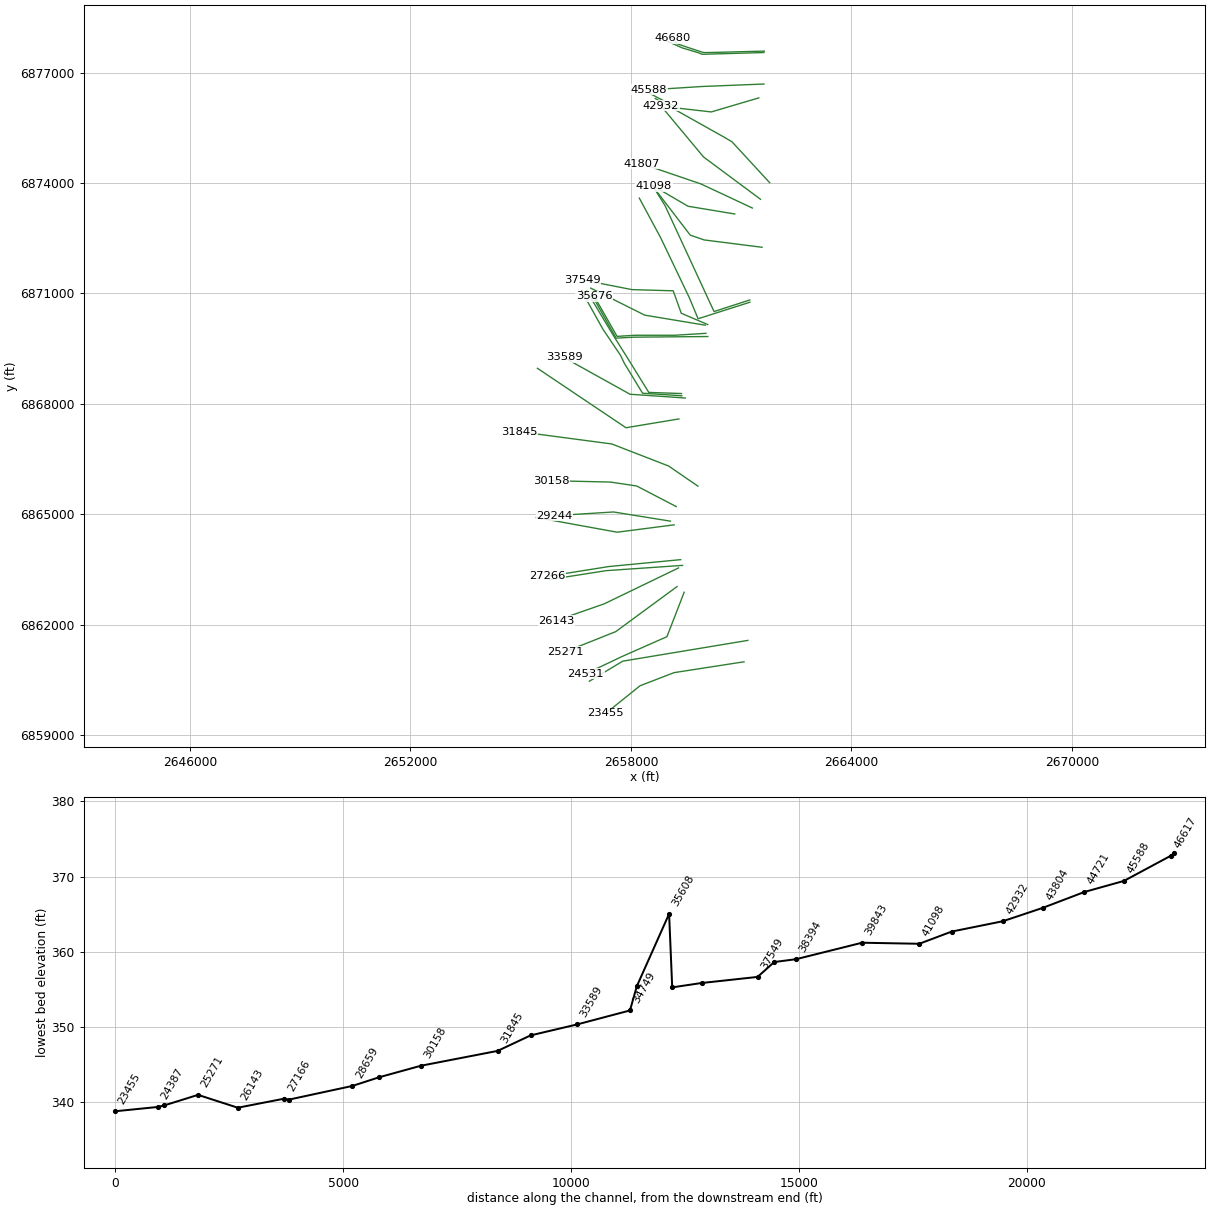
HEC-RAS study Little Cottonwood Creek.prj: Little Cottonwood Creek Base Level Engineering

--- Little Cottonwood Creek.g01 (geometry) --- (continued)

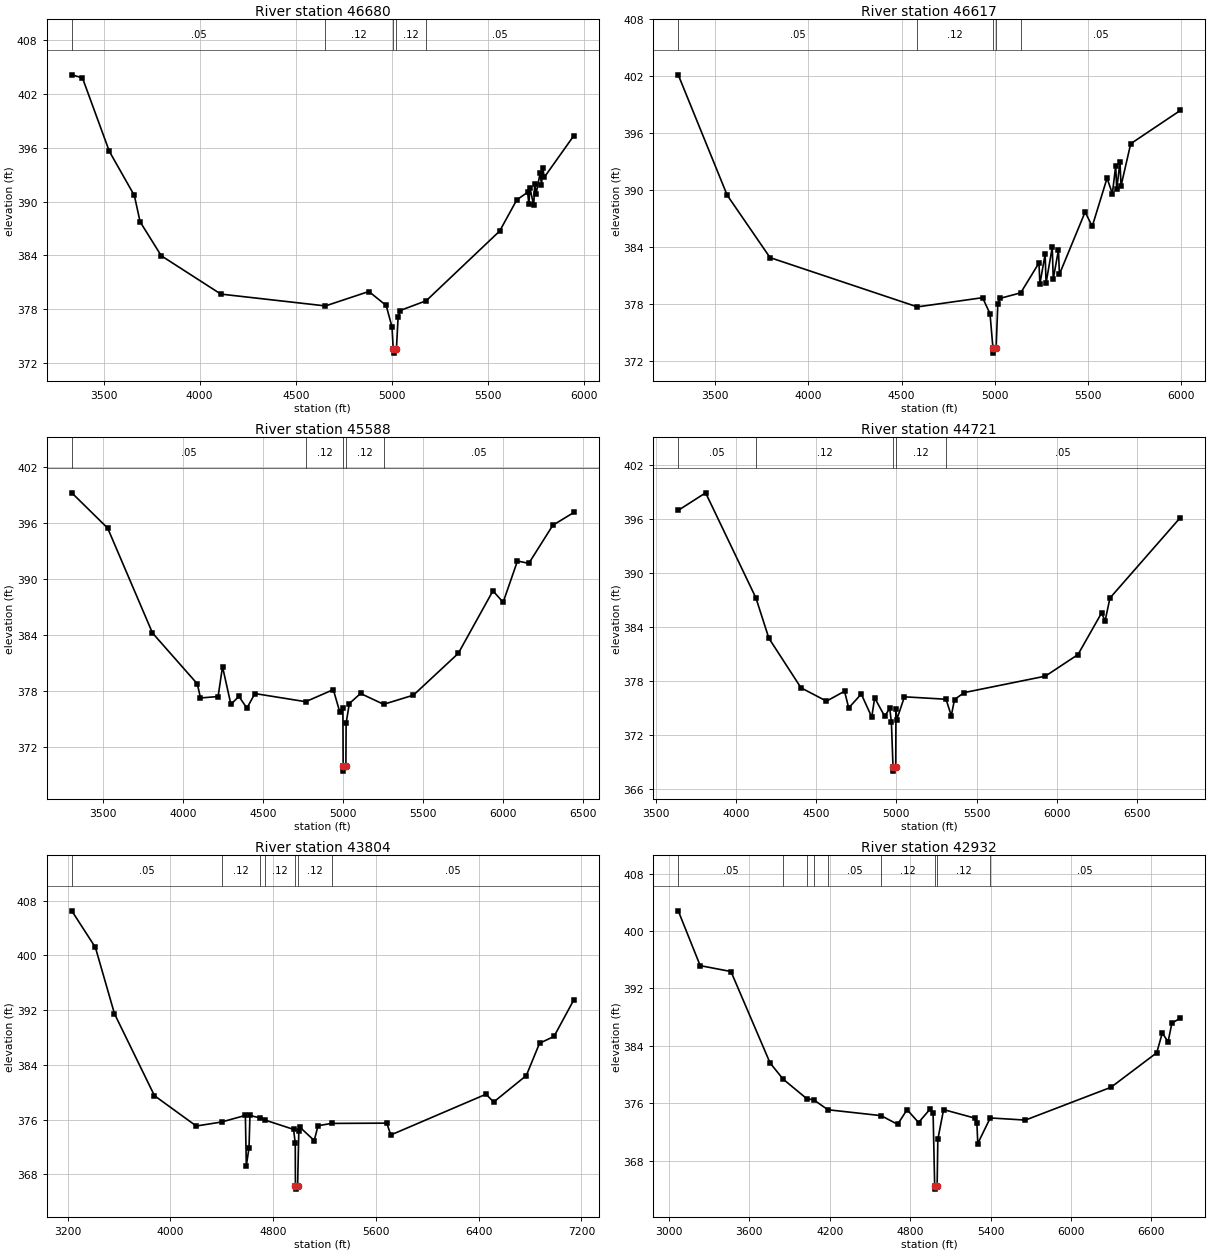
Type RM Length L Ch R = 1 ,46680   ,63,63,63
BEGIN DESCRIPTION:
Mapping XS eb0fea7c
END DESCRIPTION:
XS GIS Cut Line= 6
      2661631.53      6877588.46      2660134.13      6877549.39
      2659973.54      6877549.39      2659535.17      6877692.62
      2659266.08      6877783.77      2659122.82       6877935.7
#Sta/Elev= 30
  3334.4  404.15  3389.9  403.81    3530   395.6    3660  390.68    3690  387.74
  3800.1  383.95  4110.2  379.67  4654.4  378.35  4880.4  379.96  4970.4   378.4
  5000.8     376    5007  373.58    5009  373.08  5023.9  373.58  5032.4  377.06
  5042.1  377.83  5178.9  378.93  5561.1  386.71  5650.1  390.19  5706.6  391.04
  5712.9  389.68  5718.2  391.54  5738.2  389.58  5743.4  391.96  5750.3  390.84
  5771.7  393.19  5778.6  391.89  5785.9  393.74  5792.8   392.7    5947  397.36
#Mann= 5 ,-1 , 0
  3334.4     .05       0  4654.4     .12       0    5007     .07       0
  5023.9     .12       0  5178.9     .05       0
Bank Sta=5007,5023.9
XS Rating Curve= 0 ,0
Exp/Cntr=0.3,0.1

Type RM Length L Ch R = 1 ,46617   ,1029,1029,1029
BEGIN DESCRIPTION:
Mapping XS eb1d7fea
END DESCRIPTION:
XS GIS Cut Line= 5
      2661618.54       6877549.4      2659934.48      6877501.65
      2659847.67      6877540.71      2659396.29      6877675.26
       2658991.4      6877856.17
#Sta/Elev= 30
  3301.5  402.15  3564.1  389.45  3794.2  382.86  4584.8  377.66  4934.7  378.63
  4974.7  376.94  4990.5  373.28  4992.5  372.78  5007.4  373.28  5016.6  377.98
  5028.4  378.56  5139.3  379.14  5237.2  382.29  5242.4  380.09  5270.4  383.21
  5275.6  380.19  5308.7  383.95    5314   380.6  5341.9  383.66  5347.1   381.1
    5485  387.67  5523.3  386.16  5602.7  391.24  5631.3  389.62  5649.1  392.54
  5654.6  390.09  5672.3  392.93  5677.8  390.43  5729.7  394.88  5995.9  398.39
#Mann= 5 ,-1 , 0
  3301.5     .05       0  4584.8     .12       0  4990.5     .07       0
  5007.4     .12       0  5139.3     .05       0
Bank Sta=4990.5,5007.4
XS Rating Curve= 0 ,0
Exp/Cntr=0.3,0.1

Type RM Length L Ch R = 1 ,45588   ,867,867,867
BEGIN DESCRIPTION:
Little Cottonwood Creek 54.0
END DESCRIPTION:
XS GIS Cut Line= 3
      2661620.38      6876693.82      2659926.04      6876625.98
      2658484.79      6876533.77
#Sta/Elev= 30
  3304.3  399.21  3528.9  395.43  3809.1  384.21  4089.3  378.77  4109.3  377.26
  4219.4  377.41    4247  380.61  4299.5  376.57  4349.5  377.43  4399.6  376.17
  4449.6  377.73    4767  376.86    4940  378.15    4980  375.78  4999.8  376.19
  5001.6  369.93  5003.6  369.43  5018.6  369.93  5020.1  374.56  5040.1  376.66
  5110.3  377.74  5254.5  376.58  5440.9  377.56  5721.5  382.03  5938.2  388.72
  6002.1   387.5  6091.6  391.92  6162.4  391.66  6312.7  395.74  6444.2  397.11
#Mann= 5 ,-1 , 0
  3304.3     .05       0    4767     .12       0  5001.6     .07       0
  5018.6     .12       0  5254.5     .05       0
Bank Sta=5001.6,5018.6
XS Rating Curve= 0 ,0
Exp/Cntr=0.3,0.1

Type RM Length L Ch R = 1 ,44721   ,917,917,917
BEGIN DESCRIPTION:
Mapping XS b3aee62c
END DESCRIPTION:
XS GIS Cut Line= 4
      2661479.62      6876316.76      2660186.22      6875934.81
      2659274.76      6876038.98      2658510.93      6876438.25
#Sta/Elev= 30
  3641.1  396.98  3811.7  398.93  4124.9  387.24  4205.7  382.75    4406  377.23
  4564.7  375.75  4677.1  376.85  4703.1  374.99  4781.4  376.54  4846.7  373.97
  4864.8  376.11  4927.4  374.06  4958.7  374.95  4969.1   373.4  4979.1  368.46
  4981.1  367.96  4996.1  368.46  4997.6  374.88  5002.6  373.69  5050.3  376.23
  5309.4  375.96  5342.2  374.13  5362.3  375.93  5422.7   376.7  5928.3  378.53
  6131.4  380.93  6278.1  385.55  6300.6  384.69  6330.6  387.22    6769  396.17
#Mann= 5 ,-1 , 0
  3641.1     .05       0  4124.9     .12       0  4979.1     .07       0
  4996.1     .12       0  5309.4     .05       0
Bank Sta=4979.1,4996.1
XS Rating Curve= 0 ,0
Exp/Cntr=0.3,0.1

Type RM Length L Ch R = 1 ,43804   ,872,872,872
BEGIN DESCRIPTION:
Little Cottonwood Creek 52.0
END DESCRIPTION:
XS GIS Cut Line= 4
      2661776.01      6874010.99      2660750.45      6875123.18
      2660529.95      6875252.34      2658662.79      6876299.39
#Sta/Elev= 30
  3231.6   406.5  3415.6  401.15  3564.2  391.46  3875.5  379.49    4201  375.06
  4398.7  375.65  4583.2  376.61  4590.6  369.27  4611.6  371.87  4618.9   376.6
  4695.2  376.26  4734.7  375.94  4958.2  374.57  4971.6   372.6  4972.8  366.34
  4974.8  365.84  4989.9  366.34  4999.4   374.3  5008.9  374.87  5119.2  372.94
  5149.2  375.11    5255  375.44  5684.4  375.48  5715.4  373.75    6457  379.71
  6516.3  378.56  6770.8  382.44  6873.5  387.15  6986.4  388.15  7140.7   393.5
#Mann= 7 ,-1 , 0
  3231.6     .05       0  4398.7     .12       0  4695.2     .05       0
  4734.7     .12       0  4972.8     .07       0  4989.9     .12       0
    5255     .05       0
Bank Sta=4972.8,4989.9
XS Rating Curve= 0 ,0
Exp/Cntr=0.3,0.1

Type RM Length L Ch R = 1 ,42932   ,1125,1125,1125
BEGIN DESCRIPTION:
Little Cottonwood Creek 51.0
END DESCRIPTION:
XS GIS Cut Line= 3
      2661526.04      6873560.97        2659976.        6874711.
       2658812.1       6876105.8
#Sta/Elev= 30
  3069.4  402.81  3233.2  395.18  3462.8  394.36  3754.8  381.63  3852.1  379.38
  4027.2  376.68  4081.3  376.49  4186.3  375.12  4583.3   374.3  4706.3  373.09
  4777.2  375.13  4862.8  373.34  4949.7  375.23  4971.3  374.64    4983  364.57
    4985  364.07  5001.4  364.57  5006.6     371  5049.6  375.14  5283.9  373.95
  5298.2  373.21  5304.7  370.42  5397.7  373.98    5660  373.68  6299.1  378.25
  6640.1  383.05  6681.7  385.81  6724.7  384.57  6753.3  387.18  6816.1  387.87
#Mann= 9 ,-1 , 0
  3069.4     .05       0  3852.1     .12       0  4027.2     .05       0
  4081.3     .12       0  4186.3     .05       0  4583.3     .12       0
    4983     .07       0  5001.4     .12       0  5397.7     .05       0
Bank Sta=4983,5001.4
XS Rating Curve= 0 ,0
Exp/Cntr=0.3,0.1

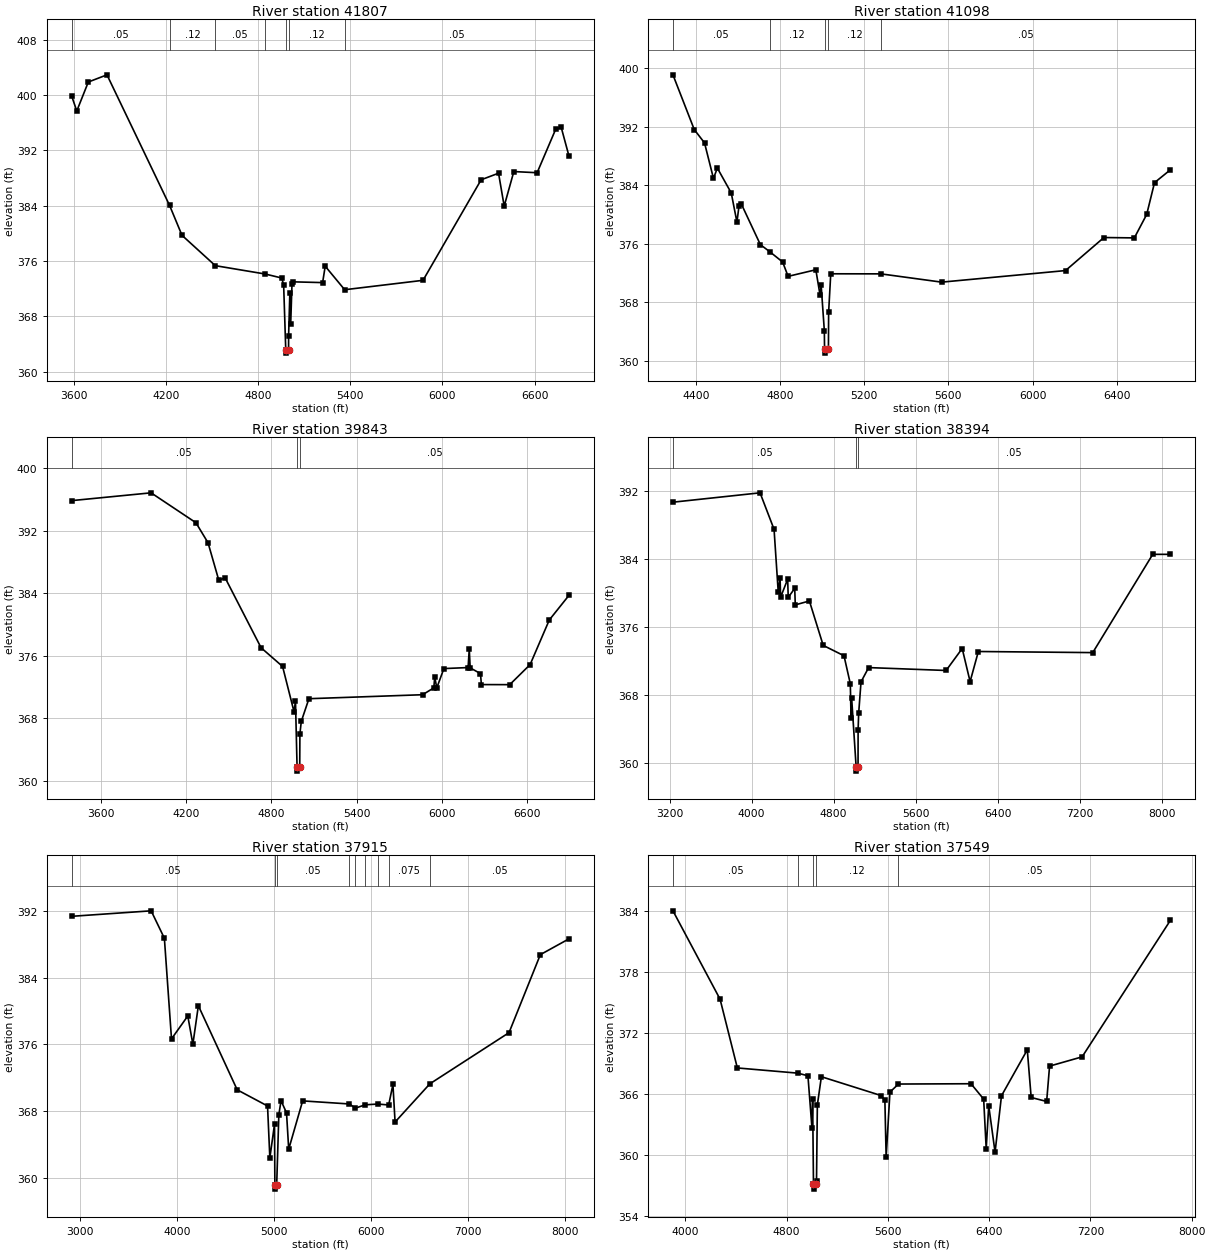
Type RM Length L Ch R = 1 ,41807   ,709,709,709
BEGIN DESCRIPTION:
Little Cottonwood Creek 50.0
END DESCRIPTION:
XS GIS Cut Line= 3
       2661304.8      6873322.91      2659905.59      6873977.93
      2658304.76      6874522.92
#Sta/Elev= 30
  3587.2  399.93  3621.3  397.71  3696.3   401.9  3817.7  402.94    4225  384.05
  4305.6  379.73  4522.4  375.34  4847.4  374.13    4955  373.55    4967   372.5
  4980.6  363.19  4982.6  362.69  4999.1  363.19  4999.2  365.16  5007.2  371.33
  5012.7  366.85  5021.3  372.76    5030     373  5220.4  372.89  5237.3  375.26
  5363.9  371.86  5873.6  373.22  6251.5  387.76  6364.8  388.71  6401.5  383.95
  6464.2  388.95  6615.7  388.78  6735.9  395.04  6772.5  395.34  6823.2  391.17
#Mann= 7 ,-1 , 0
  3587.2     .05       0    4225     .12       0  4522.4     .05       0
  4847.4     .12       0  4980.6     .07       0  4999.1     .12       0
  5363.9     .05       0
Bank Sta=4980.6,4999.1
XS Rating Curve= 0 ,0
Exp/Cntr=0.3,0.1

Type RM Length L Ch R = 1 ,41098   ,1255,1255,1255
BEGIN DESCRIPTION:
Little Cottonwood Creek 48.0
END DESCRIPTION:
XS GIS Cut Line= 3
      2660826.05      6873160.99      2659554.27      6873371.44
      2658625.48      6873913.96
#Sta/Elev= 30
  4290.8  399.06  4392.2  391.58  4440.9  389.77  4483.4  384.92  4501.9  386.33
    4568  382.93  4594.9  378.96  4605.1  381.21  4615.2  381.47  4706.4  375.88
  4749.8  374.94  4812.2  373.51  4838.2  371.55    4970  372.45  4990.2  368.97
  4995.3  370.33  5010.5   364.1  5011.4  361.57  5013.4  361.07  5029.9  361.57
  5030.8  366.63  5040.9   371.9    5279  371.89    5568  370.76  6156.9  372.34
  6339.4  376.85    6484   376.8  6542.7     380  6579.9  384.34  6655.5   386.1
#Mann= 5 ,-1 , 0
  4290.8     .05       0  4749.8     .12       0  5011.4     .07       0
  5029.9     .12       0    5279     .05       0
Bank Sta=5011.4,5029.9
XS Rating Curve= 0 ,0
Exp/Cntr=0.3,0.1

Type RM Length L Ch R = 1 ,39843   ,1449,1449,1449
BEGIN DESCRIPTION:
Mapping XS 9d5eec63
END DESCRIPTION:
XS GIS Cut Line= 4
       2661568.2      6872255.99      2659992.64      6872455.64
      2659615.04      6872585.85      2658694.89      6873783.77
#Sta/Elev= 30
  3394.4  395.87  3953.7  396.87    4269  393.04  4354.2  390.47  4429.2  385.71
  4475.2  385.95  4727.2  377.02  4878.4  374.62    4959  368.81  4969.1  370.18
  4980.3  361.71  4982.3  361.21  4998.9  361.71  5000.2  365.98  5009.9  367.58
  5063.6  370.49    5863     371  5941.9  371.88  5948.2  373.28  5962.7  371.87
  6012.5  374.35  6182.9  374.48  6191.1  376.86  6197.4  374.44    6270  373.71
  6276.3   372.3  6475.6  372.29  6618.9  374.86  6753.9  380.58  6892.5  383.74
#Mann= 3 ,-1 , 0
  3394.4     .05       0  4980.3     .03       0  4998.9     .05       0
Bank Sta=4980.3,4998.9
XS Rating Curve= 0 ,0
Exp/Cntr=0.3,0.1

Type RM Length L Ch R = 1 ,38394   ,479,479,479
BEGIN DESCRIPTION:
Mapping XS de6f4205
END DESCRIPTION:
XS GIS Cut Line= 5
      2661233.99      6870823.71      2660261.97      6870508.66
      2659949.19       6871184.7      2658929.51      6873386.26
      2658581.06      6873944.63
#Sta/Elev= 30
  3233.3  390.63  4082.7  391.73  4219.3  387.44  4260.3  380.02  4277.7  381.76
  4283.2  379.46    4352  381.58  4357.5  379.44  4420.8   380.5  4426.3  378.56
  4563.9  379.02  4698.4   373.8  4901.3  372.58  4962.9  369.29  4970.1  365.29
  4975.6  367.65  5019.6  359.52  5021.6  359.02  5038.3  359.52  5038.9  363.89
  5044.4  365.82  5067.3  369.51  5141.6  371.19    5897  370.85  6053.9  373.43
    6131  369.54  6211.4  373.08  7327.1  372.95  7911.9   384.5  8084.4   384.5
#Mann= 3 ,-1 , 0
  3233.3     .05       0  5019.6     .05       0  5038.3     .05       0
Bank Sta=5019.6,5038.3
XS Rating Curve= 0 ,0
Exp/Cntr=0.3,0.1

Type RM Length L Ch R = 1 ,37915   ,366,366,366
BEGIN DESCRIPTION:
Mapping XS a5fcf84c
END DESCRIPTION:
XS GIS Cut Line= 5
       2661238.3      6870762.94      2659827.95      6870313.34
      2659592.74      6870877.49      2658814.49      6872505.18
      2658228.53      6873592.46
#Sta/Elev= 30
  2908.5  391.38  3729.6  392.04    3866  388.75  3939.5  376.67  4107.4  379.42
  4159.9  376.03  4216.5  380.65    4617  370.56    4930  368.62  4953.8  362.38
    5002  366.44  5005.6  359.14  5007.6  358.64  5024.3  359.14  5046.5  367.56
  5069.2  369.26  5125.8  367.79  5148.3  363.43  5292.1  369.23  5774.4  368.86
  5835.7  368.36  5937.7  368.76  6067.9  368.85  6179.4  368.74  6223.2   371.2
  6245.3  366.69  6604.3  371.28  7420.7  377.42  7743.5  386.78  8039.3  388.68
#Mann= 9 ,-1 , 0
  2908.5     .05       0  5005.6     .03       0  5024.3     .05       0
  5774.4    .075       0  5835.7     .05       0  5937.7    .075       0
  6067.9     .05       0  6179.4    .075       0  6604.3     .05       0
Bank Sta=5005.6,5024.3
XS Rating Curve= 0 ,0
Exp/Cntr=0.3,0.1

Type RM Length L Ch R = 1 ,37549   ,1230,1230,1230
BEGIN DESCRIPTION:
Little Cottonwood Creek 44.0
END DESCRIPTION:
XS GIS Cut Line= 5
      2660088.32      6870155.81      2659369.61      6870463.08
      2659150.86      6871072.46      2658025.43      6871105.45
      2656676.64      6871370.58
#Sta/Elev= 30
  3902.6  383.99  4274.9  375.31  4411.3  368.56  4888.6  368.05  4968.9  367.79
  5000.6  362.68  5005.9  365.48  5012.7  357.16  5014.7  356.66  5031.4  357.16
  5036.6  357.44  5043.3  364.93  5075.1   367.7  5546.6  365.85  5576.7  365.38
  5586.7  359.78  5616.7  366.19    5684  366.98  6256.9  367.01    6357   365.5
    6377  360.63    6397  364.85    6447  360.28  6497.8  365.83  6701.6  370.34
  6732.2  365.66  6854.5  365.27  6877.6  368.74  7134.6  369.65  7832.2  383.06
#Mann= 5 ,-1 , 0
  3902.6     .05       0  4888.6     .12       0  5012.7     .07       0
  5031.4     .12       0    5684     .05       0
Bank Sta=5012.7,5031.4
XS Rating Curve= 0 ,0
Exp/Cntr=0.3,0.1

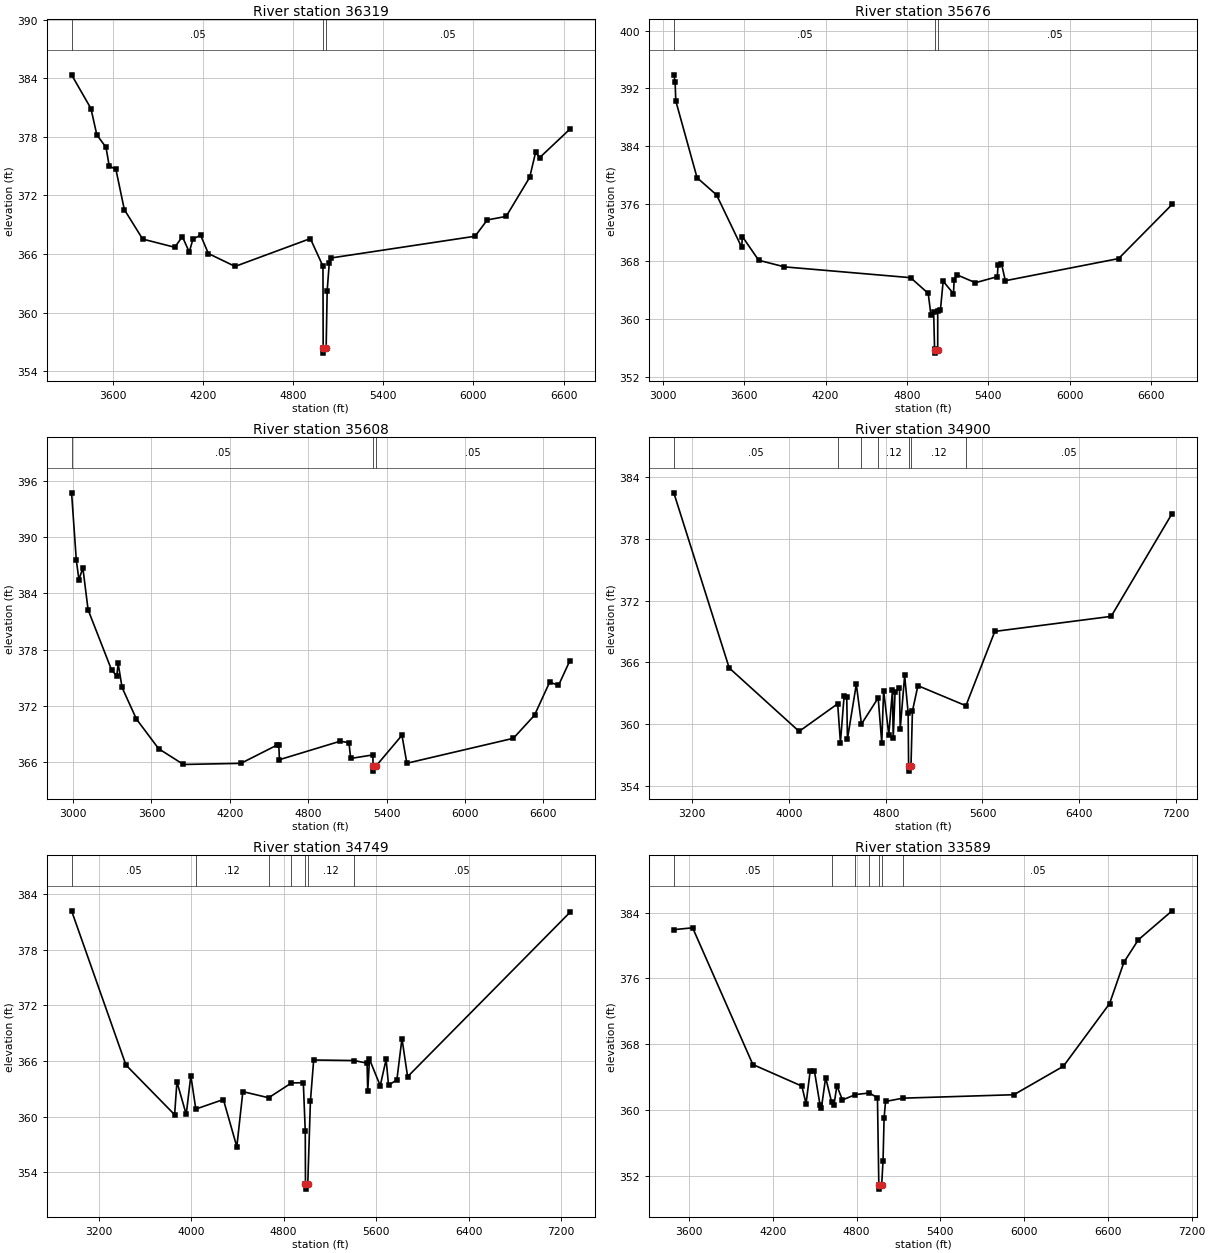
Type RM Length L Ch R = 1 ,36319   ,643,643,643
BEGIN DESCRIPTION:
Little Cottonwood Creek 43.0
END DESCRIPTION:
XS GIS Cut Line= 3
      2660023.05      6870137.93        2658376.        6870411.
      2656904.78      6871146.61
#Sta/Elev= 30
  3326.9  384.35  3455.7   380.9  3494.8   378.2  3555.8  376.93  3577.3  375.02
  3621.9  374.66  3677.8  370.55  3799.7  367.53  4013.2  366.69  4063.9  367.78
  4109.7   366.2  4134.8  367.55  4185.5  367.92  4236.7  366.05  4414.6  364.73
  4915.3  367.58  4999.2  364.75  5000.6  356.35  5002.6  355.85  5020.3  356.35
  5027.2  362.25  5041.2  365.08  5055.1   365.6    6011  367.82  6092.1  369.49
  6217.9  369.85  6374.4  373.85  6413.5   376.4  6441.5  375.88  6641.3  378.78
#Mann= 3 ,-1 , 0
  3326.9     .05       0  5000.6     .03       0  5020.3     .05       0
Bank Sta=5000.6,5020.3
XS Rating Curve= 0 ,0
Exp/Cntr=0.3,0.1

Type RM Length L Ch R = 1 ,35676   ,68,68,68
BEGIN DESCRIPTION:
Mapping XS 2b482014
END DESCRIPTION:
XS GIS Cut Line= 5
       2660040.4      6869916.58      2659189.69       6869864.5
      2658117.64       6869864.5      2657622.85      6869834.12
      2657002.18      6870923.54
#Sta/Elev= 30
  3080.8  393.89  3090.3  392.94  3095.3  390.27  3252.2  379.61  3395.8  377.23
  3581.2  369.96  3586.2  371.45  3706.4  368.16  3896.7  367.24  4826.8  365.74
  4956.8  363.56  4976.8  360.52  4996.8  360.97  5003.5  355.85    5007  355.77
    5009  355.27  5026.7  355.77  5026.8  361.08  5046.9   361.3  5066.9  365.25
  5142.9  363.52  5147.9  365.41  5167.1  366.15  5304.7  365.04  5466.4  365.88
  5471.4  367.55  5496.8  367.68  5525.4  365.32  6360.5  368.39  6754.7   375.9
#Mann= 3 ,-1 , 0
  3080.8     .05       0    5007     .03       0  5026.7     .05       0
Bank Sta=5007,5026.7
XS Rating Curve= 0 ,0
Exp/Cntr=0.3,0.1

Type RM Length L Ch R = 1 ,35608   ,708,708,708
BEGIN DESCRIPTION:
Mapping XS 71f9cda8
END DESCRIPTION:
XS GIS Cut Line= 4
      2660092.43      6869829.78      2658087.26      6869812.42
      2657596.81      6869786.37       2656950.7       6870935.5
#Sta/Elev= 30
  2988.6  394.72    3025  387.51    3045  385.47    3075  386.71    3115  382.25
    3295  375.83    3335   375.2    3345  376.56    3375  373.97  3485.1   370.6
  3655.1  367.44  3845.1  365.76  4285.1  365.88  4565.1  367.85    4575  367.84
    4580  366.27  5045.2  368.24  5112.6  368.08  5125.3   366.4  5295.5  366.78
  5297.1  365.55  5299.1  365.05  5316.9  365.55  5518.1  368.87  5555.7  365.89
  6371.1  368.55    6533  371.01    6649  374.54  6716.6  374.19  6803.3  376.81
#Mann= 3 ,-1 , 0
  2988.6     .05       0  5297.1     .03       0  5316.9     .05       0
Bank Sta=5297.1,5316.9
XS Rating Curve= 0 ,0
Exp/Cntr=0.3,0.1

Type RM Length L Ch R = 1 ,34900   ,151,151,151
BEGIN DESCRIPTION:
Mapping XS 26534c0d
END DESCRIPTION:
XS GIS Cut Line= 5
      2659376.35       6868280.3      2658486.56      6868310.68
      2657931.01      6869209.12       2657553.4      6869808.08
      2656798.21      6871062.39
#Sta/Elev= 30
  3048.4  382.46  3506.3  365.45  4084.2  359.29  4402.9  361.97  4425.8  358.21
  4456.4  362.77  4477.9  362.66  4483.7  358.55    4557  363.87  4599.5     360
  4737.8  362.54  4767.4  358.19  4782.8  363.26  4825.3  358.97  4856.1   363.3
    4862  358.61  4877.4  363.11    4914  363.47  4919.9  359.51  4956.6  364.72
  4985.5  361.07  4989.2  355.93  4991.2  355.43    5009  355.93  5020.9  361.26
  5066.2  363.73  5463.1  361.78  5701.9     369  6663.7  370.46  7167.2  380.44
#Mann= 7 ,-1 , 0
  3048.4     .05       0  4402.9     .12       0  4599.5     .05       0
  4737.8     .12       0  4989.2     .07       0    5009     .12       0
  5463.1     .05       0
Bank Sta=4989.2,5009
XS Rating Curve= 0 ,0
Exp/Cntr=0.3,0.1

Type RM Length L Ch R = 1 ,34749   ,1160,1160,1160
BEGIN DESCRIPTION:
Mapping XS bb1e8767
END DESCRIPTION:
XS GIS Cut Line= 6
        2659385.      6868219.53      2658317.29      6868288.98
       2657822.5      6869100.61      2657718.33      6869317.62
       2657240.9      6870025.09      2656659.29      6871066.78
#Sta/Elev= 30
  2966.7   382.2  3436.7  365.58  3857.6  360.22  3877.6  363.77  3957.8  360.25
  3997.9  364.43  4040.7  360.83  4279.2  361.86  4395.4  356.77  4447.6  362.71
  4670.6  362.05  4868.1  363.65  4970.5  363.67  4987.2  358.42  4988.9   352.7
  4990.9   352.2  5008.7   352.7  5031.7  361.67  5059.9  366.12  5410.2  366.06
  5521.3  365.78  5527.3  362.77  5542.3   366.2  5635.3  363.35  5686.2  366.18
  5707.2  363.41  5779.1  363.97  5823.2  368.43  5872.1  364.32  7274.5  382.02
#Mann= 7 ,-1 , 0
  2966.7     .05       0  4040.7     .12       0  4670.6     .05       0
  4868.1     .12       0  4988.9     .07       0  5008.7     .12       0
  5410.2     .05       0
Bank Sta=4988.9,5008.7
XS Rating Curve= 0 ,0
Exp/Cntr=0.3,0.1

Type RM Length L Ch R = 1 ,33589   ,1021,1021,1021
BEGIN DESCRIPTION:
Little Cottonwood Creek 39.0
END DESCRIPTION:
XS GIS Cut Line= 3
       2659480.5      6868158.77        2657976.        6868261.
      2656175.99        6869261.
#Sta/Elev= 30
  3492.1  381.95  3626.9  382.17  4057.9  365.52  4408.7  362.89  4438.8  360.74
  4468.8  364.79  4498.9  364.72    4539  360.57    4549  360.27  4579.1  363.93
  4621.5  360.96  4639.2  360.63  4659.3  362.94  4699.4   361.2  4792.5  361.86
  4891.9  362.05    4950  361.47  4959.8  350.84  4961.8  350.34  4980.2  350.84
    4990  353.81  4997.6  359.02  5008.1  361.02  5132.3  361.42  5926.7  361.84
  6281.3  365.31  6611.9  372.94  6714.9  377.99  6817.8  380.71  7059.2  384.24
#Mann= 7 ,-1 , 0
  3492.1     .05       0  4621.5     .12       0  4792.5     .05       0
  4891.9     .12       0  4959.8     .07       0  4980.2     .12       0
  5132.3     .05       0
Bank Sta=4959.8,4980.2
XS Rating Curve= 0 ,0
Exp/Cntr=0.3,0.1

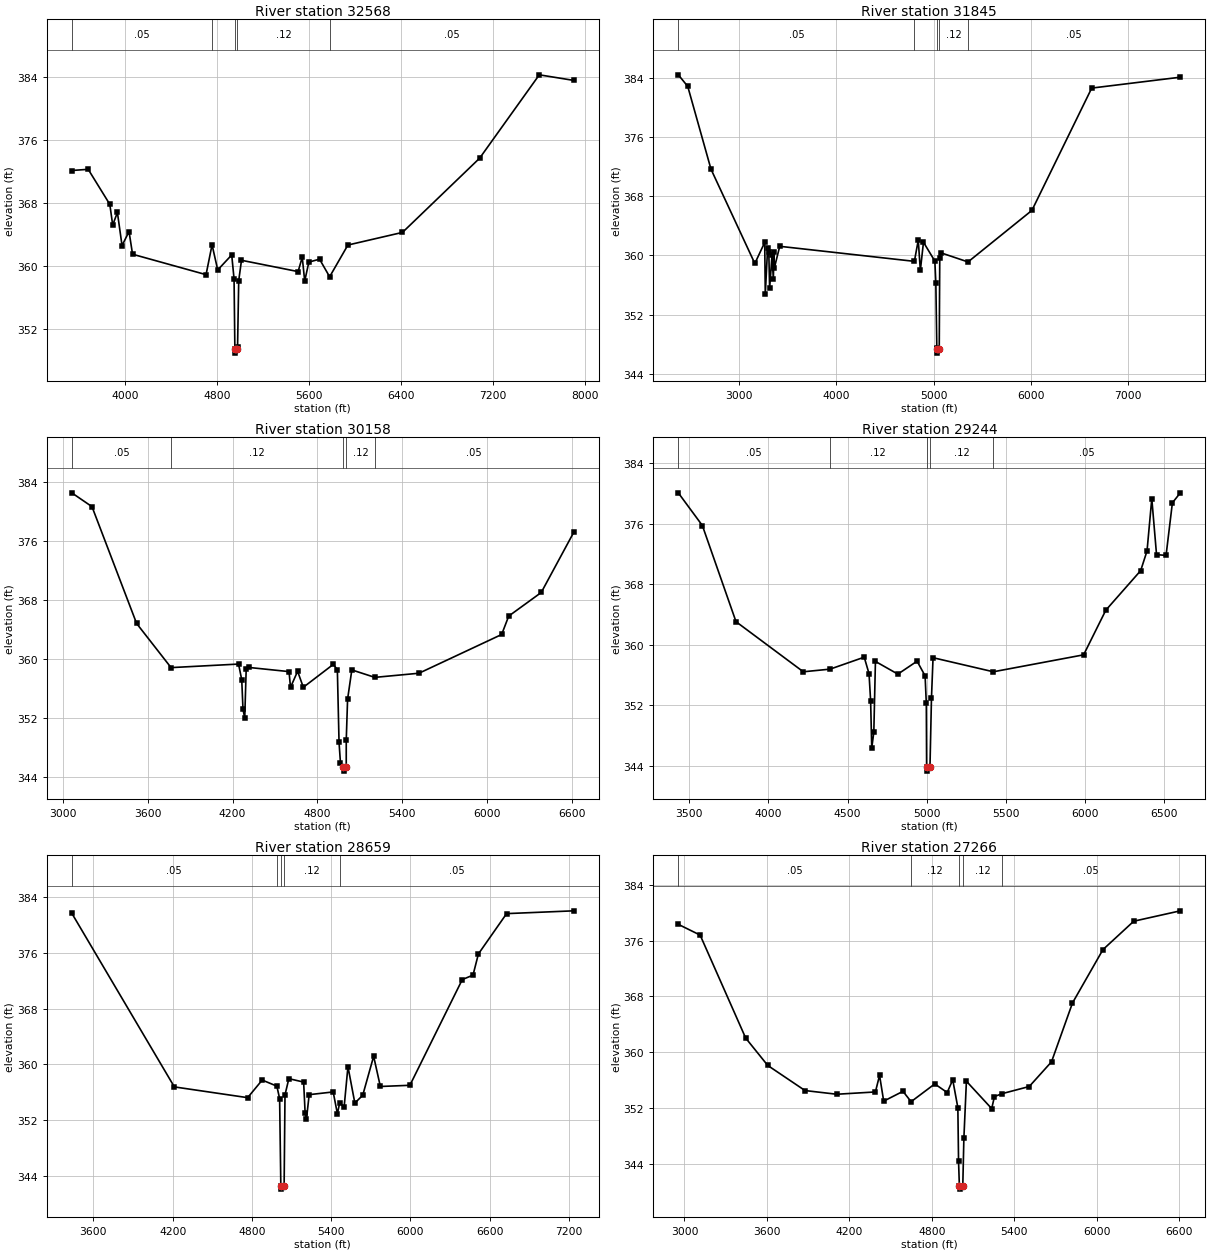
Type RM Length L Ch R = 1 ,32568   ,723,723,723
BEGIN DESCRIPTION:
Little Cottonwood Creek 37.0
END DESCRIPTION:
XS GIS Cut Line= 3
      2659306.84      6867590.19      2657865.68      6867350.83
      2655457.12      6868966.02
#Sta/Elev= 30
  3539.1  372.13  3681.8  372.28  3869.6  367.82  3894.7  365.18  3935.6  366.79
  3975.8  362.57  4036.7  364.36  4067.1  361.47  4705.7  358.87  4757.8  362.67
  4807.1  359.47  4928.7  361.38    4949  358.32  4956.1  349.38  4958.2  348.88
  4976.5  349.38  4979.4  349.65  4989.5  358.11  5013.5   360.7  5505.3  359.26
  5541.4  361.09  5562.7  358.05  5598.7  360.47  5691.7  360.84  5779.3   358.6
  5937.8  362.64  6412.1  364.25  7082.6   373.7  7600.6  384.31    7900   383.6
#Mann= 5 ,-1 , 0
  3539.1     .05       0  4757.8     .12       0  4956.1     .07       0
  4976.5     .12       0  5779.3     .05       0
Bank Sta=4956.1,4976.5
XS Rating Curve= 0 ,0
Exp/Cntr=0.3,0.1

Type RM Length L Ch R = 1 ,31845   ,1687,1687,1687
BEGIN DESCRIPTION:
Little Cottonwood Creek 36.0
END DESCRIPTION:
XS GIS Cut Line= 4
      2659823.38      6865762.93      2659026.45      6866309.83
      2657479.53      6866909.71      2654962.29      6867242.97
#Sta/Elev= 30
  2374.3  384.39  2471.1  382.83  2710.1  371.66  3161.4  358.92    3263  361.77
    3269  354.75  3292.8  360.99    3305  360.48  3313.7  355.57  3338.1  360.02
    3352  356.81  3357.6  360.46    3363  358.36  3417.5  361.24    4803  359.21
  4842.9  362.07  4864.4  357.99  4896.5  361.79  5013.6  359.25  5023.7  356.35
  5033.8  347.55  5038.1  347.32  5040.1  346.82  5058.8  347.32  5064.1  359.68
  5074.2  360.37  5354.9  359.13  6012.3  366.09  6627.6   382.6  7539.2  384.07
#Mann= 5 ,-1 , 0
  2374.3     .05       0    4803     .12       0  5038.1     .07       0
  5058.8     .12       0  5354.9     .05       0
Bank Sta=5038.1,5058.8
XS Rating Curve= 0 ,0
Exp/Cntr=0.3,0.1

Type RM Length L Ch R = 1 ,30158   ,914,914,914
BEGIN DESCRIPTION:
Little Cottonwood Creek 34.0
END DESCRIPTION:
XS GIS Cut Line= 4
      2659233.05       6865207.4      2658156.75      6865767.42
      2657439.83      6865874.16      2655825.95        6865911.
#Sta/Elev= 30
  3061.9  382.48    3205  380.61  3520.8  364.81  3764.6  358.84  4242.2  359.32
  4264.8  357.19  4273.6  353.18    4286  352.05  4296.2  358.62  4316.4  358.86
  4599.5   358.3  4609.9  356.17  4660.1  358.34  4700.6  356.18  4912.9  359.28
  4941.4  358.55  4953.3  348.74  4963.4  345.94  4983.3  345.34  4985.4  344.84
  5004.3  345.34  5004.4  349.07  5013.8  354.57  5043.8  358.53  5206.7  357.52
  5518.9  358.08  6104.1  363.32  6154.1  365.81  6384.2     369  6614.3  377.14
#Mann= 5 ,-1 , 0
  3061.9     .05       0  3764.6     .12       0  4983.3     .07       0
  5004.3     .12       0  5206.7     .05       0
Bank Sta=4983.3,5004.3
XS Rating Curve= 0 ,0
Exp/Cntr=0.3,0.1

Type RM Length L Ch R = 1 ,29244   ,585,585,585
BEGIN DESCRIPTION:
Little Cottonwood Creek 32.0
END DESCRIPTION:
XS GIS Cut Line= 3
      2659075.98        6864811.        2657526.        6865061.
      2655926.03        6864961.
#Sta/Elev= 30
  3430.4  380.08  3582.3  375.77    3795  363.06  4220.5  356.44  4389.8  356.79
  4605.4  358.37  4635.8  356.19  4645.9   352.6    4653  346.35  4666.1  348.47
  4676.3  357.81  4818.1  356.13  4939.6  357.84  4990.3   355.9  4997.9  352.25
  4999.9  343.81    5002  343.31    5021  343.81  5030.5  352.97  5040.5   358.3
  5421.7  356.44  5992.3  358.68  6132.6  364.58    6353  369.81  6393.1  372.41
  6423.2  379.32  6453.2  371.92  6513.4  371.82  6553.4  378.77  6603.5  380.09
#Mann= 5 ,-1 , 0
  3430.4     .05       0  4389.8     .12       0  4999.9     .07       0
    5021     .12       0  5421.7     .05       0
Bank Sta=4999.9,5021
XS Rating Curve= 0 ,0
Exp/Cntr=0.3,0.1

Type RM Length L Ch R = 1 ,28659   ,1393,1393,1393
BEGIN DESCRIPTION:
Little Cottonwood Creek 31.0
END DESCRIPTION:
XS GIS Cut Line= 3
      2659176.02        6864711.        2657626.        6864511.
      2655426.03      6864910.99
#Sta/Elev= 30
  3436.7  381.65  4213.1  356.79  4767.7  355.25  4877.9  357.77  4988.7   356.9
  5009.7  355.12  5018.8  342.66  5021.3  342.16  5043.8  342.66  5050.4  355.66
  5079.6  357.97  5191.4  357.48  5202.8  353.01    5213  352.21  5233.3  355.68
    5415  356.07  5446.8  352.96  5464.7  354.53  5497.6  353.86  5526.8   359.7
  5578.9  354.48  5638.6  355.59  5721.2  361.17    5772  356.85  5995.6  357.02
    6392  372.15  6473.3  372.79    6514  375.82  6727.4  381.59  7235.6  381.99
#Mann= 5 ,-1 , 0
  3436.7     .05       0  4988.7     .12       0  5018.8     .07       0
  5043.8     .12       0  5464.7     .05       0
Bank Sta=5018.8,5043.8
XS Rating Curve= 0 ,0
Exp/Cntr=0.3,0.1

Type RM Length L Ch R = 1 ,27266   ,100,100,100
BEGIN DESCRIPTION:
Little Cottonwood Creek 29.0
END DESCRIPTION:
XS GIS Cut Line= 3
      2659353.96      6863765.16      2657400.86      6863577.67
      2655729.99       6863312.2
#Sta/Elev= 30
  2955.2  378.32  3113.9  376.78  3445.4  362.01  3606.1  358.08  3877.4  354.48
  4108.4  353.95  4389.7  354.28  4419.9  356.66    4450  352.96  4590.6  354.37
  4649.4  352.88  4821.7  355.43  4912.1   354.2  4952.6  356.01  4989.8  352.03
  4994.9  344.34  5000.8  340.84  5003.3  340.34  5025.8  340.84  5033.6  347.61
  5052.1  355.82  5236.1  351.89  5256.3  353.62  5312.8  354.04  5509.5  355.06
  5671.5   358.6  5824.3  367.05  6046.1   374.7  6270.1  378.77  6609.1  380.26
#Mann= 5 ,-1 , 0
  2955.2     .05       0  4649.4     .12       0  5000.8     .07       0
  5025.8     .12       0  5312.8     .05       0
Bank Sta=5000.8,5025.8
XS Rating Curve= 0 ,0
Exp/Cntr=0.3,0.1

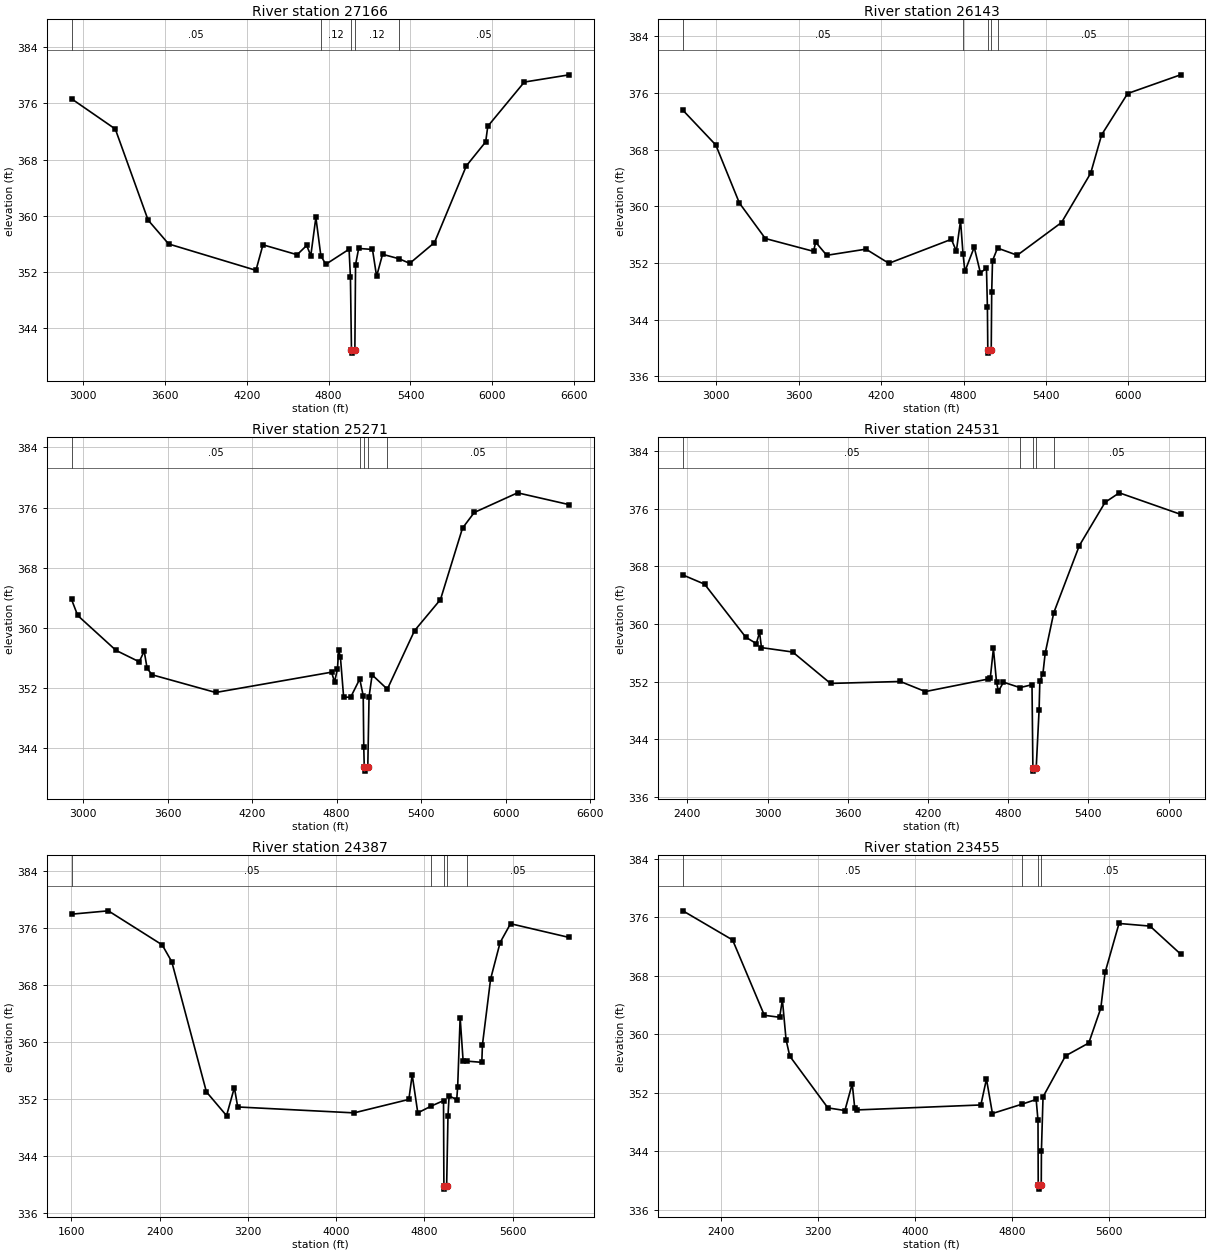
Type RM Length L Ch R = 1 ,27166   ,1023,1023,1023
BEGIN DESCRIPTION:
Little Cottonwood Creek 27.0
END DESCRIPTION:
XS GIS Cut Line= 3
      2659406.09      6863608.92      2657326.09      6863466.04
      2655781.11      6863223.51
#Sta/Elev= 30
  2915.1  376.65  3235.9  372.35  3476.5  359.39  3626.9     356  4267.2  352.25
  4318.5  355.88  4569.1  354.47  4639.2  355.79  4669.3  354.33  4706.6  359.77
  4743.2  354.31  4779.6  353.11    4950  355.25    4960  351.23  4967.5  340.97
    4970  340.47  4992.5  340.97  4997.5  353.04  5020.3  355.36  5121.6  355.22
  5151.9   351.4  5195.6  354.53  5317.3  353.89  5394.9  353.24  5576.3   356.2
  5809.9  367.11  5951.6  370.52  5967.1  372.74    6235  379.03  6563.9  380.06
#Mann= 5 ,-1 , 0
  2915.1     .05       0  4743.2     .12       0  4967.5     .07       0
  4992.5     .12       0  5317.3     .05       0
Bank Sta=4967.5,4992.5
XS Rating Curve= 0 ,0
Exp/Cntr=0.3,0.1

Type RM Length L Ch R = 1 ,26143   ,872,872,872
BEGIN DESCRIPTION:
Little Cottonwood Creek 26.0
END DESCRIPTION:
XS GIS Cut Line= 3
      2659296.46      6863540.01      2657271.64      6862562.94
      2655973.37      6862110.72
#Sta/Elev= 30
  2756.3  373.55  2995.6  368.65  3167.6  360.45  3356.4  355.44  3707.5  353.63
  3722.8  354.93  3803.5  353.07  4089.2  353.94  4255.7  351.94    4711  355.33
  4747.1  353.66  4777.6  357.96  4795.6  353.29  4809.4   350.8  4877.2  354.21
    4922   350.6  4966.4  351.24  4973.2   345.8  4976.1  339.76  4978.6  339.26
  5001.1  339.76  5004.5  347.88  5010.5  352.32    5047  354.09  5190.5  353.08
  5512.8   357.7  5725.1  364.66  5804.7  370.08  5994.2  375.91  6379.3  378.55
#Mann= 5 ,-1 , 0
  2756.3     .05       0  4795.6     .12       0  4976.1     .07       0
  5001.1     .12       0    5047     .05       0
Bank Sta=4976.1,5001.1
XS Rating Curve= 0 ,0
Exp/Cntr=0.3,0.1

Type RM Length L Ch R = 1 ,25271   ,740,740,740
BEGIN DESCRIPTION:
Mapping XS f8ce2cbf
END DESCRIPTION:
XS GIS Cut Line= 3
      2659254.83      6863032.93      2657588.13      6861808.94
       2656225.3      6861266.42
#Sta/Elev= 30
  2916.8  363.78  2960.5  361.65  3232.2  357.02  3397.3   355.5  3432.8  356.91
  3453.6  354.62  3489.1  353.77  3940.5  351.42  4763.9  354.12  4784.7  352.82
  4805.6  354.54  4813.6  357.03  4826.5  356.15  4849.5  350.79  4899.7   350.8
  4963.9  353.21  4988.5  350.98  4992.5  344.14    4996  341.47  4998.5  340.97
    5021  341.47    5030  350.85  5051.8  353.76  5159.8  351.86  5352.9  359.63
  5537.3  363.77  5693.8  373.26  5777.4  375.34  6084.8  377.95  6451.5  376.38
#Mann= 5 ,-1 , 0
  2916.8     .05       0  4963.9     .12       0    4996     .07       0
    5021     .12       0  5159.8     .05       0
Bank Sta=4996,5021
XS Rating Curve= 0 ,0
Exp/Cntr=0.3,0.1

Type RM Length L Ch R = 1 ,24531   ,144,144,144
BEGIN DESCRIPTION:
Little Cottonwood Creek 24.0
END DESCRIPTION:
XS GIS Cut Line= 4
      2659449.26        6862879.      2658980.48      6861671.47
      2657756.07      6861131.03      2656772.17      6860663.12
#Sta/Elev= 30
  2366.3  366.79  2528.8  365.51  2836.4  358.16  2915.4  357.27  2939.9  358.83
  2954.1  356.71  3187.6   356.1  3470.6  351.74    3993  352.01  4180.3  350.61
  4650.3  352.35  4666.2  352.49  4689.5  356.59  4712.8  351.91  4726.8  350.66
  4764.9  351.91    4888  351.16  4978.2  351.56  4984.8  340.07  4987.3  339.57
  5009.8  340.07  5031.4  348.12  5036.9  352.08  5059.6  353.05  5076.8  355.93
  5141.1  361.55  5332.2  370.86    5525  376.87  5631.3  378.19  6089.5  375.21
#Mann= 5 ,-1 , 0
  2366.3     .05       0    4888     .12       0  4984.8     .07       0
  5009.8     .12       0  5141.1     .05       0
Bank Sta=4984.8,5009.8
XS Rating Curve= 0 ,0
Exp/Cntr=0.3,0.1

Type RM Length L Ch R = 1 ,24387   ,932,932,932
BEGIN DESCRIPTION:
Little Cottonwood Creek 23.0
END DESCRIPTION:
XS GIS Cut Line= 3
      2661181.85      6861570.22       2657779.1      6861005.99
      2656869.31      6860460.12
#Sta/Elev= 30
  1601.8  377.98  1935.2  378.45    2423  373.67  2509.9  371.31  2824.1  353.02
  3006.6  349.68  3077.5  353.62  3107.9   350.9  4162.1  350.07  4658.8  351.96
  4689.2  355.42  4739.9  350.07  4863.6  351.04  4973.1  351.79  4976.5  339.86
    4979  339.36  5001.5  339.86  5013.6  349.67  5023.7  352.45  5092.7  351.94
  5101.3  353.72  5123.8  363.46    5151  357.31  5182.5  357.34  5320.1  357.17
  5325.9  359.64  5399.8  368.87  5486.1     374  5580.5  376.64    6112  374.71
#Mann= 5 ,-1 , 0
  1601.8     .05       0  4863.6     .12       0  4976.5     .07       0
  5001.5     .12       0  5182.5     .05       0
Bank Sta=4976.5,5001.5
XS Rating Curve= 0 ,0
Exp/Cntr=0.3,0.1

Type RM Length L Ch R = 1 ,23455   ,1087,1087,1087
BEGIN DESCRIPTION:
Little Cottonwood Creek 22.0
END DESCRIPTION:
XS GIS Cut Line= 4
      2661077.76      6860988.64      2659172.33      6860693.49
      2658249.07      6860337.14      2657320.05      6859591.88
#Sta/Elev= 30
  2082.2  376.88  2492.6  372.89  2754.8  362.58  2880.9  362.31  2903.6  364.71
    2934  359.24  2964.4     357  3279.2  349.91  3419.7  349.55  3480.4  353.22
  3500.7  349.92  3520.9  349.63  4542.4  350.31  4588.6  353.86  4637.8  349.14
  4882.3  350.42    4999  351.06  5014.1   348.2    5016  339.29  5018.5  338.79
    5041  339.29  5042.4  344.04  5055.7  351.42  5241.3  357.03  5433.4  358.79
  5532.6  363.56    5568  368.44    5683  375.15    5939  374.79    6191  370.97
#Mann= 4 ,-1 , 0
  2082.2     .05       0  4882.3     .12       0    5016     .07       0
    5041     .05       0
Bank Sta=5016,5041
XS Rating Curve= 0 ,0
Exp/Cntr=0.3,0.1