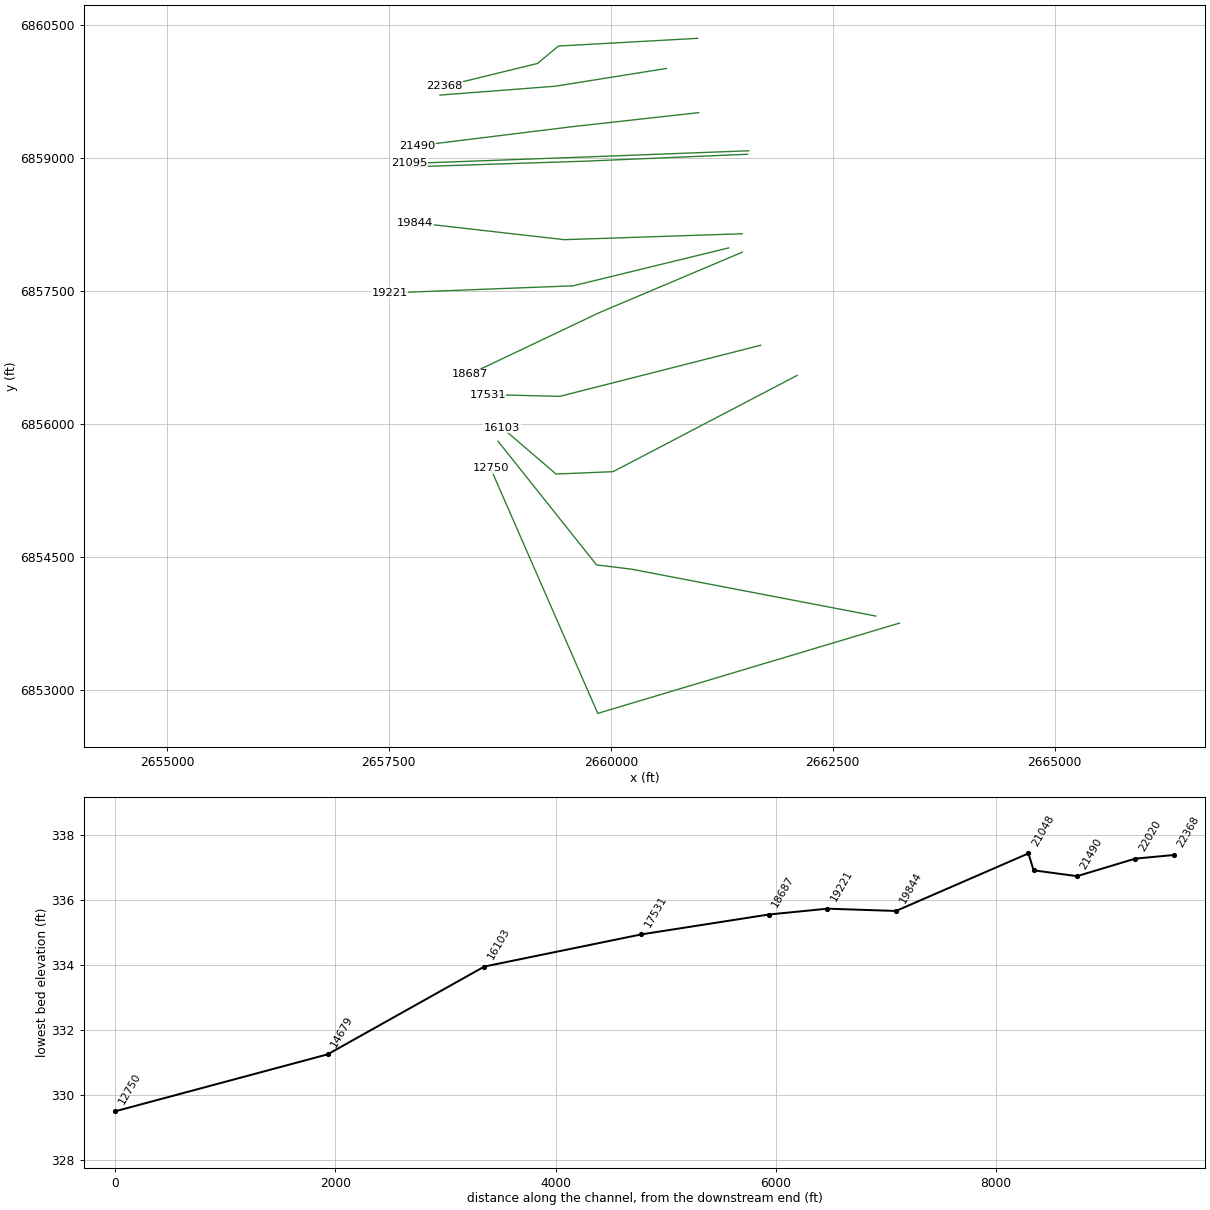
HEC-RAS study Little Cottonwood Creek.prj: Little Cottonwood Creek Base Level Engineering

--- Little Cottonwood Creek.g01 (geometry) --- (continued)

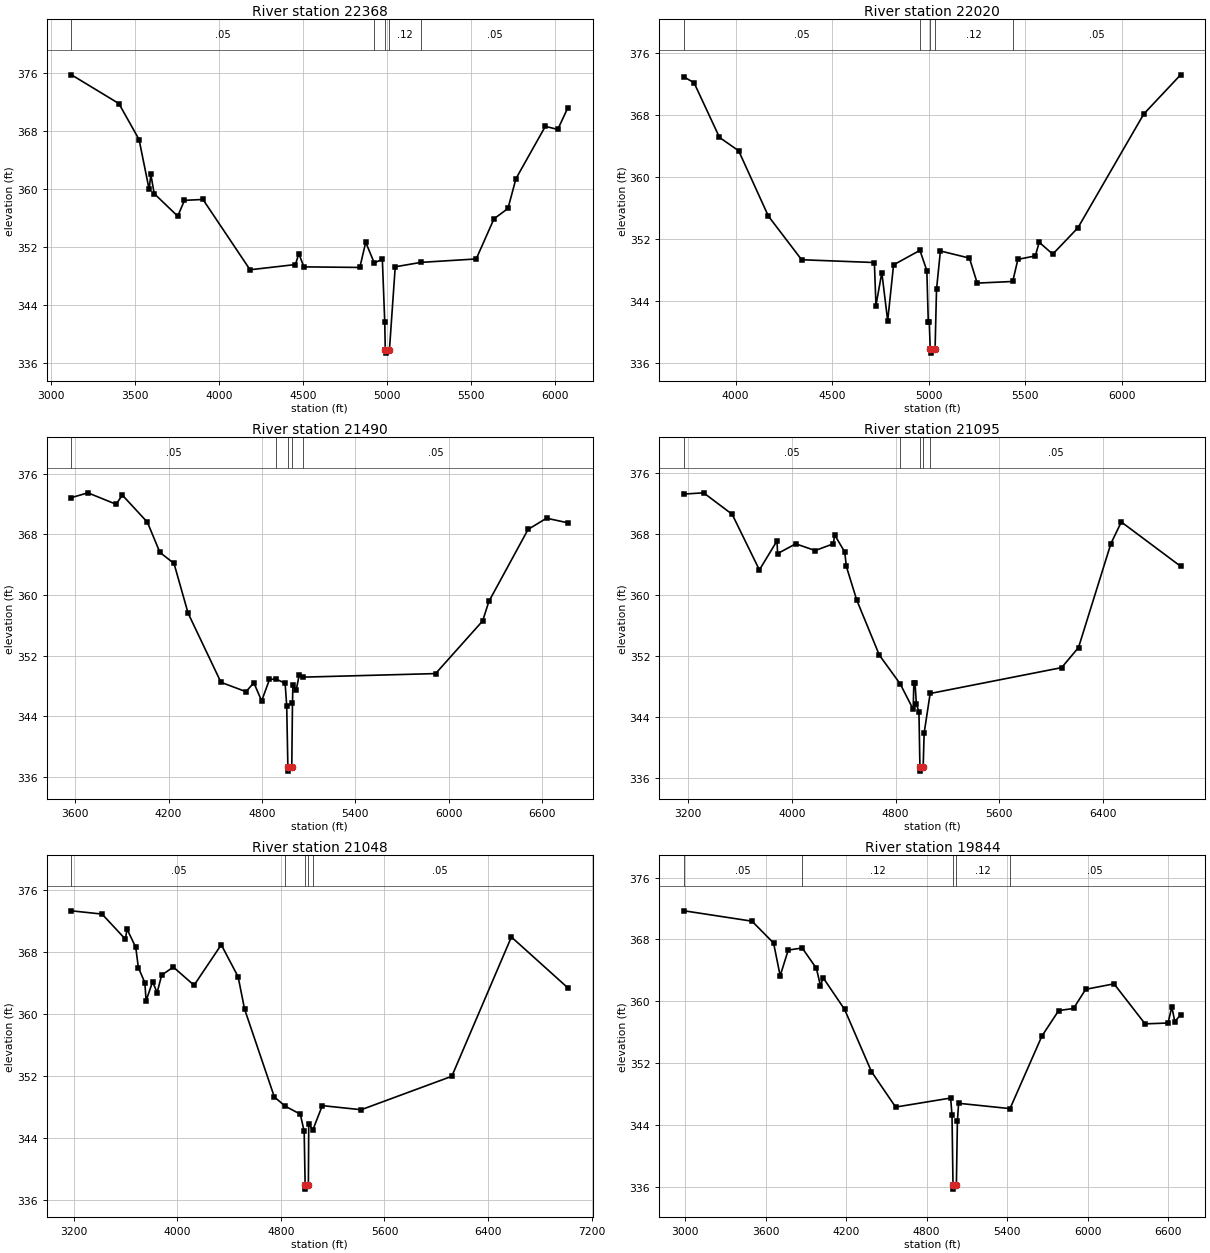
Type RM Length L Ch R = 1 ,22368   ,348,348,348
BEGIN DESCRIPTION:
Little Cottonwood Creek 21.0
END DESCRIPTION:
XS GIS Cut Line= 4
      2660977.85      6860350.61      2659411.04       6860263.8
      2659174.16      6860067.28      2658126.04      6859811.01
#Sta/Elev= 30
    3123  375.75  3405.3  371.79  3525.5  366.83  3585.6  359.95  3595.6  362.03
  3615.6  359.38  3755.8  356.26  3795.9  358.45    3906  358.57  4186.5  348.88
  4456.9   349.6  4476.9  351.11    4507  349.28  4840.3   349.2  4875.4  352.67
  4926.2  349.82  4974.4  350.34  4988.7  341.67  4991.8  337.89  4994.3  337.39
  5016.8  337.89  5051.1  349.29  5204.7   349.9  5533.4  350.37  5639.2   355.9
  5722.5  357.33  5770.2  361.44  5945.2  368.65  6019.1  368.22    6079   371.2
#Mann= 5 ,-1 , 0
    3123     .05       0  4926.2     .12       0  4991.8     .07       0
  5016.8     .12       0  5204.7     .05       0
Bank Sta=4991.8,5016.8
XS Rating Curve= 0 ,0
Exp/Cntr=0.3,0.1

Type RM Length L Ch R = 1 ,22020   ,530,530,530
BEGIN DESCRIPTION:
Little Cottonwood Creek 20.0
END DESCRIPTION:
XS GIS Cut Line= 3
        2660626.        6860011.        2659376.        6859811.
      2658076.04        6859711.
#Sta/Elev= 30
  3734.1  372.84  3784.7  372.11  3916.4  365.07  4015.8  363.34  4169.6  354.93
  4341.7  349.31  4718.3  348.95  4726.6  343.41  4756.9  347.66  4787.3  341.44
  4817.7  348.65  4954.2  350.52  4989.9  347.91  4997.5  341.32  5002.5  341.32
  5007.6  337.78  5010.1  337.28  5032.6  337.78  5040.1  345.49  5060.2  350.44
  5210.6  349.52  5250.7   346.3  5434.6  346.51  5461.4  349.36  5551.6   349.8
  5571.7  351.56  5641.9  350.03  5772.3  353.43  6113.3  368.09  6303.8  373.13
#Mann= 5 ,-1 , 0
  3734.1     .05       0  4954.2     .12       0  5007.6     .07       0
  5032.6     .12       0  5434.6     .05       0
Bank Sta=5007.6,5032.6
XS Rating Curve= 0 ,0
Exp/Cntr=0.3,0.1

Type RM Length L Ch R = 1 ,21490   ,395,395,395
BEGIN DESCRIPTION:
Little Cottonwood Creek 19.0
END DESCRIPTION:
XS GIS Cut Line= 3
      2660990.93      6859512.94      2659575.53       6859355.8
       2657822.5      6859139.67
#Sta/Elev= 30
  3575.9  372.86  3681.5  373.49  3862.6  371.98  3902.8  373.19  4063.8  369.61
  4144.3  365.62  4234.9  364.17  4325.4   357.6  4536.7  348.47  4697.7  347.23
    4748  348.41  4798.3  346.01  4848.6  348.84  4889.4  348.91  4949.2  348.34
  4959.3  345.38  4966.9  337.24  4969.4  336.74  4991.9  337.24  4996.4   345.7
  4999.1   348.1  5019.7   347.4  5039.8  349.44  5063.1  349.15  5916.4  349.62
  6218.7  356.57    6259  359.15  6510.9  368.66  6629.8  370.14  6766.3  369.53
#Mann= 5 ,-1 , 0
  3575.9     .05       0  4889.4     .12       0  4966.9     .07       0
  4991.9     .12       0  5063.1     .05       0
Bank Sta=4966.9,4991.9
XS Rating Curve= 0 ,0
Exp/Cntr=0.3,0.1

Type RM Length L Ch R = 1 ,21095   ,47,47,47
BEGIN DESCRIPTION:
Mapping XS 121e9f42
END DESCRIPTION:
XS GIS Cut Line= 3
      2661555.09      6859083.25      2659732.22       6859013.8
      2657728.97      6858940.09
#Sta/Elev= 30
  3169.6  373.22  3318.8  373.38    3539  370.57  3749.1  363.28  3884.8  367.08
  3889.8  365.42  4029.3   366.7  4179.4  365.82  4319.5   366.7  4329.5  367.87
  4407.7  365.62  4419.6  363.76  4499.7  359.35  4674.1  352.13  4835.6  348.34
  4935.6  345.01  4940.6  348.49    4950  348.45    4960  345.73    4980  344.67
  4987.5  337.42    4990  336.92  5012.5  337.42    5020  341.89  5066.4  347.09
  6080.7  350.48  6210.8  353.11    6461  366.74  6541.1  369.56  6998.4  363.76
#Mann= 5 ,-1 , 0
  3169.6     .05       0  4835.6     .12       0  4987.5     .07       0
  5012.5     .12       0  5066.4     .05       0
Bank Sta=4987.5,5012.5
XS Rating Curve= 0 ,0
Exp/Cntr=0.3,0.1

Type RM Length L Ch R = 1 ,21048   ,1204,1204,1204
BEGIN DESCRIPTION:
Mapping XS c63556fb
END DESCRIPTION:
XS GIS Cut Line= 3
      2661542.09      6859044.19      2659710.52      6858966.06
      2657710.32      6858900.98
#Sta/Elev= 30
  3181.9  373.37  3418.2  372.95  3598.4  369.71    3611  371.01  3678.4  368.66
  3698.5  366.05  3748.5   364.1  3758.5  361.76  3808.6  364.22  3843.5   362.8
  3878.6  365.07  3968.7  366.11  4128.9  363.76    4339  368.99  4469.2  364.86
  4519.2  360.68  4749.4  349.33  4834.1  348.14  4949.6  347.12  4979.6   344.9
  4987.1  337.94  4989.6  337.44  5012.1  337.94  5014.9   345.9    5046  345.06
  5119.7  348.22  5419.9  347.69  6120.2  352.01  6580.5  369.99  7016.4  363.43
#Mann= 5 ,-1 , 0
  3181.9     .05       0  4834.1     .12       0  4987.1     .07       0
  5012.1     .12       0    5046     .05       0
Bank Sta=4987.1,5012.1
XS Rating Curve= 0 ,0
Exp/Cntr=0.3,0.1

Type RM Length L Ch R = 1 ,19844   ,623,623,623
BEGIN DESCRIPTION:
Little Cottonwood Creek 16.0
END DESCRIPTION:
XS GIS Cut Line= 3
      2661480.48      6858148.06       2659475.3      6858081.16
      2657793.01      6858273.06
#Sta/Elev= 30
  2993.7  371.69  3498.5  370.35  3659.4  367.52  3708.6  363.28  3768.6  366.61
  3872.8  366.88  3978.7  364.24  4008.7  361.98  4028.8  363.03  4188.8  358.93
    4389  350.88  4569.1  346.29  4979.3  347.46  4989.3  345.21  4996.9  336.17
  4999.4  335.67  5021.9  336.17  5029.5  344.45  5038.6  346.78  5421.7  346.09
  5659.4  355.48  5784.4  358.78  5895.1  359.05  5985.6  361.53    6197  362.24
  6428.5  357.06  6599.6  357.17  6627.8  359.27  6649.9  357.35  6693.2  358.24
#Mann= 5 ,-1 , 0
  2993.7     .05       0  3872.8     .12       0  4996.9     .07       0
  5021.9     .12       0  5421.7     .05       0
Bank Sta=4996.9,5021.9
XS Rating Curve= 0 ,0
Exp/Cntr=0.3,0.1

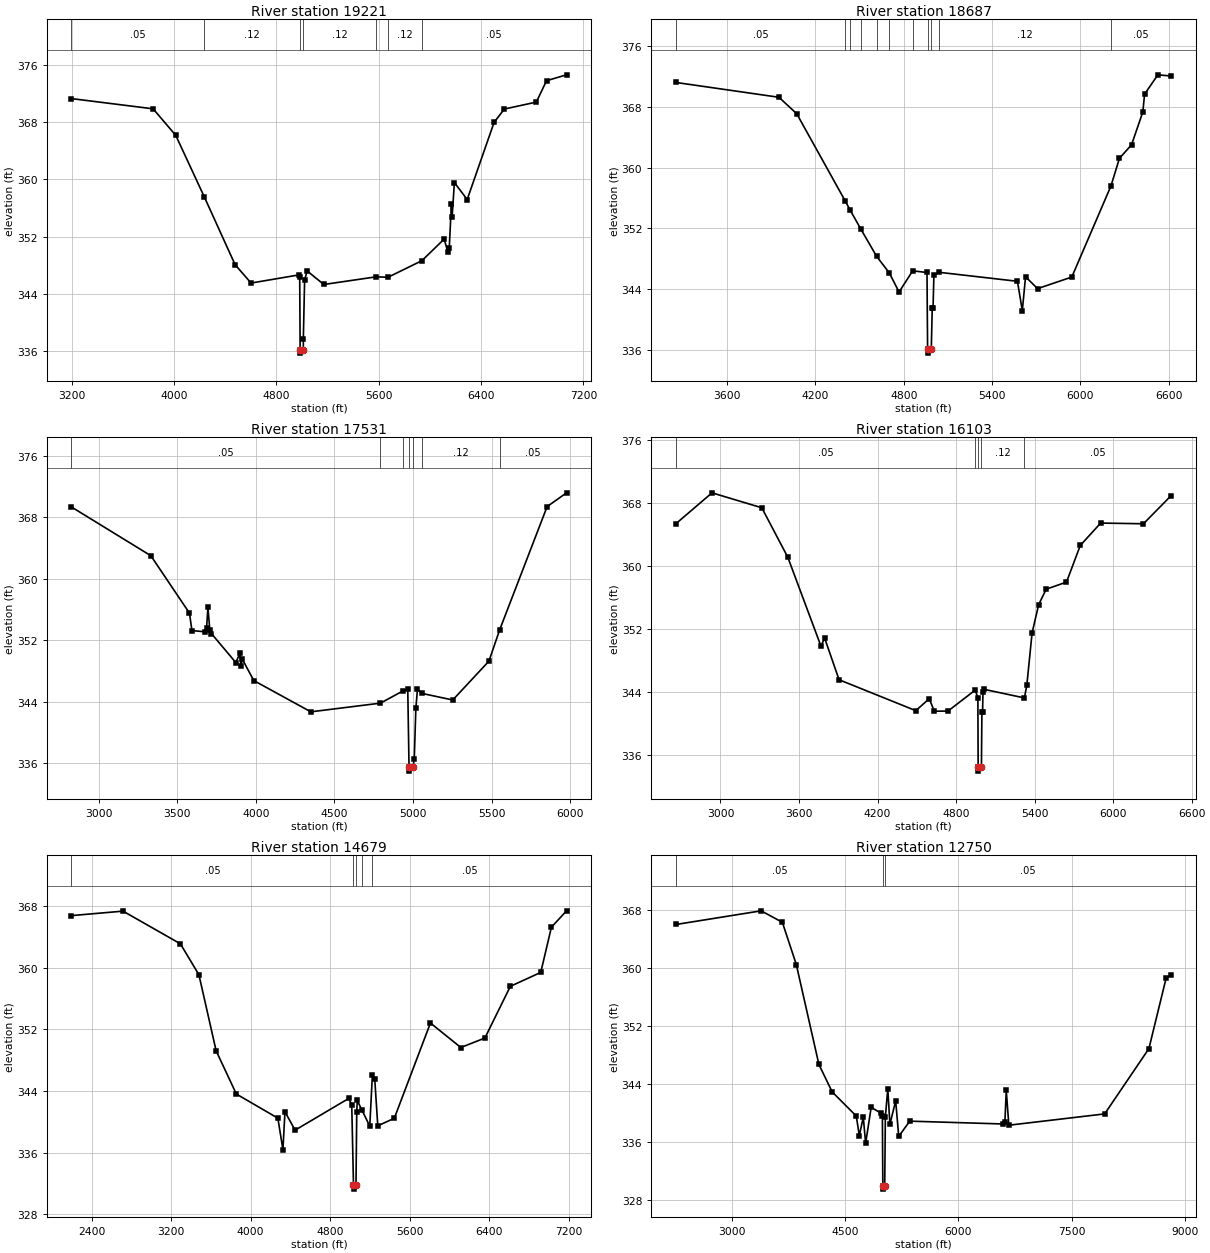
Type RM Length L Ch R = 1 ,19221   ,534,534,534
BEGIN DESCRIPTION:
Little Cottonwood Creek 15.0
END DESCRIPTION:
XS GIS Cut Line= 3
      2661327.72      6857988.34        2659576.        6857561.
      2657509.63      6857481.45
#Sta/Elev= 30
  3196.9   371.3  3835.7  369.87  4012.7  366.16  4237.2  357.51  4476.4   348.1
  4601.4  345.53  4976.6  346.67  4981.7  346.41  4984.9  336.24  4987.4  335.74
  5009.9  336.24    5010  337.78    5020  345.97    5040  347.22  5170.1  345.33
  5579.5   346.4  5672.2  346.34  5937.2  348.66  6110.8  351.67  6140.8  349.83
  6150.8  350.45  6167.8  356.61  6172.8  354.69  6190.9  359.57    6291   357.2
  6501.1  367.97  6581.2  369.84  6831.4  370.81  6911.4   373.8  7067.9  374.62
#Mann= 7 ,-1 , 0
  3196.9     .05       0  4237.2     .12       0  4984.9     .07       0
  5009.9     .12       0  5579.5     .05       0  5672.2     .12       0
  5937.2     .05       0
Bank Sta=4984.9,5009.9
XS Rating Curve= 0 ,0
Exp/Cntr=0.3,0.1

Type RM Length L Ch R = 1 ,18687   ,1156,1156,1156
BEGIN DESCRIPTION:
Little Cottonwood Creek 14.0
END DESCRIPTION:
XS GIS Cut Line= 3
      2661480.44      6857939.71        2659876.        6857261.
      2658412.39      6856565.37
#Sta/Elev= 30
  3254.3  371.24  3952.7  369.29  4073.5  367.12  4403.5  355.59  4435.7  354.43
  4509.9  351.88  4616.3  348.31  4702.1  346.14  4768.4  343.61  4860.8  346.41
  4958.1  346.19  4962.2  336.06  4964.7  335.56  4987.2  336.06  4993.7  341.45
  4999.2  341.45    5005  345.87  5042.7  346.21  5572.4  345.03  5605.4  341.16
  5627.5  345.63  5708.7  344.06  5941.5  345.59  6207.5   357.6  6265.1  361.25
  6347.2  363.02  6424.1  367.37  6435.8   369.7  6526.1  372.25  6616.9  372.09
#Mann= 11 ,-1 , 0
  3254.3     .05       0  4403.5     .12       0  4435.7     .05       0
  4509.9     .12       0  4616.3     .05       0  4702.1     .12       0
  4860.8      .1       0  4962.2     .07       0  4987.2      .1       0
  5042.7     .12       0  6207.5     .05       0
Bank Sta=4962.2,4987.2
XS Rating Curve= 0 ,0
Exp/Cntr=0.3,0.1

Type RM Length L Ch R = 1 ,17531   ,1428,1428,1428
BEGIN DESCRIPTION:
Little Cottonwood Creek 13.0
END DESCRIPTION:
XS GIS Cut Line= 3
      2661688.77      6856891.11      2659424.93      6856314.73
      2658612.46      6856335.56
#Sta/Elev= 30
  2827.2  369.34  3332.4  362.99  3577.8  355.52  3593.7  353.25  3676.2  353.09
  3686.5  353.52  3695.4  356.29  3707.2  353.31  3717.5  352.86  3872.3  349.09
  3899.9  350.31    3905  348.61  3913.6  349.54  3986.8  346.74  4349.8  342.67
  4792.6   343.8    4939  345.43  4966.1  345.61  4974.2  335.45  4976.7  334.95
  4999.2  335.45  5007.4  336.51  5017.7  343.16    5028  345.66  5053.8  345.08
  5252.2  344.21  5482.3  349.27  5550.7  353.35  5852.4  369.39    5976  371.18
#Mann= 7 ,-1 , 0
  2827.2     .05       0  4792.6     .12       0    4939      .1       0
  4974.2     .07       0  4999.2      .1       0  5053.8     .12       0
  5550.7     .05       0
Bank Sta=4974.2,4999.2
XS Rating Curve= 0 ,0
Exp/Cntr=0.3,0.1

Type RM Length L Ch R = 1 ,16103   ,1424,1424,1424
BEGIN DESCRIPTION:
Little Cottonwood Creek 12.0
END DESCRIPTION:
XS GIS Cut Line= 4
      2662098.58      6856550.86      2660026.49      6855466.23
      2659383.26      6855439.73      2658775.99      6855961.01
#Sta/Elev= 30
  2661.2  365.41  2935.5  369.31  3315.9  367.41  3514.5  361.13    3768  349.83
  3795.7  350.87  3906.1  345.57  4492.6  341.64  4595.3  343.16  4633.8  341.57
  4738.5  341.59  4946.1  344.25  4966.7   343.3  4968.8  334.46  4971.3  333.96
  4993.8  334.46  4997.5  341.45  5002.7  341.45  5005.6  344.07  5010.6  344.36
  5322.2  343.26  5340.8  344.89  5380.8  351.51  5430.9   355.1  5488.7  357.07
  5643.8  357.97  5748.9  362.62  5904.7  365.47  6231.7  365.38  6444.1  368.97
#Mann= 5 ,-1 , 0
  2661.2     .05       0  4946.1     .12       0  4968.8     .07       0
  4993.8     .12       0  5322.2     .05       0
Bank Sta=4968.8,4993.8
XS Rating Curve= 0 ,0
Exp/Cntr=0.3,0.1

Type RM Length L Ch R = 1 ,14679   ,1929,1929,1929
BEGIN DESCRIPTION:
Mapping XS 537f2e6d
END DESCRIPTION:
XS GIS Cut Line= 4
      2662985.68      6853839.05      2660235.71      6854366.82
      2659839.87      6854415.43      2658729.91      6855809.82
#Sta/Elev= 30
  2197.6  366.76  2716.8  367.34  3293.8   363.1  3480.3  359.08  3653.4  349.21
    3857   343.6  4274.5  340.47  4325.4  336.38  4345.8   341.3  4447.6  338.91
  4987.3  343.03  5017.6  342.22  5035.3  331.76  5037.8  331.26  5060.3  331.76
    5068  341.29  5073.1  342.77    5119  341.54    5199  339.44  5225.2  346.08
  5249.3   345.5  5279.6  339.48  5445.7  340.45  5809.3  352.82  6115.2  349.64
    6357  350.87  6613.3  357.58  6919.2  359.39  7026.5  365.26  7178.8  367.38
#Mann= 5 ,-1 , 0
  2197.6     .05       0  5035.3     .03       0  5060.3     .05       0
    5119     .12       0  5225.2     .05       0
Bank Sta=5035.3,5060.3
XS Rating Curve= 0 ,0
Exp/Cntr=0.3,0.1

Type RM Length L Ch R = 1 ,12750   ,0,0,0
BEGIN DESCRIPTION:
Little Cottonwood Creek 11.0
END DESCRIPTION:
XS GIS Cut Line= 3
      2663251.28      6853759.16      2659853.76      6852741.82
      2658647.14      6855502.26
#Sta/Elev= 30
    2260  365.99  3387.1  367.87  3667.5  366.29  3852.2  360.47  4151.6  346.69
  4327.5  342.91  4646.2  339.59  4687.3   336.9  4739.5  339.42  4770.8  335.82
  4843.9  340.78  4979.6  339.95  4992.7  339.54  4998.4  330.01  5000.9  329.51
  5023.4  330.01  5031.8  339.41  5064.1  343.37    5092  338.44  5168.6  341.68
  5209.2  336.78  5355.4  338.88  6592.2  338.49  6615.6  338.76  6633.5  343.11
  6667.8  338.32  7937.5  339.88  8523.2  348.88  8752.3  358.64  8819.2     359
#Mann= 3 ,-1 , 0
    2260     .05       0  4998.4     .04       0  5023.4     .05       0
Bank Sta=4998.4,5023.4
XS Rating Curve= 0 ,0
Exp/Cntr=0.3,0.1

Chan Stop Cuts=-1
Use User Specified Reach Order=0
Composite Channel Slope=5