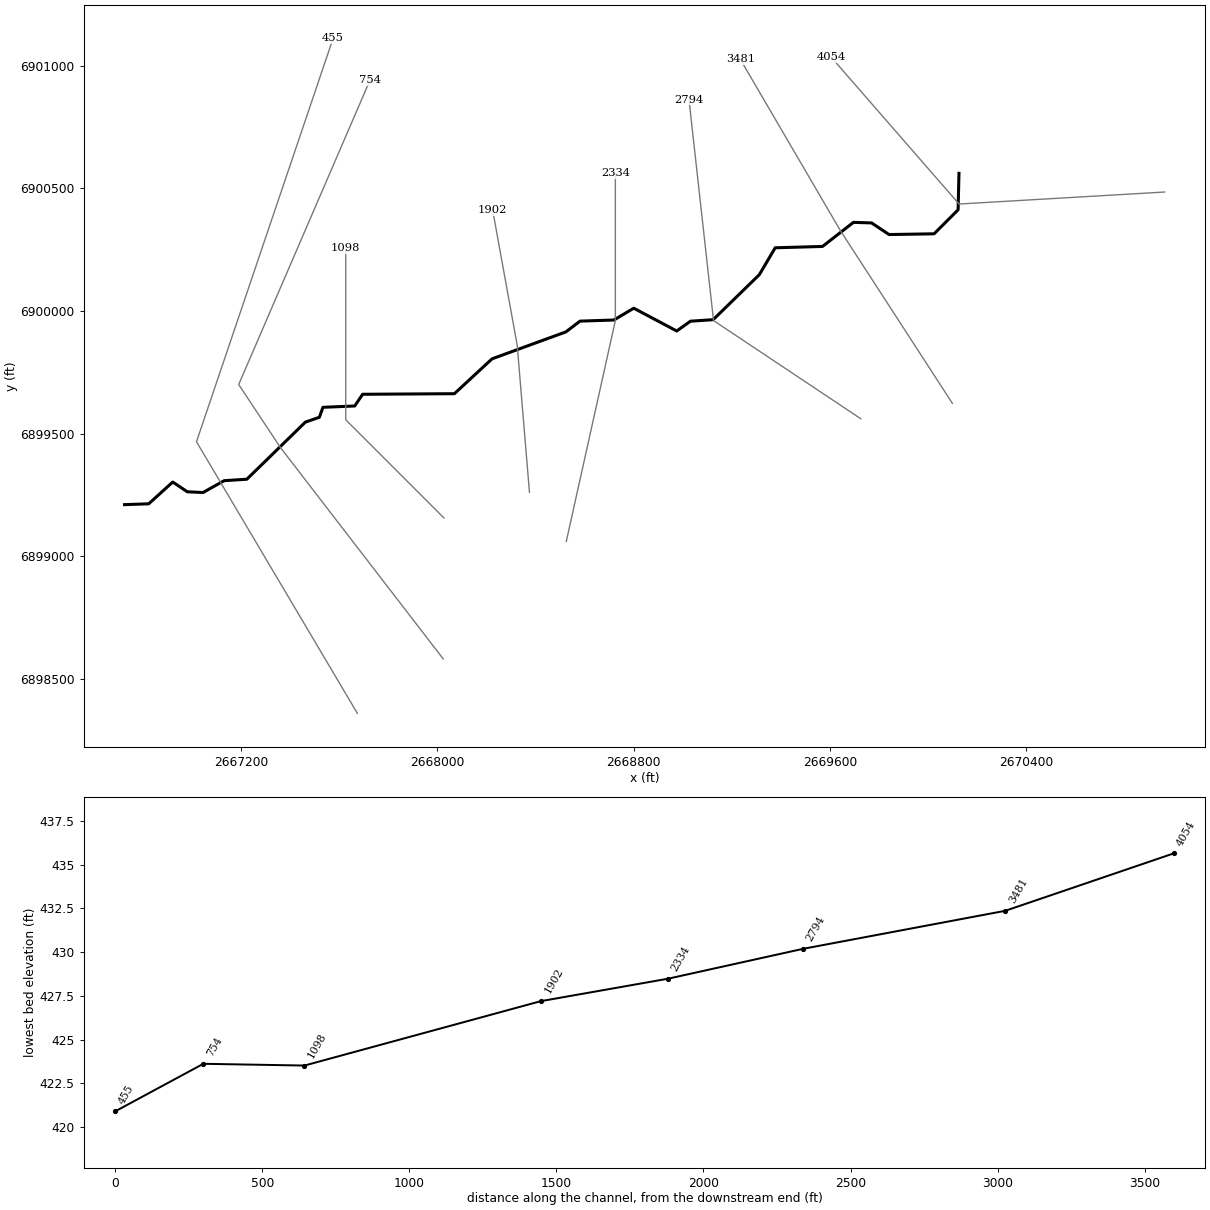
--- Little Cottonwood Creek Trib 1.prj (project) ---

Proj Title=Little Cottonwood Creek Trib 1 Base Level Engineering
Current Plan=p01
Default Exp/Contr=0.3,0.1
English Units
Geom File=g01
Flow File=f01
Plan File=p01
BEGIN DESCRIPTION:
Little Cottonwood Creek Trib 1
END DESCRIPTION:

--- Little Cottonwood Creek Trib 1.p01 (plan) ---

Plan Title=Multiple Run
Short Identifier=Multiple
Geom File=g01
Flow File=f01
Subcritical Flow
K Sum by GR= 0
Std Step Tol= 0.01
Critical Tol= 0.01
Num of Std Step Trials= 20
Max Error Tol= 0.3
Flow Tol Ratio= 0.001
Split Flow NTrial= 30
Split Flow Tol= 0.02
Split Flow Ratio= 0.02
Log Output Level= 0
Friction Slope Method= 1
Unsteady Friction Slope Method= 2
Unsteady Bridges Friction Slope Method= 1
Parabolic Critical Depth
Global Vel Dist=  1 , 1 , 1
Global Log Level= 0
CheckData=True
Encroach Param= -1, 0, 0, 0
BEGIN DESCRIPTION:
Multiple Run
END DESCRIPTION:

--- Little Cottonwood Creek Trib 1.f01 (steady flow) ---

Flow Title=Multiple
Number of Profiles=7
Profile Names=10-year,25-year,50-year,1pct_min,100-year,1pct_plu,500-year
River Rch & RM= Little Cottonwoo,Reach-1,4054
     449     593     707     418     834    1664    1162
River Rch & RM= Little Cottonwoo,Reach-1,2794
     675     914    1108     666    1328    2650    1909
Boundary for River Rch & Prof#=Little Cottonwoo,Reach-1,1
Up Type=0
Dn Type=3
Dn Slope=0.005
Boundary for River Rch & Prof#=Little Cottonwoo,Reach-1,2
Up Type=0
Dn Type=3
Dn Slope=0.005
Boundary for River Rch & Prof#=Little Cottonwoo,Reach-1,3
Up Type=0
Dn Type=3
Dn Slope=0.005
Boundary for River Rch & Prof#=Little Cottonwoo,Reach-1,4
Up Type=0
Dn Type=3
Dn Slope=0.005
Boundary for River Rch & Prof#=Little Cottonwoo,Reach-1,5
Up Type=0
Dn Type=3
Dn Slope=0.005
Boundary for River Rch & Prof#=Little Cottonwoo,Reach-1,6
Up Type=0
Dn Type=3
Dn Slope=0.005
Boundary for River Rch & Prof#=Little Cottonwoo,Reach-1,7
Up Type=0
Dn Type=3
Dn Slope=0.005

--- Little Cottonwood Creek Trib 1.g01 (geometry) ---

Geom Title=Existing Conditions

River Reach=Little Cottonwoo,Reach-1
Reach XY= 30
      2670126.00      6900561.00      2670122.51      6900412.44
      2670024.55      6900314.53      2669841.22      6900311.52
      2669770.02      6900358.84      2669696.05      6900361.21
      2669570.14      6900263.07      2669377.25      6900257.55
      2669312.36      6900147.80      2669124.50      6899964.61
      2669031.90      6899958.44      2668975.99      6899918.53
      2668801.00      6900011.41      2668720.07      6899963.30
      2668581.94      6899958.73      2668524.40      6899914.86
      2668223.70      6899805.17      2668070.15      6899663.06
      2667696.29      6899660.71      2667664.01      6899612.99
      2667534.45      6899607.59      2667520.20      6899567.06
      2667463.00      6899547.31      2667224.50      6899314.61
      2667131.98      6899308.64      2667046.04      6899260.42
      2666981.89      6899263.37      2666922.59      6899303.19
      2666824.60      6899214.41      2666726.00      6899211.00

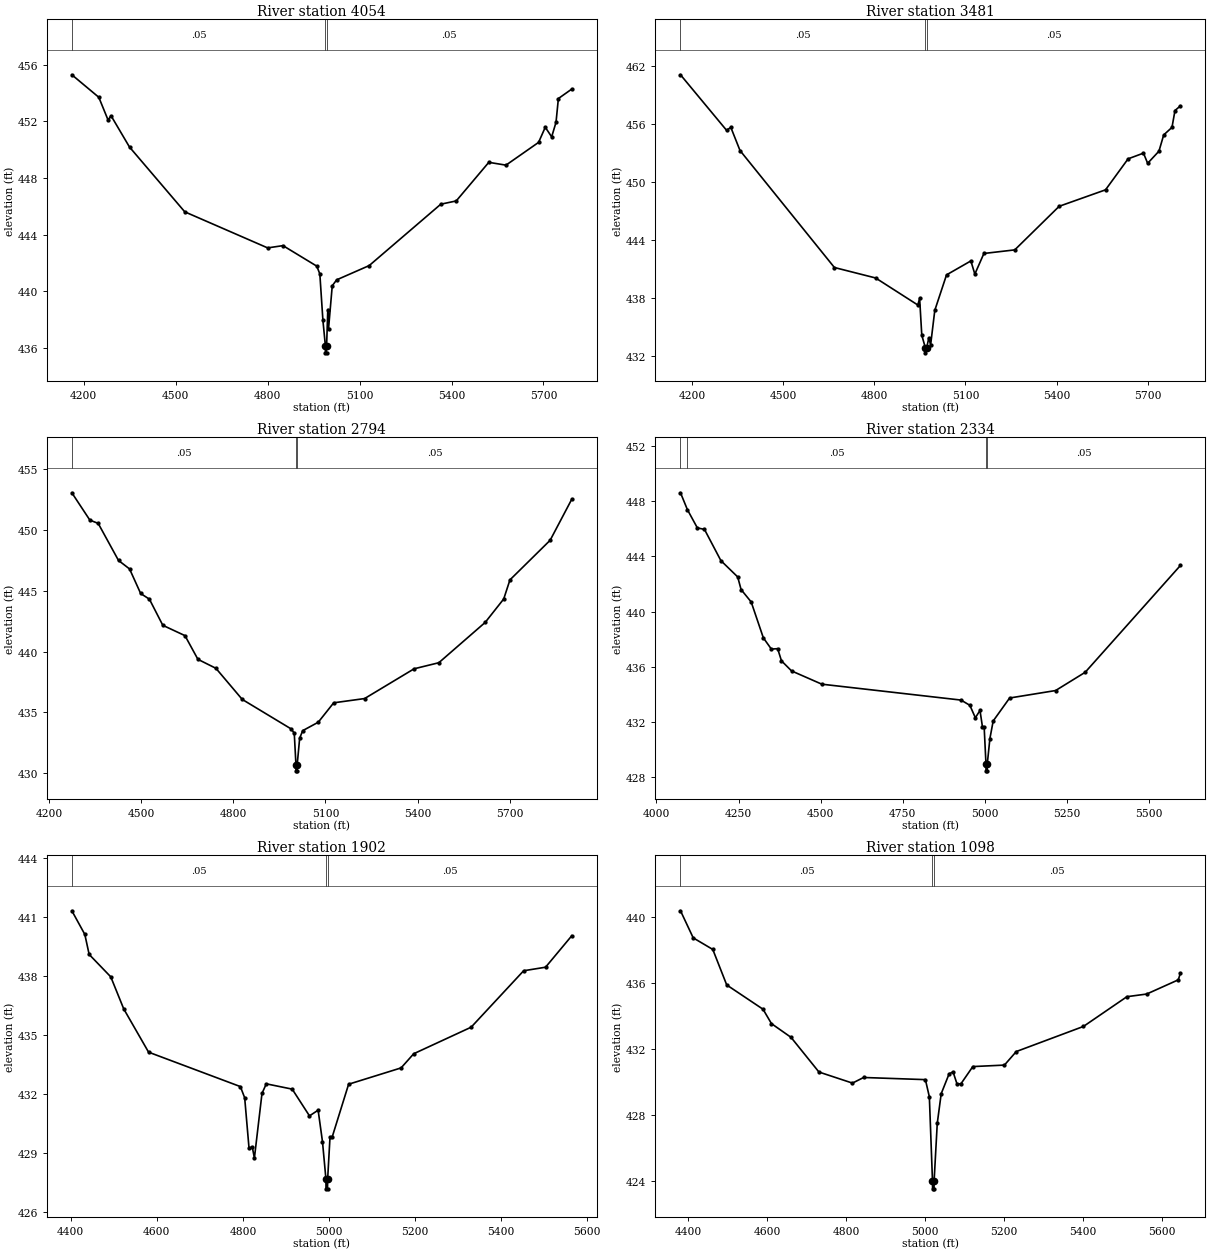
Type RM Length L Ch R = 1,4054,573,573,573
BEGIN DESCRIPTION:
Little Cottonwood Creek Trib 1 7.0
END DESCRIPTION:
XS GIS Cut Line= 3
      2670963.75      6900484.76      2670126.38      6900435.84
      2669606.11      6901033.38
#Sta/Elev= 30
  4161.2  455.30  4249.1  453.71  4279.2  452.11  4289.2  452.40  4349.3  450.19
  4529.6  445.61  4800.0  443.06  4850.1  443.22  4960.3  441.77  4970.3  441.22
  4980.3  437.95  4988.4  436.14  4988.6  435.64  4992.1  435.64  4992.4  436.14
  4996.3  438.70  4998.6  437.32  5010.8  440.38  5025.1  440.80  5131.4  441.81
  5365.0  446.15  5415.3  446.38  5521.6  449.11  5577.6  448.91  5684.0  450.52
  5705.8  451.59  5726.7  450.91  5740.9  451.94  5748.6  453.62  5792.3  454.29
#Mann=3,-1,0
  4161.2    0.05       0  4988.4    0.03       0  4992.4    0.05       0
Bank Sta=4988.4,4992.4
Exp/Cntr=0.3,0.1

Type RM Length L Ch R = 1,3481,687,687,687
BEGIN DESCRIPTION:
Little Cottonwood Creek Trib 1 6.0
END DESCRIPTION:
XS GIS Cut Line= 3
      2670099.19      6899623.62      2669642.52      6900328.04
      2669234.74      6901026.17
#Sta/Elev= 30
  4160.5  461.07  4312.3  455.34  4326.4  455.64  4356.7  453.25  4667.9  441.17
  4803.7  440.09  4942.8  437.30  4948.8  437.98  4955.9  434.18  4967.9  432.86
  4968.1  432.36  4971.9  432.86  4979.1  433.91  4985.0  433.17  4998.8  436.75
  5037.5  440.41  5117.7  441.85  5130.8  440.49  5160.7  442.62  5262.4  442.99
  5408.8  447.49  5561.6  449.19  5636.0  452.39  5686.7  452.98  5700.5  451.93
  5737.7  453.18  5753.4  454.86  5780.7  455.64  5790.6  457.38  5808.5  457.86
#Mann=3,-1,0
  4160.5    0.05       0  4967.9    0.03       0  4971.9    0.05       0
Bank Sta=4967.9,4971.9
Exp/Cntr=0.3,0.1

Type RM Length L Ch R = 1,2794,460,460,460
BEGIN DESCRIPTION:
Little Cottonwood Creek Trib 1 5.0
END DESCRIPTION:
XS GIS Cut Line= 3
      2669726.04      6899560.97      2669126.00      6899961.00
      2669026.00      6900861.00
#Sta/Elev= 30
  4274.7  453.08  4333.3  450.83  4360.4  450.56  4426.5  447.51  4462.5  446.81
  4498.6  444.79  4527.1  444.32  4570.7  442.17  4642.8  441.32  4684.9  439.37
  4743.5  438.63  4829.1  436.07  4988.3  433.64  4998.4  433.29  5003.9  430.69
  5004.2  430.19  5007.7  430.19  5007.9  430.69  5016.0  432.88  5026.0  433.50
  5076.4  434.19  5126.7  435.79  5227.3  436.14  5388.3  438.59  5468.8  439.09
  5619.7  442.41  5680.0  444.34  5700.2  445.91  5831.0  449.17  5901.4  452.55
#Mann=3,-1,0
  4274.7    0.05       0  5003.9    0.04       0  5007.9    0.05       0
Bank Sta=5003.9,5007.9
Exp/Cntr=0.3,0.1

Type RM Length L Ch R = 1,2334,432,432,432
BEGIN DESCRIPTION:
Little Cottonwood Creek Trib 1 4.0
END DESCRIPTION:
XS GIS Cut Line= 3
      2668525.99      6899060.96      2668726.00      6899961.00
      2668726.00      6900561.01
#Sta/Elev= 30
  4073.4  448.60  4094.4  447.38  4124.7  446.06  4146.4  445.95  4196.4  443.69
  4247.6  442.51  4257.8  441.60  4288.6  440.70  4325.7  438.10  4350.0  437.29
  4369.2  437.32  4380.8  436.44  4411.5  435.71  4503.7  434.75  4927.5  433.60
  4954.4  433.22  4971.1  432.32  4985.2  432.85  4992.8  431.65  4997.9  431.65
  5003.4  428.98  5003.6  428.48  5007.1  428.48  5007.4  428.98  5015.4  430.82
  5025.4  432.09  5075.4  433.75  5215.4  434.29  5305.4  435.61  5595.4  443.34
#Mann=4,-1,0
  4073.4    0.12       0  4094.4    0.05       0  5003.4    0.03       0
  5007.4    0.05       0
Bank Sta=5003.4,5007.4
Exp/Cntr=0.3,0.1

Type RM Length L Ch R = 1,1902,804,804,804
BEGIN DESCRIPTION:
Little Cottonwood Creek Trib 1 3.0
END DESCRIPTION:
XS GIS Cut Line= 3
      2668376.00      6899260.96      2668326.00      6899861.00
      2668226.01      6900410.96
#Sta/Elev= 30
  4402.7  441.34  4432.8  440.14  4442.9  439.12  4493.1  437.98  4523.2  436.35
  4580.9  434.15  4794.1  432.40  4804.1  431.83  4814.2  429.27  4821.7  429.33
  4826.7  428.77  4844.3  432.05  4854.3  432.54  4914.5  432.27  4954.6  430.91
  4974.7  431.20  4984.8  429.60  4992.8  427.70  4993.0  427.20  4996.5  427.20
  4996.8  427.70  5002.3  429.84  5007.4  429.84  5045.5  432.52  5167.4  433.35
  5196.7  434.07  5330.1  435.42  5452.0  438.29  5502.9  438.47  5563.8  440.07
#Mann=3,-1,0
  4402.7    0.05       0  4992.8    0.03       0  4996.8    0.05       0
Bank Sta=4992.8,4996.8
Exp/Cntr=0.3,0.1

Type RM Length L Ch R = 1,1098,344,344,344
BEGIN DESCRIPTION:
Little Cottonwood Creek Trib 1 2.0
END DESCRIPTION:
XS GIS Cut Line= 3
      2668027.36      6899156.86      2667627.39      6899556.83
      2667627.39      6900256.39
#Sta/Elev= 30
  4380.6  440.35  4412.8  438.71  4462.3  438.01  4497.6  435.86  4589.5  434.39
  4610.8  433.52  4660.3  432.69  4731.0  430.59  4815.8  429.92  4844.1  430.26
  5000.4  430.13  5010.4  429.09  5018.3  424.02  5018.6  423.52  5022.2  423.52
  5022.5  424.02  5030.4  427.48  5040.4  429.28  5060.4  430.48  5070.4  430.60
  5080.4  429.87  5090.4  429.88  5120.4  430.92  5200.4  431.01  5230.4  431.83
  5400.4  433.35  5510.4  435.15  5560.4  435.31  5640.4  436.17  5645.8  436.58
#Mann=3,-1,0
  4380.6    0.05       0  5018.3    0.03       0  5022.5    0.05       0
Bank Sta=5018.3,5022.5
Exp/Cntr=0.3,0.1

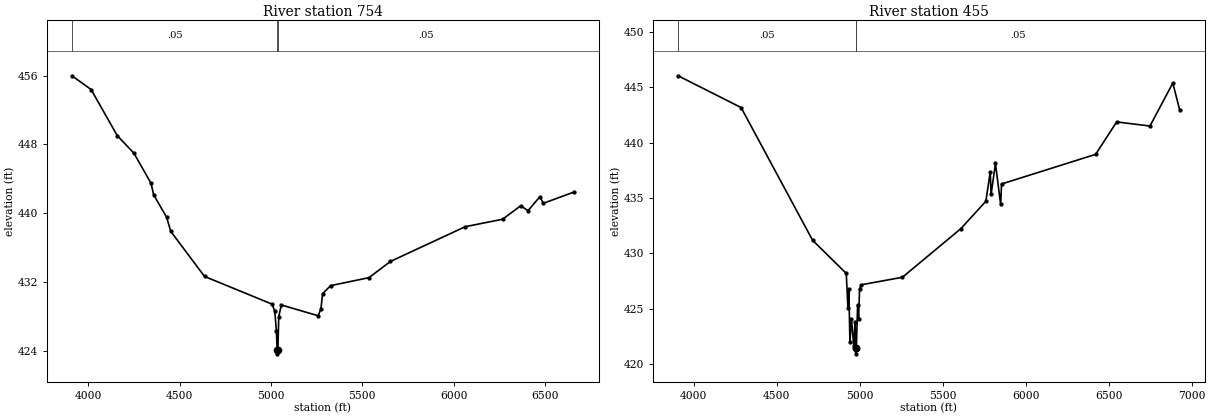
Type RM Length L Ch R = 1,754,299,299,299
BEGIN DESCRIPTION:
Mapping XS 4ae9b2a7
END DESCRIPTION:
XS GIS Cut Line= 4
      2668024.66      6898582.44      2667361.45      6899443.56
      2667191.31      6899700.51      2667726.04      6900940.11
#Sta/Elev= 30
  3911.0  455.99  4015.9  454.39  4159.1  449.02  4250.5  446.97  4343.9  443.47
  4358.4  442.12  4429.0  439.53  4451.7  437.88  4636.5  432.63  5006.8  429.40
  5020.8  428.58  5029.9  426.28  5033.8  424.12  5034.1  423.62  5038.0  424.12
  5042.8  427.96  5056.9  429.31  5258.7  428.05  5273.6  428.87  5282.6  430.62
  5326.7  431.56  5536.6  432.49  5654.2  434.38  6063.1  438.42  6267.6  439.29
  6367.1  440.86  6406.6  440.28  6472.0  441.92  6490.1  441.14  6656.1  442.44
#Mann=3,-1,0
  3911.0    0.05       0  5033.8    0.04       0  5038.0    0.05       0
Bank Sta=5033.8,5038
Exp/Cntr=0.3,0.1

Type RM Length L Ch R = 1,455,0,0,0
BEGIN DESCRIPTION:
Little Cottonwood Creek Trib 1 1.0
END DESCRIPTION:
XS GIS Cut Line= 3
      2667674.84      6898360.54      2667019.31      6899467.40
      2667575.99      6901110.97
#Sta/Elev= 30
  3906.8  446.04  4286.1  443.17  4717.0  431.17  4919.7  428.18  4929.5  425.06
  4935.3  426.77  4941.7  421.97  4951.0  424.06  4965.0  421.58  4972.4  423.79
  4976.1  421.41  4976.4  420.91  4980.4  421.41  4988.0  425.35  4993.8  424.06
  4999.8  426.76  5009.5  427.15  5257.9  427.83  5608.9  432.21  5760.7  434.70
  5786.9  437.35  5792.1  435.32  5818.3  438.12  5849.7  434.41  5855.0  436.26
  6421.7  438.94  6548.4  441.87  6749.0  441.50  6886.7  445.38  6928.5  442.92
#Mann=3,-1,0
  3906.8    0.05       0  4976.1    0.03       0  4980.4    0.05       0
Bank Sta=4976.1,4980.4
Exp/Cntr=0.3,0.1

Chan Stop Cuts=-1