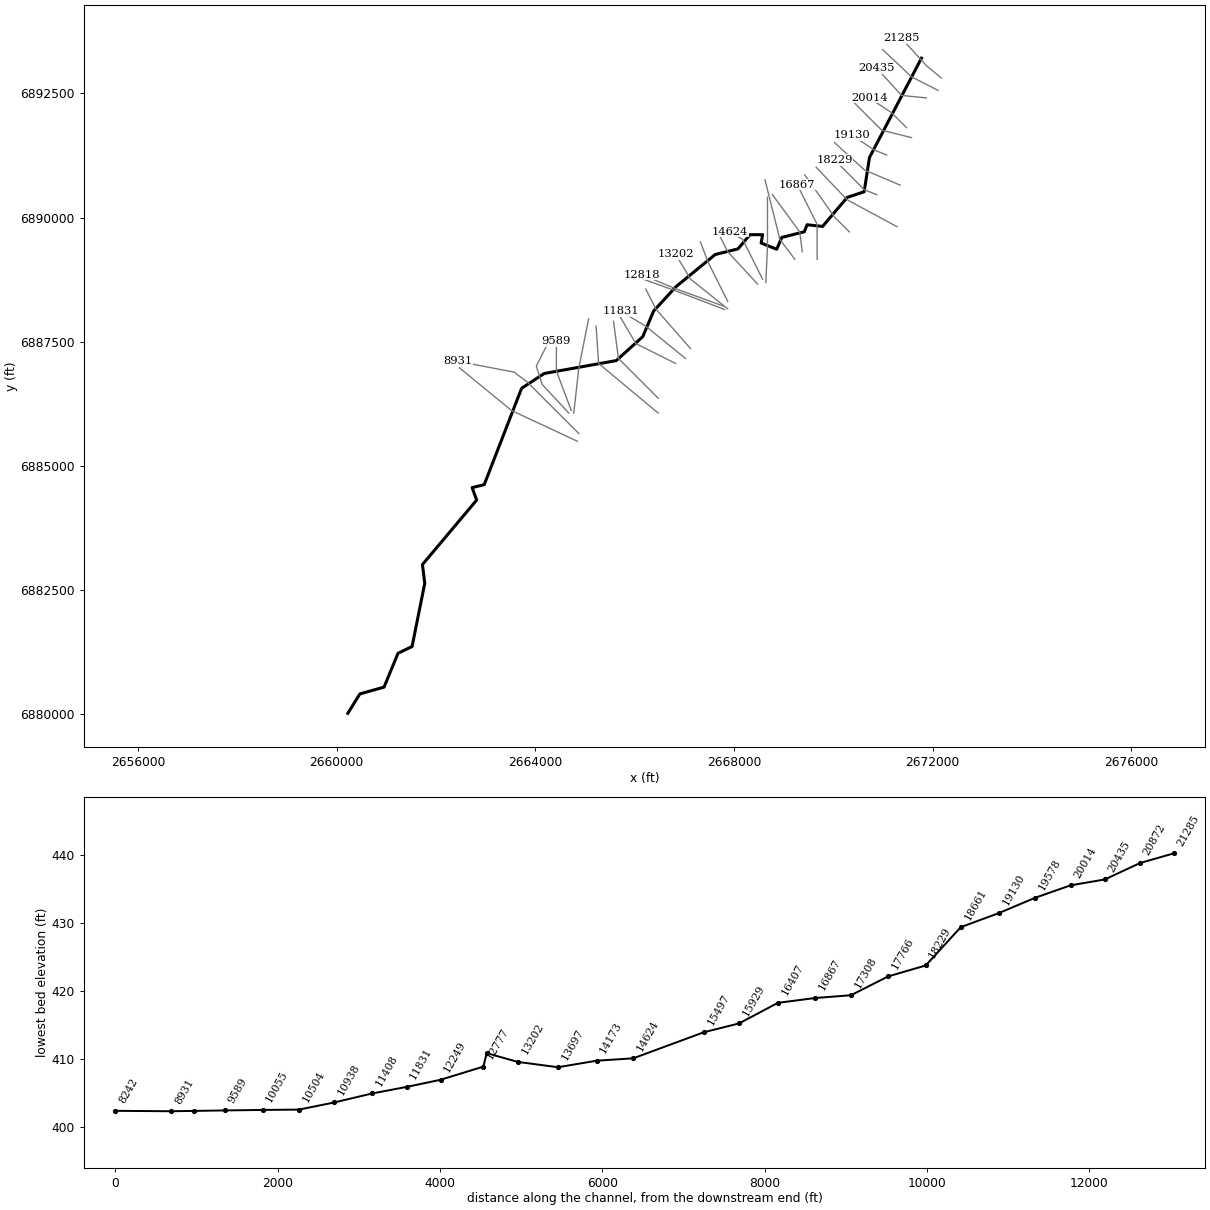
--- Little Cottonwood Creek Trib 2.prj (project) ---

Proj Title=Little Cottonwood Creek Trib 2 Base Level Engineering
Current Plan=p01
Default Exp/Contr=0.3,0.1
English Units
Geom File=g01
Flow File=f01
Plan File=p01
BEGIN DESCRIPTION:
Little Cottonwood Creek Trib 2
END DESCRIPTION:

--- Little Cottonwood Creek Trib 2.p01 (plan) ---

Plan Title=Multiple Run
Short Identifier=Multiple
Geom File=g01
Flow File=f01
Subcritical Flow
K Sum by GR= 0
Std Step Tol= 0.01
Critical Tol= 0.01
Num of Std Step Trials= 20
Max Error Tol= 0.3
Flow Tol Ratio= 0.001
Split Flow NTrial= 30
Split Flow Tol= 0.02
Split Flow Ratio= 0.02
Log Output Level= 0
Friction Slope Method= 1
Unsteady Friction Slope Method= 2
Unsteady Bridges Friction Slope Method= 1
Parabolic Critical Depth
Global Vel Dist=  1 , 1 , 1
Global Log Level= 0
CheckData=True
Encroach Param= -1, 0, 0, 0
BEGIN DESCRIPTION:
Multiple Run
END DESCRIPTION:

--- Little Cottonwood Creek Trib 2.f01 (steady flow) ---

Flow Title=Multiple
Number of Profiles=7
Profile Names=10-year,25-year,50-year,1pct_min,100-year,1pct_plu,500-year
River Rch & RM= Little Cottonwoo,Reach-1,21285
     437     577     688     407     813    1622    1133
River Rch & RM= Little Cottonwoo,Reach-1,19130
     647     875    1060     637    1270    2534    1825
River Rch & RM= Little Cottonwoo,Reach-1,16867
     897    1227    1499     906    1807    3605    2629
River Rch & RM= Little Cottonwoo,Reach-1,8242
    1360    1904    2359    1445    2884    5755    4316
River Rch & RM= Little Cottonwoo,Reach-1,5952
    1429    2000    2478    1517    3027    6041    4525
Boundary for River Rch & Prof#=Little Cottonwoo,Reach-1,1
Up Type=0
Dn Type=3
Dn Slope=0.005
Boundary for River Rch & Prof#=Little Cottonwoo,Reach-1,2
Up Type=0
Dn Type=3
Dn Slope=0.005
Boundary for River Rch & Prof#=Little Cottonwoo,Reach-1,3
Up Type=0
Dn Type=3
Dn Slope=0.005
Boundary for River Rch & Prof#=Little Cottonwoo,Reach-1,4
Up Type=0
Dn Type=3
Dn Slope=0.005
Boundary for River Rch & Prof#=Little Cottonwoo,Reach-1,5
Up Type=0
Dn Type=3
Dn Slope=0.005
Boundary for River Rch & Prof#=Little Cottonwoo,Reach-1,6
Up Type=0
Dn Type=3
Dn Slope=0.005
Boundary for River Rch & Prof#=Little Cottonwoo,Reach-1,7
Up Type=0
Dn Type=3
Dn Slope=0.005

--- Little Cottonwood Creek Trib 2.g01 (geometry) ---

Geom Title=Existing Conditions

River Reach=Little Cottonwoo,Reach-1
Reach XY= 30
      2671776.00      6893211.00      2670729.62      6891209.50
      2670622.50      6890519.46      2670281.08      6890405.96
      2669785.68      6889821.19      2669473.27      6889855.65
      2669418.03      6889713.94      2668965.82      6889600.68
      2668860.98      6889361.31      2668548.21      6889487.35
      2668578.64      6889655.24      2668323.71      6889655.16
      2668082.38      6889369.00      2667623.55      6889255.53
      2666831.61      6888605.41      2666384.14      6888117.06
      2666165.48      6887601.21      2665632.17      6887118.86
      2664181.93      6886858.75      2663726.00      6886561.00
      2662973.00      6884618.95      2662729.36      6884559.75
      2662820.94      6884308.71      2661729.47      6883009.50
      2661775.74      6882631.28      2661520.55      6881358.54
      2661236.96      6881221.42      2660956.46      6880540.48
      2660469.81      6880403.25      2660226.00      6880011.00

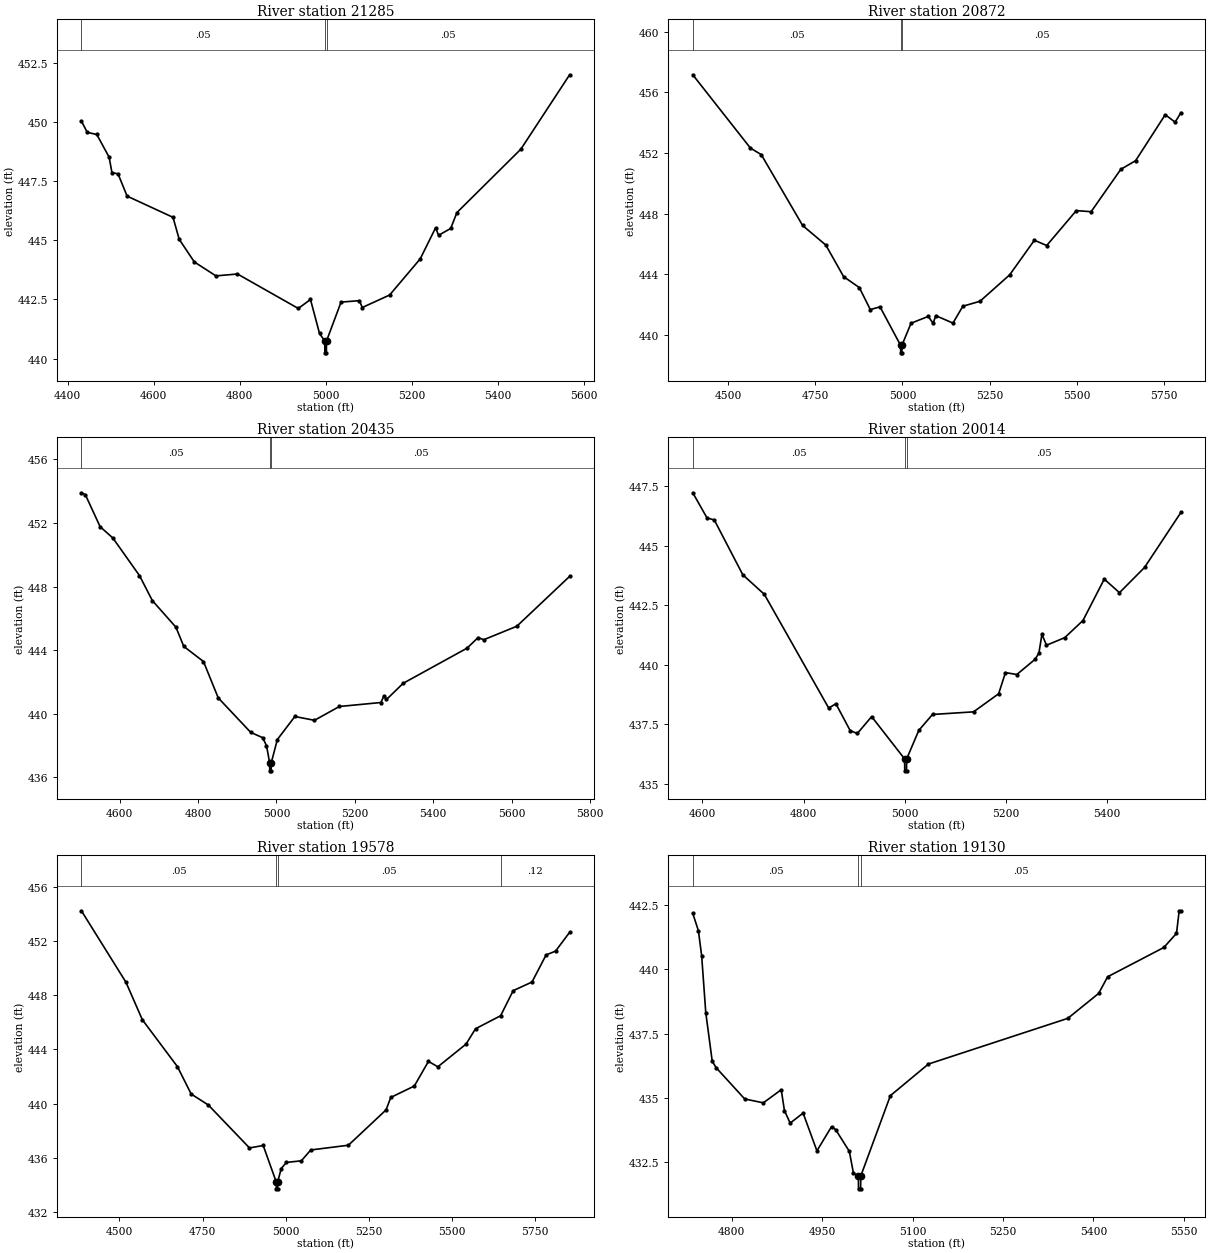
Type RM Length L Ch R = 1,21285,413,413,413
BEGIN DESCRIPTION:
Little Cottonwood Creek Trib 2 40.0
END DESCRIPTION:
XS GIS Cut Line= 3
      2672175.97      6892811.02      2671876.00      6893061.00
      2671375.99      6893611.01
#Sta/Elev= 30
  4432.0  450.06  4445.6  449.58  4467.8  449.49  4496.4  448.53  4502.9  447.88
  4517.2  447.82  4538.1  446.88  4644.8  445.98  4659.1  445.05  4694.3  444.09
  4744.4  443.50  4794.5  443.58  4935.7  442.12  4964.0  442.50  4985.0  441.06
  4997.2  440.74  4997.4  440.24  5000.9  440.24  5001.2  440.74  5035.0  442.39
  5077.6  442.45  5084.3  442.16  5147.8  442.69  5218.8  444.22  5254.6  445.54
  5261.4  445.22  5289.7  445.51  5303.9  446.18  5452.6  448.87  5565.8  452.02
#Mann=3,-1,0
  4432.0    0.05       0  4997.2    0.04       0  5001.2    0.05       0
Bank Sta=4997.2,5001.2
Exp/Cntr=0.3,0.1

Type RM Length L Ch R = 1,20872,437,437,437
BEGIN DESCRIPTION:
Mapping XS 2d6df897
END DESCRIPTION:
XS GIS Cut Line= 3
      2672110.54      6892561.75      2671574.56      6892837.34
      2670995.15      6893384.19
#Sta/Elev= 30
  4399.0  457.15  4564.3  452.32  4595.3  451.89  4713.9  447.22  4780.4  445.93
  4831.4  443.85  4876.4  443.13  4907.9  441.68  4935.7  441.86  4994.6  439.33
  4994.9  438.83  4998.4  438.83  4998.6  439.33  5024.6  440.78  5074.0  441.23
  5088.1  440.77  5095.4  441.28  5144.8  440.79  5173.1  441.90  5222.4  442.23
  5307.4  443.97  5378.2  446.25  5413.4  445.90  5498.3  448.20  5540.8  448.13
  5625.8  450.92  5668.3  451.49  5753.2  454.52  5781.5  454.03  5798.4  454.66
#Mann=3,-1,0
  4399.0    0.05       0  4994.6    0.04       0  4998.6    0.05       0
Bank Sta=4994.6,4998.6
Exp/Cntr=0.3,0.1

Type RM Length L Ch R = 1,20435,421,421,421
BEGIN DESCRIPTION:
Little Cottonwood Creek Trib 2 39.0
END DESCRIPTION:
XS GIS Cut Line= 3
      2671876.00      6892411.00      2671376.00      6892461.00
      2670876.00      6893011.00
#Sta/Elev= 30
  4502.3  453.90  4512.4  453.78  4550.0  451.77  4582.7  451.05  4650.5  448.69
  4683.2  447.12  4743.5  445.44  4763.6  444.23  4813.8  443.28  4851.5  440.99
  4934.4  438.82  4964.6  438.49  4974.6  437.99  4982.7  436.90  4982.9  436.40
  4986.4  436.40  4986.7  436.90  5002.3  438.37  5047.0  439.82  5097.0  439.58
  5160.6  440.45  5266.6  440.70  5274.1  441.11  5280.8  440.89  5323.4  441.91
  5486.3  444.12  5514.6  444.79  5528.8  444.65  5613.3  445.50  5748.1  448.64
#Mann=3,-1,0
  4502.3    0.05       0  4982.7    0.04       0  4986.7    0.05       0
Bank Sta=4982.7,4986.7
Exp/Cntr=0.3,0.1

Type RM Length L Ch R = 1,20014,436,436,436
BEGIN DESCRIPTION:
Little Cottonwood Creek Trib 2 38.0
END DESCRIPTION:
XS GIS Cut Line= 3
      2671476.03      6891810.97      2671176.00      6892111.00
      2670726.04      6892410.98
#Sta/Elev= 30
  4580.8  447.23  4609.1  446.17  4623.3  446.09  4679.8  443.78  4722.3  442.96
  4849.5  438.18  4863.7  438.36  4892.0  437.23  4906.1  437.11  4934.4  437.82
  4999.6  436.04  4999.8  435.54  5003.3  435.54  5003.6  436.04  5027.6  437.24
  5054.7  437.91  5135.8  438.02  5185.4  438.78  5198.9  439.67  5221.4  439.59
  5257.5  440.23  5265.0  440.49  5271.0  441.28  5280.0  440.82  5316.1  441.14
  5352.1  441.86  5394.2  443.60  5424.3  443.03  5473.8  444.09  5545.9  446.41
#Mann=3,-1,0
  4580.8    0.05       0  4999.6    0.04       0  5003.6    0.05       0
Bank Sta=4999.6,5003.6
Exp/Cntr=0.3,0.1

Type RM Length L Ch R = 1,19578,448,448,448
BEGIN DESCRIPTION:
Little Cottonwood Creek Trib 2 37.0
END DESCRIPTION:
XS GIS Cut Line= 3
      2671576.03      6891610.99      2670976.00      6891761.00
      2670376.02      6892360.98
#Sta/Elev= 30
  4386.1  454.24  4520.1  448.96  4569.1  446.20  4674.7  442.73  4716.0  440.71
  4767.5  439.90  4891.2  436.73  4932.4  436.91  4971.7  434.21  4971.9  433.71
  4975.4  433.71  4975.7  434.21  4986.6  435.21  5002.0  435.66  5047.0  435.78
  5075.3  436.58  5188.4  436.93  5301.6  439.54  5315.7  440.46  5386.4  441.30
  5428.9  443.12  5457.1  442.72  5542.0  444.40  5570.3  445.53  5645.7  446.49
  5683.4  448.34  5740.0  448.98  5782.4  450.98  5810.7  451.26  5853.1  452.65
#Mann=4,-1,0
  4386.1    0.05       0  4971.7    0.04       0  4975.7    0.05       0
  5645.7    0.12       0
Bank Sta=4971.7,4975.7
Exp/Cntr=0.3,0.1

Type RM Length L Ch R = 1,19130,469,469,469
BEGIN DESCRIPTION:
Little Cottonwood Creek Trib 2 36.0
END DESCRIPTION:
XS GIS Cut Line= 3
      2671076.01      6891261.00      2670826.00      6891361.00
      2670376.00      6891661.00
#Sta/Elev= 30
  4735.3  442.18  4744.7  441.50  4750.1  440.52  4756.9  438.31  4767.6  436.42
  4774.4  436.16  4821.5  434.95  4852.4  434.80  4882.1  435.31  4887.4  434.50
  4896.9  434.01  4918.4  434.40  4941.3  432.93  4965.5  433.87  4972.3  433.76
  4995.1  432.91  5001.9  432.06  5010.1  431.95  5010.3  431.45  5013.8  431.45
  5014.1  431.95  5063.2  435.08  5126.3  436.31  5357.6  438.09  5408.7  439.06
  5423.7  439.71  5516.9  440.85  5537.9  441.40  5542.4  442.28  5545.4  442.28
#Mann=3,-1,0
  4735.3    0.05       0  5010.1    0.04       0  5014.1    0.05       0
Bank Sta=5010.1,5014.1
Exp/Cntr=0.3,0.1

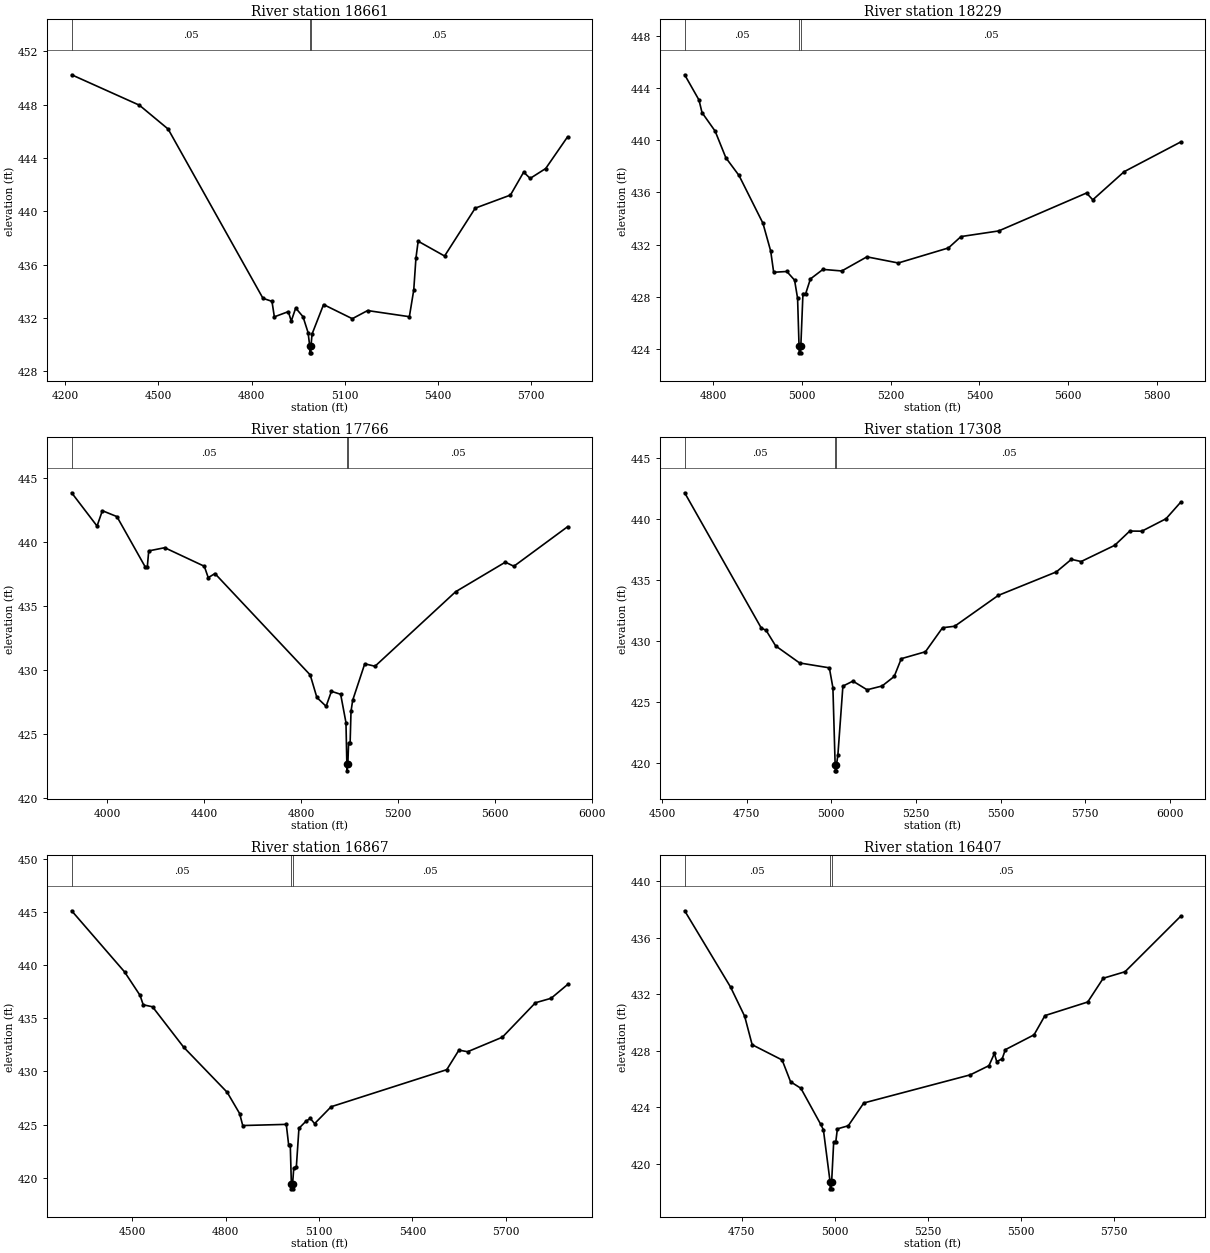
Type RM Length L Ch R = 1,18661,432,432,432
BEGIN DESCRIPTION:
Little Cottonwood Creek Trib 2 35.0
END DESCRIPTION:
XS GIS Cut Line= 3
      2671346.66      6890654.19      2670626.00      6890961.00
      2670026.00      6891511.00
#Sta/Elev= 30
  4220.8  450.23  4438.9  447.95  4531.5  446.16  4836.9  433.47  4865.9  433.24
  4873.6  432.08  4918.6  432.47  4928.0  431.76  4942.3  432.74  4965.9  432.09
  4982.3  430.89  4987.5  429.88  4987.8  429.38  4991.3  429.38  4991.5  429.88
  4995.0  430.79  5032.1  433.00  5124.6  431.94  5173.9  432.55  5308.4  432.09
  5322.5  434.09  5329.6  436.49  5336.7  437.75  5421.8  436.64  5520.5  440.23
  5633.9  441.21  5676.5  442.93  5697.4  442.46  5747.4  443.20  5818.0  445.58
#Mann=3,-1,0
  4220.8    0.05       0  4987.5    0.04       0  4991.5    0.05       0
Bank Sta=4987.5,4991.5
Exp/Cntr=0.3,0.1

Type RM Length L Ch R = 1,18229,463,463,463
BEGIN DESCRIPTION:
Little Cottonwood Creek Trib 2 34.0
END DESCRIPTION:
XS GIS Cut Line= 3
      2670876.01      6890461.00      2670626.00      6890561.00
      2670026.00      6891161.00
#Sta/Elev= 30
  4735.6  445.00  4767.9  443.07  4774.7  442.11  4804.3  440.69  4828.5  438.65
  4858.1  437.30  4912.0  433.65  4929.5  431.52  4936.2  429.90  4965.8  429.96
  4983.3  429.30  4990.1  427.91  4993.4  424.24  4993.7  423.74  4997.2  423.74
  4997.4  424.24  5002.2  428.27  5008.4  428.27  5019.0  429.39  5047.3  430.12
  5089.7  430.00  5146.3  431.08  5217.0  430.61  5330.1  431.76  5358.4  432.63
  5443.3  433.06  5641.3  435.96  5655.4  435.44  5726.1  437.59  5853.4  439.86
#Mann=3,-1,0
  4735.6    0.05       0  4993.4    0.04       0  4997.4    0.05       0
Bank Sta=4993.4,4997.4
Exp/Cntr=0.3,0.1

Type RM Length L Ch R = 1,17766,458,458,458
BEGIN DESCRIPTION:
Little Cottonwood Creek Trib 2 33.0
END DESCRIPTION:
XS GIS Cut Line= 3
      2671283.78      6889816.49      2670276.00      6890361.00
      2669656.17      6891014.41
#Sta/Elev= 30
  3854.3  443.85  3959.1  441.25  3981.0  442.45  4041.0  441.99  4158.7  438.03
  4166.6  438.09  4172.3  439.31  4238.2  439.56  4401.6  438.11  4417.8  437.22
  4445.4  437.54  4838.5  429.62  4866.0  427.86  4904.1  427.17  4926.0  428.34
  4964.1  428.11  4986.0  425.90  4989.7  422.63  4989.9  422.13  4993.7  422.63
  4996.9  424.33  5003.2  424.33  5006.8  426.77  5013.7  427.64  5063.5  430.49
  5105.9  430.30  5438.4  436.12  5643.5  438.43  5678.7  438.11  5900.4  441.20
#Mann=3,-1,0
  3854.3    0.05       0  4989.7    0.04       0  4993.7    0.05       0
Bank Sta=4989.7,4993.7
Exp/Cntr=0.3,0.1

Type RM Length L Ch R = 1,17308,441,441,441
BEGIN DESCRIPTION:
Little Cottonwood Creek Trib 2 32.0
END DESCRIPTION:
XS GIS Cut Line= 3
      2670325.99      6889711.01      2670026.00      6890011.00
      2669425.99      6890861.02
#Sta/Elev= 30
  4567.1  442.17  4793.4  431.07  4807.5  430.89  4835.8  429.61  4906.5  428.21
  4994.4  427.81  5004.9  426.18  5011.5  419.86  5011.8  419.36  5015.3  419.36
  5015.5  419.86  5019.6  420.66  5034.4  426.31  5064.0  426.72  5105.8  426.01
  5150.2  426.32  5185.9  427.10  5206.8  428.56  5278.2  429.13  5328.7  431.10
  5364.4  431.22  5493.2  433.75  5664.8  435.68  5709.2  436.71  5738.0  436.53
  5837.2  437.86  5881.6  439.03  5917.3  439.02  5988.7  440.04  6031.8  441.39
#Mann=3,-1,0
  4567.1    0.05       0  5011.5    0.04       0  5015.5    0.05       0
Bank Sta=5011.5,5015.5
Exp/Cntr=0.3,0.1

Type RM Length L Ch R = 1,16867,460,460,460
BEGIN DESCRIPTION:
Little Cottonwood Creek Trib 2 31.0
END DESCRIPTION:
XS GIS Cut Line= 3
      2669676.00      6889161.00      2669676.00      6889861.00
      2669276.01      6890660.98
#Sta/Elev= 30
  4304.6  445.13  4474.6  439.38  4524.6  437.16  4534.6  436.28  4564.6  436.09
  4664.6  432.29  4804.6  428.04  4844.6  426.04  4854.6  424.91  4994.6  425.02
  5002.1  423.12  5007.4  423.12  5010.9  419.45  5011.2  418.95  5014.7  418.95
  5015.0  419.45  5018.6  420.90  5027.0  421.04  5035.3  424.65  5057.7  425.31
  5071.7  425.58  5085.7  425.09  5138.8  426.68  5510.5  430.17  5549.6  432.01
  5577.6  431.86  5689.4  433.23  5795.6  436.47  5845.9  436.89  5899.0  438.19
#Mann=3,-1,0
  4304.6    0.05       0  5010.9    0.04       0  5015.0    0.05       0
Bank Sta=5010.9,5015
Exp/Cntr=0.3,0.1

Type RM Length L Ch R = 1,16407,478,478,478
BEGIN DESCRIPTION:
Little Cottonwood Creek Trib 2 30.0
END DESCRIPTION:
XS GIS Cut Line= 3
      2669376.00      6889310.99      2669326.00      6889711.00
      2668775.99      6890461.02
#Sta/Elev= 30
  4596.9  437.90  4720.4  432.50  4758.2  430.44  4778.3  428.43  4858.9  427.35
  4881.6  425.81  4909.3  425.35  4962.2  422.82  4969.8  422.42  4987.8  418.74
  4988.1  418.24  4991.7  418.24  4992.0  418.74  4997.5  421.55  5003.1  421.55
  5007.4  422.48  5036.7  422.70  5078.4  424.31  5364.7  426.30  5414.9  426.95
  5429.5  427.81  5435.7  427.24  5450.4  427.43  5458.9  428.08  5536.1  429.13
  5565.4  430.49  5680.4  431.45  5722.1  433.13  5780.7  433.59  5930.1  437.51
#Mann=3,-1,0
  4596.9    0.05       0  4987.8    0.04       0  4992.0    0.05       0
Bank Sta=4987.8,4992
Exp/Cntr=0.3,0.1

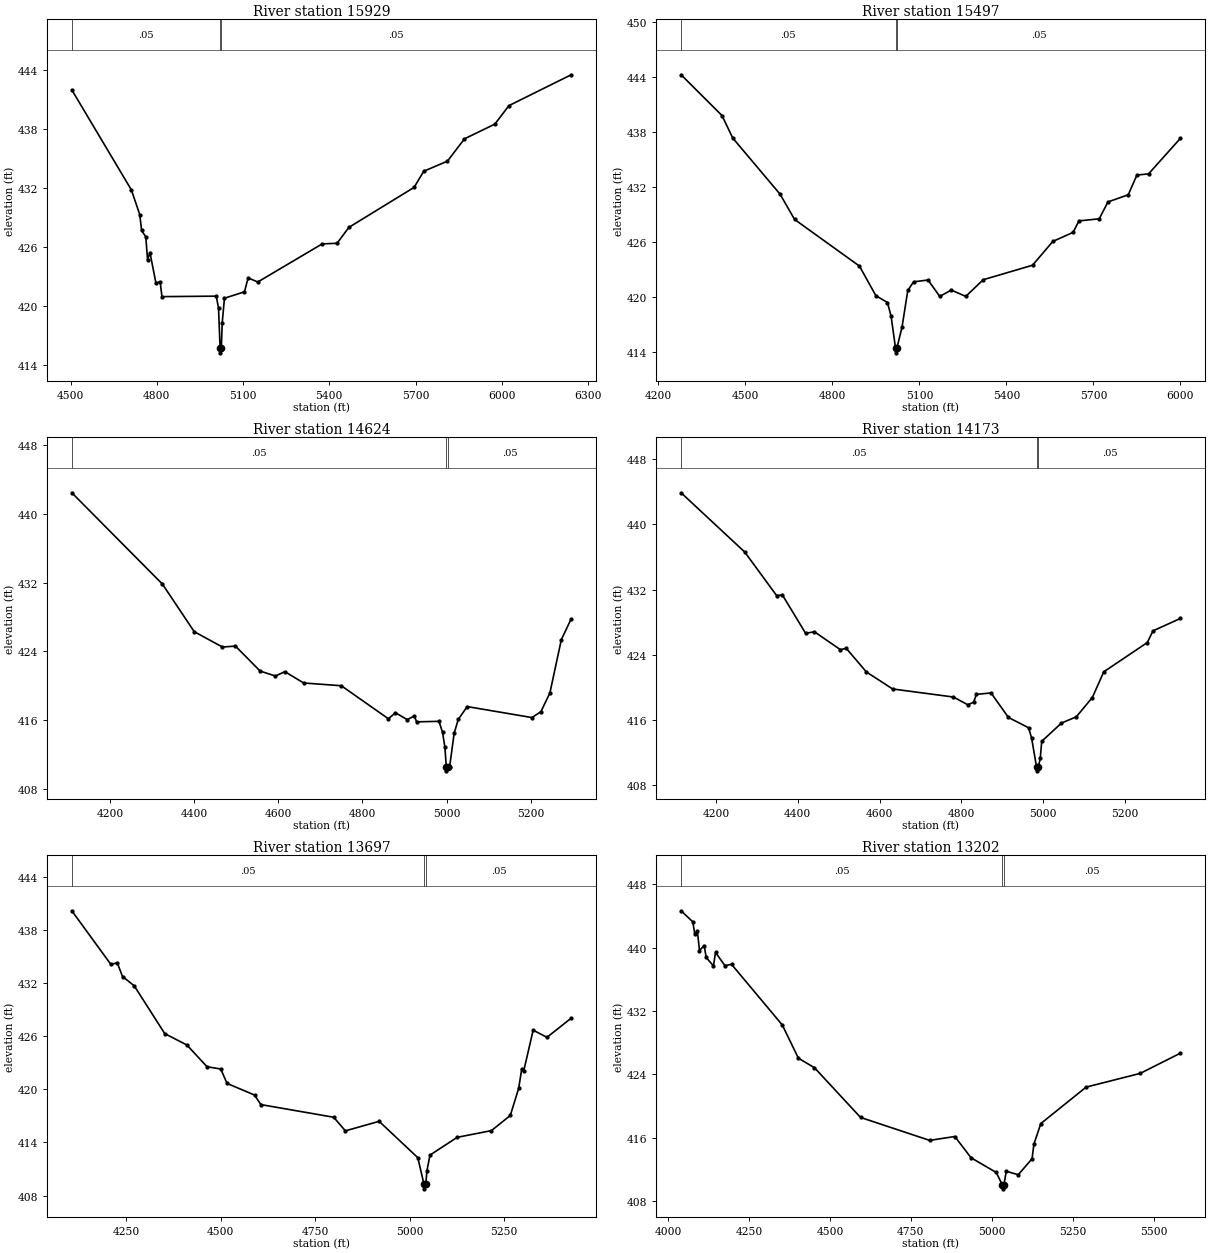
Type RM Length L Ch R = 1,15929,432,432,432
BEGIN DESCRIPTION:
Little Cottonwood Creek Trib 2 29.0
END DESCRIPTION:
XS GIS Cut Line= 3
      2669225.97      6889161.04      2668926.00      6889561.00
      2668626.00      6890761.02
#Sta/Elev= 30
  4504.5  441.97  4711.7  431.79  4740.9  429.27  4747.2  427.67  4761.7  427.02
  4768.0  424.69  4776.3  425.40  4797.2  422.30  4811.7  422.45  4818.0  420.93
  5007.0  420.98  5014.8  419.75  5020.3  415.71  5020.7  415.21  5024.6  415.71
  5027.6  418.26  5035.4  420.77  5105.0  421.42  5117.8  422.84  5151.3  422.42
  5375.5  426.30  5427.1  426.36  5468.3  427.98  5695.1  432.05  5728.6  433.69
  5811.0  434.72  5870.3  436.99  5976.0  438.49  6024.9  440.37  6241.4  443.51
#Mann=3,-1,0
  4504.5    0.05       0  5020.3    0.04       0  5024.6    0.05       0
Bank Sta=5020.3,5024.6
Exp/Cntr=0.3,0.1

Type RM Length L Ch R = 1,15497,873,873,873
BEGIN DESCRIPTION:
Little Cottonwood Creek Trib 2 28.0
END DESCRIPTION:
XS GIS Cut Line= 3
      2668642.70      6888690.22      2668676.00      6889411.00
      2668676.00      6890410.96
#Sta/Elev= 30
  4278.5  444.27  4419.4  439.82  4456.4  437.37  4619.6  431.24  4669.7  428.48
  4893.3  423.39  4950.0  420.16  4990.0  419.41  5002.5  417.90  5017.8  414.42
  5018.2  413.92  5022.3  414.42  5040.0  416.70  5060.0  420.73  5080.0  421.67
  5130.0  421.87  5170.0  420.08  5210.0  420.77  5260.0  420.08  5320.0  421.90
  5490.0  423.48  5560.0  426.08  5630.0  427.07  5650.0  428.32  5720.0  428.55
  5750.0  430.39  5820.0  431.17  5850.0  433.33  5890.0  433.45  6000.0  437.34
#Mann=3,-1,0
  4278.5    0.05       0  5017.8    0.04       0  5022.3    0.05       0
Bank Sta=5017.8,5022.3
Exp/Cntr=0.3,0.1

Type RM Length L Ch R = 1,14624,451,451,451
BEGIN DESCRIPTION:
Little Cottonwood Creek Trib 2 27.0
END DESCRIPTION:
XS GIS Cut Line= 3
      2668576.02      6888760.96      2668176.00      6889561.00
      2667926.01      6889710.99
#Sta/Elev= 30
  4109.7  442.48  4325.0  431.83  4400.4  426.29  4467.5  424.50  4498.3  424.61
  4557.0  421.70  4593.3  421.12  4615.7  421.63  4660.4  420.31  4749.8  419.99
  4861.6  416.14  4878.4  416.84  4906.3  416.04  4923.1  416.46  4928.7  415.78
  4981.8  415.84  4990.2  414.55  4995.8  412.82  4999.1  410.57  4999.5  410.07
  5003.7  410.57  5007.1  410.57  5017.8  414.44  5027.5  416.06  5048.9  417.56
  5202.4  416.28  5223.8  416.96  5245.2  419.15  5272.4  425.37  5295.7  427.78
#Mann=3,-1,0
  4109.7    0.05       0  4999.1    0.04       0  5003.7    0.05       0
Bank Sta=4999.1,5003.7
Exp/Cntr=0.3,0.1

Type RM Length L Ch R = 1,14173,476,476,476
BEGIN DESCRIPTION:
Little Cottonwood Creek Trib 2 26.0
END DESCRIPTION:
XS GIS Cut Line= 3
      2668475.97      6888661.03      2667876.00      6889311.00
      2667725.98      6889611.04
#Sta/Elev= 30
  4115.1  443.89  4270.7  436.60  4348.4  431.26  4362.6  431.33  4419.3  426.62
  4440.8  426.81  4504.3  424.61  4518.5  424.78  4567.8  421.87  4631.9  419.78
  4780.5  418.79  4815.6  417.84  4829.8  418.15  4836.6  419.12  4872.3  419.29
  4914.9  416.28  4964.2  415.01  4971.6  413.71  4983.4  410.22  4983.9  409.72
  4988.1  410.22  4992.6  411.27  4996.2  413.35  5044.4  415.59  5080.7  416.36
  5119.8  418.73  5147.8  421.89  5254.0  425.48  5268.0  426.92  5335.1  428.45
#Mann=3,-1,0
  4115.1    0.05       0  4983.4    0.04       0  4988.1    0.05       0
Bank Sta=4983.4,4988.1
Exp/Cntr=0.3,0.1

Type RM Length L Ch R = 1,13697,495,495,495
BEGIN DESCRIPTION:
Little Cottonwood Creek Trib 2 25.0
END DESCRIPTION:
XS GIS Cut Line= 3
      2667876.02      6888310.96      2667476.00      6889111.00
      2667325.99      6889511.02
#Sta/Elev= 30
  4105.5  440.18  4209.0  434.11  4225.7  434.31  4239.7  432.75  4270.5  431.71
  4351.5  426.30  4410.2  425.01  4463.3  422.56  4499.7  422.30  4516.4  420.67
  4589.1  419.36  4605.9  418.28  4798.7  416.85  4829.5  415.31  4918.9  416.39
  5021.3  412.28  5037.7  409.26  5038.2  408.76  5042.4  409.26  5045.4  410.78
  5053.4  412.57  5125.5  414.58  5216.2  415.34  5266.1  417.05  5288.3  420.12
  5296.3  422.28  5301.7  422.09  5326.6  426.69  5363.1  425.88  5427.2  428.04
#Mann=3,-1,0
  4105.5    0.05       0  5037.7    0.04       0  5042.4    0.05       0
Bank Sta=5037.7,5042.4
Exp/Cntr=0.3,0.1

Type RM Length L Ch R = 1,13202,384,384,384
BEGIN DESCRIPTION:
Little Cottonwood Creek Trib 2 24.0
END DESCRIPTION:
XS GIS Cut Line= 3
      2667875.96      6888161.03      2667126.00      6888761.00
      2666826.01      6889260.99
#Sta/Elev= 30
  4039.8  444.66  4075.8  443.27  4082.2  441.71  4090.2  442.08  4096.6  439.64
  4111.0  440.27  4117.4  438.76  4139.8  437.69  4146.2  439.40  4175.0  437.74
  4195.8  437.89  4352.7  430.23  4402.3  426.04  4452.0  424.84  4594.4  418.56
  4808.1  415.66  4885.8  416.15  4936.2  413.46  5013.8  411.61  5032.8  410.04
  5033.4  409.54  5037.6  410.04  5044.9  411.76  5081.9  411.32  5124.6  413.34
  5130.4  415.20  5151.8  417.79  5291.8  422.39  5458.9  424.12  5583.3  426.68
#Mann=3,-1,0
  4039.8    0.05       0  5032.8    0.04       0  5037.6    0.05       0
Bank Sta=5032.8,5037.6
Exp/Cntr=0.3,0.1

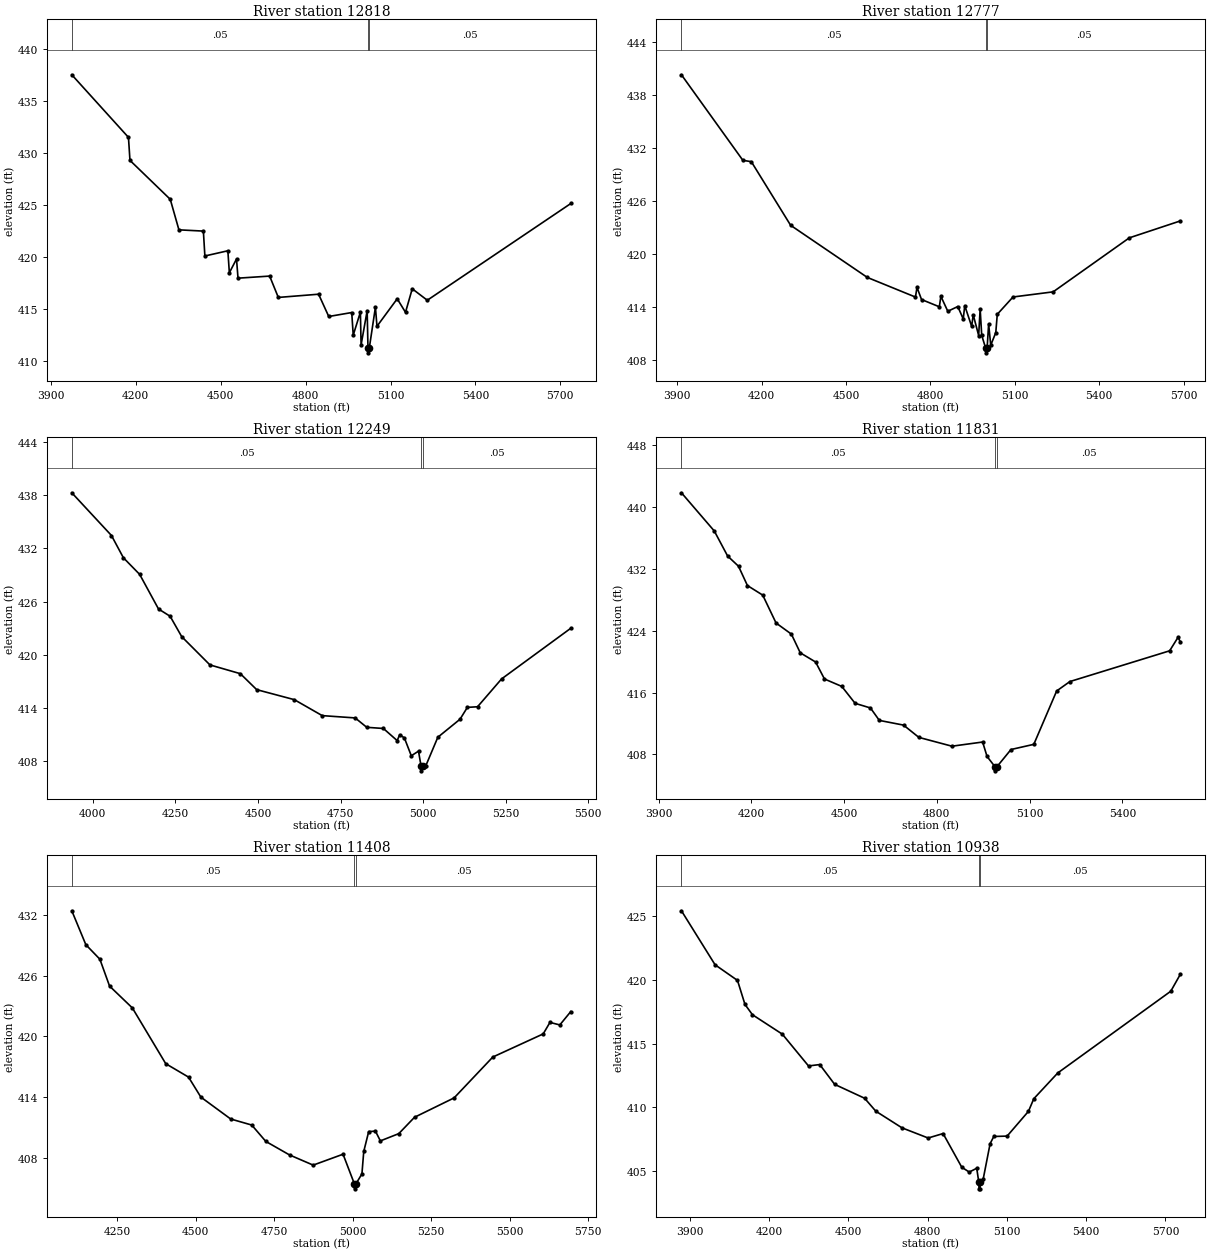
Type RM Length L Ch R = 1,12818,41,41,41
BEGIN DESCRIPTION:
Mapping XS 6cf819e0
END DESCRIPTION:
XS GIS Cut Line= 3
      2667787.70      6888217.10      2666826.30      6888566.50
      2666142.68      6888850.80
#Sta/Elev= 30
  3973.9  437.53  4174.1  431.52  4179.4  429.31  4321.8  425.57  4352.4  422.64
  4438.8  422.52  4444.1  420.13  4525.3  420.63  4530.6  418.52  4555.9  419.84
  4561.2  418.00  4673.0  418.20  4703.6  416.15  4845.9  416.46  4881.8  414.32
  4963.0  414.70  4968.3  412.53  4993.6  414.74  4996.1  411.59  5017.5  414.88
  5020.4  411.33  5021.0  410.83  5025.3  411.33  5046.7  415.21  5052.2  413.38
  5123.7  416.02  5153.0  414.72  5176.8  416.98  5230.0  415.88  5737.2  425.17
#Mann=3,-1,0
  3973.9    0.05       0  5020.4    0.04       0  5025.3    0.05       0
Bank Sta=5020.4,5025.3
Exp/Cntr=0.3,0.1

Type RM Length L Ch R = 1,12777,528,528,528
BEGIN DESCRIPTION:
Little Cottonwood Creek Trib 2 23.0
END DESCRIPTION:
XS GIS Cut Line= 3
      2667813.75      6888147.65      2666799.66      6888534.30
      2666151.40      6888768.32
#Sta/Elev= 30
  3914.7  440.31  4133.2  430.63  4163.2  430.48  4303.0  423.28  4575.8  417.38
  4746.9  415.16  4752.3  416.26  4768.5  414.88  4831.8  414.06  4837.2  415.25
  4861.9  413.55  4897.4  414.09  4916.8  412.68  4922.1  414.19  4946.8  411.84
  4952.2  413.16  4971.6  410.81  4976.9  413.81  4982.5  410.82  4996.8  409.35
  4997.4  408.85  5001.7  409.35  5007.1  412.13  5014.5  409.71  5032.5  411.14
  5037.8  413.21  5093.8  415.17  5236.5  415.75  5507.3  421.86  5689.2  423.78
#Mann=3,-1,0
  3914.7    0.05       0  4996.8    0.04       0  5001.7    0.05       0
Bank Sta=4996.8,5001.7
Exp/Cntr=0.3,0.1

Type RM Length L Ch R = 1,12249,418,418,418
BEGIN DESCRIPTION:
Little Cottonwood Creek Trib 2 22.0
END DESCRIPTION:
XS GIS Cut Line= 3
      2667125.97      6887361.03      2666426.00      6888161.00
      2666225.99      6888561.02
#Sta/Elev= 30
  3936.8  438.28  4056.8  433.46  4092.9  430.95  4142.2  429.07  4199.2  425.17
  4234.3  424.35  4269.4  422.05  4354.8  418.86  4446.9  417.87  4496.3  416.07
  4610.2  414.94  4694.6  413.14  4794.3  412.88  4829.4  411.82  4879.7  411.69
  4921.5  410.32  4929.1  410.99  4943.3  410.62  4964.2  408.61  4986.0  409.13
  4993.9  407.41  4994.6  406.91  4998.9  407.41  5008.2  407.49  5044.5  410.70
  5111.6  412.73  5133.9  414.07  5164.7  414.14  5237.4  417.28  5447.0  423.00
#Mann=3,-1,0
  3936.8    0.05       0  4993.9    0.04       0  4998.9    0.05       0
Bank Sta=4993.9,4998.9
Exp/Cntr=0.3,0.1

Type RM Length L Ch R = 1,11831,423,423,423
BEGIN DESCRIPTION:
Little Cottonwood Creek Trib 2 21.0
END DESCRIPTION:
XS GIS Cut Line= 3
      2667026.01      6887160.99      2666226.00      6887811.00
      2665725.99      6888111.01
#Sta/Elev= 30
  3974.0  441.86  4080.3  436.91  4123.4  433.67  4158.6  432.35  4187.4  429.85
  4236.9  428.61  4280.0  425.00  4329.6  423.56  4358.3  421.14  4407.9  419.95
  4436.6  417.75  4492.6  416.79  4535.7  414.60  4585.3  414.00  4614.0  412.39
  4692.3  411.78  4741.9  410.19  4848.9  409.05  4948.1  409.59  4962.4  407.72
  4988.7  406.36  4989.3  405.86  4993.7  406.36  5039.8  408.62  5113.6  409.29
  5187.5  416.20  5230.3  417.42  5552.9  421.40  5580.1  423.15  5587.9  422.52
#Mann=3,-1,0
  3974.0    0.05       0  4988.7    0.04       0  4993.7    0.05       0
Bank Sta=4988.7,4993.7
Exp/Cntr=0.3,0.1

Type RM Length L Ch R = 1,11408,470,470,470
BEGIN DESCRIPTION:
Little Cottonwood Creek Trib 2 20.0
END DESCRIPTION:
XS GIS Cut Line= 3
      2666826.00      6887061.00      2666026.00      6887461.00
      2665676.02      6888060.96
#Sta/Elev= 30
  4105.6  432.45  4150.3  429.09  4195.0  427.65  4225.8  424.99  4298.5  422.82
  4404.7  417.30  4477.3  415.97  4516.5  413.99  4611.5  411.82  4678.6  411.22
  4723.3  409.60  4798.8  408.26  4874.2  407.25  4969.3  408.33  5005.3  405.40
  5006.0  404.90  5010.4  405.40  5029.4  406.38  5035.2  408.60  5050.9  410.57
  5072.4  410.62  5088.1  409.65  5146.8  410.37  5196.8  411.99  5322.9  413.91
  5446.2  417.96  5606.6  420.25  5628.1  421.39  5659.5  421.14  5694.6  422.47
#Mann=3,-1,0
  4105.6    0.05       0  5005.3    0.04       0  5010.4    0.05       0
Bank Sta=5005.3,5010.4
Exp/Cntr=0.3,0.1

Type RM Length L Ch R = 1,10938,434,434,434
BEGIN DESCRIPTION:
Little Cottonwood Creek Trib 2 19.0
END DESCRIPTION:
XS GIS Cut Line= 3
      2666475.98      6886361.02      2665676.00      6887161.00
      2665576.00      6887911.02
#Sta/Elev= 30
  3868.9  425.45  3996.2  421.20  4081.0  419.97  4109.3  418.08  4137.6  417.27
  4250.7  415.74  4349.7  413.24  4392.1  413.35  4448.7  411.79  4561.8  410.70
  4604.3  409.68  4703.3  408.37  4802.3  407.57  4858.8  407.92  4929.5  405.27
  4957.8  404.89  4986.1  405.19  4994.1  404.07  4994.8  403.57  4998.6  403.57
  4999.3  404.07  5010.3  404.31  5036.8  407.13  5050.7  407.69  5101.1  407.72
  5181.8  409.67  5202.0  410.66  5292.8  412.69  5720.3  419.12  5756.9  420.47
#Mann=3,-1,0
  3868.9    0.05       0  4994.1    0.04       0  4999.3    0.05       0
Bank Sta=4994.1,4999.3
Exp/Cntr=0.3,0.1

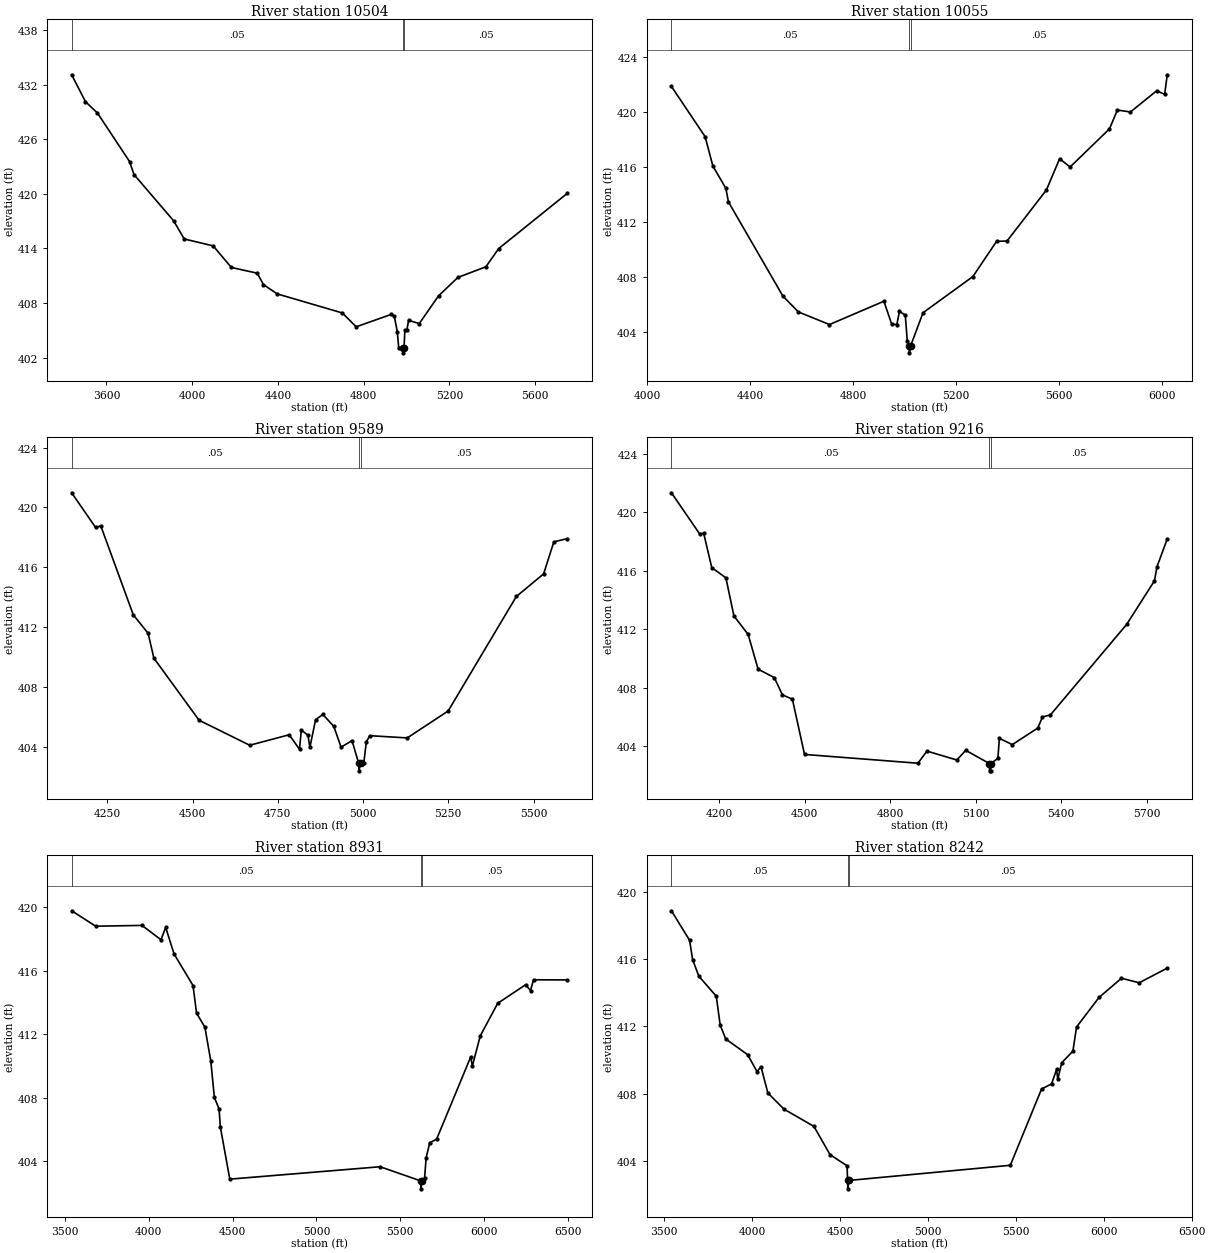
Type RM Length L Ch R = 1,10504,449,449,449
BEGIN DESCRIPTION:
Little Cottonwood Creek Trib 2 18.0
END DESCRIPTION:
XS GIS Cut Line= 3
      2666475.99      6886061.01      2665276.00      6887061.00
      2665226.00      6887810.99
#Sta/Elev= 30
  3437.5  433.07  3501.9  430.12  3557.9  428.87  3707.6  423.54  3728.4  422.11
  3913.3  417.03  3962.7  415.03  4098.1  414.27  4182.7  411.90  4303.8  411.27
  4332.4  410.02  4396.2  409.00  4700.8  406.90  4765.2  405.38  4928.6  406.74
  4942.9  406.57  4957.2  404.83  4963.7  403.06  4983.2  403.02  4984.0  402.52
  4988.5  403.02  4992.4  404.98  5002.0  405.03  5009.6  406.09  5059.7  405.74
  5149.9  408.79  5240.1  410.81  5370.4  411.97  5430.5  413.98  5751.2  420.06
#Mann=3,-1,0
  3437.5    0.05       0  4983.2    0.04       0  4988.5    0.05       0
Bank Sta=4983.2,4988.5
Exp/Cntr=0.3,0.1

Type RM Length L Ch R = 1,10055,466,466,466
BEGIN DESCRIPTION:
Little Cottonwood Creek Trib 2 17.0
END DESCRIPTION:
XS GIS Cut Line= 3
      2664776.00      6886061.03      2664876.00      6886961.00
      2665076.00      6887960.99
#Sta/Elev= 30
  4094.9  421.88  4225.7  418.22  4255.9  416.08  4306.2  414.46  4316.2  413.47
  4527.5  406.61  4587.9  405.45  4708.6  404.53  4919.9  406.23  4950.1  404.56
  4970.2  404.53  4980.3  405.49  5003.0  405.22  5010.6  403.35  5018.1  402.97
  5018.9  402.47  5023.5  402.97  5071.8  405.39  5265.6  408.03  5357.3  410.59
  5398.1  410.62  5551.1  414.34  5602.1  416.61  5642.9  416.01  5795.9  418.79
  5826.4  420.16  5877.4  420.02  5979.4  421.57  6010.0  421.30  6020.2  422.73
#Mann=3,-1,0
  4094.9    0.05       0  5018.1    0.03       0  5023.5    0.05       0
Bank Sta=5018.1,5023.5
Exp/Cntr=0.3,0.1

Type RM Length L Ch R = 1,9589,373,373,373
BEGIN DESCRIPTION:
Little Cottonwood Creek Trib 2 16.0
END DESCRIPTION:
XS GIS Cut Line= 3
      2664726.01      6886110.98      2664426.00      6886911.00
      2664426.00      6887510.98
#Sta/Elev= 30
  4145.2  420.98  4215.5  418.66  4230.7  418.77  4325.9  412.83  4369.5  411.59
  4386.4  409.93  4519.0  405.78  4667.6  404.11  4783.3  404.81  4813.6  403.84
  4818.9  405.12  4838.5  404.78  4843.9  403.96  4860.8  405.82  4882.1  406.17
  4914.2  405.37  4935.5  403.98  4967.6  404.42  4987.1  402.90  4987.9  402.40
  4992.5  402.90  5002.1  402.92  5009.6  404.33  5019.6  404.75  5129.6  404.60
  5249.6  406.40  5449.6  414.05  5529.6  415.56  5559.6  417.70  5599.6  417.92
#Mann=3,-1,0
  4145.2    0.05       0  4987.1    0.03       0  4992.5    0.05       0
Bank Sta=4987.1,4992.5
Exp/Cntr=0.3,0.1

Type RM Length L Ch R = 1,9216,285,285,285
BEGIN DESCRIPTION:
Little Cottonwood Creek Trib 2 15.0
END DESCRIPTION:
XS GIS Cut Line= 4
      2664676.03      6886060.96      2664137.40      6886641.03
      2664022.48      6887008.34      2664275.99      6887510.98
#Sta/Elev= 30
  4032.5  421.32  4131.5  418.51  4145.7  418.55  4174.0  416.21  4223.6  415.51
  4251.7  412.91  4301.5  411.65  4336.7  409.27  4393.4  408.70  4421.7  407.52
  4456.9  407.22  4499.4  403.45  4897.4  402.85  4928.8  403.68  5033.6  403.07
  5065.0  403.73  5147.8  402.83  5148.6  402.33  5152.5  402.33  5153.2  402.83
  5177.7  403.18  5183.0  404.55  5228.3  404.12  5317.5  405.25  5334.2  406.01
  5362.1  406.15  5629.8  412.34  5727.1  415.31  5735.7  416.26  5771.9  418.17
#Mann=3,-1,0
  4032.5    0.05       0  5147.8    0.03       0  5153.2    0.05       0
Bank Sta=5147.8,5153.2
Exp/Cntr=0.3,0.1

Type RM Length L Ch R = 1,8931,689,689,689
BEGIN DESCRIPTION:
Little Cottonwood Creek Trib 2 14.0
END DESCRIPTION:
XS GIS Cut Line= 4
      2664877.53      6885649.82      2663845.98      6886681.04
      2663576.01      6886886.00      2662439.61      6887103.57
#Sta/Elev= 30
  3541.4  419.77  3684.7  418.80  3960.5  418.85  4073.6  417.95  4101.9  418.72
  4151.4  417.06  4264.6  415.07  4285.8  413.33  4335.3  412.45  4370.6  410.32
  4391.8  408.03  4420.1  407.30  4427.2  406.19  4483.8  402.89  5379.7  403.67
  5621.2  402.78  5622.1  402.28  5627.0  402.78  5644.4  402.94  5653.8  404.23
  5675.0  405.18  5716.0  405.40  5919.1  410.57  5929.5  410.01  5976.2  411.90
  6080.3  413.95  6246.6  415.12  6275.7  414.75  6293.6  415.43  6496.0  415.42
#Mann=3,-1,0
  3541.4    0.05       0  5621.2    0.03       0  5627.0    0.05       0
Bank Sta=5621.2,5627
Exp/Cntr=0.3,0.1

Type RM Length L Ch R = 1,8242,654,654,654
BEGIN DESCRIPTION:
Little Cottonwood Creek Trib 2 13.0
END DESCRIPTION:
XS GIS Cut Line= 3
      2664847.13      6885493.59      2663526.00      6886111.00
      2662473.00      6886973.62
#Sta/Elev= 30
  3541.7  418.87  3644.8  417.12  3662.2  415.97  3697.5  414.98  3796.8  413.79
  3818.9  412.08  3850.5  411.25  3975.7  410.31  4028.6  409.30  4050.7  409.61
  4090.0  408.04  4181.4  407.08  4352.3  406.05  4443.7  404.37  4540.7  403.71
  4543.2  402.84  4544.4  402.34  4551.7  402.84  5468.7  403.74  5646.3  408.27
  5703.3  408.58  5732.1  409.44  5738.5  408.84  5760.8  409.83  5824.6  410.53
  5845.5  411.96  5973.2  413.72  6101.0  414.86  6201.4  414.59  6361.2  415.46
#Mann=3,-1,0
  3541.7    0.05       0  4543.2    0.03       0  4551.7    0.05       0
Bank Sta=4543.2,4551.7
Exp/Cntr=0.3,0.1