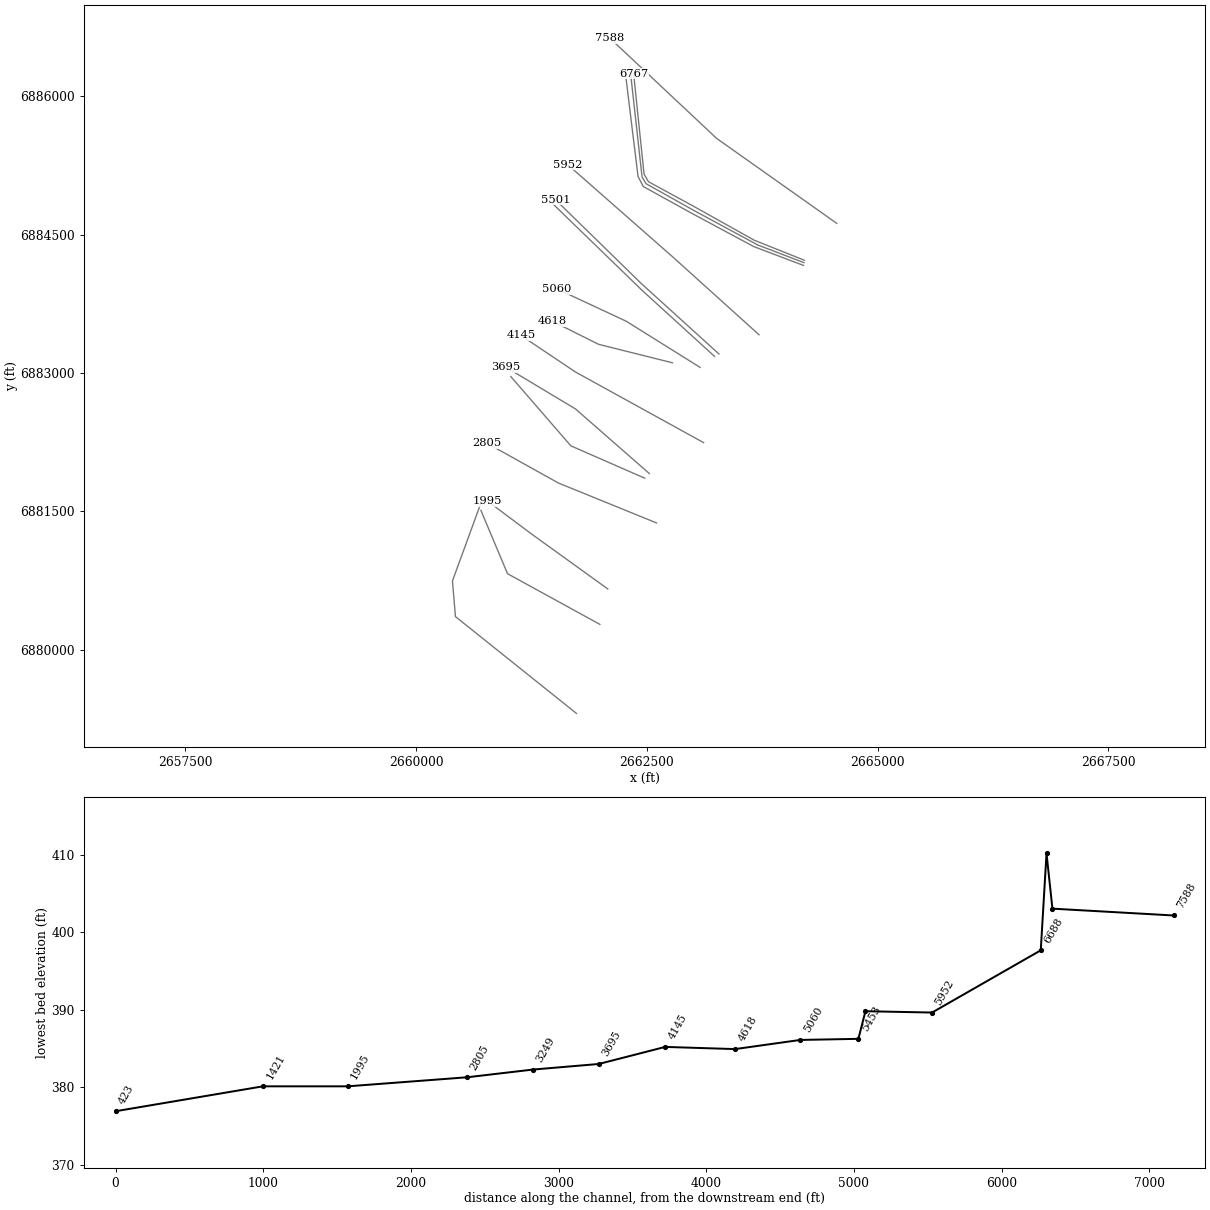
HEC-RAS study Little Cottonwood Creek Trib 2.prj: Little Cottonwood Creek Trib 2 Base Level Engineering

--- Little Cottonwood Creek Trib 2.g01 (geometry) --- (continued)

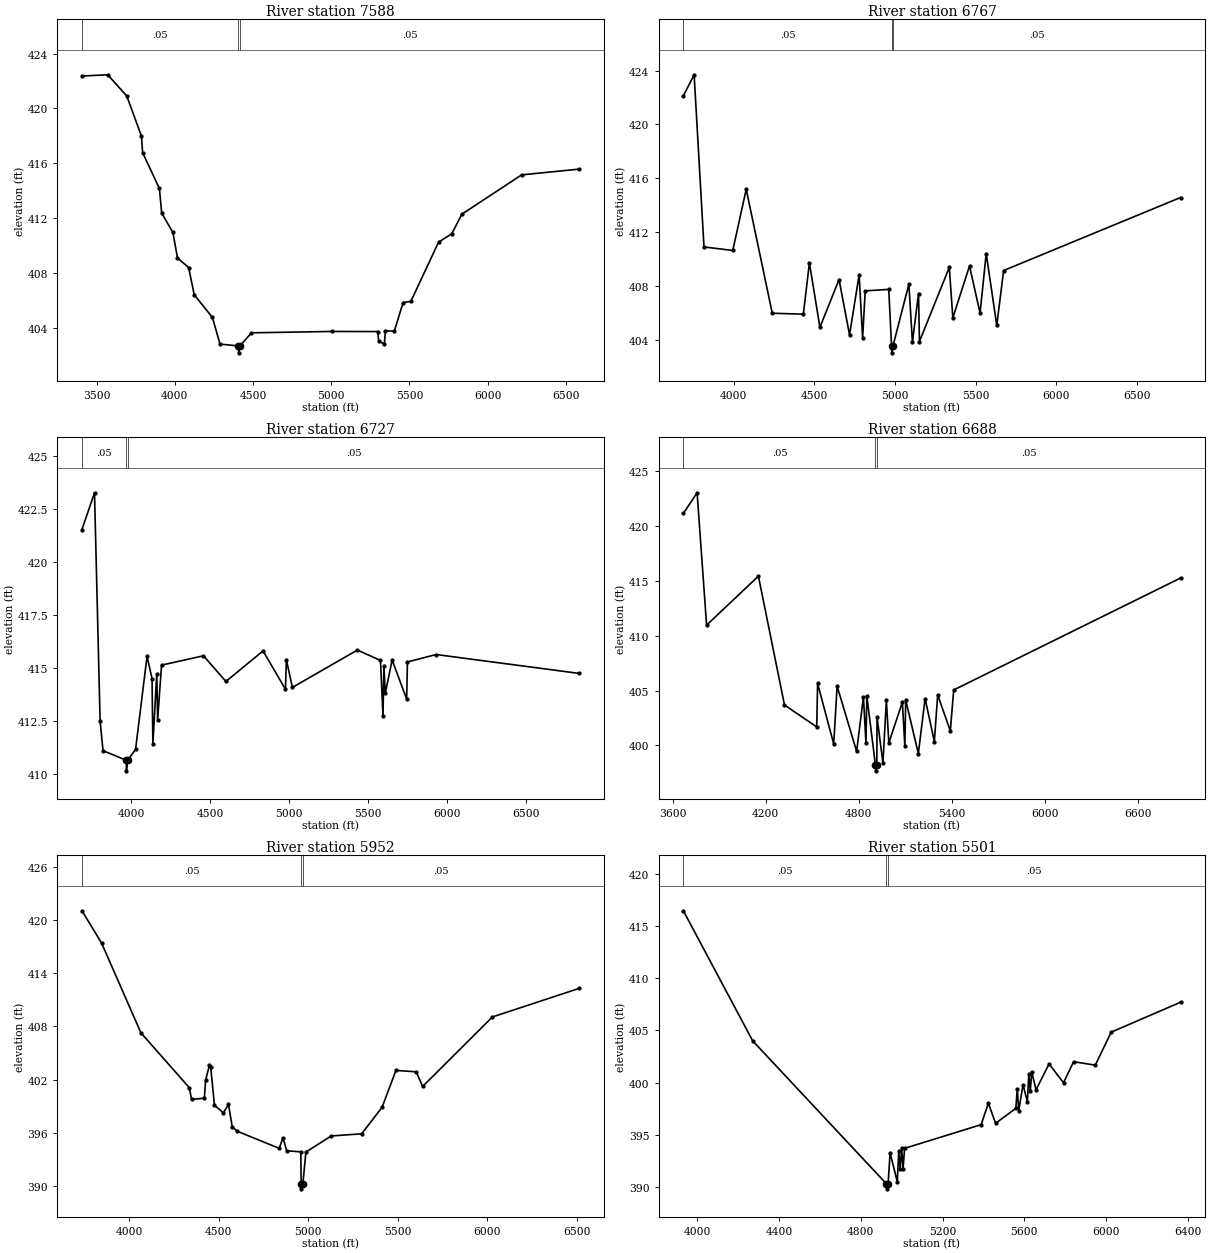
Type RM Length L Ch R = 1,7588,821,821,821
BEGIN DESCRIPTION:
Little Cottonwood Creek Trib 2 11.0
END DESCRIPTION:
XS GIS Cut Line= 3
      2664556.29      6884621.22      2663255.73      6885541.11
      2662100.55      6886625.63
#Sta/Elev= 30
  3407.0  422.36  3571.9  422.45  3693.8  420.89  3787.1  417.98  3794.7  416.77
  3901.8  414.16  3916.6  412.36  3988.0  410.95  4017.5  409.09  4088.9  408.39
  4124.6  406.40  4240.3  404.76  4289.3  402.81  4407.4  402.67  4408.7  402.17
  4416.0  402.67  4490.2  403.63  5006.8  403.73  5296.9  403.72  5303.8  403.03
  5339.4  402.81  5346.3  403.78  5402.9  403.75  5459.6  405.84  5508.9  405.92
  5685.8  410.24  5770.7  410.86  5834.7  412.28  6216.7  415.15  6584.5  415.57
#Mann=3,-1,0
  3407.0    0.05       0  4407.4    0.03       0  4416.0    0.05       0
Bank Sta=4407.4,4416
Exp/Cntr=0.3,0.1

Type RM Length L Ch R = 1,6767,40,40,40
BEGIN DESCRIPTION:
Mapping XS affc327a
END DESCRIPTION:
XS GIS Cut Line= 6
      2664204.80      6884221.87      2663662.23      6884438.90
      2663002.51      6884807.82      2662516.40      6885072.58
      2662468.66      6885155.04      2662355.81      6886244.47
#Sta/Elev= 30
  3687.1  422.13  3753.9  423.69  3815.0  410.91  3993.6  410.65  4077.0  415.19
  4238.6  405.99  4431.4  405.92  4469.0  409.73  4534.1  404.94  4652.9  408.49
  4718.0  404.38  4777.4  408.84  4799.1  404.13  4815.0  407.65  4961.2  407.76
  4978.6  403.55  4979.9  403.05  4987.2  403.55  5086.1  408.15  5108.0  403.84
  5145.9  407.45  5151.6  403.89  5336.8  409.39  5358.7  405.65  5462.2  409.50
  5527.7  406.00  5565.7  410.42  5631.3  405.09  5673.8  409.16  6771.4  414.58
#Mann=3,-1,0
  3687.1    0.05       0  4978.6    0.03       0  4987.2    0.05       0
Bank Sta=4978.6,4987.2
Exp/Cntr=0.3,0.1

Type RM Length L Ch R = 1,6727,39,39,39
BEGIN DESCRIPTION:
Mapping XS 6565dd10
END DESCRIPTION:
XS GIS Cut Line= 6
      2664200.42      6884195.85      2663701.30      6884386.81
      2663002.51      6884764.42      2662490.36      6885050.88
      2662446.96      6885124.66      2662321.09      6886261.80
#Sta/Elev= 30
  3689.4  421.54  3768.8  423.27  3804.2  412.52  3822.6  411.12  3969.5  410.67
  3970.7  410.17  3978.1  410.67  4028.5  411.18  4101.0  415.56  4132.7  414.52
  4138.0  411.44  4162.7  414.74  4168.1  412.57  4192.8  415.15  4458.2  415.59
  4600.0  414.38  4835.0  415.82  4976.8  414.01  4982.5  415.40  5020.6  414.10
  5431.7  415.86  5577.8  415.37  5593.8  412.74  5599.5  415.13  5607.9  413.82
  5651.5  415.39  5743.4  413.55  5748.4  415.30  5929.9  415.65  6834.6  414.76
#Mann=3,-1,0
  3689.4    0.05       0  3969.5    0.03       0  3978.1    0.05       0
Bank Sta=3969.5,3978.1
Exp/Cntr=0.3,0.1

Type RM Length L Ch R = 1,6688,736,736,736
BEGIN DESCRIPTION:
Mapping XS c273c11a
END DESCRIPTION:
XS GIS Cut Line= 6
      2664196.12      6884165.45      2663657.89      6884369.45
      2663002.51      6884721.02      2662459.98      6885020.50
      2662403.55      6885129.00      2662264.68      6886266.03
#Sta/Elev= 30
  3668.9  421.14  3757.5  423.02  3818.7  410.96  4152.9  415.42  4321.1  403.68
  4529.0  401.68  4534.7  405.64  4638.6  400.13  4660.6  405.40  4786.4  399.45
  4830.3  404.41  4846.5  400.21  4852.2  404.50  4908.0  398.18  4909.3  397.68
  4916.7  398.18  4918.0  402.57  4956.2  398.40  4978.1  404.11  4994.2  400.23
  5081.3  403.93  5097.4  399.97  5103.1  404.13  5184.4  399.25  5228.0  404.27
  5287.6  400.35  5309.3  404.60  5390.7  401.31  5412.5  405.05  6875.7  415.25
#Mann=3,-1,0
  3668.9    0.05       0  4908.0    0.03       0  4916.7    0.05       0
Bank Sta=4908,4916.7
Exp/Cntr=0.3,0.1

Type RM Length L Ch R = 1,5952,451,451,451
BEGIN DESCRIPTION:
Little Cottonwood Creek Trib 2 9.0
END DESCRIPTION:
XS GIS Cut Line= 3
      2663714.34      6883414.57      2662776.00      6884261.00
      2661640.35      6885258.61
#Sta/Elev= 30
  3736.6  421.05  3846.0  417.41  4065.8  407.27  4334.8  401.10  4349.0  399.75
  4420.0  399.90  4426.7  401.93  4448.1  403.60  4455.1  403.42  4476.1  399.11
  4526.1  398.23  4554.5  399.19  4575.4  396.66  4603.8  396.16  4837.7  394.23
  4858.7  395.44  4879.6  393.95  4958.1  393.84  4960.2  390.16  4961.6  389.66
  4969.4  390.16  4986.5  393.81  5127.9  395.63  5297.8  395.87  5411.6  398.86
  5489.4  403.03  5602.4  402.87  5638.4  401.22  6027.5  409.06  6511.9  412.29
#Mann=3,-1,0
  3736.6    0.05       0  4960.2    0.03       0  4969.4    0.05       0
Bank Sta=4960.2,4969.4
Exp/Cntr=0.3,0.1

Type RM Length L Ch R = 1,5501,48,48,48
BEGIN DESCRIPTION:
Mapping XS c0cfbabd
END DESCRIPTION:
XS GIS Cut Line= 3
      2663280.27      6883206.28      2662442.62      6883965.81
      2661510.86      6884875.90
#Sta/Elev= 30
  3931.7  416.47  4270.9  404.01  4924.5  390.33  4925.9  389.83  4933.8  390.33
  4943.4  393.28  4978.5  390.51  4985.9  393.43  4992.7  391.73  5000.1  393.72
  5006.9  391.75  5014.3  393.71  5389.0  395.98  5424.3  398.03  5459.8  396.11
  5558.8  397.54  5565.8  399.42  5572.9  397.32  5594.0  399.81  5615.4  398.17
  5622.3  400.80  5629.5  399.20  5636.5  401.03  5657.8  399.32  5721.4  401.80
  5792.1  399.99  5841.5  402.01  5947.7  401.68  6025.4  404.84  6364.9  407.71
#Mann=3,-1,0
  3931.7    0.05       0  4924.5    0.03       0  4933.8    0.05       0
Bank Sta=4924.5,4933.8
Exp/Cntr=0.3,0.1

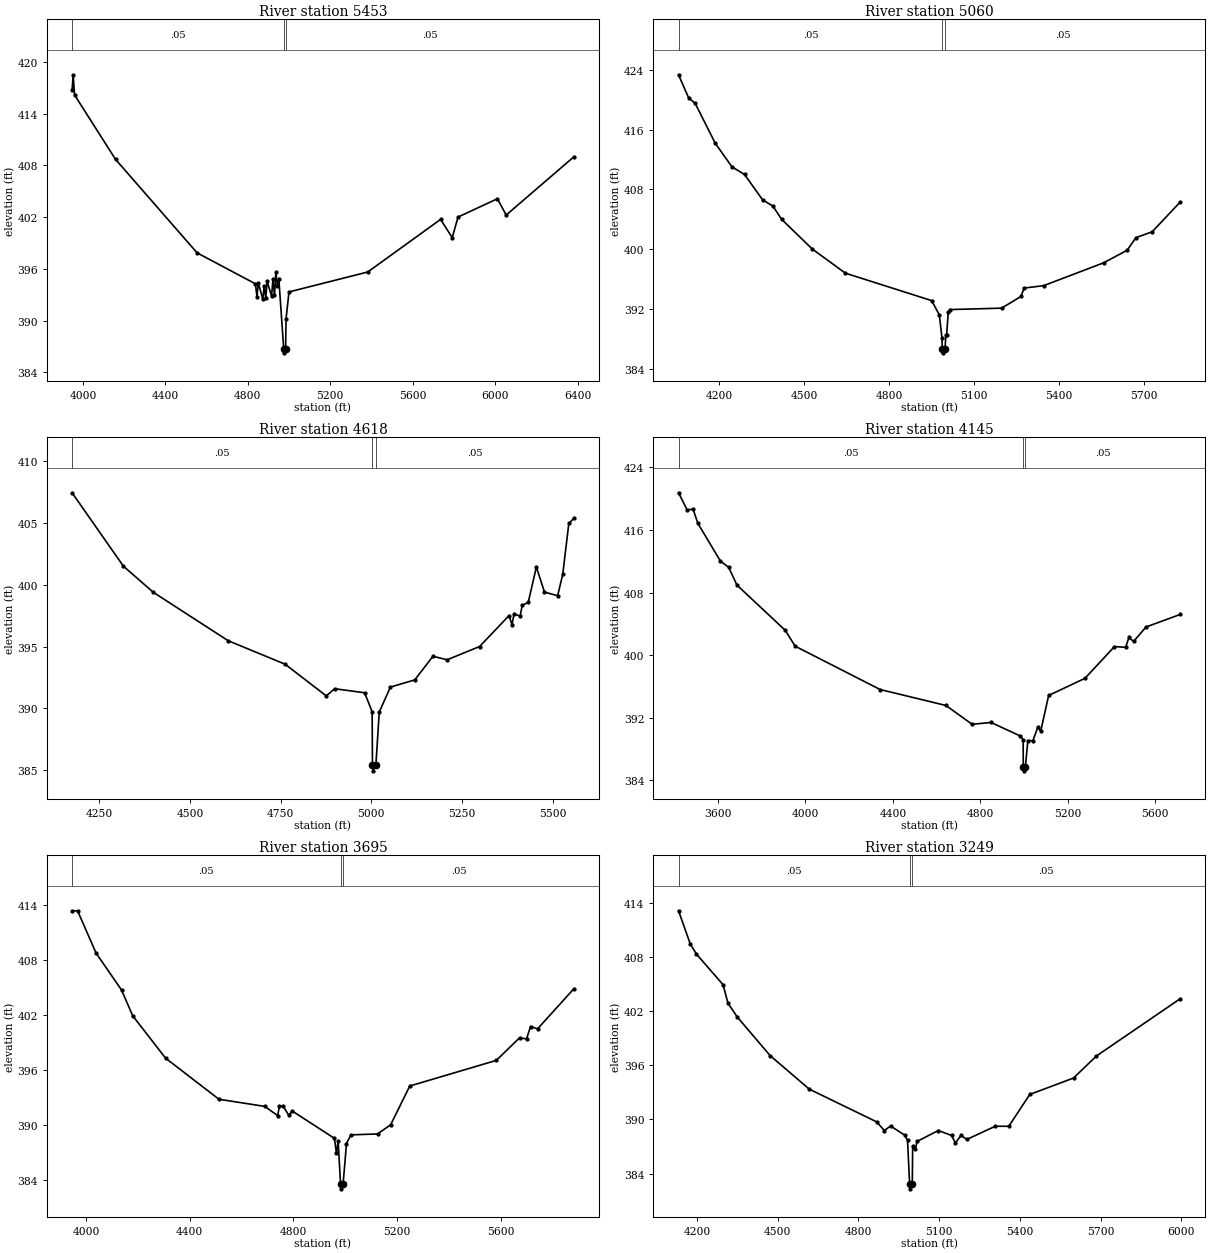
Type RM Length L Ch R = 1,5453,393,393,393
BEGIN DESCRIPTION:
Mapping XS 95a03903
END DESCRIPTION:
XS GIS Cut Line= 3
      2663232.57      6883180.20      2662446.96      6883896.36
      2661461.70      6884851.24
#Sta/Elev= 30
  3947.1  416.71  3952.5  418.50  3959.2  416.16  4157.9  408.70  4553.8  397.86
  4836.9  394.27  4844.3  392.76  4851.1  394.39  4872.7  392.47  4879.5  394.02
  4886.9  392.59  4893.6  394.55  4915.3  392.85  4922.0  394.81  4929.4  392.92
  4936.2  395.65  4943.6  393.97  4950.4  394.88  4974.1  386.77  4975.5  386.27
  4983.4  386.77  4985.5  390.20  4999.7  393.33  5381.9  395.64  5735.6  401.74
  5791.9  399.62  5820.2  402.01  6011.3  404.13  6053.8  402.24  6382.2  408.99
#Mann=3,-1,0
  3947.1    0.05       0  4974.1    0.04       0  4983.4    0.05       0
Bank Sta=4974.1,4983.4
Exp/Cntr=0.3,0.1

Type RM Length L Ch R = 1,5060,442,442,442
BEGIN DESCRIPTION:
Little Cottonwood Creek Trib 2 7.0
END DESCRIPTION:
XS GIS Cut Line= 3
      2663075.98      6883061.01      2662276.00      6883561.00
      2661526.02      6883910.99
#Sta/Elev= 30
  4057.1  423.34  4092.5  420.27  4116.0  419.50  4186.8  414.17  4245.8  411.01
  4290.0  410.00  4353.7  406.61  4390.2  405.77  4420.9  404.00  4528.8  400.03
  4646.1  396.79  4950.4  393.12  4977.5  391.22  4986.9  388.11  4988.1  386.63
  4989.4  386.13  4997.6  386.63  5000.5  388.48  5003.2  388.48  5009.1  391.59
  5014.7  391.92  5197.5  392.11  5265.3  393.67  5277.1  394.80  5345.7  395.12
  5557.0  398.17  5640.5  399.86  5671.3  401.54  5728.8  402.33  5828.1  406.33
#Mann=3,-1,0
  4057.1    0.05       0  4988.1    0.03       0  4997.6    0.05       0
Bank Sta=4988.1,4997.6
Exp/Cntr=0.3,0.1

Type RM Length L Ch R = 1,4618,473,473,473
BEGIN DESCRIPTION:
Little Cottonwood Creek Trib 2 6.0
END DESCRIPTION:
XS GIS Cut Line= 3
      2662776.01      6883111.00      2661976.00      6883311.00
      2661476.04      6883560.98
#Sta/Elev= 30
  4174.9  407.43  4316.6  401.49  4399.1  399.38  4605.3  395.47  4762.4  393.57
  4875.8  391.01  4899.0  391.59  4981.5  391.26  5002.3  389.73  5003.2  385.45
  5004.5  384.95  5012.7  385.45  5021.9  389.70  5052.6  391.72  5119.7  392.30
  5170.0  394.21  5209.2  393.93  5298.6  395.00  5379.7  397.50  5388.0  396.76
  5393.6  397.65  5410.4  397.45  5416.0  398.32  5432.8  398.58  5455.1  401.43
  5477.5  399.40  5513.8  399.11  5527.8  400.83  5544.6  404.95  5558.5  405.36
#Mann=3,-1,0
  4174.9    0.05       0  5003.2    0.03       0  5012.7    0.05       0
Bank Sta=5003.2,5012.7
Exp/Cntr=0.3,0.1

Type RM Length L Ch R = 1,4145,450,450,450
BEGIN DESCRIPTION:
Little Cottonwood Creek Trib 2 5.0
END DESCRIPTION:
XS GIS Cut Line= 3
      2663113.62      6882246.19      2661726.00      6883011.00
      2661135.66      6883406.84
#Sta/Elev= 30
  3419.4  420.76  3458.5  418.59  3486.0  418.65  3508.0  416.84  3611.0  412.03
  3648.8  411.23  3686.7  408.96  3907.7  403.18  3952.6  401.16  4341.6  395.62
  4642.7  393.58  4762.0  391.18  4849.1  391.41  4981.0  389.70  4995.8  389.23
  4996.2  385.73  4997.5  385.23  5005.8  385.73  5017.3  389.10  5039.9  389.07
  5062.3  390.77  5076.1  390.30  5112.2  394.86  5278.4  397.05  5413.5  401.11
  5464.5  401.01  5479.5  402.28  5500.6  401.76  5557.7  403.61  5714.6  405.22
#Mann=3,-1,0
  3419.4    0.05       0  4996.2    0.03       0  5005.8    0.05       0
Bank Sta=4996.2,5005.8
Exp/Cntr=0.3,0.1

Type RM Length L Ch R = 1,3695,446,446,446
BEGIN DESCRIPTION:
Little Cottonwood Creek Trib 2 4.0
END DESCRIPTION:
XS GIS Cut Line= 3
      2662526.02      6881910.98      2661726.00      6882611.00
      2660975.99      6883061.01
#Sta/Elev= 30
  3945.4  413.42  3966.8  413.41  4038.0  408.80  4136.7  404.75  4179.4  401.95
  4306.6  397.31  4512.5  392.82  4689.5  392.04  4739.4  391.03  4746.0  392.05
  4760.3  392.08  4782.1  391.08  4795.8  391.53  4958.6  388.55  4966.2  386.92
  4972.9  388.27  4982.2  383.53  4983.6  383.03  4991.9  383.53  5005.1  387.98
  5022.1  388.93  5125.1  389.03  5175.6  390.03  5249.5  394.27  5583.8  397.07
  5673.2  399.53  5700.4  399.42  5715.9  400.77  5743.1  400.52  5883.1  404.90
#Mann=3,-1,0
  3945.4    0.05       0  4982.2    0.03       0  4991.9    0.05       0
Bank Sta=4982.2,4991.9
Exp/Cntr=0.3,0.1

Type RM Length L Ch R = 1,3249,444,444,444
BEGIN DESCRIPTION:
Little Cottonwood Creek Trib 2 3.0
END DESCRIPTION:
XS GIS Cut Line= 3
      2662476.00      6881861.00      2661676.00      6882211.00
      2661025.99      6882961.01
#Sta/Elev= 30
  4130.9  413.10  4174.6  409.42  4197.6  408.30  4296.6  404.91  4314.5  402.88
  4349.2  401.34  4471.2  397.07  4617.0  393.35  4867.3  389.73  4896.1  388.77
  4919.5  389.27  4971.8  388.25  4982.3  387.67  4990.2  382.81  4991.6  382.31
  5000.0  382.81  5001.4  387.02  5011.2  386.69  5017.9  387.56  5096.7  388.77
  5146.1  388.22  5160.4  387.38  5181.2  388.23  5202.6  387.78  5308.5  389.24
  5358.9  389.24  5436.7  392.76  5599.6  394.58  5684.6  397.02  5996.6  403.37
#Mann=3,-1,0
  4130.9    0.05       0  4990.2    0.04       0  5000.0    0.05       0
Bank Sta=4990.2,5000
Exp/Cntr=0.3,0.1

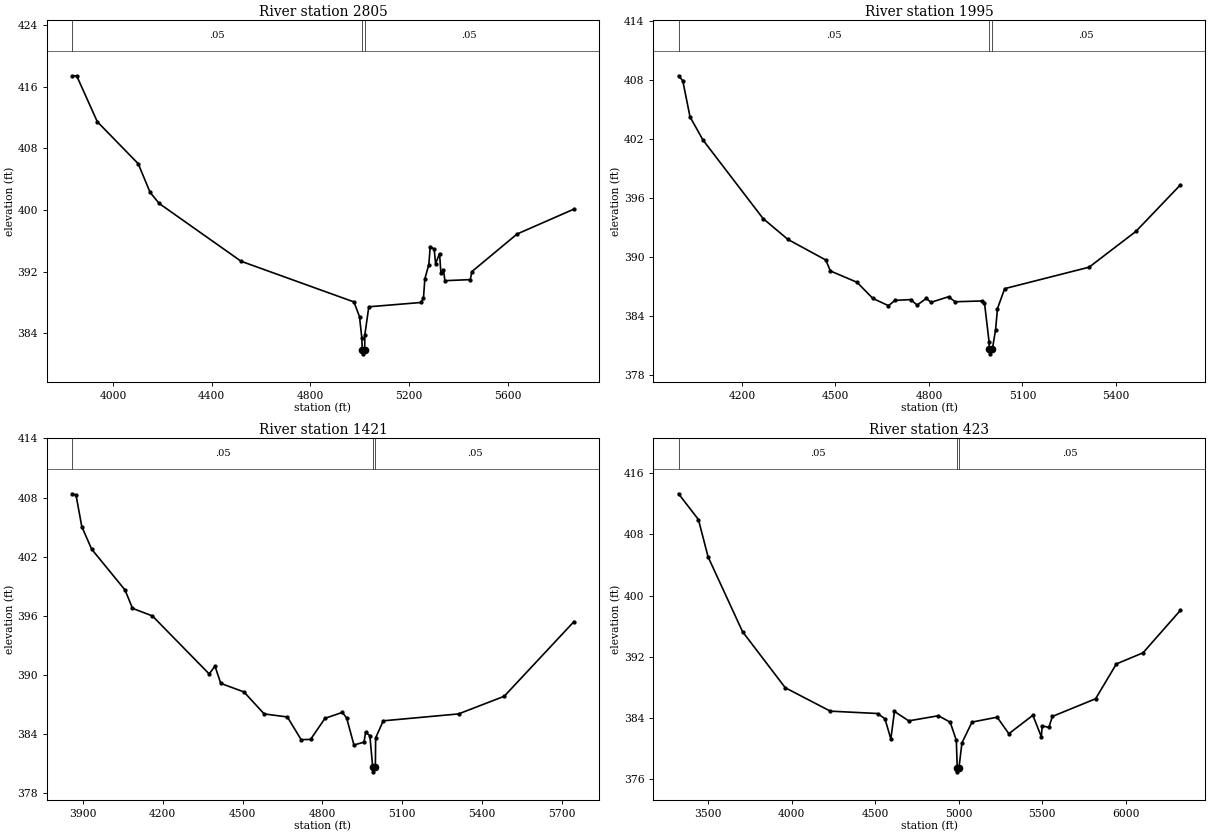
Type RM Length L Ch R = 1,2805,810,810,810
BEGIN DESCRIPTION:
Mapping XS 64d05879
END DESCRIPTION:
XS GIS Cut Line= 3
      2662603.25      6881376.38      2661540.71      6881808.69
      2660764.70      6882240.96
#Sta/Elev= 30
  3833.2  417.41  3851.8  417.43  3935.6  411.46  4101.5  406.01  4149.7  402.29
  4186.5  400.85  4518.9  393.34  4976.6  388.06  4999.1  386.15  5008.6  383.35
  5010.2  381.82  5011.6  381.32  5020.1  381.82  5020.8  383.79  5036.8  387.43
  5249.0  387.99  5258.6  388.62  5264.3  391.07  5280.3  392.92  5286.0  395.25
  5302.0  394.92  5307.8  393.03  5323.8  394.34  5329.5  391.77  5339.8  392.20
  5345.5  390.82  5448.4  390.96  5455.0  392.00  5638.2  396.88  5868.6  400.11
#Mann=3,-1,0
  3833.2    0.05       0  5010.2    0.03       0  5020.1    0.05       0
Bank Sta=5010.2,5020.1
Exp/Cntr=0.3,0.1

Type RM Length L Ch R = 1,1995,574,574,574
BEGIN DESCRIPTION:
Little Cottonwood Creek Trib 2 2.0
END DESCRIPTION:
XS GIS Cut Line= 3
      2662076.03      6880660.98      2661261.87      6881247.64
      2660776.01      6881610.99
#Sta/Elev= 30
  3996.5  408.39  4010.1  407.89  4033.3  404.22  4075.1  401.86  4267.8  393.89
  4347.5  391.77  4469.0  389.68  4483.7  388.57  4569.6  387.41  4619.9  385.78
  4670.2  385.04  4691.1  385.58  4741.4  385.66  4762.3  385.10  4791.7  385.79
  4806.5  385.38  4862.9  385.95  4884.0  385.44  4970.3  385.52  4978.3  385.32
  4993.0  381.37  4993.6  380.65  4995.0  380.15  5003.6  380.65  5013.8  382.58
  5020.0  384.75  5043.0  386.77  5313.9  388.95  5464.0  392.58  5606.7  397.30
#Mann=3,-1,0
  3996.5    0.05       0  4993.6    0.04       0  5003.6    0.05       0
Bank Sta=4993.6,5003.6
Exp/Cntr=0.3,0.1

Type RM Length L Ch R = 1,1421,998,998,998
BEGIN DESCRIPTION:
Mapping XS 4b61a74d
END DESCRIPTION:
XS GIS Cut Line= 3
      2661990.45      6880277.02      2660990.02      6880826.06
      2660701.40      6881511.81
#Sta/Elev= 30
  3859.5  408.38  3874.2  408.27  3896.0  405.05  3933.0  402.76  4058.5  398.61
  4086.5  396.75  4161.2  395.98  4374.6  390.09  4396.4  390.88  4418.2  389.13
  4505.4  388.26  4581.2  386.03  4668.4  385.72  4720.1  383.42  4755.6  383.44
  4809.6  385.58  4875.0  386.19  4891.1  385.61  4918.6  382.87  4956.5  383.17
  4962.2  384.18  4978.3  383.82  4988.9  380.65  4990.3  380.15  4998.9  380.65
  5000.1  383.60  5028.6  385.33  5311.4  386.03  5483.0  387.82  5744.7  395.39
#Mann=3,-1,0
  3859.5    0.05       0  4988.9    0.03       0  4998.9    0.05       0
Bank Sta=4988.9,4998.9
Exp/Cntr=0.3,0.1

Type RM Length L Ch R = 1,423,0,0,0
BEGIN DESCRIPTION:
Little Cottonwood Creek Trib 2 1.0
END DESCRIPTION:
XS GIS Cut Line= 4
      2661736.02      6879313.03      2660425.66      6880361.35
      2660393.24      6880747.93      2660716.05      6881630.72
#Sta/Elev= 30
  3321.9  413.32  3441.1  409.95  3498.8  405.07  3705.3  395.28  3961.4  387.94
  4231.2  384.88  4515.3  384.57  4558.5  383.88  4593.7  381.24  4615.4  384.84
  4701.0  383.61  4878.6  384.28  4949.1  383.44  4985.9  381.07  4991.5  377.44
  4992.9  376.94  5001.7  377.44  5019.7  380.73  5079.9  383.45  5230.5  384.09
  5300.7  381.93  5444.7  384.34  5495.1  381.53  5500.5  382.96  5540.3  382.75
  5561.6  384.19  5820.3  386.50  5944.9  391.06  6104.3  392.51  6327.9  398.06
#Mann=3,-1,0
  3321.9    0.05       0  4991.5    0.05       0  5001.7    0.05       0
Bank Sta=4991.5,5001.7
Exp/Cntr=0.3,0.1

Chan Stop Cuts=-1