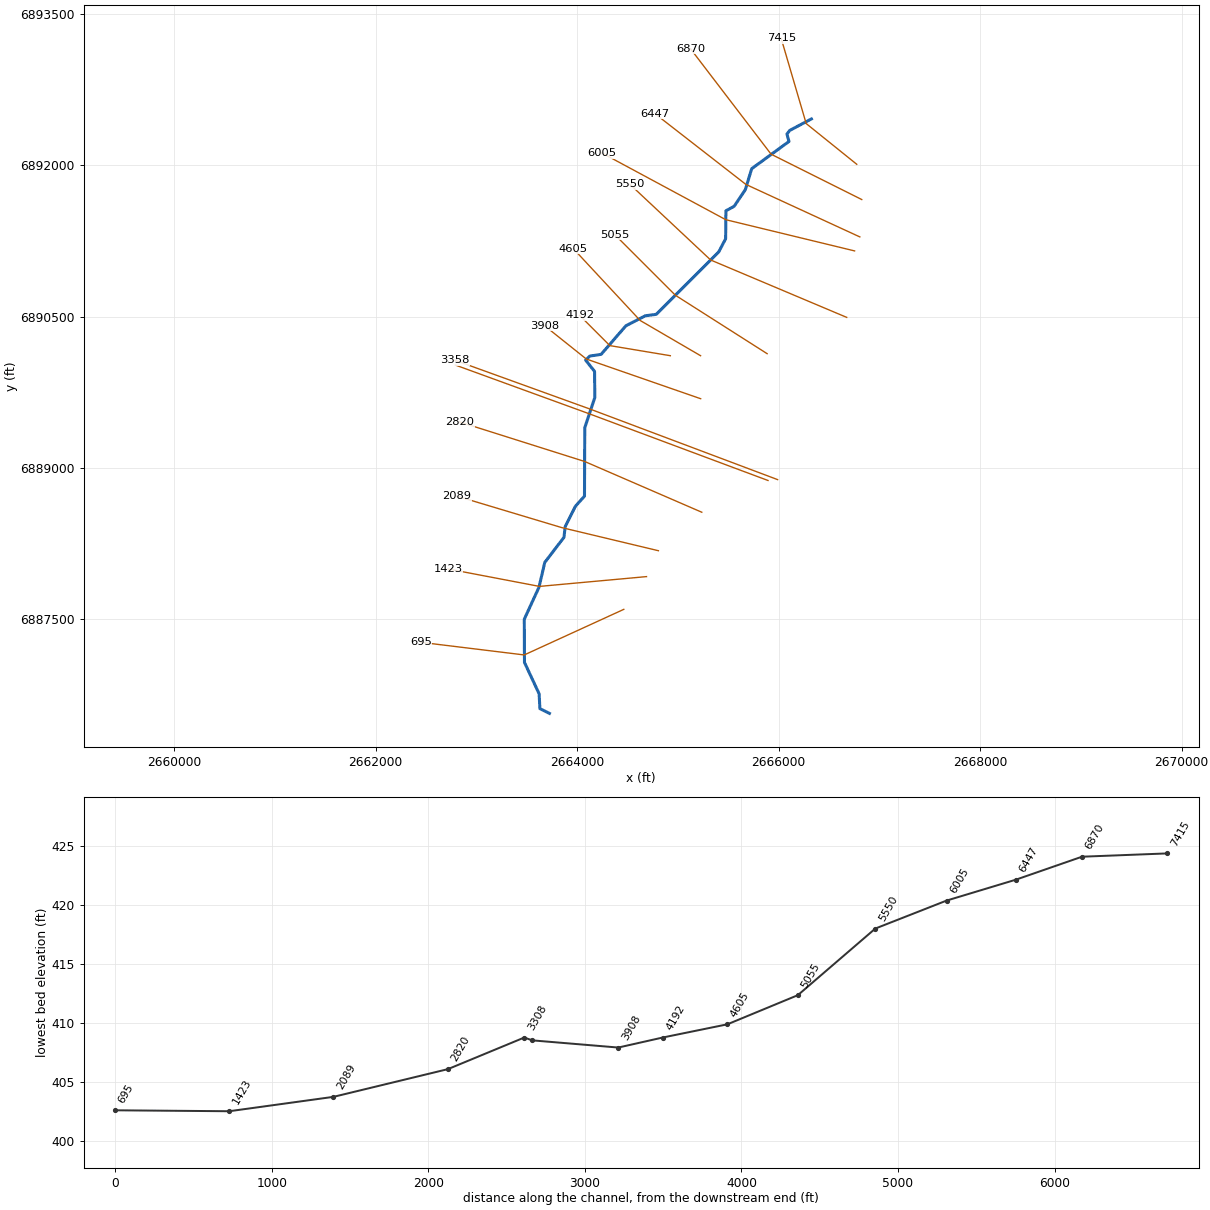
--- Little Cottonwood Creek Trib 2_1.prj (project) ---

Proj Title=Little Cottonwood Creek Trib 2_1 Base Level Engineering
Current Plan=p01
Default Exp/Contr=0.3,0.1
English Units
Geom File=g01
Flow File=f01
Plan File=p01
BEGIN DESCRIPTION:
Little Cottonwood Creek Trib 2_1
END DESCRIPTION:

--- Little Cottonwood Creek Trib 2_1.p01 (plan) ---

Plan Title=Multiple Run
Short Identifier=Multiple
Geom File=g01
Flow File=f01
Subcritical Flow
K Sum by GR= 0
Std Step Tol= 0.01
Critical Tol= 0.01
Num of Std Step Trials= 20
Max Error Tol= 0.3
Flow Tol Ratio= 0.001
Split Flow NTrial= 30
Split Flow Tol= 0.02
Split Flow Ratio= 0.02
Log Output Level= 0
Friction Slope Method= 1
Unsteady Friction Slope Method= 2
Unsteady Bridges Friction Slope Method= 1
Parabolic Critical Depth
Global Vel Dist=  1 , 1 , 1
Global Log Level= 0
CheckData=True
Encroach Param= -1, 0, 0, 0
BEGIN DESCRIPTION:
Multiple Run
END DESCRIPTION:

--- Little Cottonwood Creek Trib 2_1.f01 (steady flow) ---

Flow Title=Multiple
Number of Profiles=7
Profile Names=10-year,25-year,50-year,1pct_min,100-year,1pct_plu,500-year
River Rch & RM= Little Cottonwoo,Reach-1,7415
     427     561     668     394     787    1570    1092
River Rch & RM= Little Cottonwoo,Reach-1,6005
     590     791     953     570    1136    2267    1615
River Rch & RM= Little Cottonwoo,Reach-1,1423
     591     792     952     568    1134    2262    1607
Boundary for River Rch & Prof#=Little Cottonwoo,Reach-1,1
Up Type=0
Dn Type=3
Dn Slope=0.005
Boundary for River Rch & Prof#=Little Cottonwoo,Reach-1,2
Up Type=0
Dn Type=3
Dn Slope=0.005
Boundary for River Rch & Prof#=Little Cottonwoo,Reach-1,3
Up Type=0
Dn Type=3
Dn Slope=0.005
Boundary for River Rch & Prof#=Little Cottonwoo,Reach-1,4
Up Type=0
Dn Type=3
Dn Slope=0.005
Boundary for River Rch & Prof#=Little Cottonwoo,Reach-1,5
Up Type=0
Dn Type=3
Dn Slope=0.005
Boundary for River Rch & Prof#=Little Cottonwoo,Reach-1,6
Up Type=0
Dn Type=3
Dn Slope=0.005
Boundary for River Rch & Prof#=Little Cottonwoo,Reach-1,7
Up Type=0
Dn Type=3
Dn Slope=0.005

--- Little Cottonwood Creek Trib 2_1.g01 (geometry) ---

Geom Title=Existing Conditions

River Reach=Little Cottonwoo,Reach-1
Reach XY= 30
      2666326.00      6892461.00      2666112.00      6892347.38
      2666083.48      6892311.20      2666103.63      6892237.30
      2665733.74      6891967.45      2665670.16      6891758.71
      2665559.42      6891593.99      2665477.64      6891549.17
      2665474.80      6891271.50      2665406.22      6891140.91
      2664785.79      6890521.52      2664677.59      6890507.17
      2664484.48      6890407.49      2664239.30      6890124.40
      2664127.01      6890107.39      2664084.83      6890068.00
      2664173.92      6889955.15      2664176.43      6889695.82
      2664076.52      6889395.78      2664073.94      6888716.86
      2663984.16      6888617.05      2663881.77      6888413.32
      2663870.48      6888308.57      2663679.82      6888059.42
      2663622.17      6887812.58      2663476.52      6887495.78
      2663478.24      6887066.93      2663623.73      6886755.06
      2663631.27      6886608.31      2663726.00      6886561.00

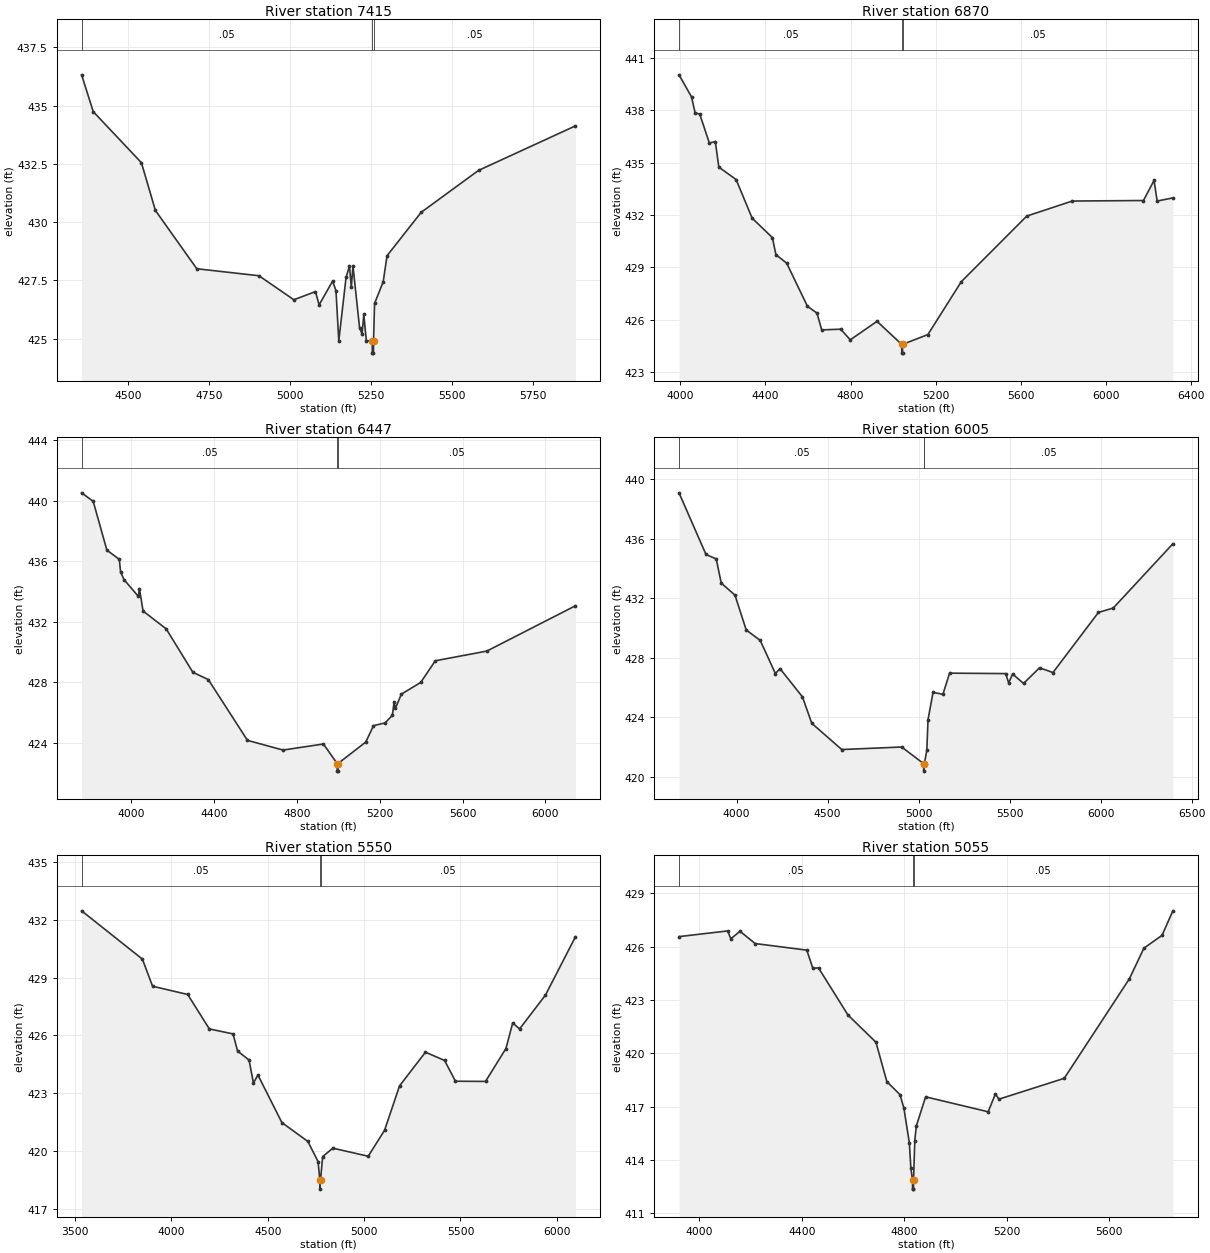
Type RM Length L Ch R = 1,7415,545,545,545
BEGIN DESCRIPTION:
Little Cottonwood Creek Trib 2_1 14.0
END DESCRIPTION:
XS GIS Cut Line= 3
      2666776.01      6892010.99      2666274.40      6892414.87
      2666026.01      6893260.96
#Sta/Elev= 30
  4356.0  436.32  4392.0  434.74  4540.8  432.55  4584.0  430.50  4711.9  428.00
  4903.9  427.70  5011.8  426.67  5078.6  427.02  5089.8  426.45  5131.5  427.47
  5141.9  427.06  5150.6  424.91  5173.1  427.63  5183.6  428.12  5189.2  427.21
  5194.4  428.12  5214.8  425.47  5222.6  425.20  5227.8  426.04  5235.7  424.92
  5253.9  424.88  5254.2  424.38  5257.7  424.38  5257.9  424.88  5261.1  426.51
  5287.8  427.44  5299.7  428.56  5405.1  430.42  5582.4  432.22  5881.8  434.13
#Mann=3,-1,0
  4356.0    0.05       0  5253.9    0.04       0  5257.9    0.05       0
Bank Sta=5253.9,5257.9
Exp/Cntr=0.3,0.1

Type RM Length L Ch R = 1,6870,423,423,423
BEGIN DESCRIPTION:
Little Cottonwood Creek Trib 2_1 13.0
END DESCRIPTION:
XS GIS Cut Line= 3
      2666825.98      6891661.01      2665926.00      6892111.00
      2665127.26      6893156.13
#Sta/Elev= 30
  3993.8  440.02  4052.5  438.76  4069.2  437.86  4091.6  437.76  4136.3  436.12
  4164.3  436.20  4181.0  434.74  4262.1  434.03  4337.6  431.82  4432.6  430.71
  4449.4  429.73  4499.7  429.25  4597.5  426.78  4642.2  426.39  4664.6  425.43
  4754.0  425.47  4798.8  424.86  4924.5  425.92  5040.6  424.60  5040.9  424.10
  5044.4  424.10  5044.6  424.60  5163.6  425.16  5321.0  428.19  5628.5  431.94
  5842.6  432.80  6177.1  432.83  6227.0  433.98  6241.5  432.80  6315.4  432.98
#Mann=3,-1,0
  3993.8    0.05       0  5040.6    0.04       0  5044.6    0.05       0
Bank Sta=5040.6,5044.6
Exp/Cntr=0.3,0.1

Type RM Length L Ch R = 1,6447,442,442,442
BEGIN DESCRIPTION:
Little Cottonwood Creek Trib 2_1 12.0
END DESCRIPTION:
XS GIS Cut Line= 3
      2666806.83      6891289.99      2665676.00      6891811.00
      2664775.96      6892511.03
#Sta/Elev= 30
  3759.5  440.51  3815.5  439.95  3881.5  436.73  3941.6  436.12  3947.6  435.30
  3964.6  434.78  4033.5  433.68  4039.0  434.18  4056.4  432.71  4167.8  431.54
  4297.0  428.67  4371.4  428.19  4560.6  424.18  4732.3  423.54  4927.5  423.94
  4993.9  422.65  4994.1  422.15  4997.6  422.15  4997.9  422.65  5132.2  424.07
  5169.3  425.15  5225.4  425.33  5260.7  425.84  5268.8  426.72  5275.1  426.29
  5304.1  427.23  5397.3  428.00  5467.9  429.43  5716.7  430.07  6144.8  433.06
#Mann=3,-1,0
  3759.5    0.05       0  4993.9    0.04       0  4997.9    0.05       0
Bank Sta=4993.9,4997.9
Exp/Cntr=0.3,0.1

Type RM Length L Ch R = 1,6005,455,455,455
BEGIN DESCRIPTION:
Little Cottonwood Creek Trib 2_1 11.0
END DESCRIPTION:
XS GIS Cut Line= 3
      2666754.76      6891151.10      2665476.00      6891461.00
      2664246.07      6892123.32
#Sta/Elev= 30
  3684.1  439.07  3832.2  434.93  3888.6  434.63  3915.8  433.01  3991.5  432.20
  4053.2  429.86  4130.0  429.16  4213.6  426.93  4238.5  427.27  4361.9  425.37
  4413.4  423.59  4578.0  421.83  4907.3  422.00  5027.9  420.88  5028.1  420.38
  5031.9  420.88  5045.3  421.79  5051.8  423.83  5079.4  425.67  5133.7  425.54
  5170.2  426.96  5478.5  426.93  5494.7  426.31  5516.6  426.90  5576.7  426.27
  5664.3  427.32  5738.1  427.00  5988.0  431.04  6069.1  431.33  6396.8  435.65
#Mann=3,-1,0
  3684.1    0.05       0  5027.9    0.04       0  5031.9    0.05       0
Bank Sta=5027.9,5031.9
Exp/Cntr=0.3,0.1

Type RM Length L Ch R = 1,5550,495,495,495
BEGIN DESCRIPTION:
Little Cottonwood Creek Trib 2_1 10.0
END DESCRIPTION:
XS GIS Cut Line= 3
      2666676.61      6890491.38      2665326.00      6891061.00
      2664526.00      6891811.00
#Sta/Elev= 30
  3534.2  432.48  3849.5  429.97  3902.4  428.56  4084.7  428.13  4196.9  426.34
  4319.9  426.08  4343.6  425.19  4403.1  424.72  4425.6  423.53  4449.3  423.94
  4573.4  421.47  4708.2  420.49  4761.2  419.44  4770.1  418.51  4770.3  418.01
  4774.1  418.51  4784.8  419.70  4837.7  420.14  5021.3  419.72  5106.2  421.07
  5183.9  423.38  5318.3  425.13  5417.4  424.70  5474.1  423.62  5629.9  423.61
  5735.9  425.32  5771.0  426.65  5806.7  426.34  5941.0  428.10  6096.6  431.13
#Mann=3,-1,0
  3534.2    0.05       0  4770.1    0.04       0  4774.1    0.05       0
Bank Sta=4770.1,4774.1
Exp/Cntr=0.3,0.1

Type RM Length L Ch R = 1,5055,450,450,450
BEGIN DESCRIPTION:
Little Cottonwood Creek Trib 2_1 9.0
END DESCRIPTION:
XS GIS Cut Line= 3
      2665886.67      6890131.14      2664976.00      6890711.00
      2664376.03      6891310.97
#Sta/Elev= 30
  3920.4  426.56  4110.3  426.88  4122.7  426.44  4158.5  426.86  4217.6  426.17
  4419.3  425.80  4442.8  424.78  4465.0  424.80  4580.1  422.15  4689.3  420.62
  4731.7  418.41  4783.3  417.67  4798.5  416.90  4819.7  414.95  4825.6  413.54
  4832.0  412.86  4832.3  412.36  4835.8  412.36  4836.0  412.86  4840.9  415.09
  4846.8  415.91  4883.2  417.55  5127.3  416.71  5155.6  417.71  5169.7  417.42
  5424.3  418.59  5678.8  424.19  5735.4  425.91  5806.1  426.63  5848.5  428.01
#Mann=3,-1,0
  3920.4    0.05       0  4832.0    0.04       0  4836.0    0.05       0
Bank Sta=4832,4836
Exp/Cntr=0.3,0.1

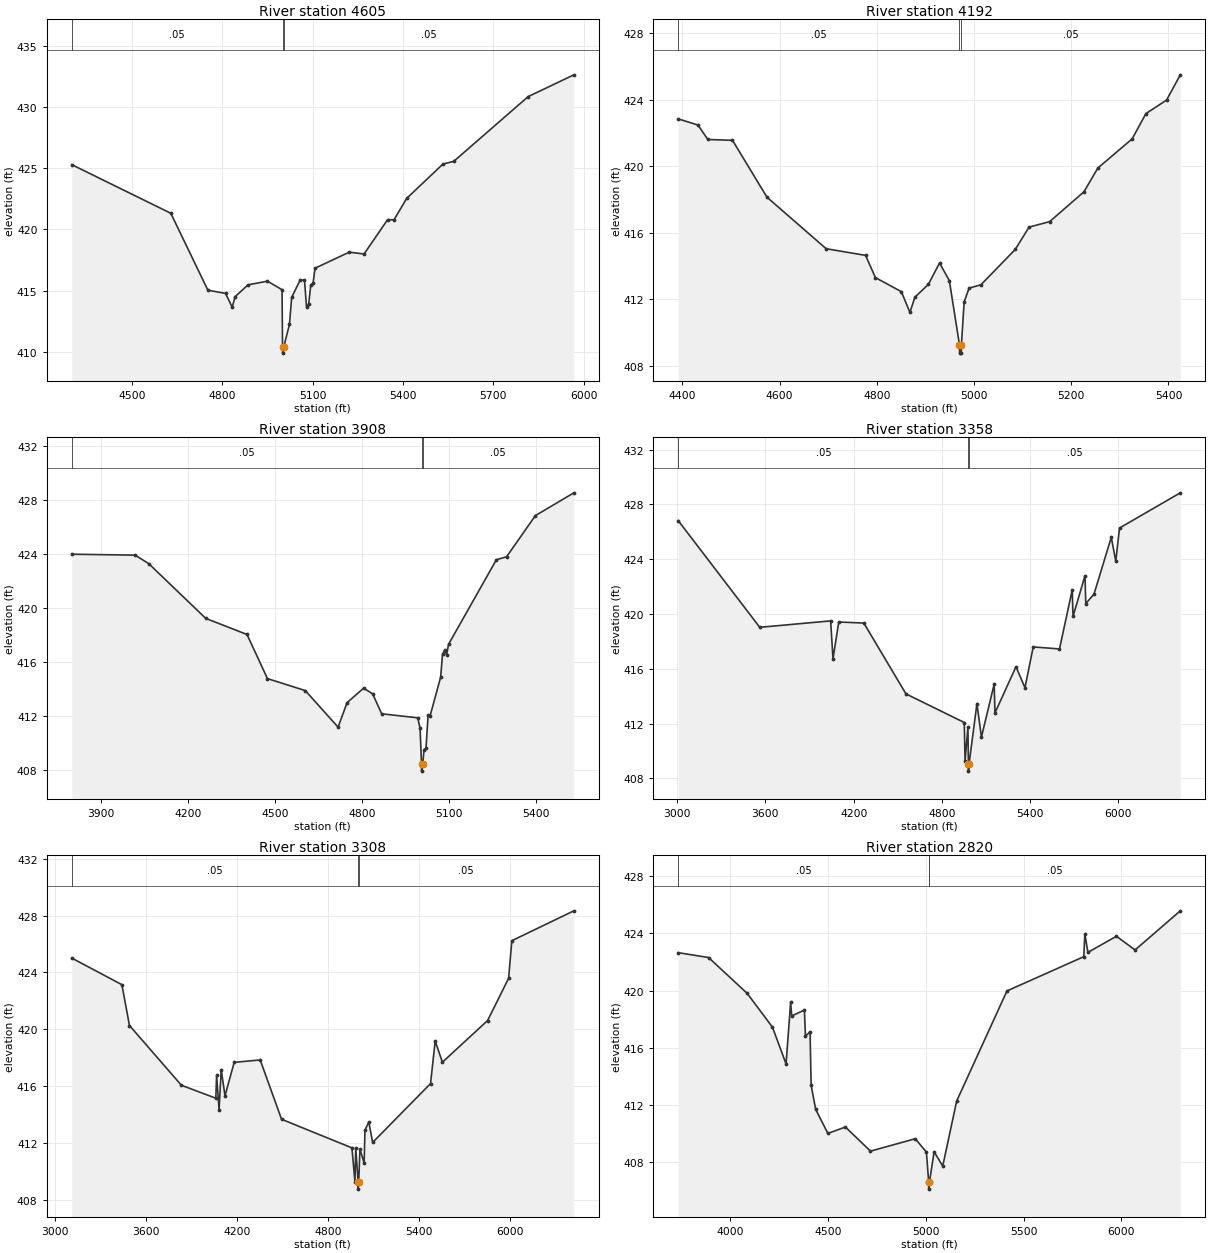
Type RM Length L Ch R = 1,4605,413,413,413
BEGIN DESCRIPTION:
Little Cottonwood Creek Trib 2_1 8.0
END DESCRIPTION:
XS GIS Cut Line= 3
      2665226.01      6890110.99      2664626.00      6890461.00
      2663963.90      6891172.84
#Sta/Elev= 30
  4300.4  425.29  4629.1  421.32  4752.3  415.03  4811.0  414.77  4833.0  413.64
  4842.5  414.50  4885.5  415.47  4950.0  415.77  4998.5  415.07  5000.1  410.39
  5000.4  409.89  5004.1  410.39  5023.1  412.24  5030.5  414.45  5058.8  415.87
  5073.0  415.84  5079.8  413.64  5087.1  413.94  5094.0  415.48  5101.3  415.58
  5108.1  416.83  5221.5  418.14  5270.8  417.99  5349.0  420.80  5370.0  420.78
  5412.5  422.54  5532.7  425.34  5568.4  425.56  5815.6  430.85  5967.2  432.63
#Mann=3,-1,0
  4300.4    0.05       0  5000.1    0.03       0  5004.1    0.05       0
Bank Sta=5000.1,5004.1
Exp/Cntr=0.3,0.1

Type RM Length L Ch R = 1,4192,284,284,284
BEGIN DESCRIPTION:
Little Cottonwood Creek Trib 2_1 7.0
END DESCRIPTION:
XS GIS Cut Line= 3
      2664926.04      6890110.99      2664326.00      6890211.00
      2664025.99      6890511.01
#Sta/Elev= 30
  4391.7  422.86  4432.3  422.49  4452.6  421.62  4503.3  421.57  4574.2  418.15
  4695.9  415.05  4777.0  414.65  4797.3  413.31  4850.5  412.47  4868.2  411.22
  4878.4  412.13  4906.2  412.91  4929.1  414.19  4949.3  413.13  4970.1  409.27
  4970.4  408.77  4973.9  408.77  4974.1  409.27  4979.7  411.85  4989.9  412.68
  5014.2  412.88  5084.9  415.01  5113.2  416.35  5155.6  416.68  5226.3  418.48
  5254.6  419.90  5325.3  421.66  5353.6  423.18  5396.0  423.99  5424.3  425.51
#Mann=3,-1,0
  4391.7    0.05       0  4970.1    0.03       0  4974.1    0.05       0
Bank Sta=4970.1,4974.1
Exp/Cntr=0.3,0.1

Type RM Length L Ch R = 1,3908,550,550,550
BEGIN DESCRIPTION:
Little Cottonwood Creek Trib 2_1 6.0
END DESCRIPTION:
XS GIS Cut Line= 3
      2665226.95      6889684.09      2664092.01      6890078.12
      2663677.43      6890408.95
#Sta/Elev= 30
  3798.6  424.00  4017.2  423.93  4064.2  423.30  4260.9  419.24  4403.0  418.05
  4473.5  414.78  4604.1  413.89  4717.2  411.18  4748.3  413.00  4805.2  414.07
  4836.4  413.65  4867.5  412.17  4992.0  411.87  5000.0  411.10  5005.0  408.42
  5005.2  407.92  5009.0  408.42  5013.4  409.45  5020.5  409.65  5027.8  412.09
  5034.2  411.99  5071.0  414.89  5077.4  416.57  5084.4  416.88  5091.8  416.56
  5098.2  417.32  5263.2  423.59  5298.4  423.81  5397.7  426.86  5530.4  428.55
#Mann=3,-1,0
  3798.6    0.05       0  5005.0    0.03       0  5009.0    0.05       0
Bank Sta=5005,5009
Exp/Cntr=0.3,0.1

Type RM Length L Ch R = 1,3358,50,50,50
BEGIN DESCRIPTION:
Mapping XS 40b97c20
END DESCRIPTION:
XS GIS Cut Line= 3
      2665990.80      6888881.16      2664133.19      6889579.93
      2662789.39      6890065.43
#Sta/Elev= 30
  3007.4  426.82  3561.8  419.03  4043.6  419.50  4059.6  416.73  4098.7  419.42
  4269.4  419.34  4555.6  414.17  4952.1  412.08  4957.4  409.28  4977.0  411.73
  4980.3  409.03  4980.6  408.53  4984.3  409.03  5038.2  413.46  5068.8  411.02
  5155.5  414.88  5160.8  412.78  5303.5  416.15  5364.8  414.62  5420.8  417.60
  5599.5  417.45  5686.2  421.77  5691.5  419.83  5772.9  422.80  5778.2  420.76
  5834.2  421.46  5951.5  425.60  5982.2  423.86  6007.5  426.28  6420.9  428.85
#Mann=3,-1,0
  3007.4    0.05       0  4980.3    0.03       0  4984.3    0.05       0
Bank Sta=4980.3,4984.3
Exp/Cntr=0.3,0.1

Type RM Length L Ch R = 1,3308,488,488,488
BEGIN DESCRIPTION:
Mapping XS c45abf9d
END DESCRIPTION:
XS GIS Cut Line= 3
      2665895.37      6888872.45      2664115.83      6889536.53
      2662792.08      6890018.29
#Sta/Elev= 30
  3111.5  425.01  3441.7  423.14  3491.6  420.27  3834.0  416.07  4060.5  415.16
  4065.8  416.76  4082.1  414.35  4096.1  417.17  4121.1  415.33  4181.7  417.68
  4352.9  417.85  4493.8  413.68  4957.4  411.67  4977.1  409.30  4982.4  411.69
  4998.1  409.27  4998.3  408.77  5002.1  409.27  5010.2  411.59  5038.0  410.60
  5043.3  412.91  5068.6  413.49  5093.8  412.05  5475.4  416.19  5506.0  419.18
  5553.5  417.69  5851.4  420.62  5989.8  423.59  6011.0  426.23  6419.6  428.33
#Mann=3,-1,0
  3111.5    0.05       0  4998.1    0.03       0  5002.1    0.05       0
Bank Sta=4998.1,5002.1
Exp/Cntr=0.3,0.1

Type RM Length L Ch R = 1,2820,731,731,731
BEGIN DESCRIPTION:
Little Cottonwood Creek Trib 2_1 4.0
END DESCRIPTION:
XS GIS Cut Line= 3
      2665238.27      6888557.34      2664076.00      6889061.00
      2662835.43      6889453.20
#Sta/Elev= 30
  3733.3  422.65  3888.4  422.31  4086.0  419.80  4215.3  417.43  4284.7  414.86
  4308.2  419.17  4313.6  418.22  4378.6  418.63  4384.0  416.80  4407.5  417.11
  4413.0  413.36  4436.4  411.67  4498.7  409.99  4588.2  410.44  4716.6  408.75
  4945.5  409.62  5002.6  408.68  5014.2  406.59  5014.4  406.09  5018.2  406.59
  5042.0  408.71  5086.0  407.70  5157.3  412.26  5414.5  419.97  5807.5  422.37
  5812.8  423.97  5828.5  422.67  5974.4  423.80  6069.8  422.84  6301.1  425.58
#Mann=3,-1,0
  3733.3    0.05       0  5014.2    0.03       0  5018.2    0.05       0
Bank Sta=5014.2,5018.2
Exp/Cntr=0.3,0.1

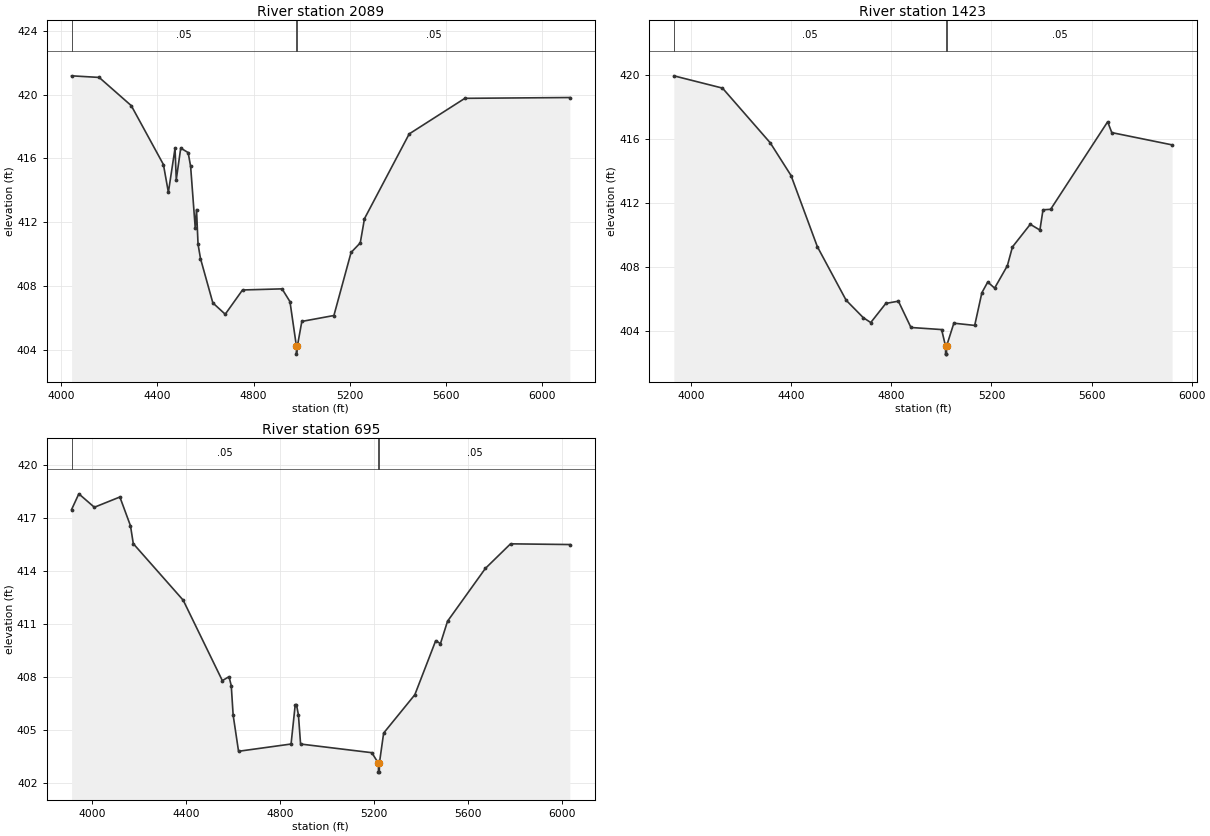
Type RM Length L Ch R = 1,2089,666,666,666
BEGIN DESCRIPTION:
Mapping XS ad4b03ba
END DESCRIPTION:
XS GIS Cut Line= 3
      2664807.63      6888175.43      2663849.34      6888404.58
      2662807.71      6888717.07
#Sta/Elev= 30
  4043.1  421.18  4157.9  421.08  4291.5  419.31  4425.2  415.62  4445.8  413.88
  4473.5  416.64  4478.6  414.67  4497.2  416.65  4528.0  416.37  4538.3  415.51
  4557.6  411.63  4562.8  412.80  4569.2  410.63  4579.4  409.73  4630.8  406.95
  4682.3  406.24  4754.2  407.76  4918.7  407.83  4951.6  407.03  4978.4  404.24
  4978.7  403.74  4982.4  404.24  5001.0  405.79  5134.4  406.16  5205.8  410.11
  5244.0  410.71  5261.6  412.23  5447.6  417.54  5679.2  419.77  6115.9  419.82
#Mann=3,-1,0
  4043.1    0.05       0  4978.4    0.03       0  4982.4    0.05       0
Bank Sta=4978.4,4982.4
Exp/Cntr=0.3,0.1

Type RM Length L Ch R = 1,1423,728,728,728
BEGIN DESCRIPTION:
Mapping XS a9dc9323
END DESCRIPTION:
XS GIS Cut Line= 3
      2664689.63      6887918.47      2663627.12      6887821.25
      2662719.15      6887994.52
#Sta/Elev= 30
  3930.6  419.97  4125.0  419.20  4315.8  415.77  4398.9  413.72  4504.0  409.26
  4619.1  405.90  4687.4  404.81  4717.5  404.50  4777.8  405.70  4828.0  405.84
  4878.2  404.19  5000.7  404.06  5016.4  403.02  5016.7  402.52  5020.2  402.52
  5020.4  403.02  5049.6  404.46  5132.9  404.32  5161.6  406.37  5185.0  407.04
  5212.5  406.66  5263.4  408.06  5283.7  409.24  5355.0  410.66  5393.5  410.30
  5405.9  411.57  5436.4  411.60  5664.3  417.09  5680.8  416.41  5921.9  415.64
#Mann=3,-1,0
  3930.6    0.05       0  5016.4    0.03       0  5020.4    0.05       0
Bank Sta=5016.4,5020.4
Exp/Cntr=0.3,0.1

Type RM Length L Ch R = 1,695,0,0,0
BEGIN DESCRIPTION:
Little Cottonwood Creek Trib 2_1 1.0
END DESCRIPTION:
XS GIS Cut Line= 3
      2664464.08      6887593.39      2663475.83      6887140.93
      2662449.18      6887266.49
#Sta/Elev= 30
  3913.1  417.46  3944.0  418.35  4010.0  417.59  4118.7  418.17  4163.9  416.54
  4175.8  415.53  4388.3  412.33  4554.9  407.78  4583.4  408.00  4592.9  407.49
  4600.9  405.83  4623.9  403.78  4847.5  404.19  4865.0  406.39  4870.5  406.42
  4878.8  405.84  4888.0  404.19  5191.2  403.70  5219.4  403.10  5219.7  402.60
  5223.2  402.60  5223.5  403.10  5241.6  404.81  5374.4  406.98  5463.3  410.04
  5483.4  409.87  5513.6  411.14  5674.8  414.13  5781.9  415.52  6034.3  415.48
#Mann=3,-1,0
  3913.1    0.05       0  5219.4    0.03       0  5223.5    0.05       0
Bank Sta=5219.4,5223.5
Exp/Cntr=0.3,0.1

Chan Stop Cuts=-1