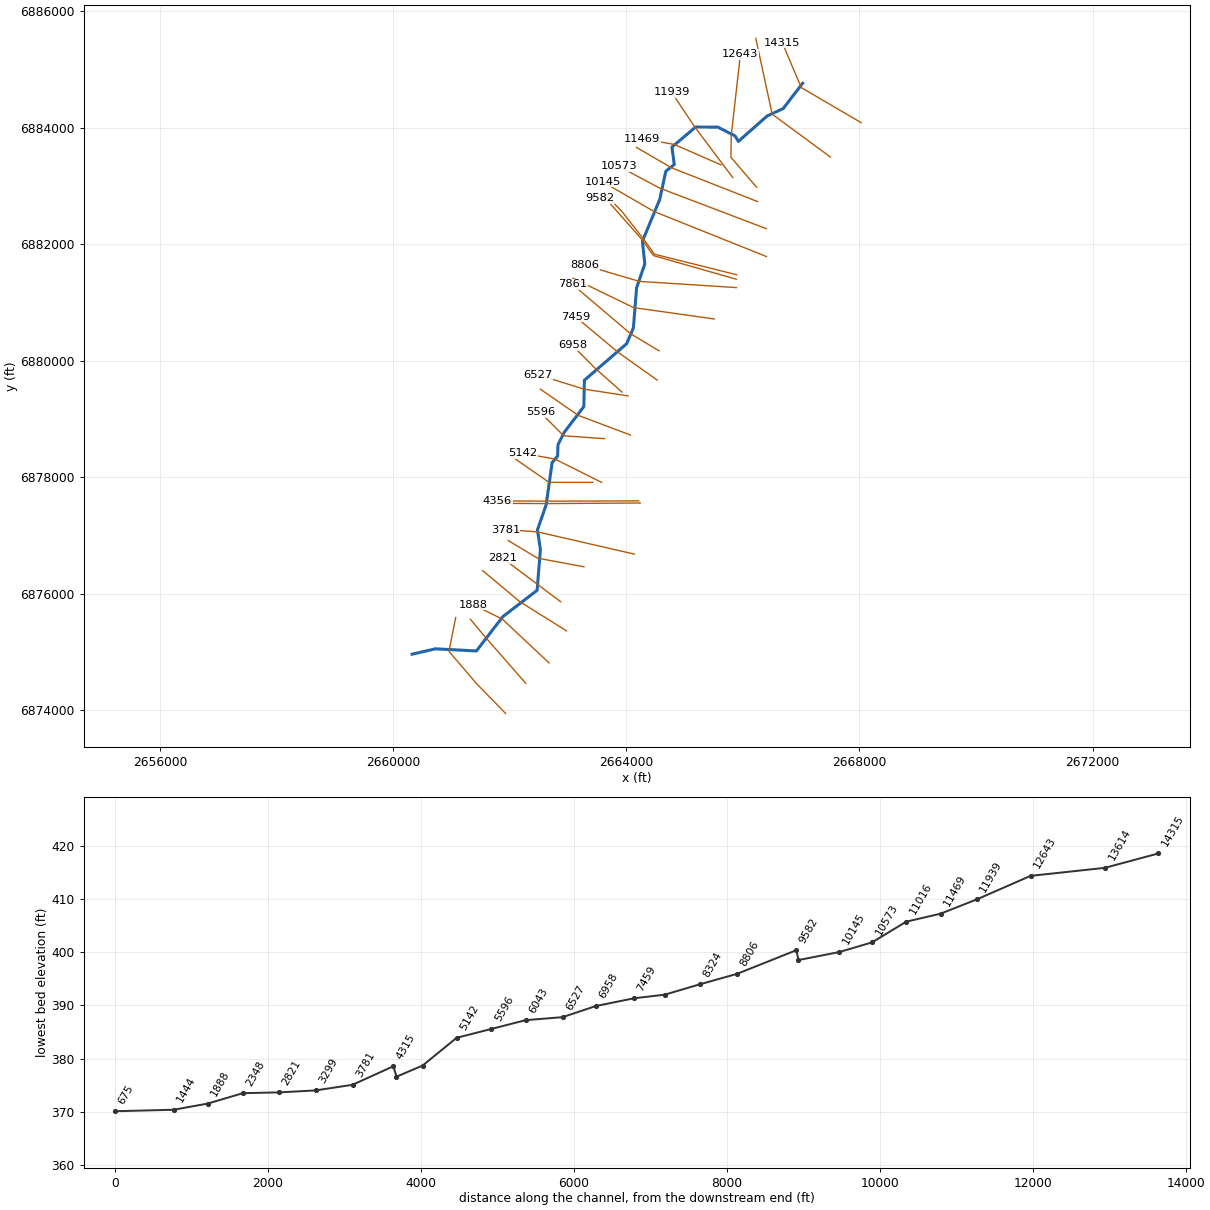
--- Little Cottonwood Creek Trib 3.prj (project) ---

Proj Title=Little Cottonwood Creek Trib 3 Base Level Engineering
Current Plan=p01
Default Exp/Contr=0.3,0.1
English Units
Geom File=g01
Flow File=f01
Plan File=p01
BEGIN DESCRIPTION:
Little Cottonwood Creek Trib 3
END DESCRIPTION:

--- Little Cottonwood Creek Trib 3.p01 (plan) ---

Plan Title=Multiple Run
Short Identifier=Multiple
Geom File=g01
Flow File=f01
Subcritical Flow
K Sum by GR= 0
Std Step Tol= 0.01
Critical Tol= 0.01
Num of Std Step Trials= 20
Max Error Tol= 0.3
Flow Tol Ratio= 0.001
Split Flow NTrial= 30
Split Flow Tol= 0.02
Split Flow Ratio= 0.02
Log Output Level= 0
Friction Slope Method= 1
Unsteady Friction Slope Method= 2
Unsteady Bridges Friction Slope Method= 1
Parabolic Critical Depth
Global Vel Dist=  1 , 1 , 1
Global Log Level= 0
CheckData=True
Encroach Param= -1, 0, 0, 0
BEGIN DESCRIPTION:
Multiple Run
END DESCRIPTION:

--- Little Cottonwood Creek Trib 3.f01 (steady flow) ---

Flow Title=Multiple
Number of Profiles=7
Profile Names=10-year,25-year,50-year,1pct_min,100-year,1pct_plu,500-year
River Rch & RM= Little Cottonwoo,Reach-1,14315
     403     529     629     371     741    1478    1027
River Rch & RM= Little Cottonwoo,Reach-1,12643
     672     912    1108     667    1331    2656    1922
River Rch & RM= Little Cottonwoo,Reach-1,10145
    1004    1386    1702    1035    2064    4119    3039
River Rch & RM= Little Cottonwoo,Reach-1,1888
    1027    1420    1745    1061    2117    4223    3119
Boundary for River Rch & Prof#=Little Cottonwoo,Reach-1,1
Up Type=0
Dn Type=3
Dn Slope=0.005
Boundary for River Rch & Prof#=Little Cottonwoo,Reach-1,2
Up Type=0
Dn Type=3
Dn Slope=0.005
Boundary for River Rch & Prof#=Little Cottonwoo,Reach-1,3
Up Type=0
Dn Type=3
Dn Slope=0.005
Boundary for River Rch & Prof#=Little Cottonwoo,Reach-1,4
Up Type=0
Dn Type=3
Dn Slope=0.005
Boundary for River Rch & Prof#=Little Cottonwoo,Reach-1,5
Up Type=0
Dn Type=3
Dn Slope=0.005
Boundary for River Rch & Prof#=Little Cottonwoo,Reach-1,6
Up Type=0
Dn Type=3
Dn Slope=0.005
Boundary for River Rch & Prof#=Little Cottonwoo,Reach-1,7
Up Type=0
Dn Type=3
Dn Slope=0.005

--- Little Cottonwood Creek Trib 3.g01 (geometry) ---

Geom Title=Existing Conditions

River Reach=Little Cottonwoo,Reach-1
Reach XY= 30
      2667026.00      6884761.00      2666692.68      6884327.64
      2666416.32      6884200.24      2665923.92      6883763.94
      2665867.97      6883857.90      2665570.14      6884008.94
      2665191.36      6884010.99      2664783.80      6883667.21
      2664824.04      6883366.88      2664679.08      6883252.69
      2664573.76      6882766.93      2664277.20      6882050.49
      2664318.44      6881661.00      2664177.22      6881250.50
      2664122.25      6880562.55      2664006.37      6880290.84
      2663281.46      6879663.45      2663272.25      6879212.55
      2662931.52      6878763.43      2662828.07      6878555.14
      2662822.26      6878362.53      2662727.93      6878249.05
      2662624.80      6877521.50      2662476.52      6877095.78
      2662526.81      6876755.97      2662470.53      6876058.55
      2661881.62      6875605.38      2661428.70      6875016.36
      2660726.00      6875053.44      2660326.00      6874961.00

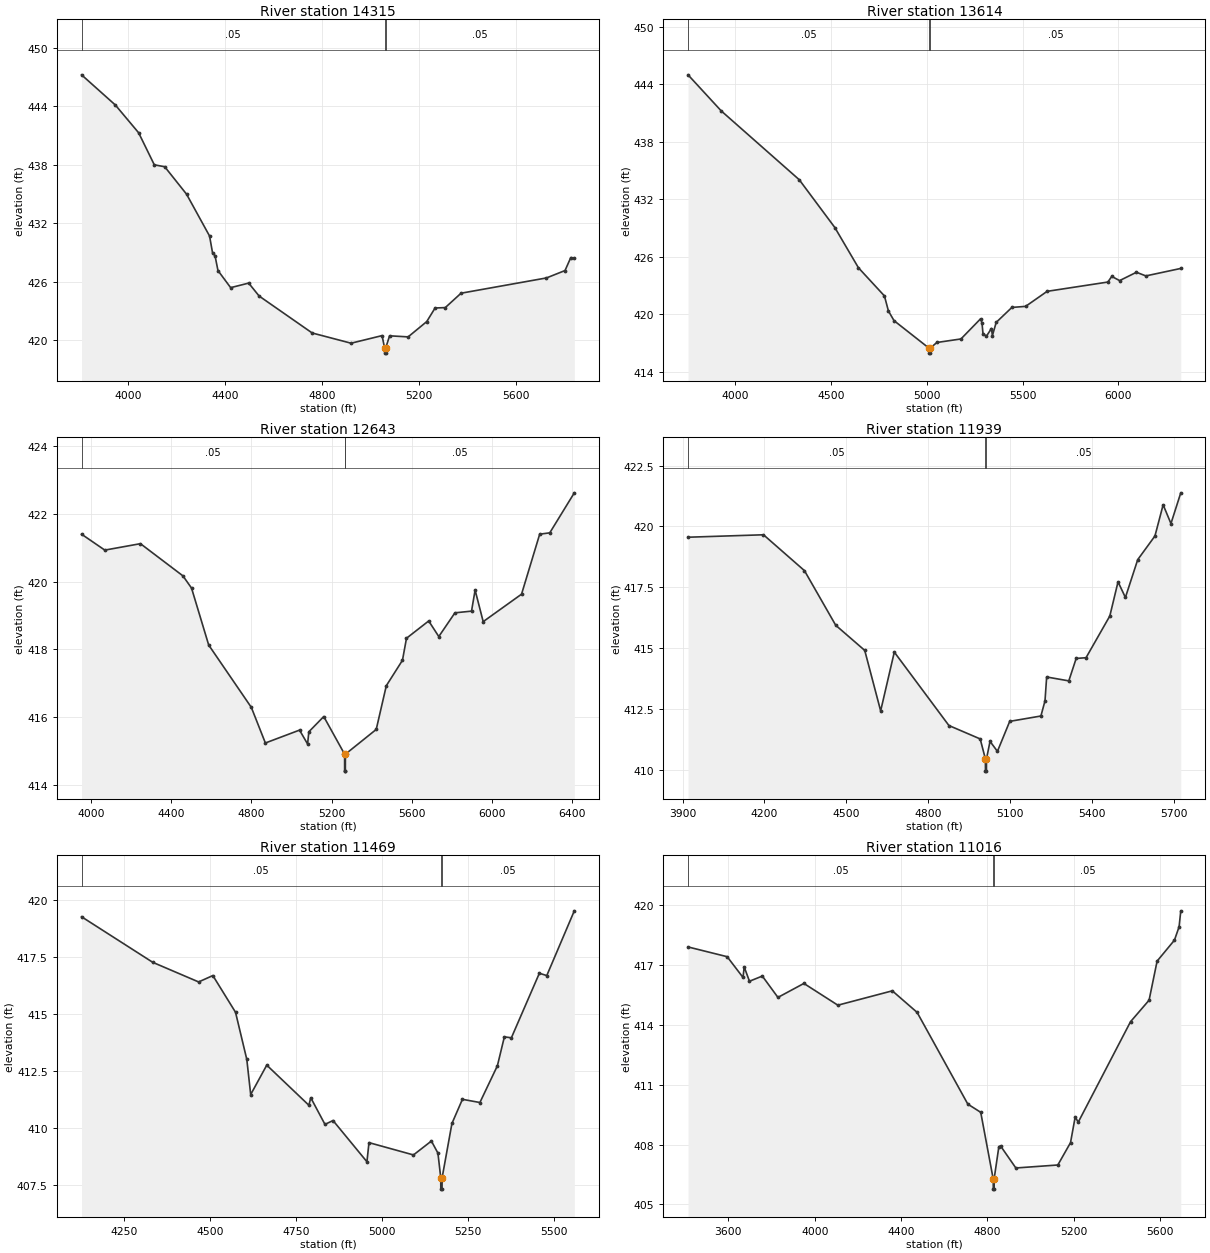
Type RM Length L Ch R = 1,14315,701,701,701
BEGIN DESCRIPTION:
Little Cottonwood Creek Trib 3 27.0
END DESCRIPTION:
XS GIS Cut Line= 3
      2668031.37      6884085.39      2667002.90      6884687.57
      2666675.99      6885461.02
#Sta/Elev= 30
  3808.2  447.25  3947.8  444.14  4043.6  441.29  4108.1  438.00  4151.1  437.80
  4241.1  434.98  4335.9  430.68  4348.5  428.92  4358.4  428.66  4370.6  427.13
  4422.9  425.37  4497.2  425.84  4540.2  424.51  4759.1  420.71  4919.4  419.66
  5047.1  420.44  5057.8  419.14  5058.1  418.64  5061.6  418.64  5061.8  419.14
  5078.1  420.42  5154.6  420.31  5231.2  421.88  5265.7  423.28  5307.7  423.32
  5372.8  424.80  5724.9  426.37  5801.4  427.13  5825.1  428.46  5839.7  428.40
#Mann=3,-1,0
  3808.2    0.05       0  5057.8    0.04       0  5061.8    0.05       0
Bank Sta=5057.8,5061.8
Exp/Cntr=0.3,0.1

Type RM Length L Ch R = 1,13614,971,971,971
BEGIN DESCRIPTION:
Mapping XS 50c015bd
END DESCRIPTION:
XS GIS Cut Line= 3
      2667503.62      6883495.09      2666503.59      6884231.23
      2666222.33      6885533.34
#Sta/Elev= 30
  3752.1  444.97  3925.8  441.20  4333.1  434.02  4519.0  429.03  4642.3  424.83
  4778.1  421.89  4798.9  420.32  4828.2  419.31  5012.1  416.42  5012.3  415.92
  5015.8  415.92  5016.1  416.42  5051.7  417.03  5177.8  417.40  5280.1  419.50
  5287.7  419.07  5292.9  417.94  5310.8  417.69  5337.0  418.49  5342.1  417.75
  5361.9  419.13  5443.8  420.69  5515.4  420.80  5627.9  422.37  5945.1  423.34
  5965.5  423.93  6006.5  423.49  6094.4  424.36  6143.7  423.98  6326.0  424.76
#Mann=3,-1,0
  3752.1    0.05       0  5012.1    0.04       0  5016.1    0.05       0
Bank Sta=5012.1,5016.1
Exp/Cntr=0.3,0.1

Type RM Length L Ch R = 1,12643,704,704,704
BEGIN DESCRIPTION:
Little Cottonwood Creek Trib 3 26.0
END DESCRIPTION:
XS GIS Cut Line= 4
      2666236.20      6882977.79      2665795.26      6883491.64
      2665801.21      6883861.08      2665958.45      6885262.49
#Sta/Elev= 30
  3953.4  421.40  4069.3  420.93  4247.0  421.12  4458.9  420.17  4501.7  419.81
  4587.3  418.13  4799.9  416.29  4869.9  415.24  5040.2  415.62  5080.4  415.21
  5086.6  415.57  5160.9  416.02  5264.9  414.91  5265.1  414.41  5268.6  414.41
  5268.9  414.91  5422.6  415.64  5472.9  416.93  5553.4  417.68  5573.5  418.33
  5684.2  418.84  5734.5  418.38  5815.0  419.08  5897.7  419.13  5915.6  419.75
  5955.9  418.82  6147.1  419.63  6237.6  421.40  6287.9  421.44  6410.2  422.62
#Mann=3,-1,0
  3953.4    0.05       0  5264.9    0.04       0  5268.9    0.05       0
Bank Sta=5264.9,5268.9
Exp/Cntr=0.3,0.1

Type RM Length L Ch R = 1,11939,470,470,470
BEGIN DESCRIPTION:
Little Cottonwood Creek Trib 3 25.0
END DESCRIPTION:
XS GIS Cut Line= 3
      2665826.53      6883144.39      2665176.00      6884011.00
      2664776.01      6884610.99
#Sta/Elev= 30
  3920.1  419.56  4196.5  419.66  4346.5  418.19  4461.1  415.95  4567.3  414.92
  4625.6  412.44  4675.6  414.85  4875.6  411.84  4990.2  411.29  5009.2  410.47
  5009.5  409.97  5013.0  409.97  5013.2  410.47  5026.2  411.19  5053.3  410.78
  5098.3  412.01  5212.5  412.23  5227.5  412.85  5233.6  413.83  5314.7  413.67
  5341.7  414.59  5377.8  414.62  5464.9  416.33  5495.0  417.73  5522.0  417.09
  5567.1  418.64  5630.2  419.61  5660.2  420.89  5688.8  420.12  5724.8  421.38
#Mann=3,-1,0
  3920.1    0.05       0  5009.2    0.03       0  5013.2    0.05       0
Bank Sta=5009.2,5013.2
Exp/Cntr=0.3,0.1

Type RM Length L Ch R = 1,11469,453,453,453
BEGIN DESCRIPTION:
Little Cottonwood Creek Trib 3 24.0
END DESCRIPTION:
XS GIS Cut Line= 3
      2665625.99      6883361.00      2664826.00      6883711.00
      2664276.02      6883811.00
#Sta/Elev= 30
  4126.2  419.25  4333.2  417.25  4466.5  416.39  4507.8  416.67  4573.7  415.06
  4606.5  412.99  4617.8  411.45  4664.5  412.74  4786.9  410.98  4792.4  411.31
  4833.7  410.14  4857.1  410.31  4955.7  408.50  4961.6  409.34  5090.9  408.80
  5143.0  409.41  5162.0  408.88  5170.2  407.80  5170.4  407.30  5173.9  407.30
  5174.2  407.80  5202.7  410.18  5233.2  411.24  5284.0  411.10  5334.8  412.71
  5355.1  413.98  5375.5  413.94  5456.8  416.77  5478.4  416.67  5558.4  419.51
#Mann=3,-1,0
  4126.2    0.05       0  5170.2    0.03       0  5174.2    0.05       0
Bank Sta=5170.2,5174.2
Exp/Cntr=0.3,0.1

Type RM Length L Ch R = 1,11016,443,443,443
BEGIN DESCRIPTION:
Little Cottonwood Creek Trib 3 23.0
END DESCRIPTION:
XS GIS Cut Line= 3
      2666253.61      6882731.22      2664776.00      6883311.00
      2664176.01      6883661.00
#Sta/Elev= 30
  3413.2  417.91  3594.6  417.42  3667.9  416.38  3673.3  416.91  3697.7  416.19
  3757.3  416.45  3829.6  415.38  3949.8  416.08  4107.1  414.99  4359.2  415.71
  4474.1  414.63  4709.0  410.03  4768.7  409.62  4826.6  406.27  4826.9  405.77
  4830.4  405.77  4830.6  406.27  4852.7  407.90  4860.8  407.93  4931.4  406.83
  5125.8  406.98  5184.5  408.10  5206.0  409.38  5220.5  409.13  5462.3  414.16
  5548.3  415.24  5585.5  417.20  5665.8  418.25  5687.3  418.92  5695.1  419.72
#Mann=3,-1,0
  3413.2    0.05       0  4826.6    0.03       0  4830.6    0.05       0
Bank Sta=4826.6,4830.6
Exp/Cntr=0.3,0.1

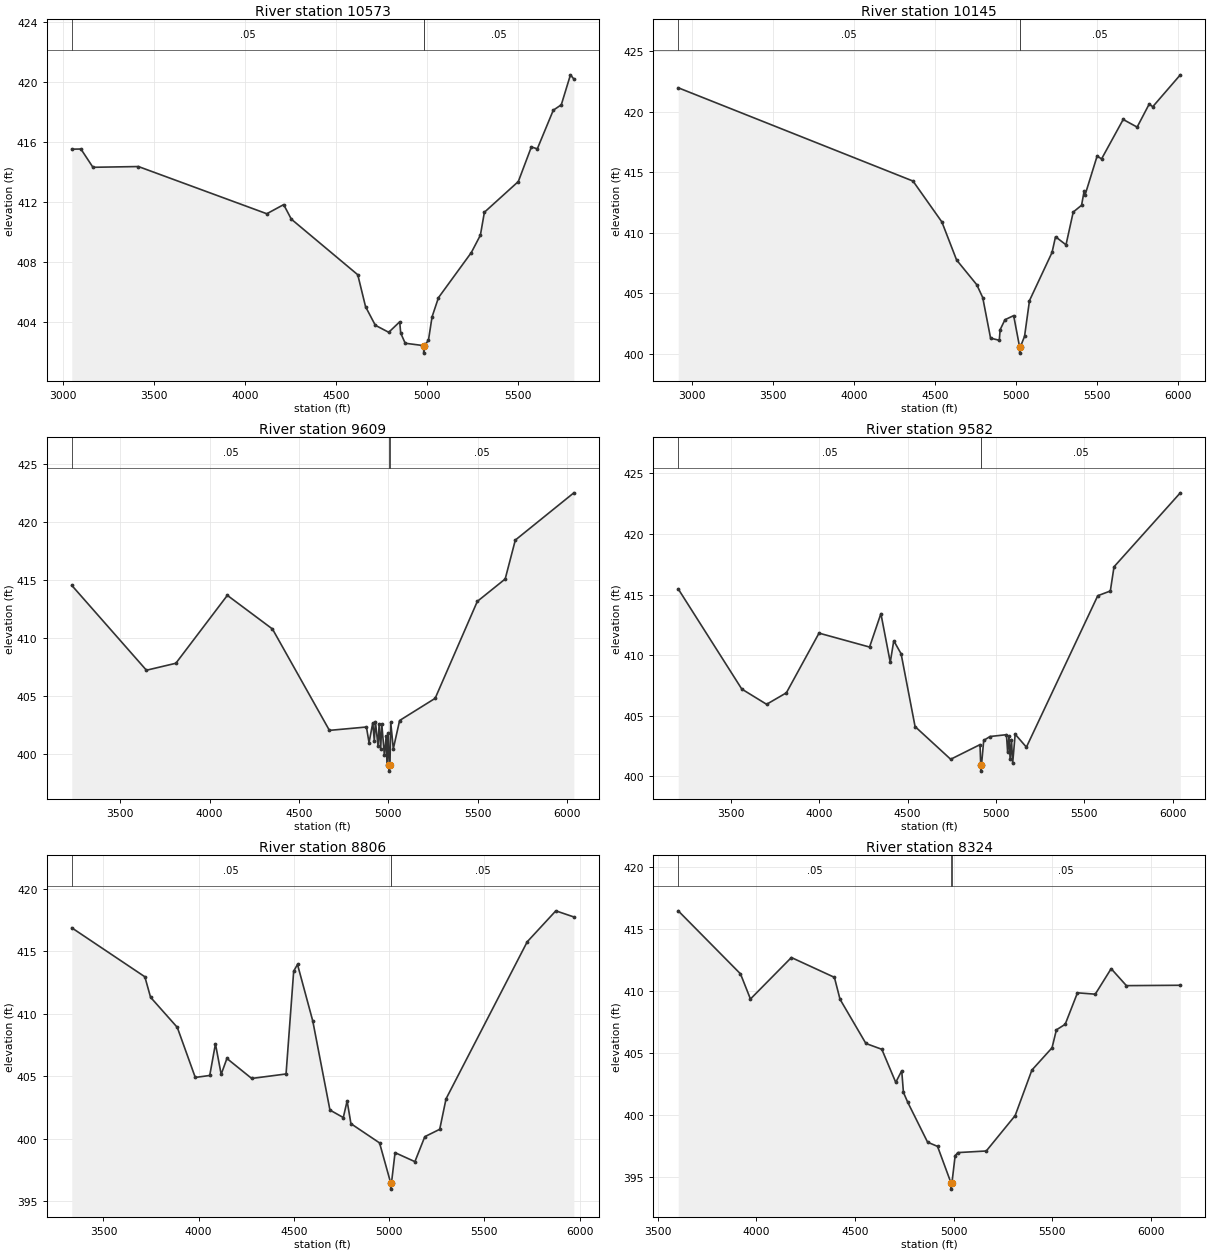
Type RM Length L Ch R = 1,10573,428,428,428
BEGIN DESCRIPTION:
Little Cottonwood Creek Trib 3 22.0
END DESCRIPTION:
XS GIS Cut Line= 3
      2666402.92      6882265.94      2664576.00      6882961.00
      2663869.62      6883338.09
#Sta/Elev= 30
  3049.4  415.50  3099.6  415.51  3165.6  414.29  3415.2  414.34  4119.8  411.19
  4212.3  411.80  4254.3  410.83  4618.9  407.12  4661.7  404.99  4715.2  403.75
  4788.9  403.28  4849.2  403.98  4854.5  403.23  4879.3  402.55  4980.7  402.39
  4980.9  401.89  4984.7  402.39  5006.9  402.75  5026.7  404.31  5061.8  405.59
  5242.1  408.60  5291.9  409.76  5313.9  411.29  5500.1  413.34  5571.7  415.65
  5604.2  415.52  5692.0  418.10  5735.9  418.46  5786.2  420.46  5804.8  420.18
#Mann=3,-1,0
  3049.4    0.05       0  4980.7    0.03       0  4984.7    0.05       0
Bank Sta=4980.7,4984.7
Exp/Cntr=0.3,0.1

Type RM Length L Ch R = 1,10145,536,536,536
BEGIN DESCRIPTION:
Little Cottonwood Creek Trib 3 21.0
END DESCRIPTION:
XS GIS Cut Line= 3
      2666406.41      6881786.76      2664476.00      6882561.00
      2663593.86      6883071.51
#Sta/Elev= 30
  2915.5  422.00  4364.6  414.29  4542.9  410.91  4633.6  407.77  4758.4  405.72
  4795.0  404.66  4843.4  401.31  4897.2  401.13  4902.6  402.01  4932.2  402.83
  4986.0  403.17  5022.7  400.57  5023.1  400.07  5026.9  400.57  5053.2  401.46
  5083.6  404.41  5222.8  408.39  5244.4  409.69  5309.0  409.02  5353.6  411.73
  5405.1  412.29  5420.9  413.46  5426.6  413.14  5501.2  416.36  5528.5  416.12
  5662.0  419.38  5748.1  418.75  5822.7  420.66  5844.2  420.43  6014.6  423.07
#Mann=3,-1,0
  2915.5    0.05       0  5022.7    0.04       0  5026.9    0.05       0
Bank Sta=5022.7,5026.9
Exp/Cntr=0.3,0.1

Type RM Length L Ch R = 1,9609,27,27,27
BEGIN DESCRIPTION:
Mapping XS 5c3e6daf
END DESCRIPTION:
XS GIS Cut Line= 5
      2665895.96      6881474.28      2664482.76      6881828.45
      2664305.67      6882074.98      2663937.62      6882547.20
      2663625.14      6882873.57
#Sta/Elev= 30
  3228.4  414.55  3646.4  407.24  3811.1  407.84  4099.4  413.69  4352.1  410.79
  4670.9  402.06  4878.1  402.35  4892.8  401.00  4913.7  402.71  4922.3  401.16
  4928.4  402.81  4943.1  400.72  4949.3  402.62  4957.9  400.46  4964.0  402.62
  4978.8  399.91  4988.8  401.59  4993.3  399.11  4999.6  401.83  5005.6  399.05
  5006.0  398.55  5009.9  399.05  5014.1  402.76  5028.6  400.47  5063.9  402.91
  5262.9  404.82  5499.0  413.17  5655.0  415.10  5711.7  418.45  6039.4  422.52
#Mann=3,-1,0
  3228.4    0.05       0  5005.6    0.04       0  5009.9    0.05       0
Bank Sta=5005.6,5009.9
Exp/Cntr=0.3,0.1

Type RM Length L Ch R = 1,9582,776,776,776
BEGIN DESCRIPTION:
Mapping XS 37ac0136
END DESCRIPTION:
XS GIS Cut Line= 5
      2665889.03      6881397.88      2664465.39      6881804.14
      2664270.95      6882078.45      2663701.51      6882720.81
      2663549.86      6882789.74
#Sta/Elev= 30
  3201.9  415.46  3561.6  407.19  3702.1  405.93  3814.0  406.88  3998.7  411.81
  4284.8  410.66  4349.0  413.42  4401.9  409.40  4421.8  411.18  4463.4  410.10
  4542.4  404.09  4743.9  401.39  4910.0  402.60  4914.0  400.91  4914.4  400.41
  4918.3  400.91  4930.9  402.95  4966.6  403.27  5059.6  403.42  5066.3  401.97
  5073.8  403.28  5080.5  401.39  5088.0  403.01  5094.7  401.06  5108.9  403.46
  5172.5  402.39  5576.4  414.90  5647.5  415.29  5668.4  417.29  6043.6  423.40
#Mann=3,-1,0
  3201.9    0.05       0  4914.0    0.04       0  4918.3    0.05       0
Bank Sta=4914,4918.3
Exp/Cntr=0.3,0.1

Type RM Length L Ch R = 1,8806,482,482,482
BEGIN DESCRIPTION:
Little Cottonwood Creek Trib 3 18.0
END DESCRIPTION:
XS GIS Cut Line= 3
      2665889.00      6881254.66      2664226.00      6881361.00
      2663295.26      6881634.87
#Sta/Elev= 30
  3333.6  416.87  3717.4  412.95  3747.4  411.31  3887.7  408.90  3982.2  404.89
  4058.1  405.05  4088.1  407.58  4118.2  405.14  4148.3  406.41  4278.5  404.81
  4458.9  405.17  4499.0  413.40  4519.0  413.94  4599.2  409.41  4689.4  402.28
  4759.5  401.68  4779.6  403.01  4799.6  401.19  4949.9  399.65  5008.3  396.45
  5008.6  395.95  5012.6  396.45  5031.3  398.87  5135.5  398.15  5187.6  400.15
  5265.8  400.74  5299.1  403.18  5725.3  415.75  5875.6  418.23  5970.2  417.74
#Mann=3,-1,0
  3333.6    0.05       0  5008.3    0.04       0  5012.6    0.05       0
Bank Sta=5008.3,5012.6
Exp/Cntr=0.3,0.1

Type RM Length L Ch R = 1,8324,463,463,463
BEGIN DESCRIPTION:
Little Cottonwood Creek Trib 3 17.0
END DESCRIPTION:
XS GIS Cut Line= 3
      2665508.83      6880715.60      2664126.00      6880911.00
      2663090.28      6881413.15
#Sta/Elev= 30
  3603.0  416.47  3918.9  411.38  3969.4  409.35  4177.1  412.70  4395.4  411.10
  4423.9  409.33  4555.2  405.76  4636.0  405.29  4706.7  402.62  4737.0  403.56
  4745.7  401.81  4767.3  401.02  4868.3  397.79  4918.8  397.45  4987.1  394.50
  4987.6  394.00  4991.8  394.50  5008.1  396.70  5021.8  396.95  5166.1  397.08
  5312.7  399.94  5397.4  403.61  5499.7  405.41  5521.9  406.86  5566.5  407.31
  5628.7  409.85  5719.0  409.74  5799.7  411.80  5877.0  410.43  6150.6  410.46
#Mann=3,-1,0
  3603.0    0.05       0  4987.1    0.04       0  4991.8    0.05       0
Bank Sta=4987.1,4991.8
Exp/Cntr=0.3,0.1

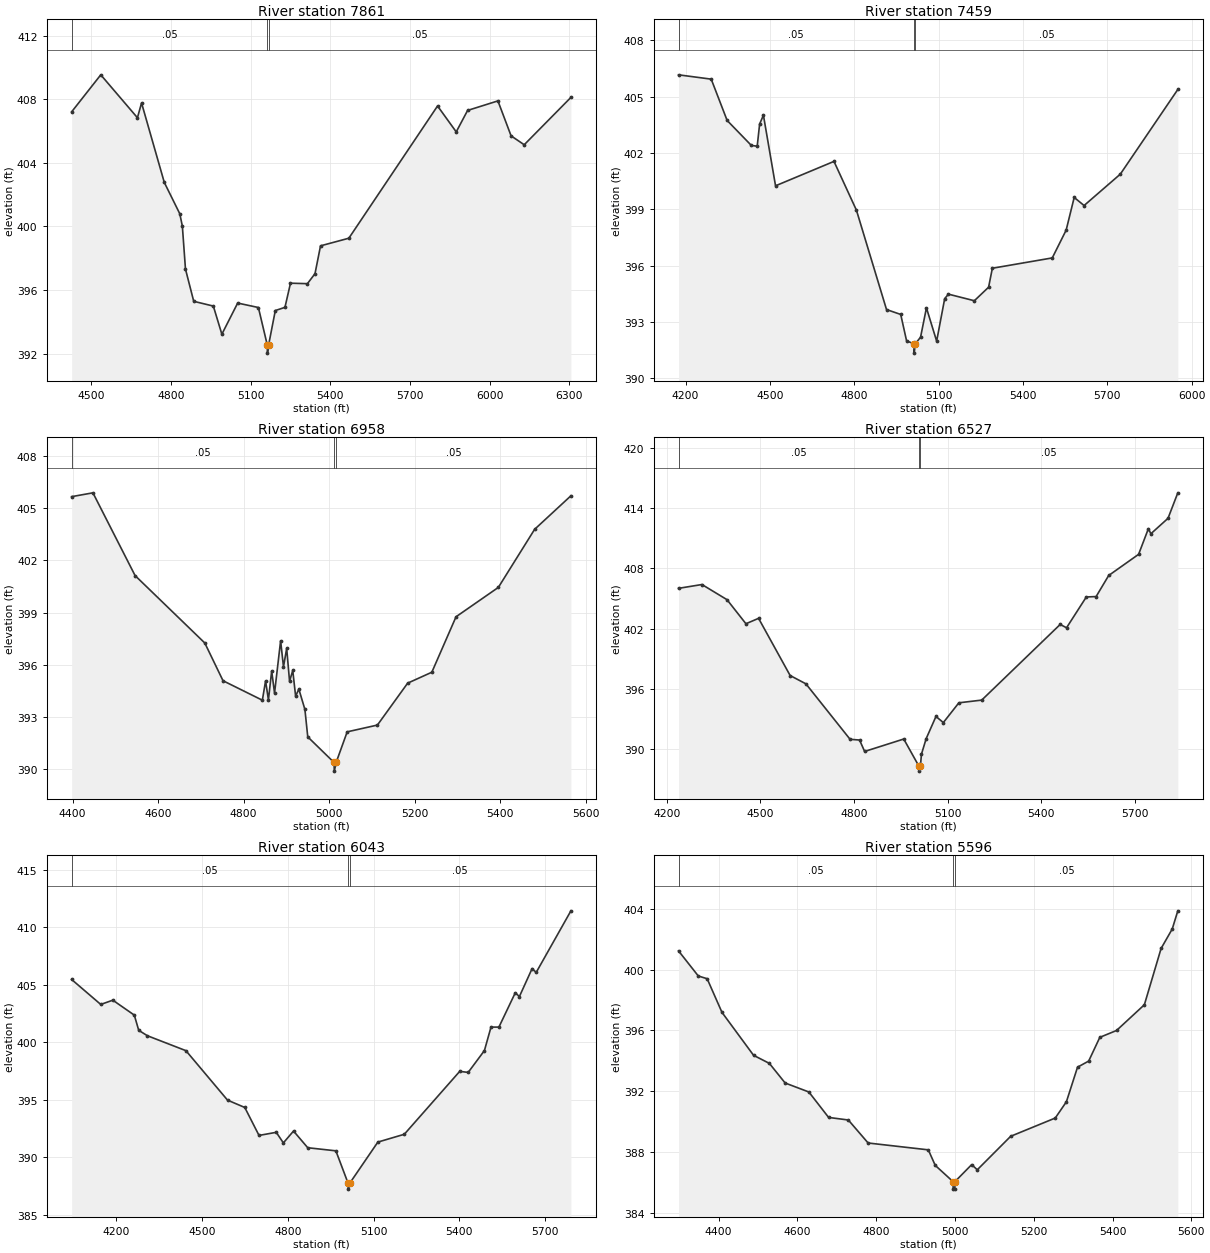
Type RM Length L Ch R = 1,7861,402,402,402
BEGIN DESCRIPTION:
Little Cottonwood Creek Trib 3 16.0
END DESCRIPTION:
XS GIS Cut Line= 3
      2664563.53      6880168.70      2664076.00      6880461.00
      2663076.52      6881309.33
#Sta/Elev= 30
  4426.7  407.21  4536.4  409.54  4674.4  406.84  4689.9  407.77  4775.5  402.77
  4833.8  400.80  4843.5  400.02  4855.2  397.32  4886.3  395.29  4960.1  394.99
  4992.2  393.22  5051.7  395.18  5129.7  394.90  5163.3  392.53  5163.8  392.03
  5168.0  392.53  5193.4  394.71  5229.7  394.91  5250.5  396.43  5314.2  396.40
  5342.8  397.03  5363.6  398.78  5470.2  399.26  5804.1  407.58  5874.4  405.95
  5917.2  407.30  6031.3  407.90  6080.9  405.70  6130.3  405.14  6306.1  408.12
#Mann=3,-1,0
  4426.7    0.05       0  5163.3    0.04       0  5168.0    0.05       0
Bank Sta=5163.3,5168
Exp/Cntr=0.3,0.1

Type RM Length L Ch R = 1,7459,501,501,501
BEGIN DESCRIPTION:
Little Cottonwood Creek Trib 3 15.0
END DESCRIPTION:
XS GIS Cut Line= 3
      2664532.25      6879666.11      2663859.49      6880143.96
      2663129.78      6880753.66
#Sta/Elev= 30
  4174.8  406.17  4291.1  405.94  4347.7  403.74  4433.8  402.41  4454.7  402.37
  4463.3  403.55  4476.8  404.02  4519.9  400.26  4727.8  401.56  4807.7  398.96
  4914.7  393.67  4965.2  393.41  4986.1  392.00  5012.6  391.85  5013.1  391.35
  5017.3  391.85  5035.8  392.20  5056.7  393.76  5093.0  391.99  5121.6  394.25
  5134.9  394.49  5227.1  394.14  5277.8  394.86  5291.2  395.87  5504.3  396.42
  5553.7  397.90  5582.3  399.64  5617.5  399.21  5746.3  400.88  5950.9  405.39
#Mann=3,-1,0
  4174.8    0.05       0  5012.6    0.04       0  5017.3    0.05       0
Bank Sta=5012.6,5017.3
Exp/Cntr=0.3,0.1

Type RM Length L Ch R = 1,6958,431,431,431
BEGIN DESCRIPTION:
Little Cottonwood Creek Trib 3 14.0
END DESCRIPTION:
XS GIS Cut Line= 3
      2663926.00      6879461.00      2663476.00      6879861.00
      2663075.97      6880261.03
#Sta/Elev= 30
  4397.9  405.67  4447.7  405.89  4546.3  401.13  4709.4  397.25  4752.0  395.08
  4844.0  393.96  4851.5  395.07  4858.2  393.98  4865.8  395.64  4872.5  394.37
  4886.7  397.38  4893.4  395.88  4900.9  396.94  4907.6  395.05  4915.1  395.67
  4921.8  394.19  4929.3  394.60  4943.5  393.43  4950.2  391.85  5011.6  390.38
  5012.3  389.88  5016.6  390.38  5042.4  392.14  5113.1  392.53  5183.8  394.94
  5240.4  395.57  5297.0  398.76  5396.0  400.45  5480.8  403.79  5565.7  405.72
#Mann=3,-1,0
  4397.9    0.05       0  5011.6    0.04       0  5016.6    0.05       0
Bank Sta=5011.6,5016.6
Exp/Cntr=0.3,0.1

Type RM Length L Ch R = 1,6527,484,484,484
BEGIN DESCRIPTION:
Little Cottonwood Creek Trib 3 13.0
END DESCRIPTION:
XS GIS Cut Line= 3
      2664029.65      6879395.29      2663276.00      6879511.00
      2662476.03      6879760.99
#Sta/Elev= 30
  4237.5  406.02  4312.6  406.40  4392.9  404.89  4453.6  402.49  4494.1  403.03
  4595.3  397.33  4645.9  396.50  4787.5  390.97  4817.9  390.90  4834.1  389.76
  4959.5  391.00  5008.0  388.30  5008.6  387.80  5013.0  388.30  5016.2  389.48
  5031.4  391.04  5062.8  393.25  5086.4  392.64  5136.2  394.61  5209.5  394.88
  5461.0  402.42  5481.4  402.09  5544.8  405.16  5576.2  405.20  5616.5  407.30
  5712.4  409.41  5743.8  411.97  5751.7  411.46  5806.7  413.00  5838.1  415.54
#Mann=3,-1,0
  4237.5    0.05       0  5008.0    0.04       0  5013.0    0.05       0
Bank Sta=5008,5013
Exp/Cntr=0.3,0.1

Type RM Length L Ch R = 1,6043,447,447,447
BEGIN DESCRIPTION:
Little Cottonwood Creek Trib 3 12.0
END DESCRIPTION:
XS GIS Cut Line= 3
      2664071.32      6878723.41      2663176.00      6879061.00
      2662526.02      6879510.99
#Sta/Elev= 30
  4043.4  405.46  4145.3  403.29  4187.6  403.66  4262.8  402.36  4278.2  401.04
  4308.4  400.57  4443.4  399.27  4589.0  394.97  4649.4  394.33  4699.2  391.90
  4759.6  392.17  4784.4  391.25  4820.0  392.28  4869.7  390.83  4968.2  390.56
  5011.1  387.73  5011.9  387.23  5016.4  387.73  5115.1  391.32  5207.7  392.00
  5401.6  397.47  5431.3  397.38  5488.1  399.28  5511.1  401.32  5538.8  401.32
  5596.2  404.31  5610.4  403.97  5655.0  406.41  5669.2  406.07  5790.8  411.43
#Mann=3,-1,0
  4043.4    0.05       0  5011.1    0.04       0  5016.4    0.05       0
Bank Sta=5011.1,5016.4
Exp/Cntr=0.3,0.1

Type RM Length L Ch R = 1,5596,454,454,454
BEGIN DESCRIPTION:
Little Cottonwood Creek Trib 3 11.0
END DESCRIPTION:
XS GIS Cut Line= 3
      2663626.03      6878661.00      2662926.00      6878711.00
      2662526.00      6879111.00
#Sta/Elev= 30
  4298.2  401.23  4348.4  399.58  4370.9  399.40  4408.5  397.19  4488.7  394.37
  4528.8  393.84  4568.9  392.55  4629.1  391.96  4679.2  390.29  4729.3  390.12
  4779.5  388.61  4932.3  388.16  4949.9  387.14  4994.8  386.08  4995.6  385.58
  4999.5  385.58  5000.2  386.08  5042.4  387.19  5056.6  386.85  5141.4  389.05
  5254.6  390.25  5282.9  391.32  5311.1  393.59  5339.4  393.99  5367.7  395.55
  5410.1  396.00  5480.8  397.69  5523.3  401.39  5551.6  402.67  5565.7  403.86
#Mann=3,-1,0
  4298.2    0.05       0  4994.8    0.03       0  5000.2    0.05       0
Bank Sta=4994.8,5000.2
Exp/Cntr=0.3,0.1

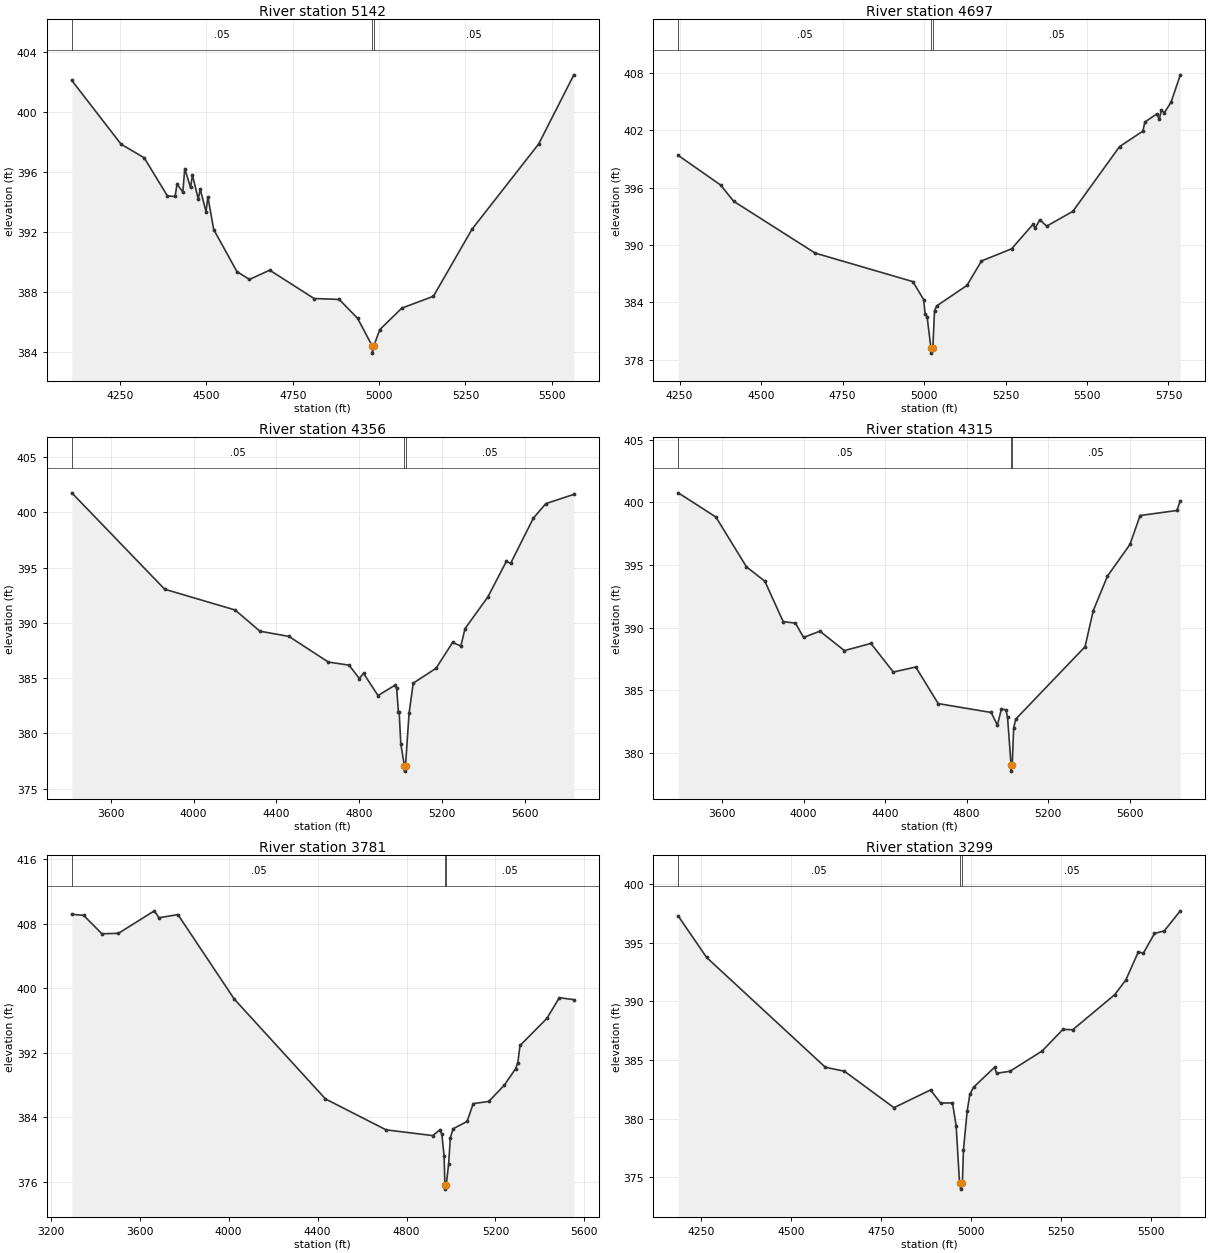
Type RM Length L Ch R = 1,5142,445,445,445
BEGIN DESCRIPTION:
Little Cottonwood Creek Trib 3 10.0
END DESCRIPTION:
XS GIS Cut Line= 3
      2663576.04      6877910.98      2662776.00      6878311.00
      2662225.99      6878411.00
#Sta/Elev= 30
  4110.3  402.09  4252.9  397.84  4320.0  396.93  4387.1  394.39  4409.4  394.35
  4415.0  395.18  4431.8  394.65  4437.4  396.21  4454.1  394.95  4459.7  395.78
  4476.5  394.18  4482.1  394.84  4498.9  393.35  4504.5  394.32  4521.2  392.15
  4588.3  389.35  4624.6  388.82  4683.3  389.44  4811.9  387.55  4884.6  387.49
  4937.7  386.23  4979.7  384.41  4980.5  383.91  4985.2  384.41  5002.0  385.48
  5065.8  386.91  5157.2  387.70  5269.0  392.17  5462.2  397.86  5563.8  402.46
#Mann=3,-1,0
  4110.3    0.05       0  4979.7    0.03       0  4985.2    0.05       0
Bank Sta=4979.7,4985.2
Exp/Cntr=0.3,0.1

Type RM Length L Ch R = 1,4697,341,341,341
BEGIN DESCRIPTION:
Little Cottonwood Creek Trib 3 9.0
END DESCRIPTION:
XS GIS Cut Line= 3
      2663425.95      6877911.00      2662676.00      6877911.00
      2662026.02      6878360.99
#Sta/Elev= 30
  4245.8  399.39  4375.8  396.29  4415.8  394.59  4665.8  389.16  4965.8  386.17
  4998.8  384.28  5003.2  382.81  5009.3  382.51  5021.3  379.18  5022.2  378.68
  5026.9  379.18  5032.2  383.13  5039.0  383.63  5131.6  385.77  5176.2  388.33
  5268.7  389.61  5334.3  392.17  5340.4  391.74  5355.2  392.65  5376.2  391.98
  5456.6  393.53  5599.8  400.31  5671.5  401.94  5677.5  402.88  5713.3  403.72
  5722.1  403.19  5728.2  404.16  5737.0  403.84  5757.9  404.96  5786.3  407.83
#Mann=3,-1,0
  4245.8    0.05       0  5021.3    0.03       0  5026.9    0.05       0
Bank Sta=5021.3,5026.9
Exp/Cntr=0.3,0.1

Type RM Length L Ch R = 1,4356,41,41,41
BEGIN DESCRIPTION:
Mapping XS df417997
END DESCRIPTION:
XS GIS Cut Line= 3
      2664214.48      6877593.20      2662633.80      6877588.00
      2661790.51      6877593.20
#Sta/Elev= 30
  3411.7  401.77  3860.2  393.05  4200.2  391.17  4320.2  389.25  4460.2  388.78
  4650.2  386.46  4750.2  386.18  4800.2  384.97  4820.2  385.44  4890.2  383.43
  4970.2  384.34  4980.2  384.09  4988.8  381.91  4992.4  381.91  5000.2  379.07
  5017.4  377.09  5018.2  376.59  5023.0  377.09  5040.2  381.83  5060.2  384.55
  5170.2  385.89  5250.2  388.23  5290.2  387.91  5310.2  389.48  5420.2  392.34
  5510.2  395.58  5530.2  395.38  5640.2  399.48  5700.2  400.79  5835.7  401.63
#Mann=3,-1,0
  3411.7    0.05       0  5017.4    0.03       0  5023.0    0.05       0
Bank Sta=5017.4,5023
Exp/Cntr=0.3,0.1

Type RM Length L Ch R = 1,4315,534,534,534
BEGIN DESCRIPTION:
Mapping XS 0bf40472
END DESCRIPTION:
XS GIS Cut Line= 3
      2664240.60      6877556.75      2662636.40      6877546.33
      2661779.05      6877551.53
#Sta/Elev= 30
  3385.8  400.76  3570.4  398.83  3720.4  394.85  3810.4  393.71  3900.4  390.48
  3960.4  390.36  4000.4  389.22  4080.4  389.72  4200.4  388.17  4330.4  388.74
  4440.4  386.46  4550.4  386.86  4660.4  383.94  4920.4  383.23  4950.4  382.22
  4970.4  383.51  4992.7  383.44  5000.4  382.84  5017.6  379.05  5018.5  378.55
  5023.2  379.05  5030.4  381.99  5040.4  382.70  5380.4  388.48  5420.4  391.35
  5490.4  394.12  5600.4  396.64  5650.4  398.95  5830.5  399.35  5847.4  400.13
#Mann=3,-1,0
  3385.8    0.05       0  5017.6    0.03       0  5023.2    0.05       0
Bank Sta=5017.6,5023.2
Exp/Cntr=0.3,0.1

Type RM Length L Ch R = 1,3781,482,482,482
BEGIN DESCRIPTION:
Little Cottonwood Creek Trib 3 7.0
END DESCRIPTION:
XS GIS Cut Line= 3
      2664138.09      6876679.59      2662476.00      6877061.00
      2661924.61      6877100.58
#Sta/Elev= 30
  3294.3  409.19  3347.7  409.06  3429.8  406.77  3504.3  406.83  3665.8  409.62
  3686.3  408.76  3771.8  409.15  4024.9  398.67  4435.3  386.26  4708.1  382.42
  4917.5  381.71  4948.3  382.38  4958.6  381.93  4968.8  379.21  4972.6  375.56
  4973.6  375.06  4978.5  375.56  4989.3  378.20  4997.0  381.46  5009.6  382.56
  5072.1  383.46  5099.9  385.68  5170.0  385.95  5240.2  387.99  5290.3  390.02
  5300.4  390.75  5310.4  392.90  5430.7  396.25  5487.1  398.83  5552.4  398.59
#Mann=3,-1,0
  3294.3    0.05       0  4972.6    0.05       0  4978.5    0.05       0
Bank Sta=4972.6,4978.5
Exp/Cntr=0.3,0.1

Type RM Length L Ch R = 1,3299,478,478,478
BEGIN DESCRIPTION:
Little Cottonwood Creek Trib 3 6.0
END DESCRIPTION:
XS GIS Cut Line= 3
      2663276.01      6876461.00      2662476.00      6876611.00
      2661976.04      6876910.98
#Sta/Elev= 30
  4185.6  397.27  4264.5  393.74  4595.1  384.38  4647.7  384.05  4785.9  380.94
  4887.6  382.45  4915.6  381.33  4948.7  381.35  4958.9  379.39  4968.2  374.60
  4970.3  374.50  4971.3  374.00  4976.2  374.50  4979.2  377.33  4989.4  380.62
  4997.0  382.08  5007.3  382.68  5065.6  384.38  5071.5  383.87  5108.4  384.04
  5197.8  385.76  5256.1  387.61  5283.3  387.58  5399.9  390.56  5431.0  391.82
  5466.0  394.22  5479.6  394.09  5510.7  395.78  5537.9  396.00  5582.6  397.71
#Mann=3,-1,0
  4185.6    0.05       0  4970.3    0.05       0  4976.2    0.05       0
Bank Sta=4970.3,4976.2
Exp/Cntr=0.3,0.1

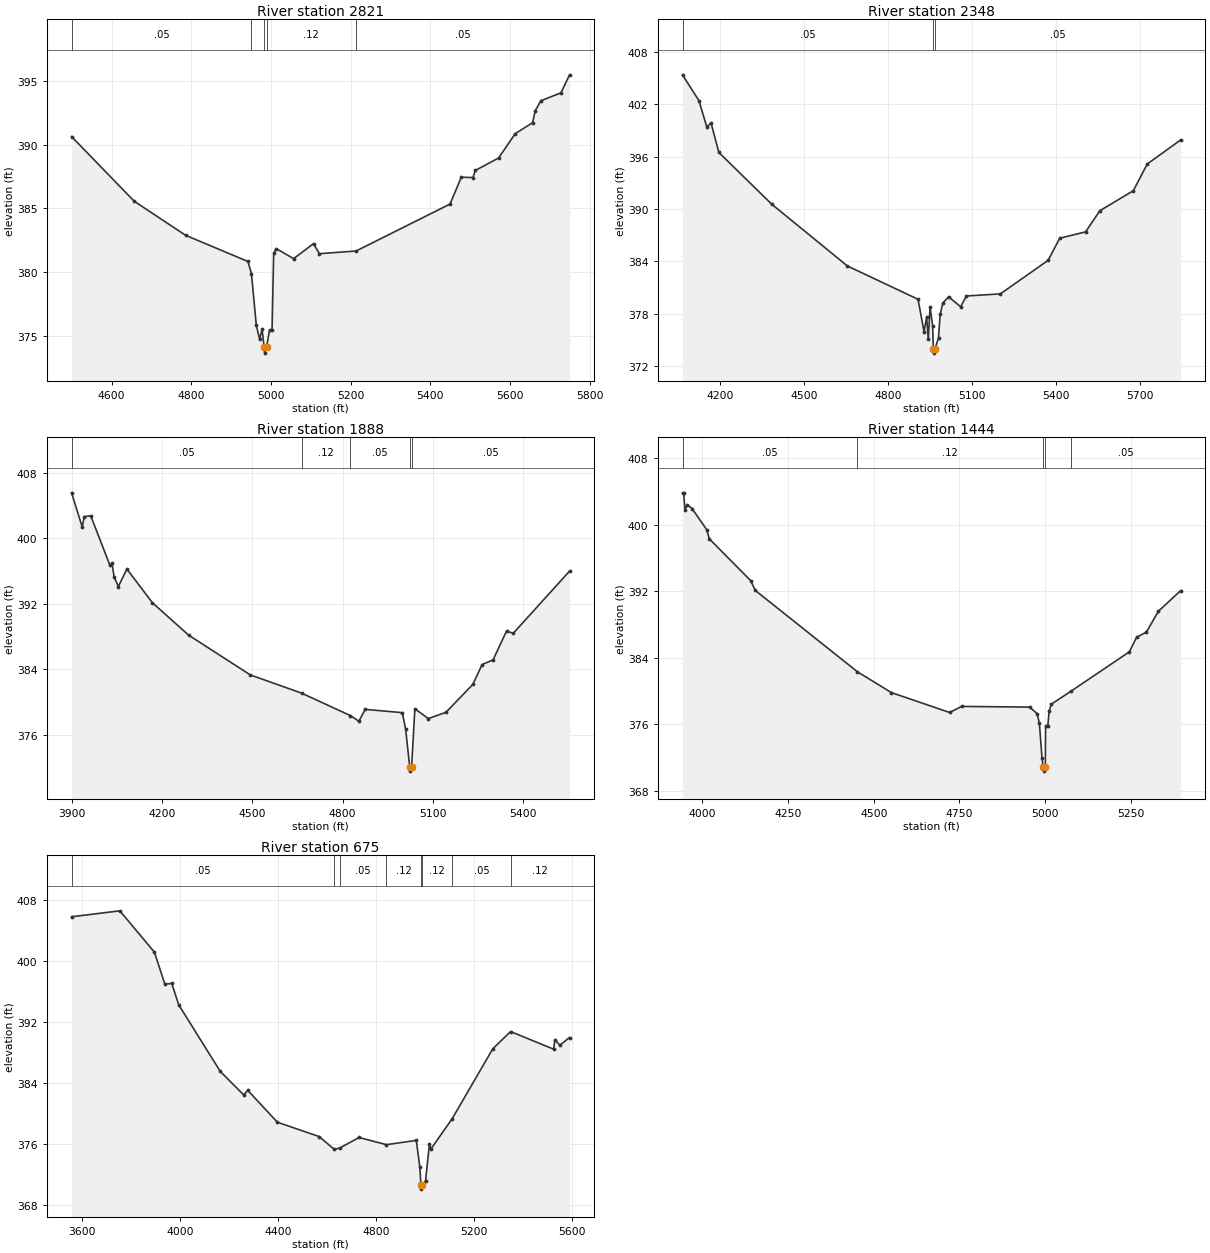
Type RM Length L Ch R = 1,2821,473,473,473
BEGIN DESCRIPTION:
Little Cottonwood Creek Trib 3 5.0
END DESCRIPTION:
XS GIS Cut Line= 3
      2662876.02      6875860.98      2662476.00      6876161.00
      2661876.02      6876610.98
#Sta/Elev= 30
  4499.6  390.64  4656.9  385.56  4786.1  382.88  4942.3  380.83  4951.1  379.88
  4963.2  375.84  4971.5  374.72  4977.8  375.49  4983.0  374.13  4984.0  373.63
  4989.1  374.13  4996.5  375.45  5002.8  375.45  5006.9  381.48  5013.2  381.84
  5056.9  381.05  5106.9  382.23  5121.5  381.44  5213.7  381.65  5449.6  385.34
  5477.8  387.45  5506.9  387.42  5513.2  387.98  5571.5  388.96  5613.2  390.87
  5656.9  391.73  5663.2  392.66  5677.8  393.46  5727.8  394.07  5749.6  395.49
#Mann=5,-1,0
  4499.6    0.05       0  4951.1    0.12       0  4983.0    0.07       0
  4989.1    0.12       0  5213.7    0.05       0
Bank Sta=4983,4989.1
Exp/Cntr=0.3,0.1

Type RM Length L Ch R = 1,2348,460,460,460
BEGIN DESCRIPTION:
Little Cottonwood Creek Trib 3 4.0
END DESCRIPTION:
XS GIS Cut Line= 3
      2662975.99      6875361.01      2662176.00      6875861.00
      2661534.84      6876396.73
#Sta/Elev= 30
  4064.7  405.38  4123.6  402.41  4151.4  399.41  4166.7  399.86  4194.4  396.49
  4383.1  390.56  4653.7  383.47  4906.1  379.65  4927.3  375.95  4936.7  377.60
  4942.6  375.10  4949.1  378.77  4958.0  376.64  4960.8  373.98  4961.8  373.48
  4966.9  373.98  4979.2  375.26  4985.1  377.92  4994.5  379.22  5015.2  379.93
  5058.2  378.80  5079.0  380.03  5200.0  380.27  5370.5  384.11  5412.2  386.65
  5504.6  387.38  5555.3  389.80  5675.1  392.10  5724.8  395.16  5843.6  397.91
#Mann=3,-1,0
  4064.7    0.05       0  4960.8    0.03       0  4966.9    0.05       0
Bank Sta=4960.8,4966.9
Exp/Cntr=0.3,0.1

Type RM Length L Ch R = 1,1888,444,444,444
BEGIN DESCRIPTION:
Little Cottonwood Creek Trib 3 3.0
END DESCRIPTION:
XS GIS Cut Line= 3
      2662676.01      6874811.00      2661876.00      6875561.00
      2661376.01      6875811.00
#Sta/Elev= 30
  3898.8  405.59  3934.2  401.41  3941.1  402.67  3962.5  402.78  4026.1  396.74
  4033.4  396.96  4040.2  395.29  4054.4  394.12  4082.7  396.26  4167.7  392.13
  4287.9  388.17  4493.0  383.30  4663.9  381.06  4825.2  378.33  4854.0  377.63
  4875.0  379.08  4998.2  378.68  5009.4  376.67  5023.0  372.02  5024.0  371.52
  5029.2  372.02  5040.1  379.16  5084.8  377.95  5143.5  378.72  5233.0  382.15
  5263.7  384.57  5300.1  385.14  5344.8  388.67  5367.1  388.39  5554.4  396.01
#Mann=5,-1,0
  3898.8    0.05       0  4663.9    0.12       0  4825.2    0.05       0
  5023.0    0.03       0  5029.2    0.05       0
Bank Sta=5023,5029.2
Exp/Cntr=0.3,0.1

Type RM Length L Ch R = 1,1444,769,769,769
BEGIN DESCRIPTION:
Little Cottonwood Creek Trib 3 2.0
END DESCRIPTION:
XS GIS Cut Line= 3
      2662275.98      6874461.03      2661576.00      6875261.00
      2661326.00      6875561.01
#Sta/Elev= 30
  3942.0  403.82  3945.3  403.82  3949.1  401.75  3955.7  402.40  3970.0  401.92
  4012.7  399.39  4020.3  398.29  4140.8  393.27  4154.6  392.08  4452.7  382.30
  4551.8  379.80  4721.7  377.41  4756.8  378.14  4955.2  378.06  4977.0  377.26
  4983.6  376.12  4991.2  371.96  4994.7  370.86  4995.8  370.36  5001.0  370.86
  5001.7  375.78  5008.2  375.78  5012.1  377.61  5018.6  378.41  5077.3  380.01
  5246.4  384.71  5267.3  386.46  5295.9  387.07  5331.1  389.59  5395.5  392.05
#Mann=5,-1,0
  3942.0    0.05       0  4452.7    0.12       0  4994.7    0.07       0
  5001.0    0.12       0  5077.3    0.05       0
Bank Sta=4994.7,5001
Exp/Cntr=0.3,0.1

Type RM Length L Ch R = 1,675,0,0,0
BEGIN DESCRIPTION:
Little Cottonwood Creek Trib 3 1.0
END DESCRIPTION:
XS GIS Cut Line= 4
      2661928.91      6873945.23      2661438.48      6874448.67
      2660956.71      6875010.98      2661073.90      6875590.15
#Sta/Elev= 30
  3556.7  405.79  3753.8  406.57  3895.2  401.15  3937.7  396.95  3966.0  397.05
  3994.3  394.25  4164.0  385.52  4259.5  382.44  4276.7  383.02  4397.4  378.85
  4567.6  376.98  4630.2  375.28  4652.6  375.48  4731.1  376.85  4842.8  375.91
  4964.9  376.47  4979.2  372.97  4983.6  370.58  4984.7  370.08  4990.0  370.58
  5002.6  371.17  5018.5  376.01  5023.6  375.30  5111.5  379.32  5277.2  388.48
  5349.9  390.74  5525.7  388.43  5530.8  389.68  5551.0  388.95  5590.9  389.96
#Mann=8,-1,0
  3556.7    0.05       0  4630.2    0.12       0  4652.6    0.05       0
  4842.8    0.12       0  4983.6    0.07       0  4990.0    0.12       0
  5111.5    0.05       0  5349.9    0.12       0
Bank Sta=4983.6,4990
Exp/Cntr=0.3,0.1

Chan Stop Cuts=-1