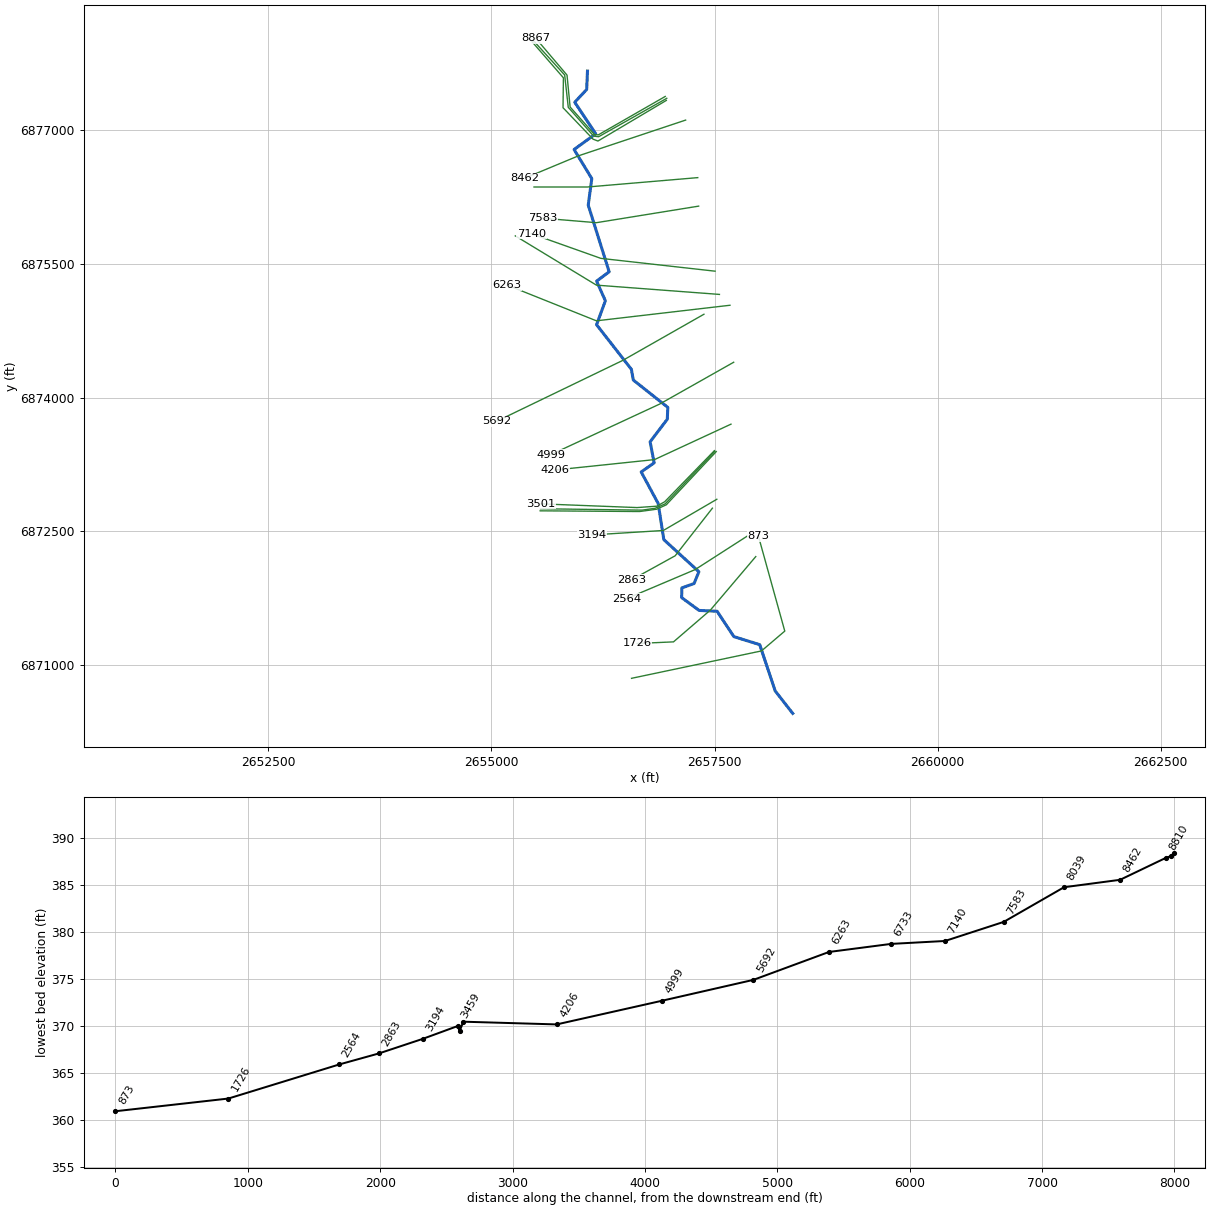
--- Little Cottonwood Creek Trib 4.prj (project) ---

Proj Title=Little Cottonwood Creek Trib 4 Base Level Engineering
Current Plan=p01
Default Exp/Contr=0.3,0.1
English Units
Geom File=g01
Flow File=f01
Plan File=p01
BEGIN DESCRIPTION:
Little Cottonwood Creek Trib 4
END DESCRIPTION:

--- Little Cottonwood Creek Trib 4.p01 (plan) ---

Plan Title=Multiple Run
Short Identifier=Multiple
Geom File=g01
Flow File=f01
Subcritical Flow
K Sum by GR= 0
Std Step Tol= 0.01
Critical Tol= 0.01
Num of Std Step Trials= 20
Max Error Tol= 0.3
Flow Tol Ratio= 0.001
Split Flow NTrial= 30
Split Flow Tol= 0.02
Split Flow Ratio= 0.02
Log Output Level= 0
Friction Slope Method= 1
Unsteady Friction Slope Method= 2
Unsteady Bridges Friction Slope Method= 1
Parabolic Critical Depth
Global Vel Dist=  1 , 1 , 1
Global Log Level= 0
CheckData=True
Encroach Param= -1, 0, 0, 0
BEGIN DESCRIPTION:
Multiple Run
END DESCRIPTION:

--- Little Cottonwood Creek Trib 4.f01 (steady flow) ---

Flow Title=Multiple
Number of Profiles=7
Profile Names=10-year,25-year,50-year,1pct_min,100-year,1pct_plu,500-year
River Rch & RM= Little Cottonwoo,Reach-1,8867
     598     794     949     562    1122    2239    1568
River Rch & RM= Little Cottonwoo,Reach-1,2863
     634     845    1013     601    1200    2394    1684
Boundary for River Rch & Prof#=Little Cottonwoo,Reach-1,1
Up Type=0
Dn Type=3
Dn Slope=0.005
Boundary for River Rch & Prof#=Little Cottonwoo,Reach-1,2
Up Type=0
Dn Type=3
Dn Slope=0.005
Boundary for River Rch & Prof#=Little Cottonwoo,Reach-1,3
Up Type=0
Dn Type=3
Dn Slope=0.005
Boundary for River Rch & Prof#=Little Cottonwoo,Reach-1,4
Up Type=0
Dn Type=3
Dn Slope=0.005
Boundary for River Rch & Prof#=Little Cottonwoo,Reach-1,5
Up Type=0
Dn Type=3
Dn Slope=0.005
Boundary for River Rch & Prof#=Little Cottonwoo,Reach-1,6
Up Type=0
Dn Type=3
Dn Slope=0.005
Boundary for River Rch & Prof#=Little Cottonwoo,Reach-1,7
Up Type=0
Dn Type=3
Dn Slope=0.005

--- Little Cottonwood Creek Trib 4.g01 (geometry) ---

Geom Title=Existing Conditions

River Reach=Little Cottonwoo,Reach-1
Reach XY= 30
      2656076.00      6877661.00      2656066.85      6877454.27
      2655933.07      6877311.00      2656168.41      6876957.65
      2655925.61      6876781.28      2656124.38      6876454.97
      2656084.24      6876157.77      2656318.80      6875410.70
      2656177.89      6875305.29      2656276.49      6875086.04
      2656177.79      6874817.09      2656568.12      6874317.16
      2656589.26      6874197.35      2656975.97      6873890.80
      2656970.61      6873758.32      2656777.97      6873505.11
      2656823.16      6873269.01      2656677.76      6873167.17
      2656867.99      6872814.33      2656931.47      6872408.55
      2657324.54      6872048.86      2657270.56      6871916.25
      2657133.63      6871867.50      2657131.39      6871758.56
      2657327.55      6871614.75      2657528.73      6871605.65
      2657716.18      6871321.47      2658006.41      6871231.21
      2658179.76      6870712.56      2658376.00      6870461.00

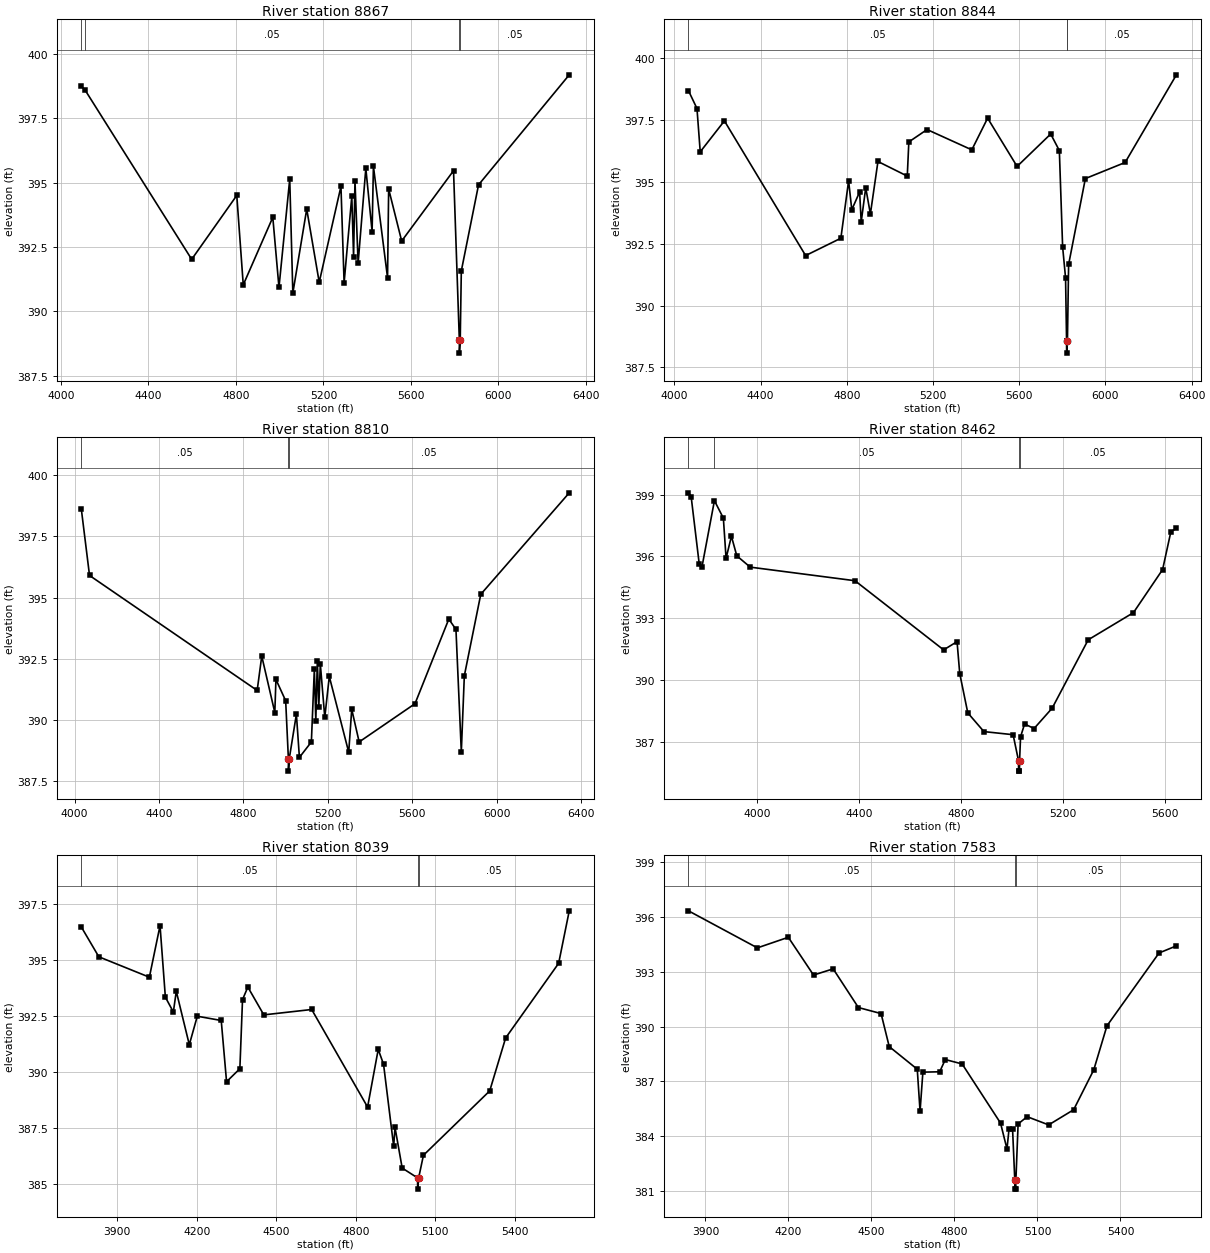
Type RM Length L Ch R = 1,8867,23,23,23
BEGIN DESCRIPTION:
Mapping XS fbd99a46
END DESCRIPTION:
XS GIS Cut Line= 6
      2656947.16      6877375.69      2656197.19      6876945.15
      2656155.53      6876948.63      2655881.22      6877257.65
      2655846.50      6877615.29      2655496.84      6878027.27
#Sta/Elev= 30
  4093.2  398.73  4109.6  398.60  4597.8  392.02  4804.0  394.50  4833.6  391.03
  4968.7  393.65  4996.9  390.93  5046.1  395.13  5060.3  390.71  5123.8  393.97
  5180.9  391.13  5280.3  394.85  5294.7  391.11  5329.9  394.46  5338.0  392.12
  5344.4  395.06  5358.8  391.87  5394.0  395.55  5422.7  393.10  5428.7  395.63
  5493.3  391.31  5498.4  394.75  5557.9  392.73  5795.0  395.46  5821.6  388.88
  5821.8  388.38  5825.6  388.88  5830.6  391.57  5909.3  394.91  6324.1  399.18
#Mann=4,-1,0
  4093.2   0.075       0  4109.6    0.05       0  5821.6    0.03       0
  5825.6    0.05       0
Bank Sta=5821.6,5825.6
Exp/Cntr=0.3,0.1

Type RM Length L Ch R = 1,8844,34,34,34
BEGIN DESCRIPTION:
Mapping XS 0beacc07
END DESCRIPTION:
XS GIS Cut Line= 6
      2656964.55      6877354.88      2656200.66      6876924.32
      2656145.11      6876931.26      2655860.39      6877254.18
      2655820.24      6877616.23      2655465.29      6878006.84
#Sta/Elev= 30
  4065.3  398.68  4104.8  397.96  4119.9  396.21  4232.1  397.46  4608.9  392.02
  4772.4  392.72  4808.4  395.04  4823.1  393.87  4859.5  394.59  4866.8  393.38
  4887.8  394.76  4909.4  393.70  4944.5  395.82  5080.6  395.23  5087.8  396.61
  5172.5  397.11  5380.0  396.29  5453.4  397.57  5590.1  395.62  5746.1  396.93
  5786.2  396.26  5801.4  392.37  5815.0  391.12  5819.7  388.58  5820.0  388.08
  5823.7  388.58  5829.2  391.66  5906.9  395.13  6091.4  395.78  6329.3  399.32
#Mann=3,-1,0
  4065.3    0.05       0  5819.7    0.03       0  5823.7    0.05       0
Bank Sta=5819.7,5823.7
Exp/Cntr=0.3,0.1

Type RM Length L Ch R = 1,8810,348,348,348
BEGIN DESCRIPTION:
Mapping XS c18c140d
END DESCRIPTION:
XS GIS Cut Line= 6
      2656959.33      6877331.26      2656193.26      6876876.20
      2656138.57      6876897.04      2655801.77      6877249.47
      2655806.06      6877584.91      2655453.85      6877990.04
#Sta/Elev= 30
  4031.9  398.61  4070.8  395.90  4865.1  391.21  4886.8  392.61  4948.7  390.31
  4954.0  391.66  5000.1  390.79  5013.0  388.42  5013.3  387.92  5017.0  388.42
  5050.9  390.24  5065.2  388.48  5121.9  389.11  5136.0  392.08  5142.9  389.97
  5150.2  392.42  5157.1  390.54  5164.3  392.29  5185.4  390.11  5206.8  391.78
  5298.8  388.69  5313.1  390.44  5348.3  389.11  5612.9  390.67  5773.0  394.12
  5806.9  393.70  5832.3  388.71  5846.6  391.81  5924.4  395.13  6343.7  399.27
#Mann=3,-1,0
  4031.9    0.05       0  5013.0    0.03       0  5017.0    0.05       0
Bank Sta=5013,5017
Exp/Cntr=0.3,0.1

Type RM Length L Ch R = 1,8462,423,423,423
BEGIN DESCRIPTION:
Little Cottonwood Creek Trib 4 12.0
END DESCRIPTION:
XS GIS Cut Line= 3
      2657175.99      6877111.00      2655976.00      6876711.00
      2655376.00      6876461.00
#Sta/Elev= 30
  3730.9  399.09  3741.4  398.91  3773.0  395.65  3783.6  395.47  3832.8  398.71
  3867.9  397.86  3878.5  395.91  3899.5  396.98  3920.6  396.03  3973.3  395.48
  4384.4  394.82  4732.3  391.46  4785.0  391.86  4795.5  390.31  4827.1  388.40
  4890.4  387.49  5005.0  387.34  5026.3  386.07  5026.5  385.57  5030.0  385.57
  5030.3  386.07  5034.3  387.24  5050.0  387.86  5087.3  387.64  5158.3  388.63
  5299.7  391.95  5477.3  393.27  5591.6  395.36  5624.1  397.20  5645.8  397.36
#Mann=4,-1,0
  3730.9   0.075       0  3832.8    0.05       0  5026.3    0.03       0
  5030.3    0.05       0
Bank Sta=5026.3,5030.3
Exp/Cntr=0.3,0.1

Type RM Length L Ch R = 1,8039,456,456,456
BEGIN DESCRIPTION:
Little Cottonwood Creek Trib 4 11.0
END DESCRIPTION:
XS GIS Cut Line= 3
      2657311.82      6876465.99      2656076.00      6876361.00
      2655475.97      6876361.00
#Sta/Elev= 30
  3764.5  396.47  3830.6  395.14  4021.2  394.23  4061.4  396.53  4081.5  393.34
  4111.6  392.68  4122.7  393.60  4171.8  391.22  4201.9  392.49  4292.2  392.30
  4312.3  389.57  4362.5  390.15  4372.5  393.23  4392.6  393.79  4452.8  392.55
  4633.4  392.79  4844.2  388.44  4884.3  391.01  4904.4  390.35  4942.6  386.69
  4947.6  387.53  4974.7  385.72  5032.8  385.28  5033.0  384.78  5036.8  385.28
  5054.8  386.29  5304.8  389.16  5364.8  391.52  5564.8  394.85  5604.8  397.19
#Mann=3,-1,0
  3764.5    0.05       0  5032.8    0.04       0  5036.8    0.05       0
Bank Sta=5032.8,5036.8
Exp/Cntr=0.3,0.1

Type RM Length L Ch R = 1,7583,443,443,443
BEGIN DESCRIPTION:
Little Cottonwood Creek Trib 4 10.0
END DESCRIPTION:
XS GIS Cut Line= 3
      2657322.18      6876146.54      2656176.00      6875961.00
      2655575.98      6876011.00
#Sta/Elev= 30
  3838.9  396.34  4087.9  394.31  4199.7  394.89  4290.9  392.82  4361.8  393.16
  4453.0  391.04  4534.9  390.71  4564.4  388.90  4665.7  387.66  4675.8  385.36
  4686.0  387.50  4746.7  387.52  4767.0  388.19  4827.8  387.95  4966.6  384.71
  4989.9  383.29  4997.5  384.41  5010.0  384.41  5018.1  381.59  5018.3  381.09
  5021.8  381.09  5022.1  381.59  5030.1  384.66  5062.7  385.06  5140.5  384.61
  5230.8  385.44  5303.6  387.63  5351.2  390.04  5539.4  394.03  5602.1  394.42
#Mann=3,-1,0
  3838.9    0.05       0  5018.1    0.04       0  5022.1    0.05       0
Bank Sta=5018.1,5022.1
Exp/Cntr=0.3,0.1

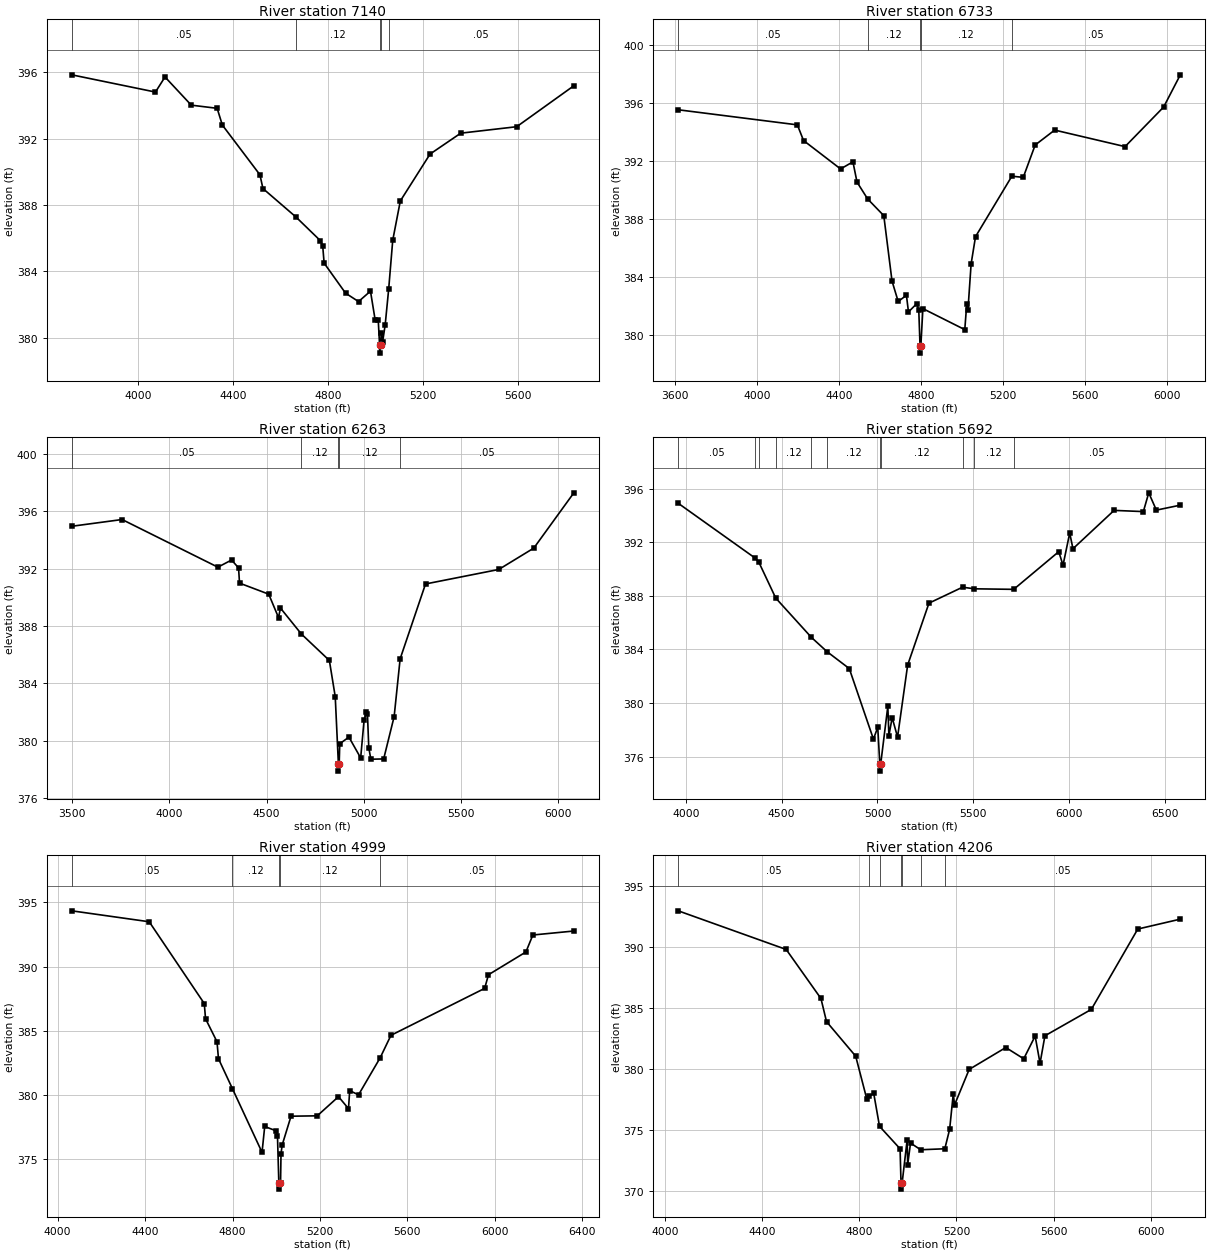
Type RM Length L Ch R = 1,7140,407,407,407
BEGIN DESCRIPTION:
Little Cottonwood Creek Trib 4 9.0
END DESCRIPTION:
XS GIS Cut Line= 3
      2657506.22      6875417.38      2656226.00      6875561.00
      2655447.19      6875837.52
#Sta/Elev= 30
  3719.7  395.85  4072.1  394.81  4112.4  395.72  4223.1  394.02  4332.0  393.83
  4353.9  392.82  4512.2  389.82  4524.9  388.99  4664.1  387.27  4766.4  385.85
  4776.5  385.55  4782.6  384.49  4872.8  382.68  4927.5  382.17  4977.8  382.80
  4997.9  381.03  5010.6  381.04  5016.1  379.56  5016.3  379.06  5020.1  379.56
  5023.4  380.29  5029.2  379.76  5039.8  380.77  5054.4  382.91  5071.6  385.87
  5103.5  388.24  5228.8  391.07  5358.1  392.33  5593.8  392.72  5834.4  395.19
#Mann=5,-1,0
  3719.7    0.05       0  4664.1    0.12       0  5016.1    0.07       0
  5020.1    0.12       0  5054.4    0.05       0
Bank Sta=5016.1,5020.1
Exp/Cntr=0.3,0.1

Type RM Length L Ch R = 1,6733,470,470,470
BEGIN DESCRIPTION:
Little Cottonwood Creek Trib 4 8.0
END DESCRIPTION:
XS GIS Cut Line= 3
      2657554.86      6875156.96      2656176.00      6875261.00
      2655266.62      6875813.22
#Sta/Elev= 30
  3616.2  395.53  4196.7  394.49  4226.8  393.41  4407.3  391.45  4467.5  391.94
  4487.5  390.54  4539.3  389.38  4617.9  388.23  4658.0  383.72  4688.1  382.31
  4728.2  382.74  4738.2  381.59  4778.4  382.16  4788.4  381.72  4794.5  379.25
  4794.8  378.75  4798.5  379.25  4808.4  381.82  5012.6  380.37  5022.2  382.15
  5028.1  381.74  5043.5  384.91  5064.9  386.78  5242.0  390.95  5297.5  390.87
  5355.6  393.10  5450.6  394.13  5793.6  392.99  5981.7  395.72  6062.9  397.94
#Mann=5,-1,0
  3616.2    0.05       0  4539.3    0.12       0  4794.5    0.07       0
  4798.5    0.12       0  5242.0    0.05       0
Bank Sta=4794.5,4798.5
Exp/Cntr=0.3,0.1

Type RM Length L Ch R = 1,6263,571,571,571
BEGIN DESCRIPTION:
Little Cottonwood Creek Trib 4 7.0
END DESCRIPTION:
XS GIS Cut Line= 3
      2657672.93      6875035.44      2656176.00      6874861.00
      2655175.99      6875261.00
#Sta/Elev= 30
  3497.5  394.95  3756.5  395.42  4249.5  392.10  4320.0  392.60  4355.9  392.05
  4360.9  390.99  4511.2  390.22  4561.6  388.59  4571.6  389.25  4679.5  387.44
  4823.3  385.60  4853.5  383.08  4869.8  378.39  4870.1  377.89  4873.8  378.39
  4876.8  379.80  4924.0  380.26  4984.4  378.81  5002.0  381.44  5014.0  382.00
  5019.4  381.86  5026.1  379.52  5036.9  378.72  5102.8  378.74  5156.7  381.69
  5187.5  385.71  5318.2  390.93  5695.2  391.94  5875.6  393.43  6081.6  397.28
#Mann=5,-1,0
  3497.5    0.05       0  4679.5    0.12       0  4869.8    0.07       0
  4873.8    0.12       0  5187.5    0.05       0
Bank Sta=4869.8,4873.8
Exp/Cntr=0.3,0.1

Type RM Length L Ch R = 1,5692,693,693,693
BEGIN DESCRIPTION:
Mapping XS ba63f1f9
END DESCRIPTION:
XS GIS Cut Line= 3
      2657381.22      6874934.74      2656471.50      6874417.38
      2655054.84      6873733.35
#Sta/Elev= 30
  3960.6  394.90  4361.1  390.82  4380.7  390.52  4469.3  387.83  4655.9  384.89
  4737.2  383.83  4853.1  382.57  4979.0  377.31  5001.7  378.19  5012.4  375.42
  5012.8  374.92  5016.7  375.42  5054.2  379.76  5059.8  377.57  5076.8  378.91
  5105.0  377.46  5157.6  382.83  5268.8  387.45  5444.0  388.64  5506.2  388.52
  5711.0  388.48  5946.0  391.29  5968.3  390.28  6003.2  392.68  6020.2  391.51
  6234.8  394.37  6387.5  394.28  6415.6  395.68  6455.3  394.39  6580.3  394.76
#Mann=11,-1,0
  3960.6    0.05       0  4361.1   0.075       0  4380.7    0.05       0
  4469.3    0.12       0  4655.9    0.05       0  4737.2    0.12       0
  5012.4    0.07       0  5016.7    0.12       0  5444.0    0.05       0
  5506.2    0.12       0  5711.0    0.05       0
Bank Sta=5012.4,5016.7
Exp/Cntr=0.3,0.1

Type RM Length L Ch R = 1,4999,793,793,793
BEGIN DESCRIPTION:
Mapping XS 48e75a4f
END DESCRIPTION:
XS GIS Cut Line= 3
      2657714.52      6874396.52      2656884.69      6873927.79
      2655665.95      6873361.83
#Sta/Elev= 30
  4064.5  394.33  4418.8  393.48  4670.7  387.12  4676.4  385.94  4728.9  384.15
  4735.6  382.83  4799.2  380.51  4934.9  375.55  4947.1  377.56  4999.8  377.22
  5005.6  376.80  5011.7  373.19  5012.1  372.69  5016.1  373.19  5019.6  373.19
  5021.7  375.46  5027.2  376.13  5067.5  378.36  5187.5  378.39  5284.6  379.88
  5330.4  378.95  5335.9  380.35  5376.2  380.02  5475.5  382.91  5524.6  384.65
  5953.3  388.30  5970.7  389.36  6142.0  391.13  6173.8  392.45  6361.3  392.76
#Mann=5,-1,0
  4064.5    0.05       0  4799.2    0.12       0  5011.7    0.07       0
  5016.1    0.12       0  5475.5    0.05       0
Bank Sta=5011.7,5016.1
Exp/Cntr=0.3,0.1

Type RM Length L Ch R = 1,4206,705,705,705
BEGIN DESCRIPTION:
Little Cottonwood Creek Trib 4 6.0
END DESCRIPTION:
XS GIS Cut Line= 3
      2657684.20      6873702.63      2656827.04      6873305.49
      2655711.94      6873188.73
#Sta/Elev= 30
  4055.3  392.94  4499.5  389.78  4642.5  385.77  4665.4  383.88  4785.5  381.05
  4831.3  377.54  4841.7  377.78  4859.7  378.01  4883.5  375.32  4968.1  373.48
  4972.0  370.68  4972.5  370.18  4976.5  370.68  4997.2  374.20  4999.4  372.18
  5011.1  373.95  5052.9  373.40  5152.2  373.48  5172.0  375.07  5187.1  378.00
  5192.1  377.06  5252.4  379.97  5403.2  381.76  5476.9  380.84  5523.9  382.70
  5544.0  380.47  5564.1  382.72  5755.1  384.88  5946.2  391.45  6121.2  392.26
#Mann=7,-1,0
  4055.3    0.05       0  4841.7    0.12       0  4883.5    0.05       0
  4972.0    0.03       0  4976.5    0.05       0  5052.9    0.12       0
  5152.2    0.05       0
Bank Sta=4972,4976.5
Exp/Cntr=0.3,0.1

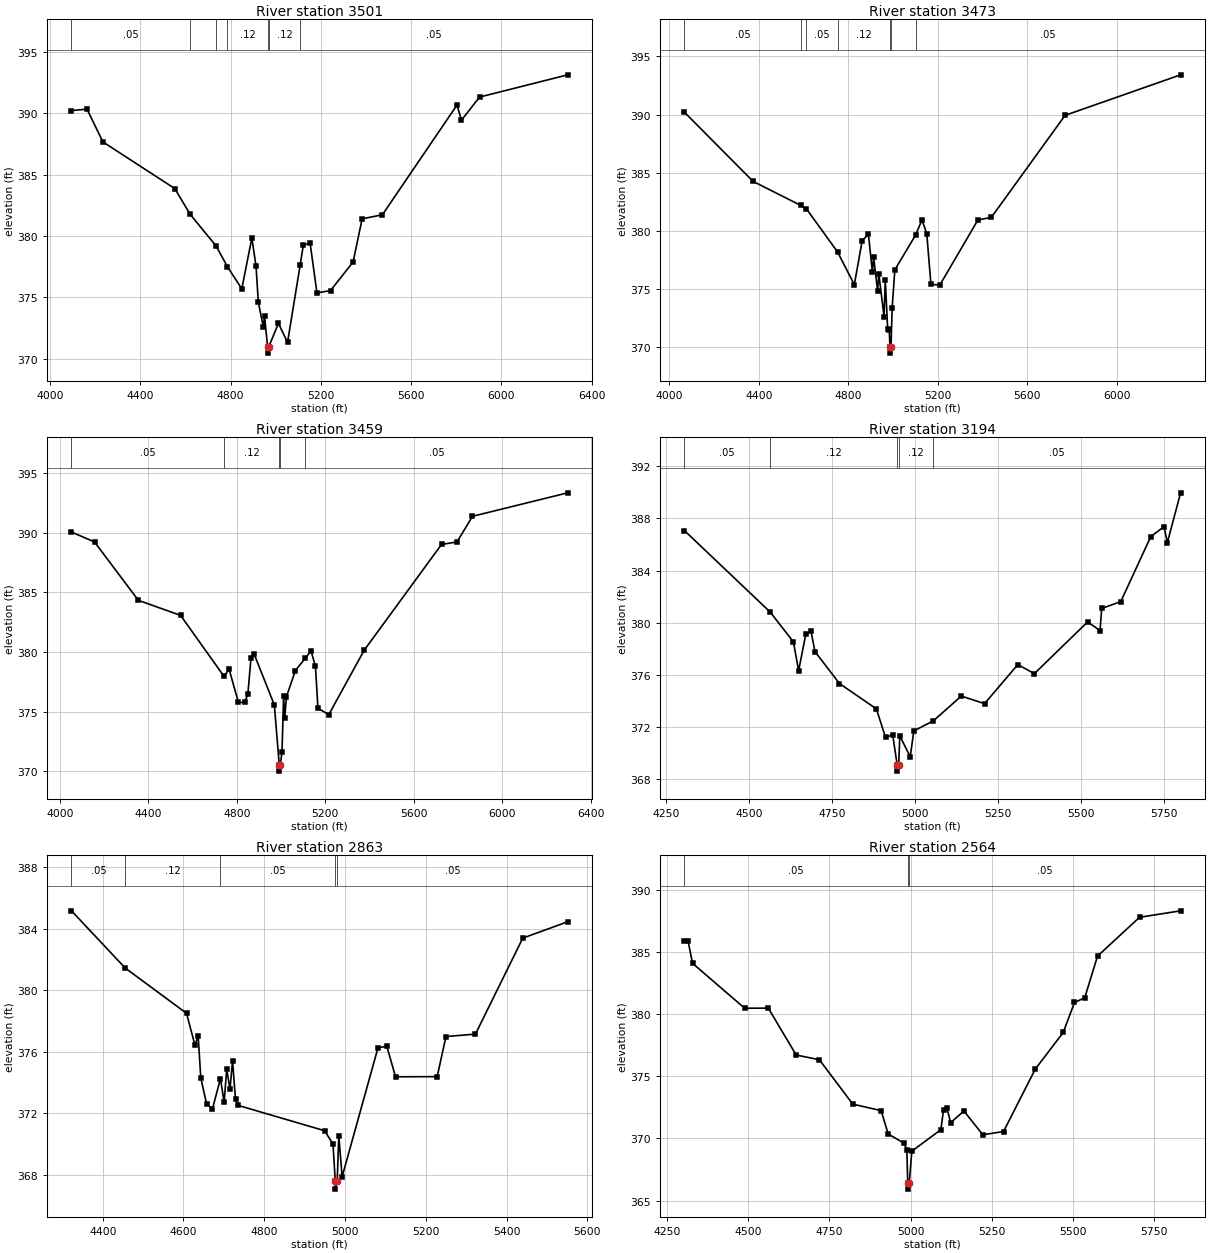
Type RM Length L Ch R = 1,3501,28,28,28
BEGIN DESCRIPTION:
Mapping XS fae57e20
END DESCRIPTION:
XS GIS Cut Line= 5
      2657498.42      6873405.76      2656941.12      6872832.83
      2656852.57      6872783.35      2656631.22      6872767.72
      2655555.74      6872809.39
#Sta/Elev= 30
  4094.9  390.20  4163.6  390.32  4234.3  387.65  4552.5  383.86  4620.8  381.76
  4735.8  379.19  4785.7  377.51  4849.6  375.70  4894.2  379.83  4912.7  377.56
  4922.9  374.61  4944.7  372.63  4950.4  373.47  4964.1  370.97  4964.5  370.47
  4968.7  370.97  5012.2  372.89  5052.3  371.34  5108.0  377.60  5122.5  379.27
  5152.6  379.40  5182.6  375.37  5242.8  375.56  5342.8  377.88  5382.9  381.39
  5472.9  381.73  5803.2  390.65  5823.2  389.42  5903.2  391.30  6293.8  393.11
#Mann=7,-1,0
  4094.9    0.05       0  4620.8    0.12       0  4735.8    0.05       0
  4785.7    0.12       0  4964.1    0.07       0  4968.7    0.12       0
  5108.0    0.05       0
Bank Sta=4964.1,4968.7
Exp/Cntr=0.3,0.1

Type RM Length L Ch R = 1,3473,14,14,14
BEGIN DESCRIPTION:
Mapping XS 94ab6d75
END DESCRIPTION:
XS GIS Cut Line= 5
      2657503.58      6873397.90      2656946.32      6872809.39
      2656834.35      6872759.91      2656688.51      6872739.08
      2655549.44      6872754.68
#Sta/Elev= 30
  4066.7  390.20  4374.1  384.24  4587.4  382.17  4612.7  381.87  4751.6  378.17
  4826.8  375.35  4862.0  379.15  4889.8  379.68  4907.6  376.45  4913.1  377.71
  4930.9  374.81  4936.4  376.26  4959.7  372.59  4965.1  375.79  4975.9  371.54
  4983.0  371.46  4986.1  369.95  4986.6  369.45  4990.7  369.95  4996.0  373.36
  5008.0  376.63  5100.5  379.61  5129.3  380.92  5150.7  379.75  5169.4  375.37
  5209.4  375.32  5379.5  380.92  5439.5  381.14  5769.5  389.93  6286.1  393.42
#Mann=7,-1,0
  4066.7    0.05       0  4587.4    0.12       0  4612.7    0.05       0
  4751.6    0.12       0  4986.1    0.07       0  4990.7    0.12       0
  5100.5    0.05       0
Bank Sta=4986.1,4990.7
Exp/Cntr=0.3,0.1

Type RM Length L Ch R = 1,3459,265,265,265
BEGIN DESCRIPTION:
Mapping XS dfaf7eb0
END DESCRIPTION:
XS GIS Cut Line= 5
      2657519.21      6873395.29      2656959.35      6872798.97
      2656852.57      6872749.49      2656659.87      6872723.45
      2655545.28      6872731.26
#Sta/Elev= 30
  4051.7  390.07  4155.9  389.24  4354.2  384.34  4545.2  383.08  4742.2  377.95
  4764.5  378.58  4807.0  375.77  4835.3  375.78  4849.5  376.46  4863.6  379.46
  4877.8  379.84  4969.4  375.56  4991.7  370.51  4992.1  370.01  4996.3  370.51
  5004.1  371.63  5011.3  376.32  5016.3  374.45  5024.2  376.26  5064.6  378.45
  5109.0  379.47  5135.2  380.11  5155.4  378.80  5166.7  375.28  5215.7  374.75
  5375.7  380.15  5725.7  389.03  5795.7  389.24  5865.7  391.39  6296.4  393.36
#Mann=5,-1,0
  4051.7    0.05       0  4742.2    0.12       0  4991.7    0.07       0
  4996.3    0.12       0  5109.0    0.05       0
Bank Sta=4991.7,4996.3
Exp/Cntr=0.3,0.1

Type RM Length L Ch R = 1,3194,331,331,331
BEGIN DESCRIPTION:
Little Cottonwood Creek Trib 4 4.0
END DESCRIPTION:
XS GIS Cut Line= 3
      2657525.97      6872860.98      2656926.00      6872511.00
      2656126.05      6872461.00
#Sta/Elev= 30
  4305.4  387.07  4563.9  380.83  4634.1  378.54  4649.8  376.34  4671.3  379.11
  4687.0  379.37  4699.0  377.80  4773.0  375.35  4884.2  373.41  4911.9  371.22
  4933.4  371.42  4946.8  369.14  4947.3  368.64  4951.5  369.14  4954.9  371.34
  4986.3  369.74  4997.1  371.72  5056.4  372.50  5140.3  374.39  5210.4  373.81
  5310.6  376.80  5360.7  376.11  5521.0  380.07  5558.6  379.41  5563.6  381.10
  5621.2  381.63  5711.4  386.60  5751.5  387.37  5761.5  386.14  5801.5  389.96
#Mann=5,-1,0
  4305.4    0.05       0  4563.9    0.12       0  4946.8    0.07       0
  4951.5    0.12       0  5056.4    0.05       0
Bank Sta=4946.8,4951.5
Exp/Cntr=0.3,0.1

Type RM Length L Ch R = 1,2863,299,299,299
BEGIN DESCRIPTION:
Little Cottonwood Creek Trib 4 3.0
END DESCRIPTION:
XS GIS Cut Line= 3
      2657476.02      6872761.02      2657058.87      6872227.30
      2656576.03      6871961.02
#Sta/Elev= 30
  4322.6  385.15  4455.6  381.44  4607.5  378.50  4628.3  376.44  4636.4  377.00
  4642.8  374.32  4657.2  372.61  4671.7  372.30  4691.6  374.26  4700.6  372.72
  4707.0  374.88  4715.1  373.56  4721.5  375.40  4728.8  372.91  4735.9  372.52
  4949.4  370.88  4970.2  370.02  4975.9  367.59  4976.4  367.09  4980.6  367.59
  4984.6  370.55  4992.8  367.89  5081.5  376.25  5103.3  376.37  5125.1  374.38
  5228.2  374.39  5250.0  376.99  5323.0  377.15  5440.2  383.38  5551.4  384.44
#Mann=5,-1,0
  4322.6    0.05       0  4455.6    0.12       0  4691.6    0.05       0
  4975.9    0.03       0  4980.6    0.05       0
Bank Sta=4975.9,4980.6
Exp/Cntr=0.3,0.1

Type RM Length L Ch R = 1,2564,838,838,838
BEGIN DESCRIPTION:
Mapping XS c319f76d
END DESCRIPTION:
XS GIS Cut Line= 3
      2657865.57      6872447.39      2657282.26      6872072.41
      2656514.03      6871746.89
#Sta/Elev= 30
  4303.4  385.89  4314.8  385.84  4328.5  384.07  4489.0  380.46  4561.7  380.47
  4647.6  376.70  4719.0  376.32  4821.9  372.75  4909.2  372.23  4930.9  370.35
  4980.5  369.60  4988.3  369.04  4991.1  366.42  4991.7  365.92  4995.9  366.42
  5003.6  368.97  5093.1  370.70  5101.4  372.32  5111.3  372.48  5123.1  371.26
  5164.1  372.20  5222.3  370.29  5286.0  370.55  5383.8  375.57  5469.9  378.52
  5504.5  380.93  5535.8  381.29  5575.5  384.65  5704.7  387.77  5831.2  388.29
#Mann=3,-1,0
  4303.4    0.05       0  4991.1    0.03       0  4995.9    0.05       0
Bank Sta=4991.1,4995.9
Exp/Cntr=0.3,0.1

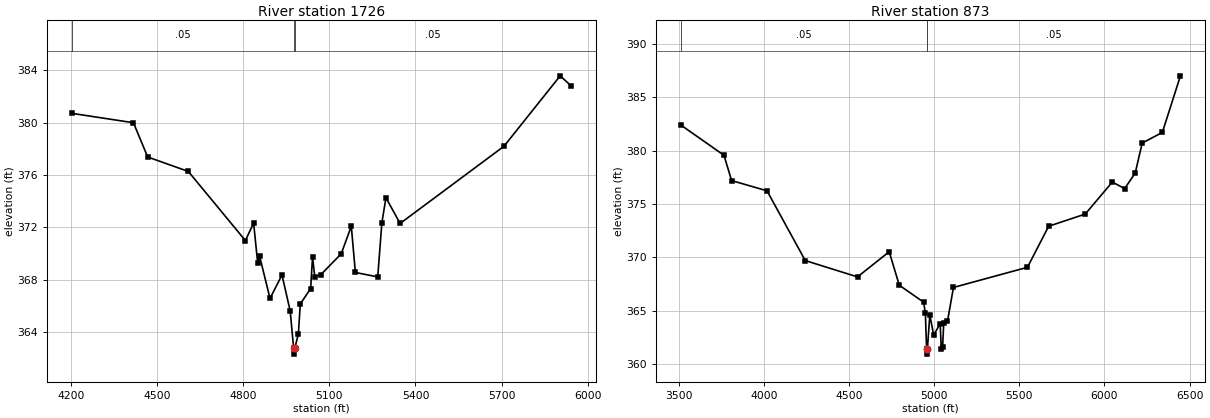
Type RM Length L Ch R = 1,1726,853,853,853
BEGIN DESCRIPTION:
Mapping XS 1ba07e70
END DESCRIPTION:
XS GIS Cut Line= 4
      2657961.96      6872218.25      2657454.14      6871619.29
      2657040.07      6871262.51      2656631.21      6871244.29
#Sta/Elev= 30
  4202.3  380.72  4417.6  380.00  4467.1  377.38  4608.8  376.27  4807.6  370.98
  4836.2  372.33  4850.5  369.23  4857.0  369.79  4893.3  366.55  4935.0  368.35
  4963.6  365.59  4975.4  362.79  4976.0  362.29  4980.3  362.79  4992.2  363.85
  4998.8  366.13  5034.9  367.31  5041.5  369.73  5049.2  368.22  5070.1  368.37
  5141.4  369.97  5176.5  372.08  5190.7  368.54  5268.6  368.20  5282.9  372.33
  5297.2  374.26  5346.5  372.29  5708.4  378.20  5904.2  383.59  5943.4  382.80
#Mann=3,-1,0
  4202.3    0.05       0  4975.4    0.03       0  4980.3    0.05       0
Bank Sta=4975.4,4980.3
Exp/Cntr=0.3,0.1

Type RM Length L Ch R = 1,873,0,0,0
BEGIN DESCRIPTION:
Little Cottonwood Creek Trib 4 1.0
END DESCRIPTION:
XS GIS Cut Line= 4
      2656569.77      6870853.93      2658026.33      6871161.08
      2658287.25      6871383.17      2657992.12      6872446.53
#Sta/Elev= 30
  3511.4  382.43  3766.0  379.58  3810.6  377.21  4018.5  376.25  4243.3  369.71
  4550.0  368.18  4736.1  370.54  4795.3  367.40  4938.3  365.81  4948.6  364.76
  4955.6  361.44  4956.2  360.94  4960.5  361.44  4974.7  364.63  4997.3  362.71
  5035.4  363.80  5042.0  361.44  5049.7  361.62  5056.3  363.84  5078.3  364.02
  5113.4  367.19  5547.9  369.08  5672.5  372.93  5887.4  374.07  6046.1  377.07
  6118.9  376.46  6181.0  377.93  6221.7  380.73  6340.0  381.72  6446.2  387.03
#Mann=3,-1,0
  3511.4    0.05       0  4955.6    0.03       0  4960.5    0.05       0
Bank Sta=4955.6,4960.5
Exp/Cntr=0.3,0.1

Chan Stop Cuts=-1