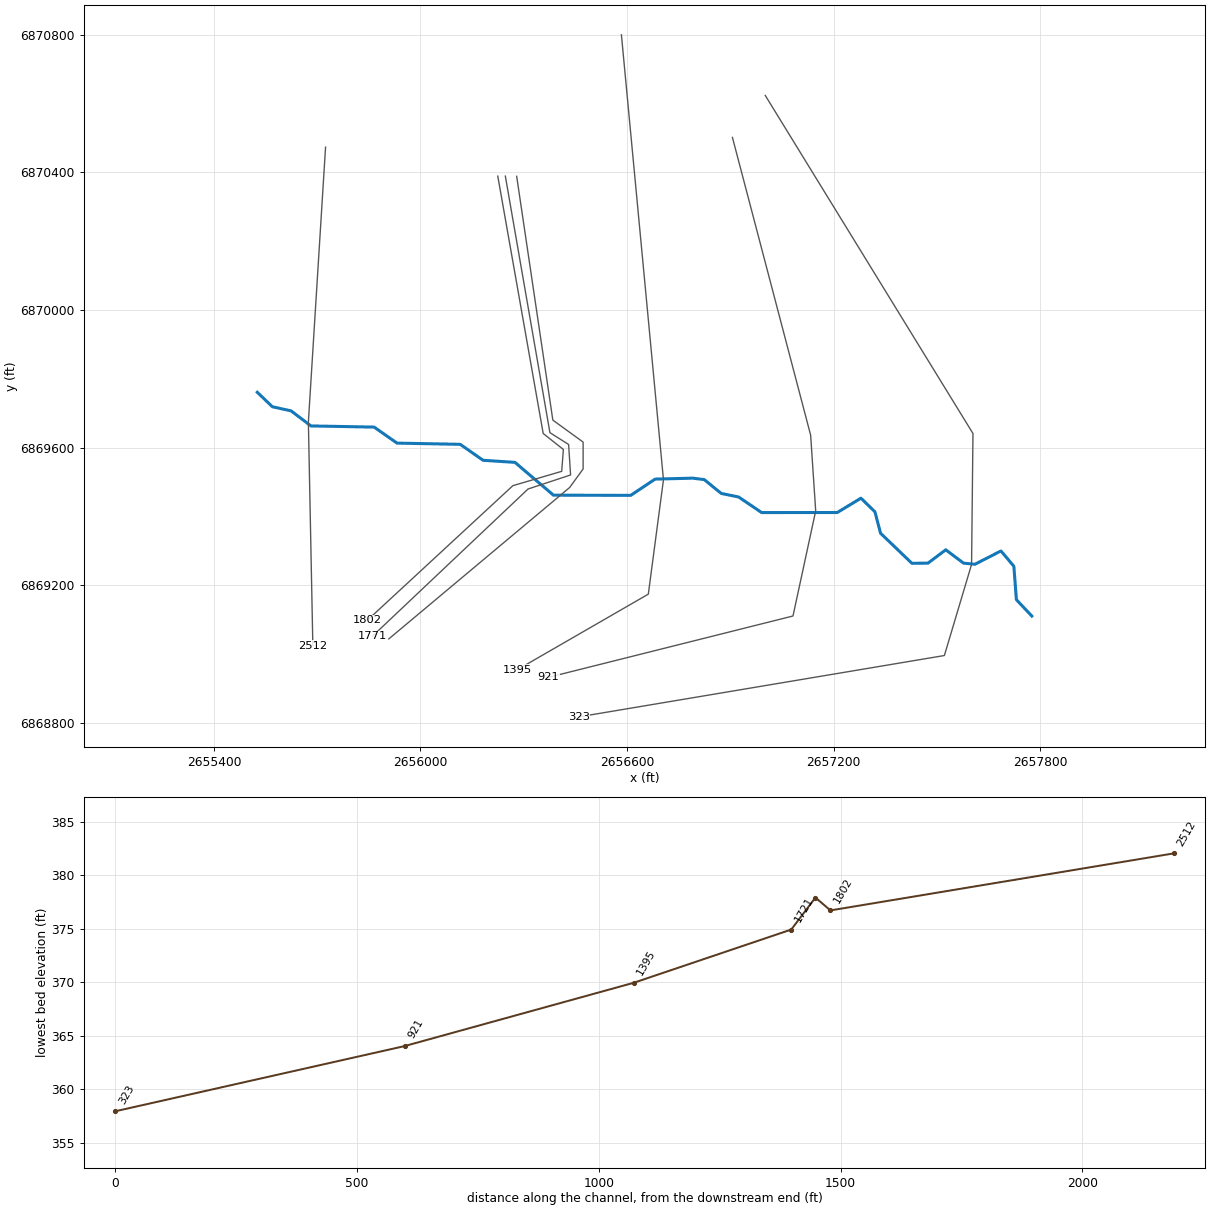
--- Little Cottonwood Creek Trib 5.prj (project) ---

Proj Title=Little Cottonwood Creek Trib 5 Base Level Engineering
Current Plan=p01
Default Exp/Contr=0.3,0.1
English Units
Geom File=g01
Flow File=f01
Plan File=p01
BEGIN DESCRIPTION:
Little Cottonwood Creek Trib 5
END DESCRIPTION:

--- Little Cottonwood Creek Trib 5.p01 (plan) ---

Plan Title=Multiple Run
Short Identifier=Multiple
Geom File=g01
Flow File=f01
Subcritical Flow
K Sum by GR= 0
Std Step Tol= 0.01
Critical Tol= 0.01
Num of Std Step Trials= 20
Max Error Tol= 0.3
Flow Tol Ratio= 0.001
Split Flow NTrial= 30
Split Flow Tol= 0.02
Split Flow Ratio= 0.02
Log Output Level= 0
Friction Slope Method= 1
Unsteady Friction Slope Method= 2
Unsteady Bridges Friction Slope Method= 1
Parabolic Critical Depth
Global Vel Dist=  1 , 1 , 1
Global Log Level= 0
CheckData=True
Encroach Param= -1, 0, 0, 0
BEGIN DESCRIPTION:
Multiple Run
END DESCRIPTION:

--- Little Cottonwood Creek Trib 5.f01 (steady flow) ---

Flow Title=Multiple
Number of Profiles=7
Profile Names=10-year,25-year,50-year,1pct_min,100-year,1pct_plu,500-year
River Rch & RM= Little Cottonwoo,Reach-1,2512
     365     474     558     327     652    1301     888
Boundary for River Rch & Prof#=Little Cottonwoo,Reach-1,1
Up Type=0
Dn Type=3
Dn Slope=0.005
Boundary for River Rch & Prof#=Little Cottonwoo,Reach-1,2
Up Type=0
Dn Type=3
Dn Slope=0.005
Boundary for River Rch & Prof#=Little Cottonwoo,Reach-1,3
Up Type=0
Dn Type=3
Dn Slope=0.005
Boundary for River Rch & Prof#=Little Cottonwoo,Reach-1,4
Up Type=0
Dn Type=3
Dn Slope=0.005
Boundary for River Rch & Prof#=Little Cottonwoo,Reach-1,5
Up Type=0
Dn Type=3
Dn Slope=0.005
Boundary for River Rch & Prof#=Little Cottonwoo,Reach-1,6
Up Type=0
Dn Type=3
Dn Slope=0.005
Boundary for River Rch & Prof#=Little Cottonwoo,Reach-1,7
Up Type=0
Dn Type=3
Dn Slope=0.005

--- Little Cottonwood Creek Trib 5.g01 (geometry) ---

Geom Title=Existing Conditions

River Reach=Little Cottonwoo,Reach-1
Reach XY= 30
      2655526.00      6869761.00      2655569.85      6869718.91
      2655624.31      6869706.92      2655681.92      6869663.23
      2655865.49      6869659.78      2655931.94      6869613.26
      2656115.50      6869609.78      2656181.98      6869563.36
      2656274.50      6869557.38      2656386.44      6869462.06
      2656610.78      6869461.52      2656681.94      6869508.75
      2656791.16      6869511.48      2656824.44      6869507.26
      2656873.82      6869467.12      2656924.26      6869456.81
      2656991.21      6869411.51      2657210.85      6869411.67
      2657279.67      6869453.31      2657320.15      6869413.85
      2657336.77      6869351.33      2657427.64      6869264.15
      2657474.35      6869264.57      2657526.00      6869303.38
      2657577.65      6869264.64      2657610.65      6869261.30
      2657686.43      6869300.05      2657723.89      6869255.53
      2657731.23      6869158.46      2657776.00      6869111.00

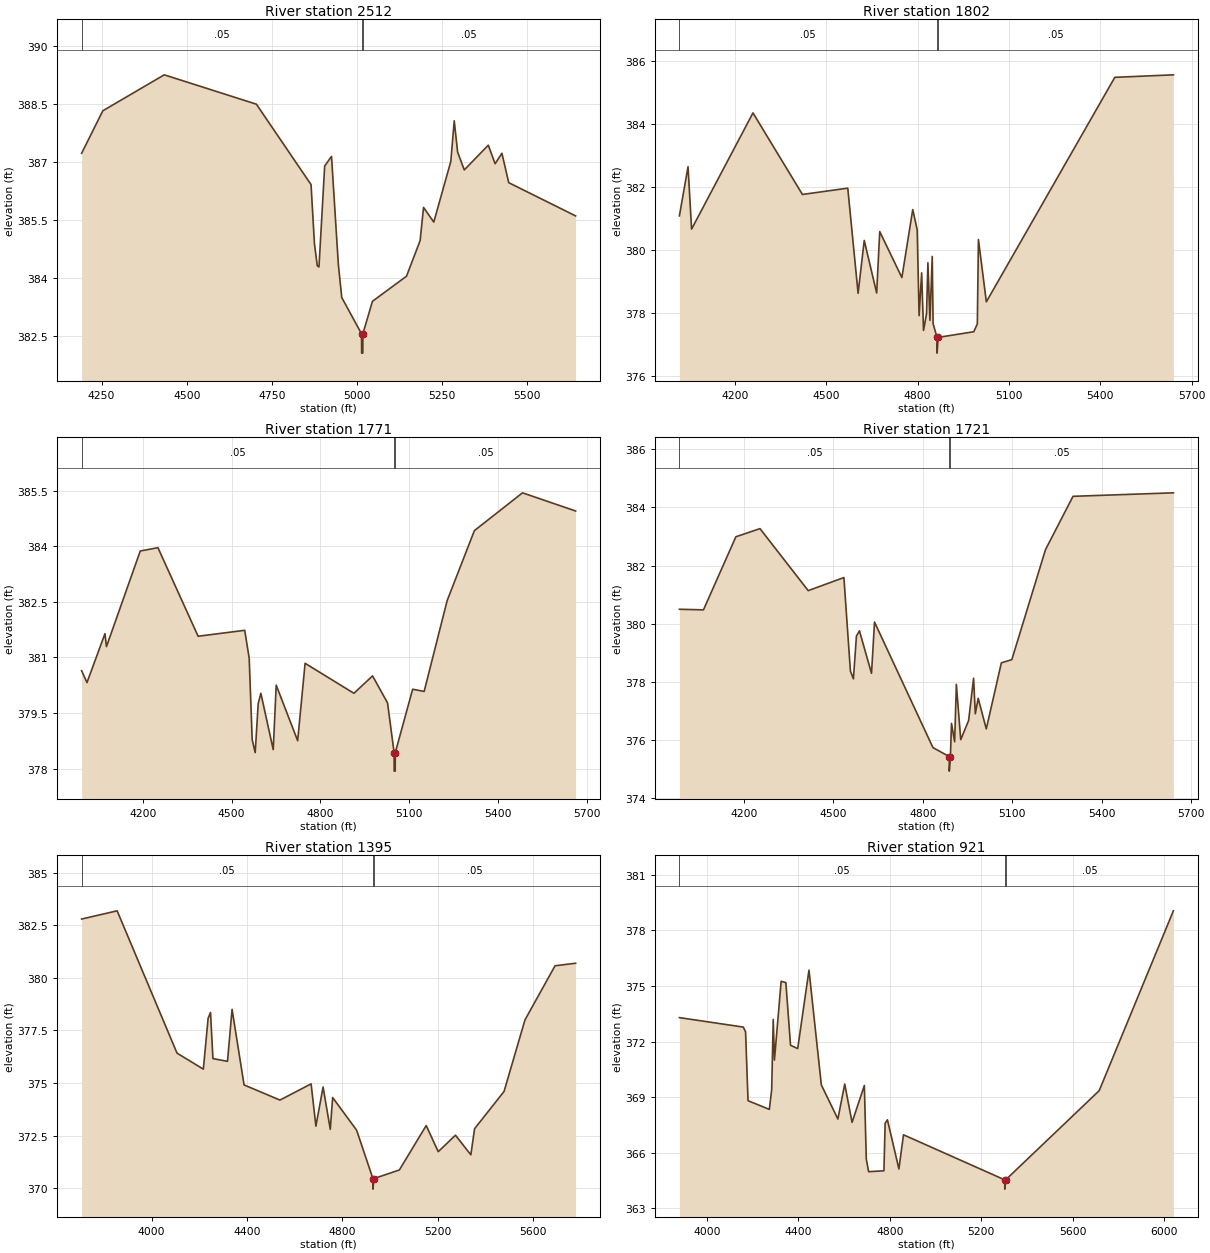
Type RM Length L Ch R = 1,2512,710,710,710
BEGIN DESCRIPTION:
Mapping XS 63166951
END DESCRIPTION:
XS GIS Cut Line= 3
      2655724.36      6870473.15      2655674.45      6869674.56
      2655687.45      6869024.74
#Sta/Elev= 30
  4191.5  387.23  4253.8  388.33  4434.1  389.26  4704.6  388.50  4865.0  386.42
  4875.0  384.89  4883.3  384.32  4888.3  384.29  4905.0  386.90  4925.1  387.15
  4945.1  384.36  4955.1  383.50  5013.2  382.56  5013.5  382.06  5017.0  382.06
  5017.2  382.56  5045.2  383.40  5145.2  384.05  5185.2  384.97  5195.2  385.83
  5225.3  385.45  5275.3  387.02  5285.3  388.07  5295.3  387.26  5314.8  386.80
  5385.3  387.44  5405.3  386.96  5425.3  387.23  5445.3  386.47  5641.6  385.61
#Mann=3,-1,0
  4191.5    0.05       0  5013.2    0.04       0  5017.2    0.05       0
Bank Sta=5013.2,5017.2
Exp/Cntr=0.3,0.1

Type RM Length L Ch R = 1,1802,31,31,31
BEGIN DESCRIPTION:
Mapping XS a2418c04
END DESCRIPTION:
XS GIS Cut Line= 6
      2656224.65      6870388.89      2656356.59      6869641.23
      2656415.23      6869594.81      2656410.34      6869531.29
      2656268.63      6869489.75      2655845.95      6869098.83
#Sta/Elev= 30
  4017.8  381.09  4046.1  382.65  4057.8  380.67  4259.4  384.36  4421.8  381.77
  4570.7  381.97  4604.6  378.63  4624.8  380.31  4665.6  378.64  4675.7  380.59
  4748.4  379.13  4784.1  381.29  4798.7  380.65  4805.0  377.92  4813.3  379.28
  4819.5  377.45  4829.4  377.98  4833.9  379.60  4840.5  377.77  4848.1  379.80
  4850.9  377.67  4863.7  377.23  4863.9  376.73  4867.7  377.23  4984.7  377.41
  4996.2  377.66  4999.8  380.34  5025.8  378.36  5447.7  385.49  5640.1  385.57
#Mann=3,-1,0
  4017.8    0.05       0  4863.7    0.03       0  4867.7    0.05       0
Bank Sta=4863.7,4867.7
Exp/Cntr=0.3,0.1

Type RM Length L Ch R = 1,1771,50,50,50
BEGIN DESCRIPTION:
Mapping XS 47bc7f02
END DESCRIPTION:
XS GIS Cut Line= 6
      2656246.64      6870388.90      2656376.14      6869643.68
      2656430.42      6869609.32      2656436.14      6869520.78
      2656312.61      6869479.98      2655860.78      6869052.57
#Sta/Elev= 30
  3993.1  380.64  4011.3  380.32  4072.0  381.64  4077.1  381.29  4191.3  383.87
  4251.0  383.96  4386.8  381.57  4544.2  381.73  4559.4  380.98  4569.5  378.78
  4579.7  378.43  4589.8  379.75  4598.8  380.03  4640.6  378.51  4650.7  380.25
  4723.2  378.75  4748.3  380.84  4913.3  380.03  4976.3  380.50  5026.9  379.77
  5049.1  378.43  5049.3  377.93  5052.8  377.93  5053.1  378.43  5111.8  380.14
  5150.6  380.08  5228.3  382.53  5320.4  384.42  5483.0  385.44  5662.4  384.95
#Mann=3,-1,0
  3993.1    0.05       0  5049.1    0.03       0  5053.1    0.05       0
Bank Sta=5049.1,5053.1
Exp/Cntr=0.3,0.1

Type RM Length L Ch R = 1,1721,326,326,326
BEGIN DESCRIPTION:
Mapping XS 023f6575
END DESCRIPTION:
XS GIS Cut Line= 6
      2656279.53      6870388.39      2656384.58      6869680.15
      2656472.55      6869616.28      2656472.55      6869538.10
      2656433.46      6869484.34      2655908.13      6869044.54
#Sta/Elev= 30
  3983.8  380.50  4064.5  380.48  4173.2  382.99  4254.1  383.27  4415.9  381.14
  4535.6  381.59  4557.4  378.38  4567.5  378.11  4577.6  379.58  4587.7  379.76
  4628.2  378.30  4638.3  380.06  4834.2  375.75  4888.9  375.44  4889.1  374.94
  4892.9  375.44  4896.5  376.58  4907.1  375.95  4912.8  377.92  4927.5  376.02
  4954.0  376.68  4970.6  378.13  4976.4  376.91  4986.1  377.44  5013.2  376.39
  5063.8  378.66  5098.9  378.77  5211.9  382.55  5304.2  384.38  5640.9  384.50
#Mann=3,-1,0
  3983.8    0.05       0  4888.9    0.04       0  4892.9    0.05       0
Bank Sta=4888.9,4892.9
Exp/Cntr=0.3,0.1

Type RM Length L Ch R = 1,1395,474,474,474
BEGIN DESCRIPTION:
Mapping XS 833895c9
END DESCRIPTION:
XS GIS Cut Line= 4
      2656583.81      6870799.34      2656705.97      6869506.85
      2656661.99      6869174.57      2656282.10      6868955.41
#Sta/Elev= 30
  3706.3  382.79  3855.3  383.18  4106.5  376.42  4216.9  375.66  4237.0  378.08
  4247.0  378.35  4257.1  376.16  4318.2  376.03  4337.4  378.50  4387.7  374.91
  4538.3  374.19  4668.9  374.96  4689.0  372.95  4719.1  374.81  4749.3  372.80
  4759.3  374.31  4859.8  372.76  4928.1  370.46  4928.3  369.96  4932.1  370.46
  5039.1  370.87  5151.7  372.98  5202.1  371.74  5274.4  372.52  5339.0  371.59
  5354.6  372.83  5478.2  374.60  5566.0  378.00  5692.1  380.57  5778.3  380.69
#Mann=3,-1,0
  3706.3    0.05       0  4928.1    0.03       0  4932.1    0.05       0
Bank Sta=4928.1,4932.1
Exp/Cntr=0.3,0.1

Type RM Length L Ch R = 1,921,598,598,598
BEGIN DESCRIPTION:
Mapping XS c7c0220b
END DESCRIPTION:
XS GIS Cut Line= 5
      2656906.32      6870501.26      2657133.54      6869636.35
      2657148.20      6869416.45      2657082.23      6869111.05
      2656371.25      6868932.69
#Sta/Elev= 30
  3879.6  373.29  4159.0  372.78  4168.9  372.52  4179.7  368.81  4272.8  368.34
  4283.1  369.41  4289.9  373.19  4295.1  371.00  4324.5  375.25  4345.1  375.18
  4365.5  371.80  4396.8  371.62  4446.2  375.85  4500.2  369.66  4572.6  367.82
  4602.4  369.71  4634.6  367.64  4688.3  369.63  4696.7  365.67  4707.0  364.98
  4773.9  365.03  4779.2  367.59  4789.2  367.78  4839.4  365.13  4859.4  366.97
  5302.2  364.54  5302.4  364.04  5306.2  364.54  5715.2  369.35  6039.7  379.05
#Mann=3,-1,0
  3879.6    0.05       0  5302.2    0.03       0  5306.2    0.05       0
Bank Sta=5302.2,5306.2
Exp/Cntr=0.3,0.1

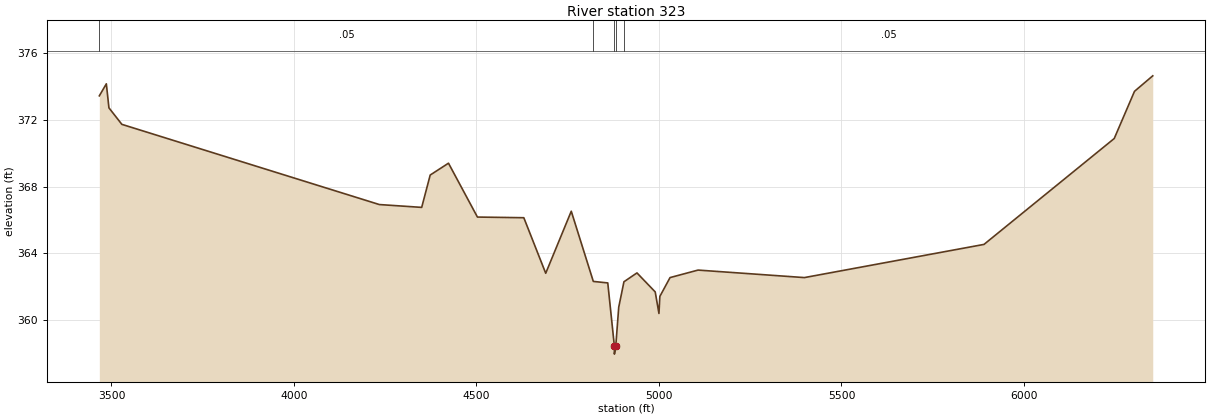
Type RM Length L Ch R = 1,323,0,0,0
BEGIN DESCRIPTION:
Little Cottonwood Creek Trib 5 1.0
END DESCRIPTION:
XS GIS Cut Line= 5
      2657001.62      6870623.38      2657605.08      6869641.23
      2657601.00      6869260.78      2657522.01      6868996.22
      2656460.07      6868818.01
#Sta/Elev= 30
  3466.8  373.44  3486.0  374.16  3493.1  372.72  3528.5  371.73  4234.0  366.92
  4350.0  366.75  4373.3  368.69  4423.4  369.40  4502.7  366.17  4629.8  366.13
  4689.8  362.80  4759.8  366.52  4820.2  362.31  4859.8  362.22  4877.8  358.45
  4878.0  357.95  4881.8  358.45  4889.8  360.76  4904.1  362.29  4939.8  362.82
  4989.8  361.68  5000.0  360.39  5002.5  361.41  5030.4  362.54  5107.1  362.99
  5398.5  362.54  5890.6  364.53  6247.4  370.88  6302.9  373.71  6352.9  374.64
#Mann=5,-1,0
  3466.8    0.05       0  4820.2    0.12       0  4877.8    0.03       0
  4881.8    0.12       0  4904.1    0.05       0
Bank Sta=4877.8,4881.8
Exp/Cntr=0.3,0.1

Chan Stop Cuts=-1