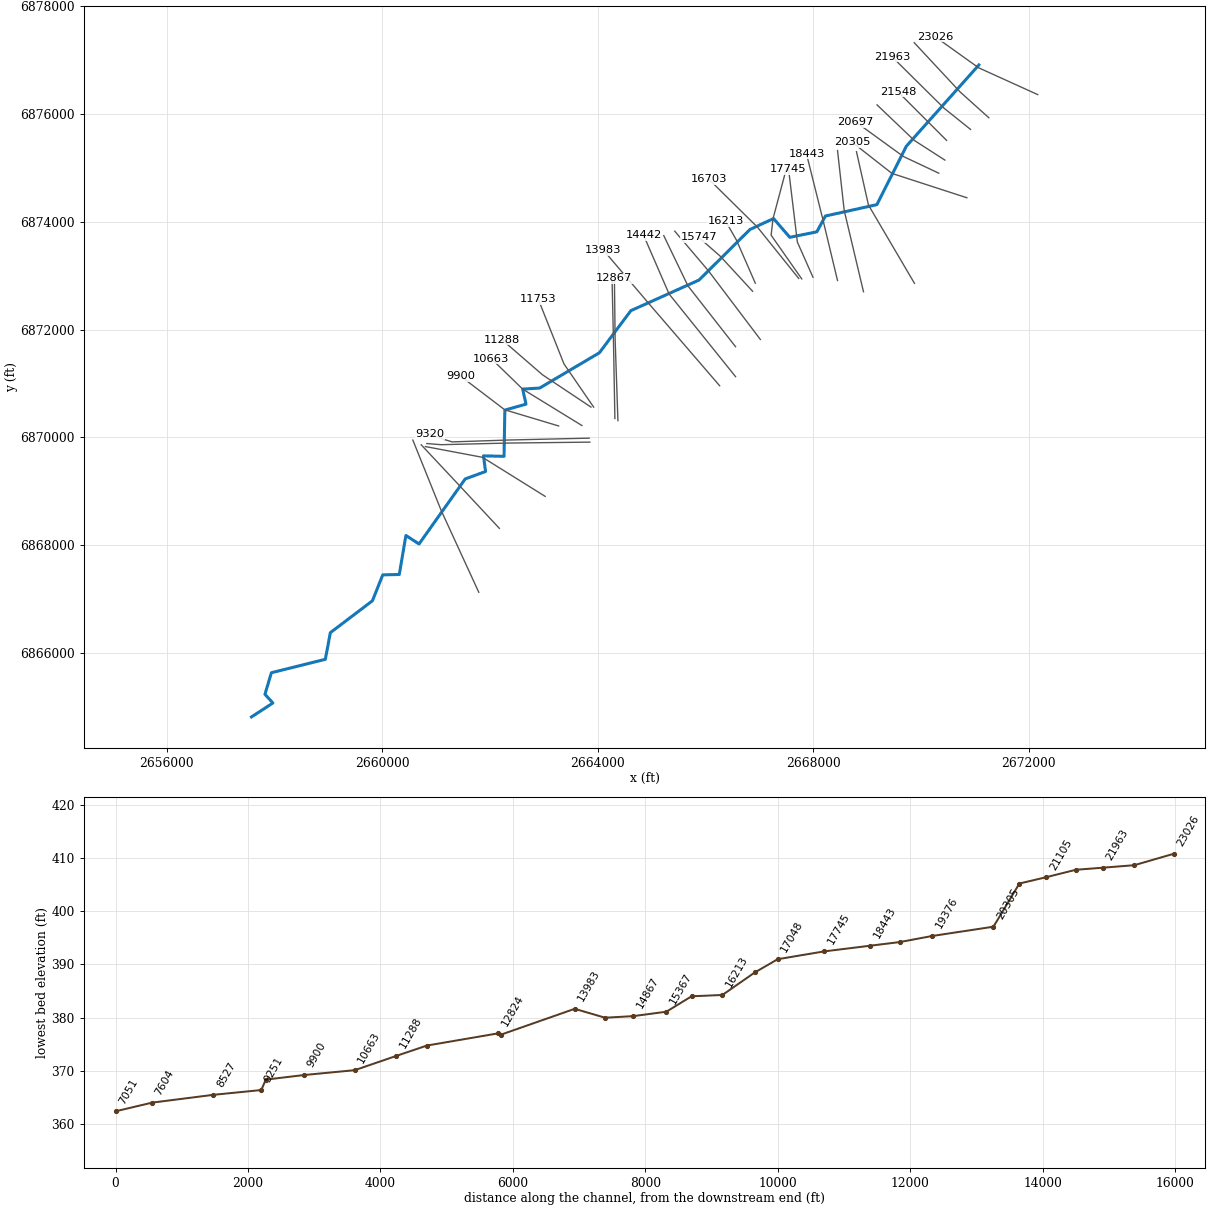
--- Little Cottonwood Creek Trib 6.prj (project) ---

Proj Title=Little Cottonwood Creek Trib 6 Base Level Engineering
Current Plan=p01
Default Exp/Contr=0.3,0.1
English Units
Geom File=g01
Flow File=f01
Plan File=p01
Y Axis Title=Elevation
X Axis Title(PF)=Main Channel Distance
X Axis Title(XS)=Station
BEGIN DESCRIPTION:
Little Cottonwood Creek Trib 6
END DESCRIPTION:
DSS Export Rating Curves= 0
DSS Export Rating Curve Sorted= 0
DSS Export Volume Flow Curves= 0
DXF OffsetX= 0
DXF OffsetY= 0
DXF ScaleX= 1
DXF ScaleY= 10

--- Little Cottonwood Creek Trib 6.p01 (plan) ---

Plan Title=Multiple Run
Short Identifier=Multiple
Geom File=g01
Flow File=f01
Subcritical Flow
K Sum by GR= 0
Std Step Tol= 0.01
Critical Tol= 0.01
Num of Std Step Trials= 20
Max Error Tol= 0.3
Flow Tol Ratio= 0.001
Split Flow NTrial= 30
Split Flow Tol= 0.02
Split Flow Ratio= 0.02
Log Output Level= 0
Friction Slope Method= 1
Unsteady Friction Slope Method= 2
Unsteady Bridges Friction Slope Method= 1
Parabolic Critical Depth
Global Vel Dist=  1 , 1 , 1
Global Log Level= 0
CheckData=True
Encroach Param= -1, 0, 0, 0
BEGIN DESCRIPTION:
Multiple Run
END DESCRIPTION:

--- Little Cottonwood Creek Trib 6.f01 (steady flow) ---

Flow Title=Multiple
Number of Profiles=7
Profile Names=10-year,25-year,50-year,1pct_min,100-year,1pct_plu,500-year
River Rch & RM= Little Cottonwoo,Reach-1,23026
     442     583     694     411     819    1634    1140
River Rch & RM= Little Cottonwoo,Reach-1,22431
     614     826     997     597    1191    2376    1699
River Rch & RM= Little Cottonwoo,Reach-1,19376
     676     911    1101     659    1315    2623    1877
River Rch & RM= Little Cottonwoo,Reach-1,16703
    1111    1543    1904    1162    2318    4625    3442
River Rch & RM= Little Cottonwoo,Reach-1,15747
    1342    1875    2321    1420    2833    5652    4227
River Rch & RM= Little Cottonwoo,Reach-1,9320
    1459    2041    2528    1547    3086    6157    4607
Boundary for River Rch & Prof#=Little Cottonwoo,Reach-1,1
Up Type=0
Dn Type=3
Dn Slope=0.005
Boundary for River Rch & Prof#=Little Cottonwoo,Reach-1,2
Up Type=0
Dn Type=3
Dn Slope=0.005
Boundary for River Rch & Prof#=Little Cottonwoo,Reach-1,3
Up Type=0
Dn Type=3
Dn Slope=0.005
Boundary for River Rch & Prof#=Little Cottonwoo,Reach-1,4
Up Type=0
Dn Type=3
Dn Slope=0.005
Boundary for River Rch & Prof#=Little Cottonwoo,Reach-1,5
Up Type=0
Dn Type=3
Dn Slope=0.005
Boundary for River Rch & Prof#=Little Cottonwoo,Reach-1,6
Up Type=0
Dn Type=3
Dn Slope=0.005
Boundary for River Rch & Prof#=Little Cottonwoo,Reach-1,7
Up Type=0
Dn Type=3
Dn Slope=0.005

--- Little Cottonwood Creek Trib 6.g01 (geometry) ---

Geom Title=Existing Conditions
Program Version=4.10

River Reach=Little Cottonwoo,Reach-1
Reach XY= 30
        2671076.        6876911.      2669731.58      6875405.42
      2669182.19      6874318.82      2668227.56      6874107.19
      2668068.09      6873813.91      2667565.48      6873712.18
      2667265.38      6874060.41      2666827.36      6873857.71
      2665882.05      6872919.16      2664616.19      6872350.57
      2664032.17      6871568.86      2662924.55      6870914.53
      2662608.68      6870894.73      2662671.08      6870616.03
      2662278.04      6870505.15      2662262.56      6869647.36
      2661880.92      6869655.98      2661920.62      6869366.18
      2661542.44      6869227.79       2660685.4      6868021.04
      2660442.06      6868178.23      2660318.31      6867454.48
      2660012.43      6867447.54      2659820.53      6866966.26
       2659039.2      6866374.73      2658946.65       6865880.4
      2657945.42      6865631.54      2657825.62      6865231.14
      2657973.35       6865069.5        2657576.        6864811.

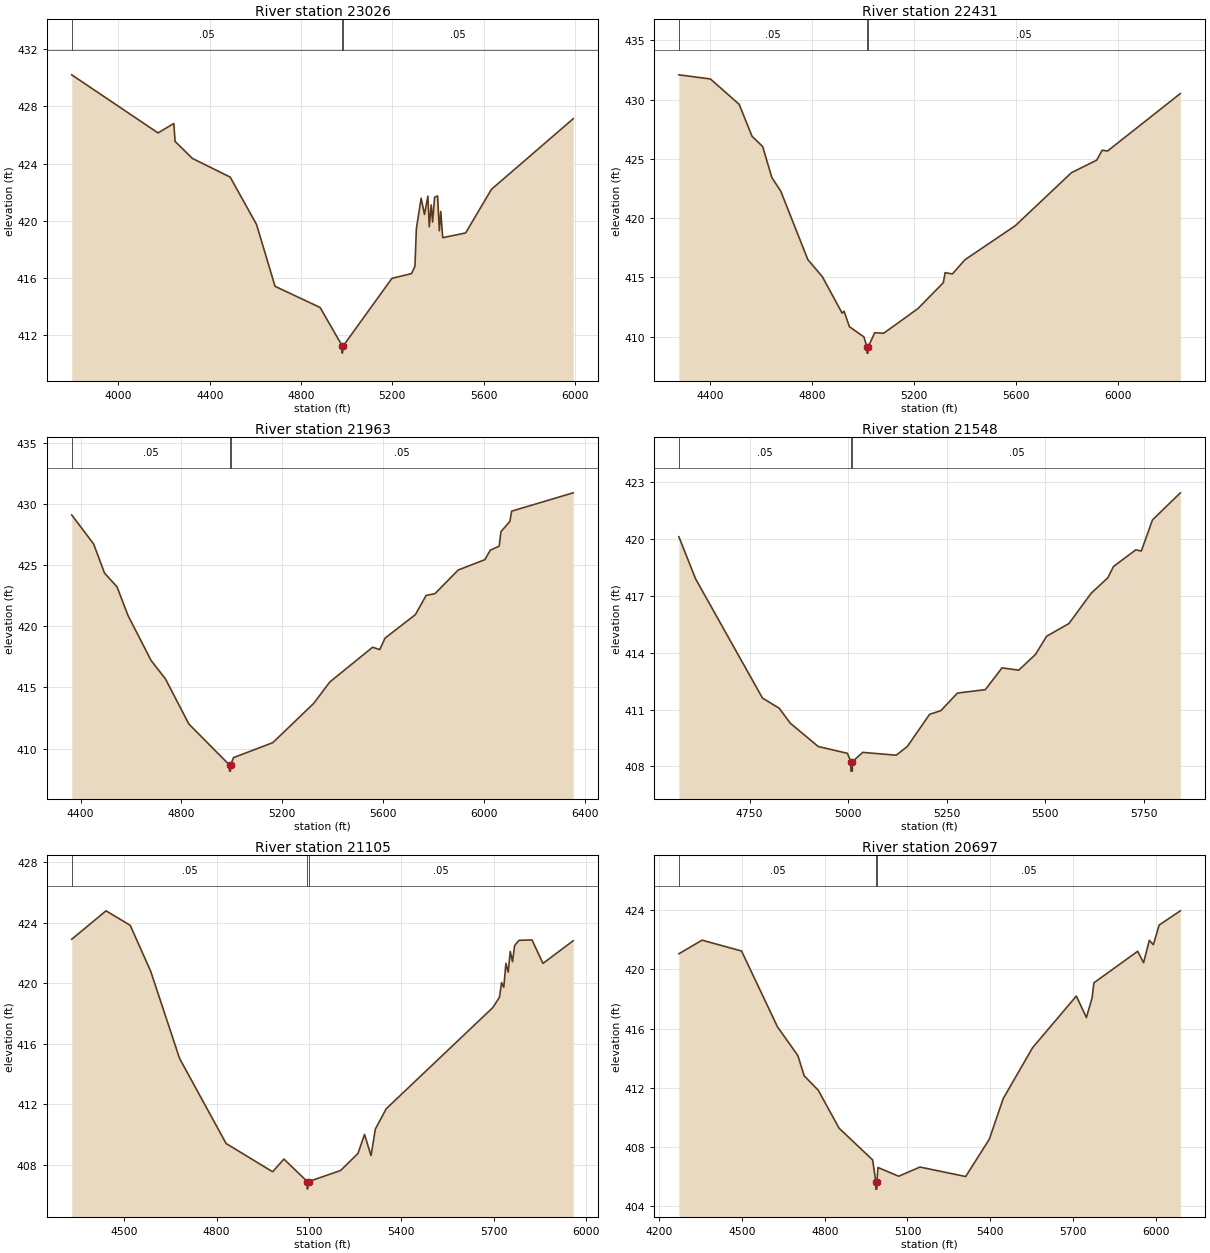
Type RM Length L Ch R = 1 ,23026   ,595,595,595
BEGIN DESCRIPTION:
Little Cottonwood Creek Trib 6 43.0
END DESCRIPTION:
XS GIS Cut Line= 3
      2672167.35      6876360.58      2671070.32      6876858.64
      2670262.64      6877436.48
#Sta/Elev= 30
  3795.2   430.2  4173.4  426.14  4242.6   426.8  4248.1  425.55  4323.8  424.36
  4489.8  423.05  4605.2  419.74  4686.3  415.42  4883.9  413.94  4980.8  411.25
    4981  410.75  4984.8  411.25  5198.8  415.98  5284.8  416.31  5299.5  416.83
  5305.7  419.44  5326.6  421.58  5341.3  420.44  5356.1  421.72  5362.2  419.58
  5370.8  421.11  5376.9  419.91  5385.5  421.64  5398.8  421.74  5406.4   419.3
  5412.6  420.65  5421.2  418.82  5521.7  419.15  5634.9   422.2  5993.1  427.13
#Mann= 3 ,-1 , 0
  3795.2     .05       0  4980.8     .03       0  4984.8     .05       0
Bank Sta=4980.8,4984.8
XS Rating Curve= 0 ,0
Exp/Cntr=0.3,0.1

Type RM Length L Ch R = 1 ,22431   ,468,468,468
BEGIN DESCRIPTION:
Little Cottonwood Creek Trib 6 42.0
END DESCRIPTION:
XS GIS Cut Line= 3
      2671260.25      6875930.87        2670726.        6876411.
       2669875.7       6877324.1
#Sta/Elev= 30
  4277.4  432.09  4401.1  431.74  4513.9   429.6    4564  426.91  4605.9  426.04
  4641.8  423.43  4676.9  422.27    4783   416.5  4839.8  415.06  4917.6  411.98
  4925.1  412.15    4946  410.84  5002.8  409.98  5014.9  409.11  5015.2  408.61
  5018.7  408.61  5018.9  409.11  5045.3  410.33  5080.5  410.29  5214.8  412.37
    5314  414.55  5321.3   415.4  5349.7  415.29    5399  416.49  5596.9  419.37
  5816.2  423.83  5915.4  424.89  5936.9  425.73  5957.9  425.66  6243.4  430.51
#Mann= 3 ,-1 , 0
  4277.4     .05       0  5014.9     .04       0  5018.9     .05       0
Bank Sta=5014.9,5018.9
XS Rating Curve= 0 ,0
Exp/Cntr=0.3,0.1

Type RM Length L Ch R = 1 ,21963   ,415,415,415
BEGIN DESCRIPTION:
Little Cottonwood Creek Trib 6 41.0
END DESCRIPTION:
XS GIS Cut Line= 3
      2670921.65       6875713.9        2670426.        6876111.
      2669463.33      6877063.72
#Sta/Elev= 30
  4364.9  429.12  4451.8  426.74    4495  424.36  4544.7  423.23  4587.9   420.9
  4679.7  417.21  4736.7   415.7  4829.5  412.01  4990.8  408.65    4991  408.15
  4994.5  408.15  4994.8  408.65  5007.1  409.26  5162.6  410.48  5325.2   413.7
  5388.9  415.45  5558.6  418.29  5586.9   418.1  5608.1  419.04  5728.3  420.96
  5770.8  422.53  5806.1  422.68  5898.1  424.61  6004.1  425.46  6025.3  426.23
  6060.7  426.57  6067.8  427.75  6103.1  428.59  6110.2  429.43  6354.4  430.93
#Mann= 3 ,-1 , 0
  4364.9     .05       0  4990.8     .04       0  4994.8     .05       0
Bank Sta=4990.8,4994.8
XS Rating Curve= 0 ,0
Exp/Cntr=0.3,0.1

Type RM Length L Ch R = 1 ,21548   ,443,443,443
BEGIN DESCRIPTION:
Little Cottonwood Creek Trib 6 40.0
END DESCRIPTION:
XS GIS Cut Line= 3
        2670476.        6875511.        2670176.        6875811.
        2669576.        6876411.
#Sta/Elev= 30
  4570.7  420.12  4613.1   417.9  4782.8  411.61  4825.3  411.07  4853.5  410.28
  4924.3  409.05  4998.5  408.69  5007.1  408.25  5007.4  407.75  5010.9  407.75
  5011.1  408.25  5037.4  408.74  5122.2  408.59  5150.5  409.05  5207.1  410.75
  5235.4  410.94  5277.8  411.87  5348.5  412.05  5390.9   413.2  5433.4  413.08
  5475.8  413.91  5504.1  414.87  5560.7  415.54  5617.2  417.14  5659.6  417.96
  5673.8  418.55  5730.4  419.43  5744.5  419.37  5772.8  421.01  5843.5  422.44
#Mann= 3 ,-1 , 0
  4570.7     .05       0  5007.1     .04       0  5011.1     .05       0
Bank Sta=5007.1,5011.1
XS Rating Curve= 0 ,0
Exp/Cntr=0.3,0.1

Type RM Length L Ch R = 1 ,21105   ,408,408,408
BEGIN DESCRIPTION:
Little Cottonwood Creek Trib 6 39.0
END DESCRIPTION:
XS GIS Cut Line= 3
      2670444.22      6875145.32        2669876.        6875511.
      2669185.56      6876169.61
#Sta/Elev= 30
    4329  422.91  4440.5  424.79  4519.1  423.83  4585.8  420.78  4679.5  415.02
  4830.7  409.39  4981.9  407.52  5018.7  408.36  5094.7  406.87    5095  406.37
  5098.7  406.87  5202.7   407.6  5259.3  408.73  5280.7  409.99  5301.8  408.59
  5315.9  410.35  5351.2  411.69  5697.8  418.39  5719.2  419.07  5726.1  420.04
  5733.3  419.73  5740.2  421.31  5747.5  420.73  5754.4   422.1  5761.6  421.42
  5768.5  422.49  5782.7  422.84  5825.1  422.86  5860.7  421.31  5958.9  422.81
#Mann= 3 ,-1 , 0
    4329     .05       0  5094.7     .03       0  5098.7     .05       0
Bank Sta=5094.7,5098.7
XS Rating Curve= 0 ,0
Exp/Cntr=0.3,0.1

Type RM Length L Ch R = 1 ,20697   ,392,392,392
BEGIN DESCRIPTION:
Little Cottonwood Creek Trib 6 38.0
END DESCRIPTION:
XS GIS Cut Line= 3
      2670331.42      6874902.24        2669676.        6875211.
      2668790.79      6875852.63
#Sta/Elev= 30
  4271.4  421.05  4355.5  421.97  4498.5  421.24  4628.9  416.12  4702.8  414.18
  4725.6  412.82  4776.7  411.84  4852.2  409.28  4973.8  407.14  4985.3  405.67
  4985.5  405.17    4989  405.17  4989.3  405.67  4993.1  406.63  5068.2  406.04
  5145.5  406.66    5311  406.02  5396.8  408.54  5447.1  411.28  5553.8  414.72
  5712.2   418.2  5748.6  416.75  5769.5  418.09  5775.7  419.09  5934.6  421.22
  5955.9  420.45  5976.7  421.96  5991.4  421.66  6012.3  422.99  6089.2  423.95
#Mann= 3 ,-1 , 0
  4271.4     .05       0  4985.3     .04       0  4989.3     .05       0
Bank Sta=4985.3,4989.3
XS Rating Curve= 0 ,0
Exp/Cntr=0.3,0.1

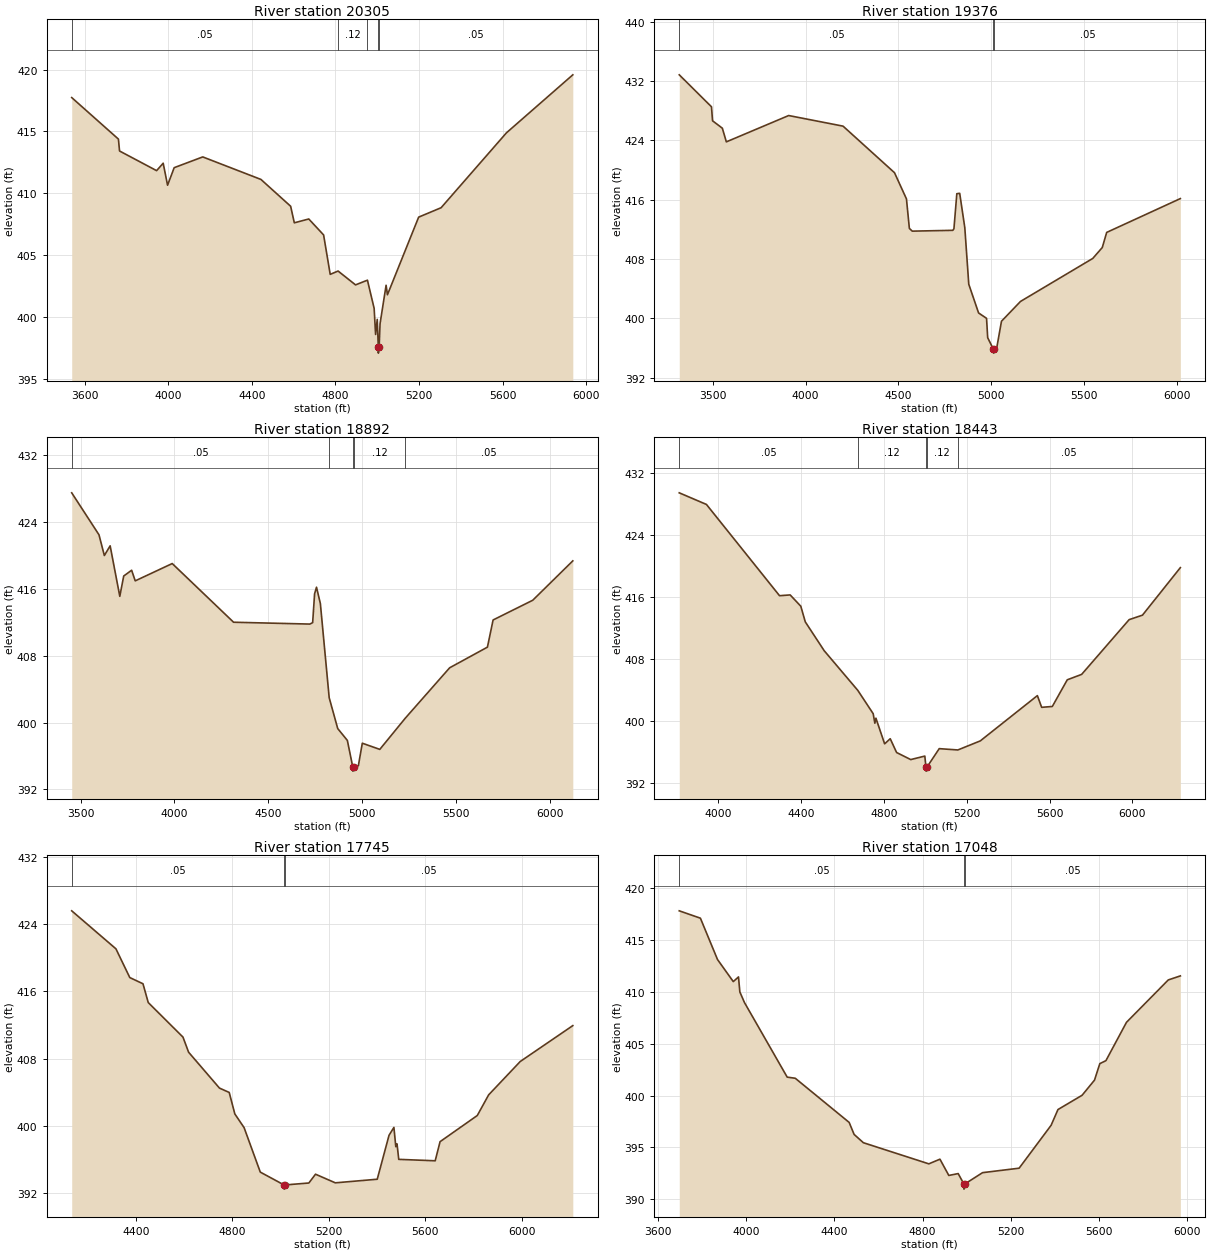
Type RM Length L Ch R = 1 ,20305   ,929,929,929
BEGIN DESCRIPTION:
Little Cottonwood Creek Trib 6 37.0
END DESCRIPTION:
XS GIS Cut Line= 3
      2670852.21      6874446.52      2669461.97      6874897.95
      2668725.51      6875475.15
#Sta/Elev= 30
  3538.3  417.74  3761.8  414.38  3767.1  413.42  3944.4  411.83  3975.9  412.43
  3996.9  410.65  4028.5  412.07  4165.2  412.94  4443.5  411.12  4585.7  408.95
  4603.3  407.61  4672.5  407.92  4743.4  406.63    4775  403.44  4812.7  403.71
  4896.2  402.59  4953.1  402.97  4985.2  400.69  4992.1  398.58    5000   399.8
  5005.1  397.57  5005.4  397.07  5009.1  397.57  5013.5  399.45  5042.4  402.56
  5048.8  401.79  5198.2  408.07  5305.5  408.83  5618.3  414.89  5935.7  419.58
#Mann= 5 ,-1 , 0
  3538.3     .05       0  4812.7     .12       0  4953.1     .05       0
  5005.1     .03       0  5009.1     .05       0
Bank Sta=5005.1,5009.1
XS Rating Curve= 0 ,0
Exp/Cntr=0.3,0.1

Type RM Length L Ch R = 1 ,19376   ,484,484,484
BEGIN DESCRIPTION:
Little Cottonwood Creek Trib 6 35.0
END DESCRIPTION:
XS GIS Cut Line= 3
      2669879.99      6872858.01        2669026.        6874311.
      2668803.62      6875301.57
#Sta/Elev= 30
  3318.8  432.85  3492.4  428.54  3498.2  426.65    3551  425.65  3572.5  423.81
  3908.5  427.36  4201.5  425.93  4478.8  419.65  4543.2  416.12  4558.9  412.14
  4574.5  411.77  4793.3  411.88  4799.1  412.09  4814.7  416.82  4830.2  416.87
  4857.7  412.24  4879.1  404.61  4931.9  400.74  4974.9  400.01    4981   397.4
  5012.3  395.82  5012.7  395.32  5016.5  395.82  5028.4  395.83  5055.4  399.62
  5157.9  402.29  5547.4  408.09  5598.6  409.56  5622.4   411.6  6019.4  416.16
#Mann= 3 ,-1 , 0
  3318.8     .05       0  5012.3     .03       0  5016.5     .05       0
Bank Sta=5012.3,5016.5
XS Rating Curve= 0 ,0
Exp/Cntr=0.3,0.1

Type RM Length L Ch R = 1 ,18892   ,449,449,449
BEGIN DESCRIPTION:
Little Cottonwood Creek Trib 6 34.0
END DESCRIPTION:
XS GIS Cut Line= 3
      2668933.83      6872701.74        2668576.        6874211.
      2668452.07      6875323.22
#Sta/Elev= 30
  3453.1  427.48  3598.4  422.46    3627  419.98  3657.9  421.14  3709.3   415.1
  3730.2  417.53  3772.4  418.22  3791.5  416.95  3988.7  419.02  4315.6     412
    4722  411.78    4737  411.95  4747.3   415.4  4757.5  416.19  4778.1  414.23
  4825.1  402.97  4870.6  399.28    4922  397.86  4950.7  394.69    4951  394.19
  4954.9  394.69  4980.5  394.83  5001.6  397.53  5094.8  396.79  5230.5  400.52
    5467  406.55  5668.3  409.02  5698.5  412.27  5909.8  414.63  6123.3  419.34
#Mann= 5 ,-1 , 0
  3453.1     .05       0  4825.1     .12       0  4950.7     .07       0
  4954.9     .12       0  5230.5     .05       0
Bank Sta=4950.7,4954.9
XS Rating Curve= 0 ,0
Exp/Cntr=0.3,0.1

Type RM Length L Ch R = 1 ,18443   ,698,698,698
BEGIN DESCRIPTION:
Little Cottonwood Creek Trib 6 33.0
END DESCRIPTION:
XS GIS Cut Line= 3
      2668452.05       6872910.1        2668176.        6874061.
      2667875.99      6875261.02
#Sta/Elev= 30
  3811.5   429.4  3942.8   427.9  4295.8  416.13  4347.2  416.23  4398.6  414.77
  4420.3  412.75  4511.7  409.03  4673.8  403.92  4748.2  400.91  4756.3  399.68
  4761.4  400.33  4803.5  397.02  4830.5  397.68  4861.4   395.9  4929.5  394.99
  4997.6  395.44  5003.2     394  5003.6   393.5  5007.6     394  5067.2   396.4
  5157.2  396.23  5265.6   397.4  5541.4  403.24    5562  401.73  5613.5  401.84
  5685.7  405.28  5755.2  405.98  5984.6  413.04    6049  413.62    6232  419.75
#Mann= 5 ,-1 , 0
  3811.5     .05       0  4673.8     .12       0  5003.2     .07       0
  5007.6     .12       0  5157.2     .05       0
Bank Sta=5003.2,5007.6
XS Rating Curve= 0 ,0
Exp/Cntr=0.3,0.1

Type RM Length L Ch R = 1 ,17745   ,697,697,697
BEGIN DESCRIPTION:
Little Cottonwood Creek Trib 6 32.0
END DESCRIPTION:
XS GIS Cut Line= 3
      2667996.32      6872970.86      2667706.82      6873624.43
      2667543.27      6874977.47
#Sta/Elev= 30
  4133.8  425.62  4317.1  421.09  4374.6  417.66  4429.3  416.92  4451.1  414.68
  4595.1  410.56  4618.4  408.76  4746.4  404.48  4786.8  403.96  4810.1   401.4
  4848.6  399.76  4915.7  394.46  5014.1  392.93  5014.6  392.43  5018.6  392.93
  5117.1  393.16  5144.7  394.21  5226.7  393.18  5400.6  393.61  5449.5  398.85
  5469.7  399.79  5477.6  397.49  5482.6  397.83  5489.8  395.98  5640.9  395.81
  5661.1  398.09  5815.5  401.21  5862.5  403.67  5993.5  407.65  6211.5  411.93
#Mann= 3 ,-1 , 0
  4133.8     .05       0  5014.1     .03       0  5018.6     .05       0
Bank Sta=5014.1,5018.6
XS Rating Curve= 0 ,0
Exp/Cntr=0.3,0.1

Type RM Length L Ch R = 1 ,17048   ,345,345,345
BEGIN DESCRIPTION:
Little Cottonwood Creek Trib 6 31.0
END DESCRIPTION:
XS GIS Cut Line= 4
      2667787.97      6872940.48      2667219.42      6873752.07
      2667255.87      6874061.41      2667505.64      6874996.84
#Sta/Elev= 30
  3697.6  417.83  3793.4  417.12  3870.9  413.13  3942.4     411    3966  411.45
  3972.1     410    3993  408.98  4186.6  401.78  4223.2  401.67  4467.4  397.41
  4489.9  396.25  4531.8  395.45  4828.4  393.41  4878.8  393.86    4919  392.29
  4961.4  392.47  4987.2  391.47  4987.7  390.97  4991.8  391.47    5072  392.56
  5237.6  392.99  5382.5  397.13  5413.6  398.65    5523  400.03  5579.2  401.49
  5603.2  403.08  5630.9  403.37  5724.1  407.07  5913.5  411.16  5968.2  411.55
#Mann= 3 ,-1 , 0
  3697.6     .05       0  4987.2     .03       0  4991.8     .05       0
Bank Sta=4987.2,4991.8
XS Rating Curve= 0 ,0
Exp/Cntr=0.3,0.1

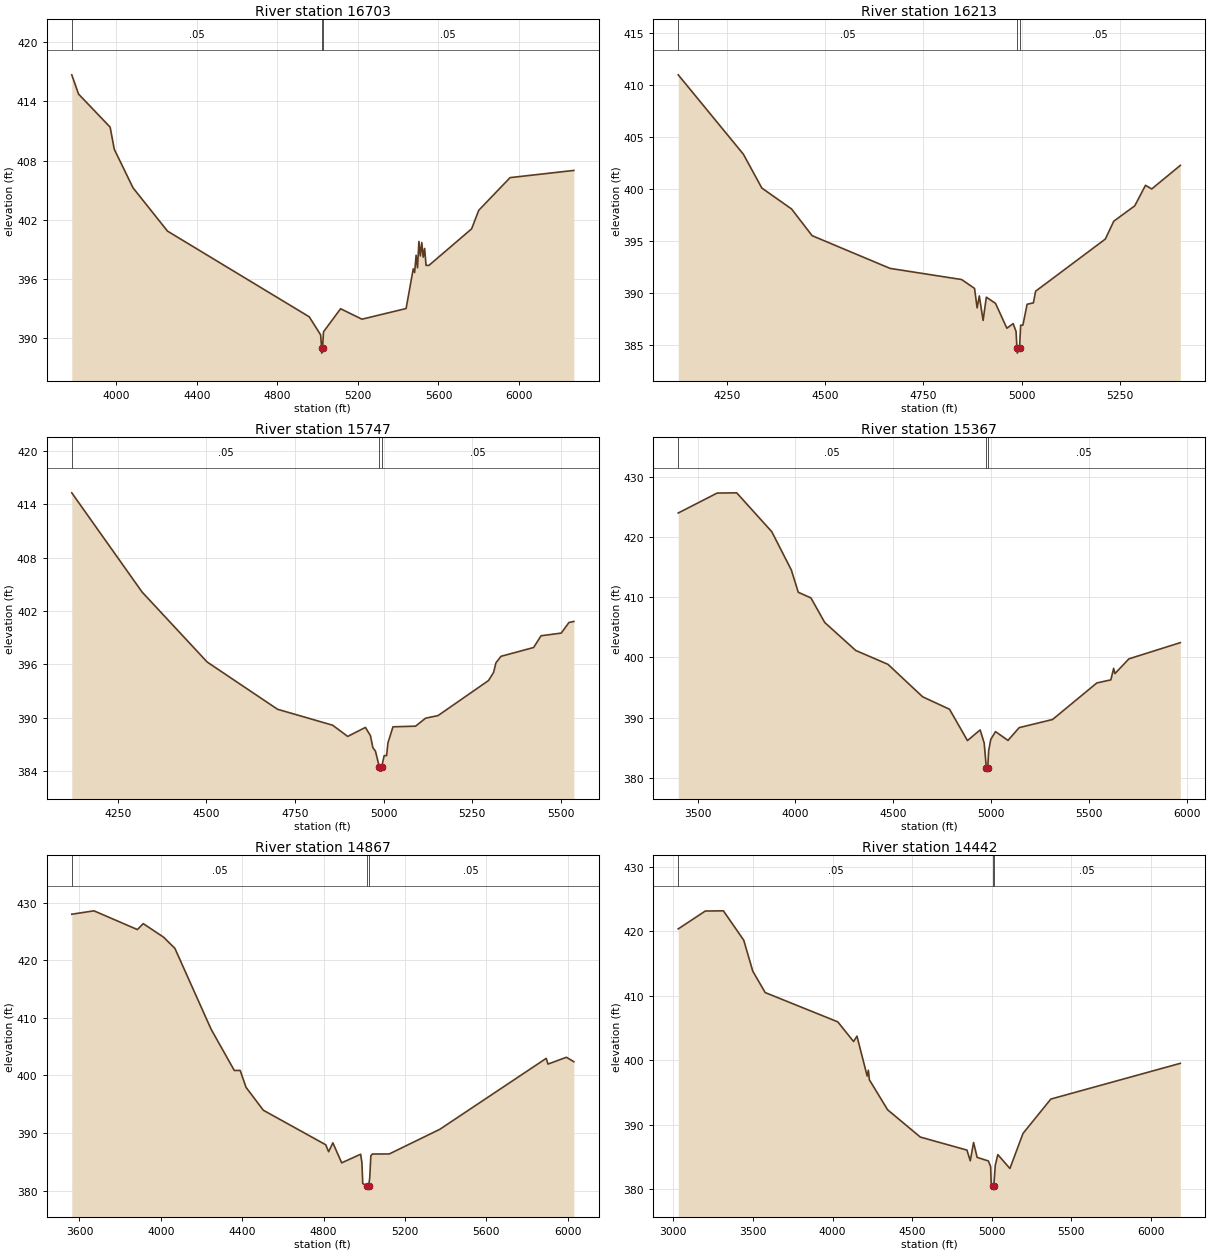
Type RM Length L Ch R = 1 ,16703   ,490,490,490
BEGIN DESCRIPTION:
Little Cottonwood Creek Trib 6 30.0
END DESCRIPTION:
XS GIS Cut Line= 3
      2667731.58      6872949.12      2666966.38      6873900.09
      2666060.81       6874793.5
#Sta/Elev= 30
  3779.4   416.7  3813.1  414.75  3969.8   411.4  3990.6  409.15  4083.4  405.25
  4254.6  400.86  4958.5  392.17    5015  390.34  5019.8  388.99  5020.3  388.49
  5024.4  388.99  5029.2  390.65    5114  392.99  5220.1  391.93  5439.3  393.01
  5474.7  397.03  5481.7  396.66  5488.9  398.41  5495.9  397.14    5503  399.81
    5510  398.34  5517.1   399.7  5524.2  398.21  5531.3   399.1  5538.3  397.39
  5552.5  397.38  5764.6  401.09    5800  402.97  5955.6  406.28  6272.1  407.01
#Mann= 3 ,-1 , 0
  3779.4     .05       0  5019.8     .03       0  5024.4     .05       0
Bank Sta=5019.8,5024.4
XS Rating Curve= 0 ,0
Exp/Cntr=0.3,0.1

Type RM Length L Ch R = 1 ,16213   ,466,466,466
BEGIN DESCRIPTION:
Little Cottonwood Creek Trib 6 29.0
END DESCRIPTION:
XS GIS Cut Line= 3
      2666926.01      6872860.98        2666576.        6873661.
      2666376.02      6874010.96
#Sta/Elev= 30
  4126.6  410.96  4292.3  403.34  4339.1   400.1  4414.7  398.09  4466.9  395.53
    4665  392.39    4847  391.32  4879.8  390.47  4886.4   388.6  4891.9  389.75
  4901.6   387.4  4909.8  389.63  4933.2  389.03    4962  386.65    4978  387.09
  4985.4  386.33  4987.6  384.76  4988.6  384.26  4994.2  384.76  4997.1  386.94
  5002.7  386.94  5013.5  388.95  5029.4  389.08  5035.1   390.2  5212.2   395.2
  5233.8  396.92  5287.1  398.39  5314.4  400.36  5330.2  400.01  5402.9  402.27
#Mann= 3 ,-1 , 0
  4126.6     .05       0  4987.6     .03       0  4994.2     .05       0
Bank Sta=4987.6,4994.2
XS Rating Curve= 0 ,0
Exp/Cntr=0.3,0.1

Type RM Length L Ch R = 1 ,15747   ,380,380,380
BEGIN DESCRIPTION:
Little Cottonwood Creek Trib 6 28.0
END DESCRIPTION:
XS GIS Cut Line= 3
      2666876.01      6872710.99        2666276.        6873361.
      2665876.01      6873710.99
#Sta/Elev= 30
  4120.1  415.28  4318.3  404.14    4502  396.27  4700.5  390.96  4855.9  389.17
  4898.4  387.91  4948.3  388.92  4962.5     388  4969.3  386.66  4976.6  386.26
  4987.4  384.51  4988.5  384.01  4993.2  384.01  4994.2  384.51  5001.3  385.75
    5008  385.75  5011.8  387.17  5026.1  388.99  5089.7  389.06  5118.1  389.96
  5153.2  390.25  5295.6  394.19  5309.8   395.1  5316.5  396.18  5330.7  396.91
  5422.8   397.9  5443.7  399.22  5500.6  399.52  5522.4  400.71  5536.2  400.83
#Mann= 3 ,-1 , 0
  4120.1     .05       0  4987.4     .04       0  4994.2     .05       0
Bank Sta=4987.4,4994.2
XS Rating Curve= 0 ,0
Exp/Cntr=0.3,0.1

Type RM Length L Ch R = 1 ,15367   ,500,500,500
BEGIN DESCRIPTION:
Little Cottonwood Creek Trib 6 27.0
END DESCRIPTION:
XS GIS Cut Line= 3
      2667019.77      6871816.31      2666055.57      6873091.27
       2665431.2      6873825.89
#Sta/Elev= 30
  3401.5  423.97  3600.1  427.28  3699.9  427.32  3878.9  420.87  3978.8  414.51
  4014.2  410.81  4078.7  409.88  4149.4  405.79  4307.5  401.15  4471.9  398.85
  4648.9  393.46  4786.2  391.39  4877.7  386.19  4942.3  387.96  4963.1  385.79
  4974.2  381.62  4975.3  381.12  4981.1  381.62  4985.9  384.52  4996.7  386.39
  5020.9  387.68  5084.6  386.22  5141.7  388.34    5312  389.69  5538.2  395.76
  5609.6  396.27  5623.9  398.18  5630.4  397.31  5701.8  399.76  5964.1  402.45
#Mann= 3 ,-1 , 0
  3401.5     .05       0  4974.2     .04       0  4981.1     .05       0
Bank Sta=4974.2,4981.1
XS Rating Curve= 0 ,0
Exp/Cntr=0.3,0.1

Type RM Length L Ch R = 1 ,14867   ,425,425,425
BEGIN DESCRIPTION:
Little Cottonwood Creek Trib 6 26.0
END DESCRIPTION:
XS GIS Cut Line= 3
       2666559.7      6871681.76        2665676.        6872811.
      2665227.23      6873743.41
#Sta/Elev= 30
    3562  427.97  3671.2  428.56  3884.6  425.31  3913.5  426.34    4013     424
  4069.1  422.05  4247.2  408.02  4361.2  400.87  4390.1  400.87    4419  397.94
    4504  393.97  4810.6  387.99    4825  386.78  4845.8  388.32  4889.2  384.85
  4982.3  386.34  4988.7  384.85  4992.7  381.27  5014.6  380.79  5015.7  380.29
  5021.6  380.79  5027.1  382.26  5032.6  386.07  5040.3  386.38  5123.1  386.39
    5372  390.67  5894.8  402.97  5903.6  401.98  5994.1  403.16  6030.7  402.39
#Mann= 3 ,-1 , 0
    3562     .05       0  5014.6     .03       0  5021.6     .05       0
Bank Sta=5014.6,5021.6
XS Rating Curve= 0 ,0
Exp/Cntr=0.3,0.1

Type RM Length L Ch R = 1 ,14442   ,459,459,459
BEGIN DESCRIPTION:
Little Cottonwood Creek Trib 6 25.0
END DESCRIPTION:
XS GIS Cut Line= 3
      2666559.72      6871126.18        2665326.        6872661.
      2664854.34      6873746.89
#Sta/Elev= 30
  3030.8  420.33  3200.8   423.1  3314.4  423.13  3442.4  418.57  3498.9  413.78
  3576.9  410.46  4032.8  405.92    4132  402.87  4153.2  403.71  4217.4  397.52
  4224.8  398.42  4231.2  396.94  4345.7  392.29  4551.2  388.06    4844  386.04
  4864.8  384.38  4885.6  387.22    4908  384.91  4978.4  384.36  4992.8  383.48
  4996.8  380.52  5005.4  380.49  5006.5  379.99  5012.5  380.49  5021.8  383.69
  5037.9  385.34  5113.7  383.19  5196.2  388.63  5370.7  393.95  6183.9  399.49
#Mann= 3 ,-1 , 0
  3030.8     .05       0  5005.4     .03       0  5012.5     .05       0
Bank Sta=5005.4,5012.5
XS Rating Curve= 0 ,0
Exp/Cntr=0.3,0.1

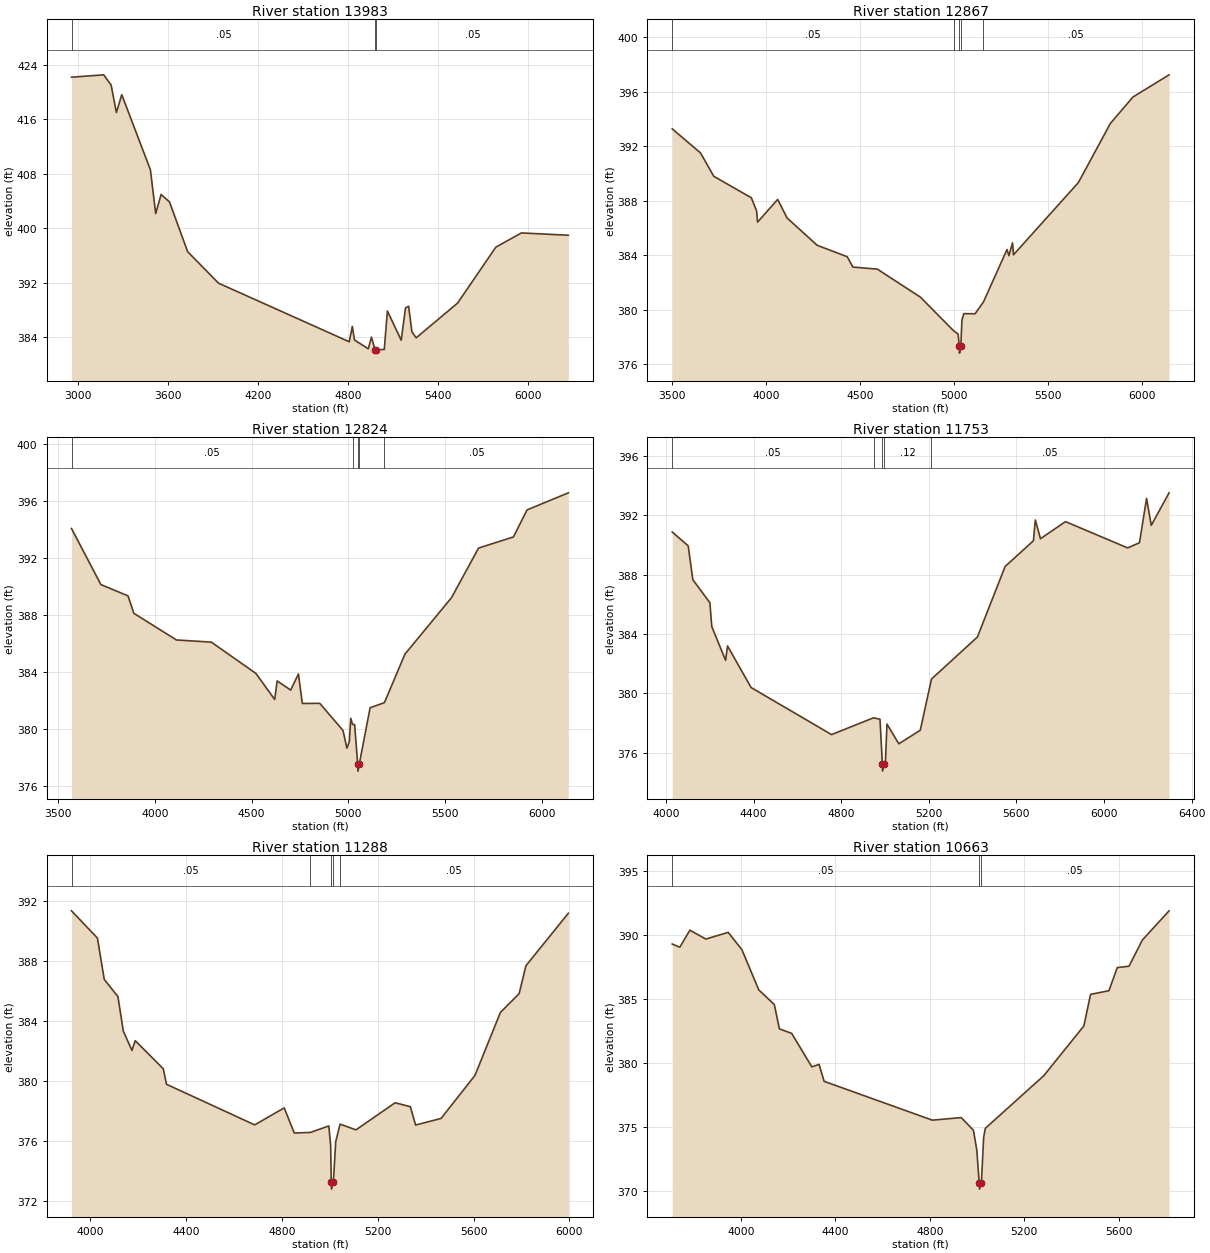
Type RM Length L Ch R = 1 ,13983   ,1116,1116,1116
BEGIN DESCRIPTION:
Little Cottonwood Creek Trib 6 24.0
END DESCRIPTION:
XS GIS Cut Line= 3
      2666264.59       6870956.9        2664926.        6872511.
      2664107.45      6873474.29
#Sta/Elev= 30
  2953.9   422.2  3168.9  422.55  3218.3  421.05  3253.4  417.01  3289.3  419.63
  3480.5  408.59  3515.6  402.16  3551.8  404.98  3607.8  403.87  3728.5  396.58
  3934.7  391.94    4807  383.33  4827.8  385.59  4842.1  383.59  4934.2   382.3
  4955.1  384.02  4979.7  382.16  4980.8  381.66  4987.6  382.16  5040.7  382.19
  5061.6  387.85  5153.8  383.56  5182.4   388.3  5203.2  388.55  5225.2  384.78
  5253.8  383.91  5529.9  389.01  5785.3  397.23  5955.6  399.32  6269.1  398.98
#Mann= 3 ,-1 , 0
  2953.9     .05       0  4979.7     .03       0  4987.6     .05       0
Bank Sta=4979.7,4987.6
XS Rating Curve= 0 ,0
Exp/Cntr=0.3,0.1

Type RM Length L Ch R = 1 ,12867   ,43,43,43
BEGIN DESCRIPTION:
Mapping XS 57a6c0d1
END DESCRIPTION:
XS GIS Cut Line= 3
      2664376.54      6870310.19      2664324.46      6871824.99
      2664311.44      6872953.42
#Sta/Elev= 30
    3500  393.27  3650.9   391.5  3720.9  389.79  3921.1  388.21  3949.2  387.24
  3954.2  386.42  4061.1  388.09  4111.2  386.73  4271.3  384.72  4431.4  383.88
  4461.4  383.12  4591.5  382.97    4821  380.91  4998.4  378.43  5021.7   378.2
  5027.6   377.3  5028.8   376.8  5035.8   377.3  5041.7  379.21  5051.7   379.7
  5111.7  379.69  5156.4  380.56  5281.7  384.41  5291.7  383.96  5311.1   384.9
  5316.1  384.02  5661.7  389.33  5831.8  393.67  5951.8  395.61  6144.2  397.24
#Mann= 5 ,-1 , 0
    3500     .05       0  4998.4     .12       0  5027.6     .07       0
  5035.8     .12       0  5156.4     .05       0
Bank Sta=5027.6,5035.8
XS Rating Curve= 0 ,0
Exp/Cntr=0.3,0.1

Type RM Length L Ch R = 1 ,12824   ,1071,1071,1071
BEGIN DESCRIPTION:
Mapping XS d1401960
END DESCRIPTION:
XS GIS Cut Line= 3
      2664320.12      6870349.27      2664294.08      6871781.59
      2664268.03      6872914.44
#Sta/Elev= 30
  3570.1  394.05  3721.9  390.12  3861.9  389.33  3891.9  388.11  4111.9  386.24
  4291.9  386.09    4522   383.9  4619.4  382.07    4632  383.37    4702  382.73
    4742  383.86    4762  381.79    4852   381.8  4972.1   379.9  4992.1  378.66
  5004.9  379.12  5012.1  380.75  5021.7  380.32  5032.1  380.31    5048  377.55
  5049.2  377.05  5056.2  377.55  5112.1  381.49    5186  381.85  5292.1  385.25
  5532.2   389.2  5672.2  392.68  5852.3  393.46  5922.3  395.35  6135.8  396.55
#Mann= 5 ,-1 , 0
  3570.1     .05       0  5021.7     .12       0    5048     .03       0
  5056.2     .12       0    5186     .05       0
Bank Sta=5048,5056.2
XS Rating Curve= 0 ,0
Exp/Cntr=0.3,0.1

Type RM Length L Ch R = 1 ,11753   ,465,465,465
BEGIN DESCRIPTION:
Little Cottonwood Creek Trib 6 19.0
END DESCRIPTION:
XS GIS Cut Line= 3
      2663926.03      6870560.96        2663376.        6871361.
      2662896.75      6872566.56
#Sta/Elev= 30
  4028.7  390.87  4101.6  389.94  4122.8  387.66  4200.6  386.11  4209.4   384.5
  4272.3  382.23  4281.1   383.2  4388.7   380.4    4756  377.23  4947.6  378.36
  4977.2  378.26  4987.9  375.27  4989.1  374.77  4996.4  375.27  5002.3   375.5
    5009  377.94    5063  376.61    5161  377.52  5212.2  380.97  5421.9   383.8
  5548.4  388.55  5677.5  390.28  5686.4  391.68  5709.8  390.42    5824  391.57
    6108   389.8  6161.8  390.15  6194.1  393.13  6215.6  391.32  6296.9  393.51
#Mann= 5 ,-1 , 0
  4028.7     .05       0  4947.6     .12       0  4987.9     .07       0
  4996.4     .12       0  5212.2     .05       0
Bank Sta=4987.9,4996.4
XS Rating Curve= 0 ,0
Exp/Cntr=0.3,0.1

Type RM Length L Ch R = 1 ,11288   ,625,625,625
BEGIN DESCRIPTION:
Little Cottonwood Creek Trib 6 18.0
END DESCRIPTION:
XS GIS Cut Line= 3
      2663875.99      6870561.01        2662976.        6871161.
      2662226.02      6871810.98
#Sta/Elev= 30
  3921.8  391.32    4030  389.51  4058.5  386.76  4115.6  385.62  4138.1  383.32
  4174.2  382.04  4187.7  382.69  4304.9  380.82  4318.4  379.79  4686.5  377.09
  4809.7  378.22  4851.7  376.55  4919.4  376.59  4995.9  377.02  5003.5  375.73
  5006.2  373.32  5007.4  372.82    5015  373.32  5024.8  375.98    5043  377.14
  5109.3  376.76  5272.7  378.56  5336.3   378.3  5358.2  377.08  5464.6  377.52
  5606.1  380.38  5712.4  384.57  5790.3  385.81  5818.8  387.67  5995.9  391.16
#Mann= 5 ,-1 , 0
  3921.8     .05       0  4919.4     .12       0  5006.2     .07       0
    5015     .12       0    5043     .05       0
Bank Sta=5006.2,5015
XS Rating Curve= 0 ,0
Exp/Cntr=0.3,0.1

Type RM Length L Ch R = 1 ,10663   ,763,763,763
BEGIN DESCRIPTION:
Little Cottonwood Creek Trib 6 17.0
END DESCRIPTION:
XS GIS Cut Line= 3
      2663708.17      6870219.07      2662608.68      6870894.73
      2662026.01      6871460.99
#Sta/Elev= 30
  3709.5  389.27  3741.6  389.02  3784.2  390.35  3851.7  389.66  3946.4  390.18
  4004.4  388.83  4075.9  385.69  4141.7  384.55    4163  382.65  4215.1   382.3
  4300.3  379.69  4331.1  379.88  4352.4  378.56  4810.5  375.53  4932.7  375.73
  4984.4  374.74  4998.6   373.2  5008.9  370.65  5010.2  370.15    5018  370.65
  5027.6  374.17  5034.6  374.89  5282.2     379  5451.8  382.88  5480.1  385.34
    5558  385.63  5593.2  387.43  5642.9  387.54  5699.4  389.58  5812.5  391.86
#Mann= 3 ,-1 , 0
  3709.5     .05       0  5008.9     .04       0    5018     .05       0
Bank Sta=5008.9,5018
XS Rating Curve= 0 ,0
Exp/Cntr=0.3,0.1

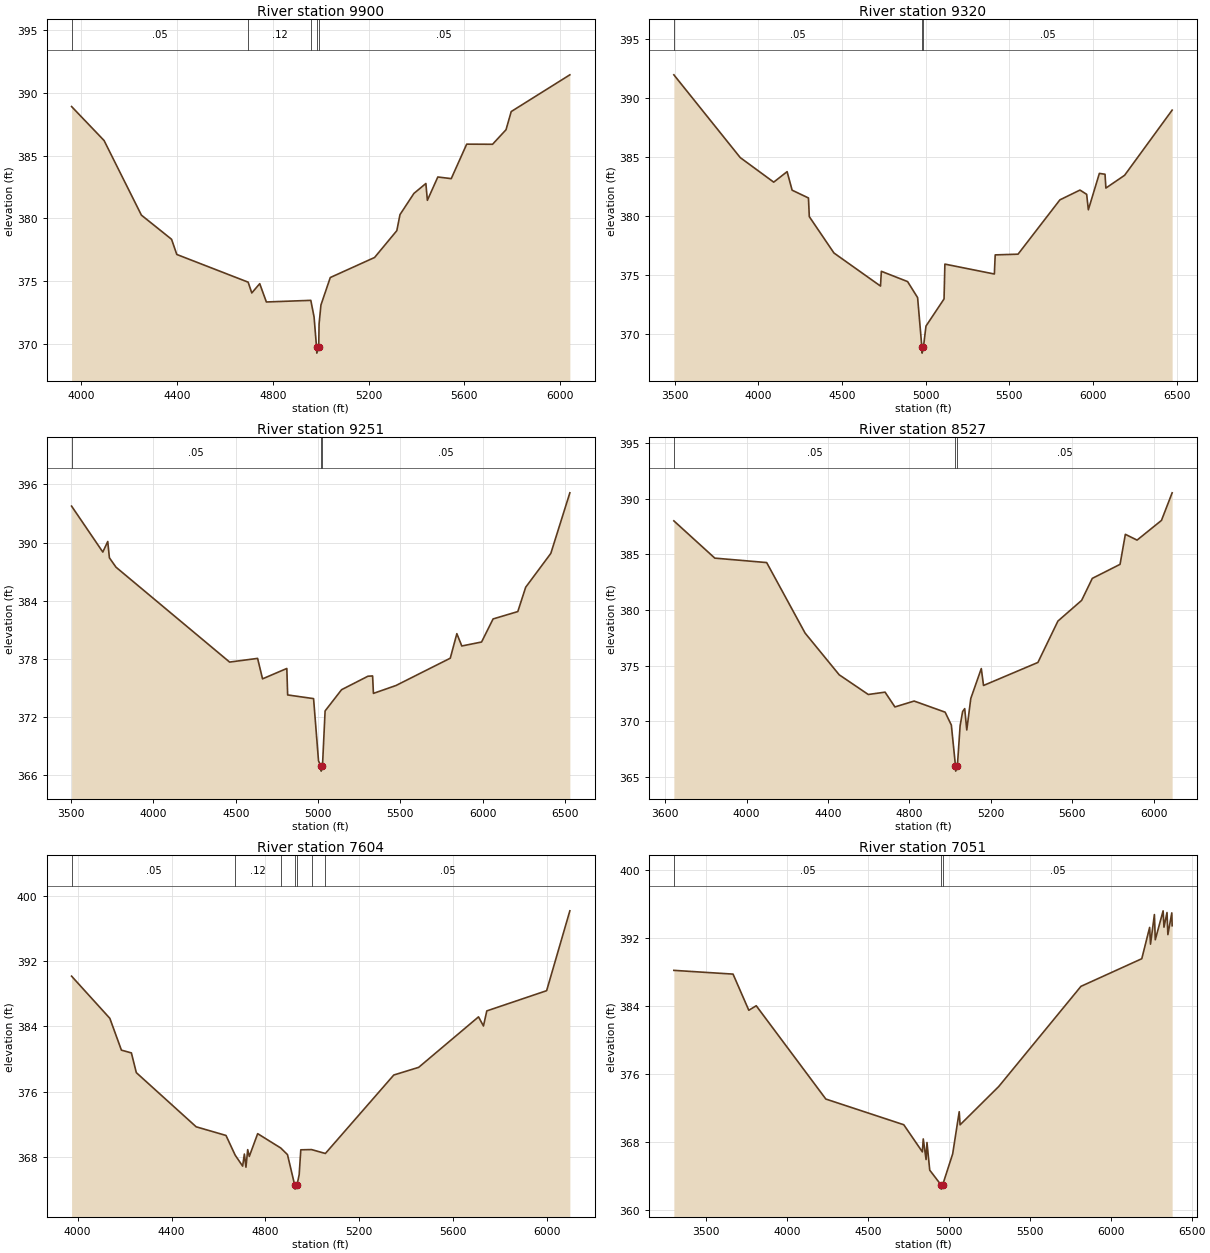
Type RM Length L Ch R = 1 ,9900    ,580,580,580
BEGIN DESCRIPTION:
Little Cottonwood Creek Trib 6 15.0
END DESCRIPTION:
XS GIS Cut Line= 3
      2663276.02      6870210.99        2662276.        6870511.
      2661451.17      6871139.25
#Sta/Elev= 30
  3959.8  388.91  4095.5   386.2  4251.3  380.25  4377.4  378.32  4399.2  377.11
  4697.2   374.9  4712.4  374.04  4745.5  374.78  4773.3  373.32  4958.9  373.45
  4972.5  372.13  4982.7  369.74    4984  369.24  4991.9  369.74  4993.4  371.57
  5001.2  373.08  5040.2  375.27  5225.2  376.87  5318.1  379.01  5331.3  380.29
  5389.5  381.98  5439.4  382.77  5445.7  381.43  5489.3  383.29  5545.4  383.16
  5609.9  385.91  5717.9   385.9  5774.1  387.06  5795.8  388.51  6040.7  391.44
#Mann= 5 ,-1 , 0
  3959.8     .05       0  4697.2     .12       0  4958.9     .05       0
  4982.7     .03       0  4991.9     .05       0
Bank Sta=4982.7,4991.9
XS Rating Curve= 0 ,0
Exp/Cntr=0.3,0.1

Type RM Length L Ch R = 1 ,9320    ,69,69,69
BEGIN DESCRIPTION:
Mapping XS 8f92448b
END DESCRIPTION:
XS GIS Cut Line= 5
      2663842.73      6869984.71      2662345.29      6869949.99
      2661299.29      6869915.27      2661116.99      6869971.69
      2660891.35      6870062.82
#Sta/Elev= 30
  3495.3  391.95  3892.1  384.94  4092.2  382.86  4172.2  383.75  4202.2  382.18
  4299.9  381.52  4304.9  379.94  4452.3  376.86  4730.6  374.06  4735.6  375.31
  4892.4  374.44  4952.4  373.08  4977.8  368.88  4979.1  368.38  4987.1  368.88
  5002.4  370.67  5110.4  372.97  5115.4  375.92  5411.2  375.08  5416.2   376.7
  5552.7  376.76  5802.9  381.36  5922.9  382.19    5963  381.83    5973  380.52
  6038.9   383.6  6072.7  383.53  6077.9  382.36  6189.7  383.44  6473.9  388.96
#Mann= 3 ,-1 , 0
  3495.3     .05       0  4977.8     .03       0  4987.1     .05       0
Bank Sta=4977.8,4987.1
XS Rating Curve= 0 ,0
Exp/Cntr=0.3,0.1

Type RM Length L Ch R = 1 ,9251    ,724,724,724
BEGIN DESCRIPTION:
Mapping XS afcd57f7
END DESCRIPTION:
XS GIS Cut Line= 4
       2663855.7      6869910.93      2662332.27      6869893.56
      2661095.29      6869863.18      2660830.75      6869884.87
#Sta/Elev= 30
  3502.9  393.76  3692.6  389.02  3722.6  390.11  3732.6  388.43  3772.6  387.46
  4462.7  377.67  4632.7  378.05  4662.7  375.94  4810.2  377.01  4815.2  374.28
  4972.7   373.9  5002.7  367.48  5017.4  366.92  5018.7  366.42  5026.7  366.92
  5042.7  372.63  5142.7  374.82  5302.8  376.21  5331.2  376.24  5336.2  374.44
  5472.8  375.25  5802.9  378.07  5842.9   380.6  5872.9  379.33    5993  379.74
    6063  382.12  6213.1  382.88  6260.9  385.39  6413.6  388.88  6529.2  395.13
#Mann= 3 ,-1 , 0
  3502.9     .05       0  5017.4     .05       0  5026.7     .05       0
Bank Sta=5017.4,5026.7
XS Rating Curve= 0 ,0
Exp/Cntr=0.3,0.1

Type RM Length L Ch R = 1 ,8527    ,923,923,923
BEGIN DESCRIPTION:
Mapping XS 9a82d011
END DESCRIPTION:
XS GIS Cut Line= 3
      2663026.69        6868904.      2661863.52      6869628.81
      2660804.49      6869828.46
#Sta/Elev= 30
    3643  388.02  3844.1  384.67    4099  384.27  4287.8  377.93  4455.4  374.18
  4598.2  372.41  4680.7  372.62  4729.1  371.29  4823.5  371.82  4975.8  370.82
  5006.4  369.66  5026.5  366.02  5027.9  365.52  5036.1  366.02  5049.5  369.61
  5061.9  370.88    5072  371.14  5082.2  369.22  5101.9  372.05  5153.5  374.74
  5164.5  373.22  5431.7  375.29    5530  379.01  5646.5  380.87    5699  382.85
  5835.3  384.11  5861.3  386.81  5918.9  386.29  6038.8  388.06  6091.2  390.54
#Mann= 3 ,-1 , 0
    3643     .05       0  5026.5     .05       0  5036.1     .05       0
Bank Sta=5026.5,5036.1
XS Rating Curve= 0 ,0
Exp/Cntr=0.3,0.1

Type RM Length L Ch R = 1 ,7604    ,553,553,553
BEGIN DESCRIPTION:
Little Cottonwood Creek Trib 6 10.0
END DESCRIPTION:
XS GIS Cut Line= 3
      2662176.02      6868310.98        2661476.        6869061.
      2660726.02      6869860.98
#Sta/Elev= 30
  3974.3  390.17  4137.3     385  4186.6   381.1  4229.1  380.76  4250.1  378.34
  4505.1   371.7  4632.1  370.64  4671.3  368.22    4703  366.88  4710.3  368.36
  4717.1  366.75  4724.5   368.9  4731.3  368.07    4767  370.86  4865.4   369.1
    4894  368.29  4924.7  364.56  4926.1  364.06  4934.6  364.56  4943.8  365.84
  4950.7  368.88  4996.4  368.91  5055.4  368.43  5346.8  378.05  5452.8  378.99
  5707.8  385.18  5728.8  384.06    5743  385.91  5997.9  388.39  6096.8  398.18
#Mann= 7 ,-1 , 0
  3974.3     .05       0  4671.3     .12       0  4865.4     .05       0
  4924.7     .07       0  4934.6     .05       0  4996.4     .12       0
  5055.4     .05       0
Bank Sta=4924.7,4934.6
XS Rating Curve= 0 ,0
Exp/Cntr=0.3,0.1

Type RM Length L Ch R = 1 ,7051    ,296,296,296
BEGIN DESCRIPTION:
Mapping XS 3ac3f255
END DESCRIPTION:
XS GIS Cut Line= 3
      2661794.08      6867124.47      2661099.63      6868634.88
      2660570.57      6869948.86
#Sta/Elev= 30
  3300.5  388.15  3666.2  387.71  3763.6  383.46  3809.5  383.99  4239.6  373.02
  4721.1     370    4836  366.81  4841.5  368.33    4859  365.91  4864.5  367.91
  4881.6  364.66  4951.3  362.93  4952.7  362.43  4961.4  362.93  5023.4  366.58
  5063.7  371.53  5069.1  369.99  5308.2   374.5  5815.9  386.27  6191.9  389.52
  6240.3   393.2  6245.7  391.23  6269.8  394.71  6275.2  391.75  6323.6  395.15
  6328.9  393.23  6347.7  394.95  6353.1  392.35  6377.3  394.91  6379.4   393.4
#Mann= 3 ,-1 , 0
  3300.5     .05       0  4951.3     .04       0  4961.4     .05       0
Bank Sta=4951.3,4961.4
XS Rating Curve= 0 ,0
Exp/Cntr=0.3,0.1