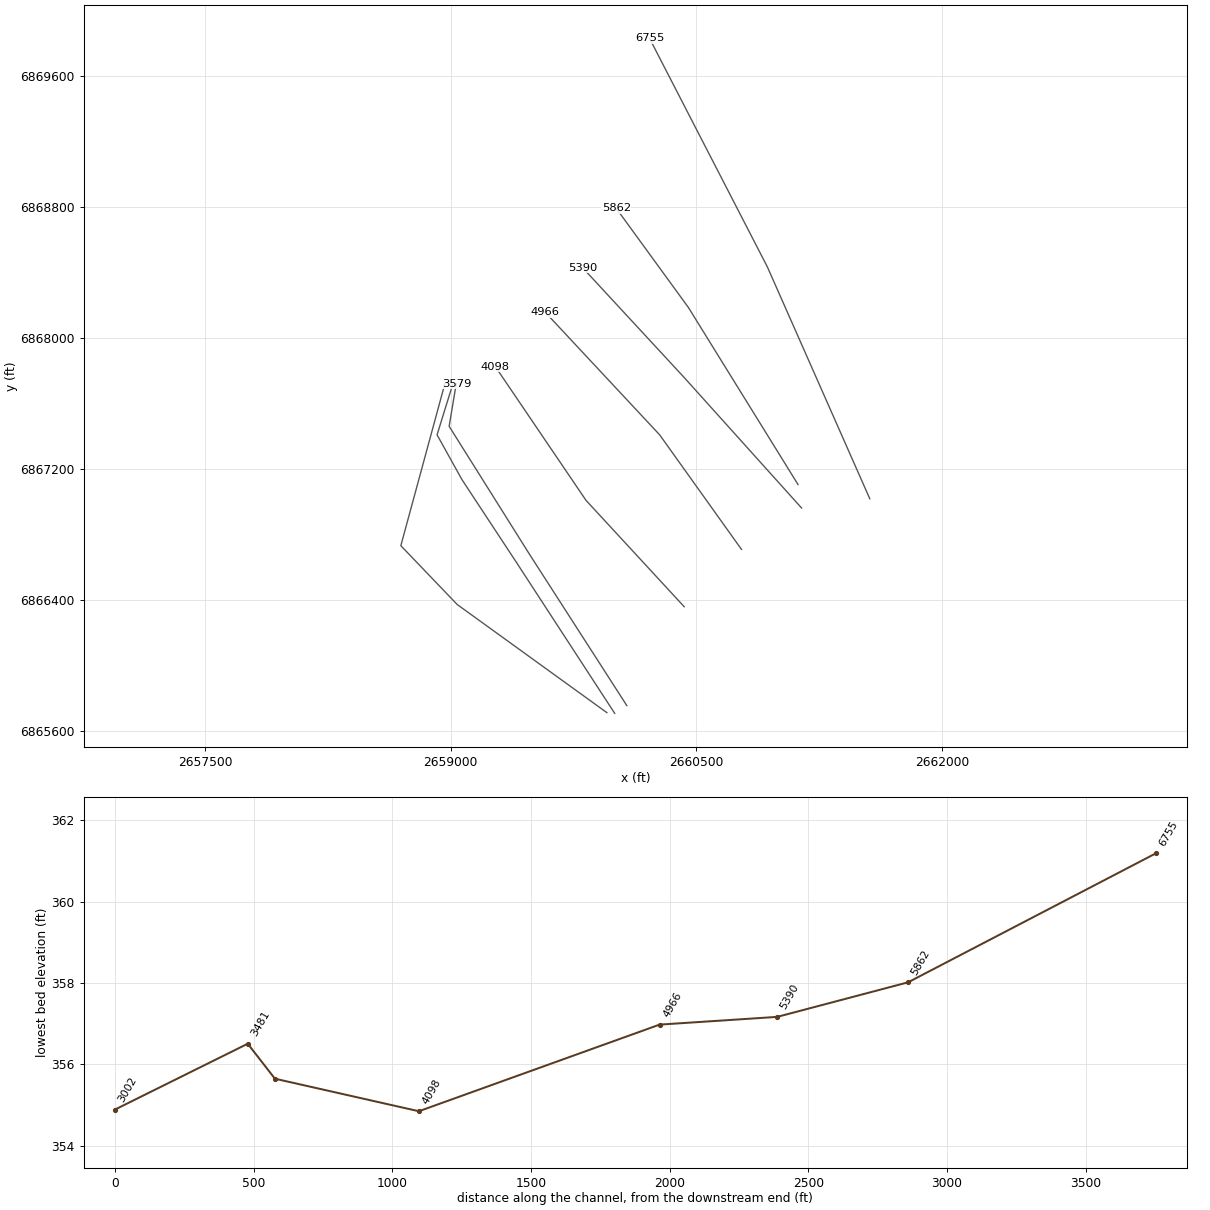
HEC-RAS study Little Cottonwood Creek Trib 6.prj: Little Cottonwood Creek Trib 6 Base Level Engineering

--- Little Cottonwood Creek Trib 6.g01 (geometry) --- (continued)

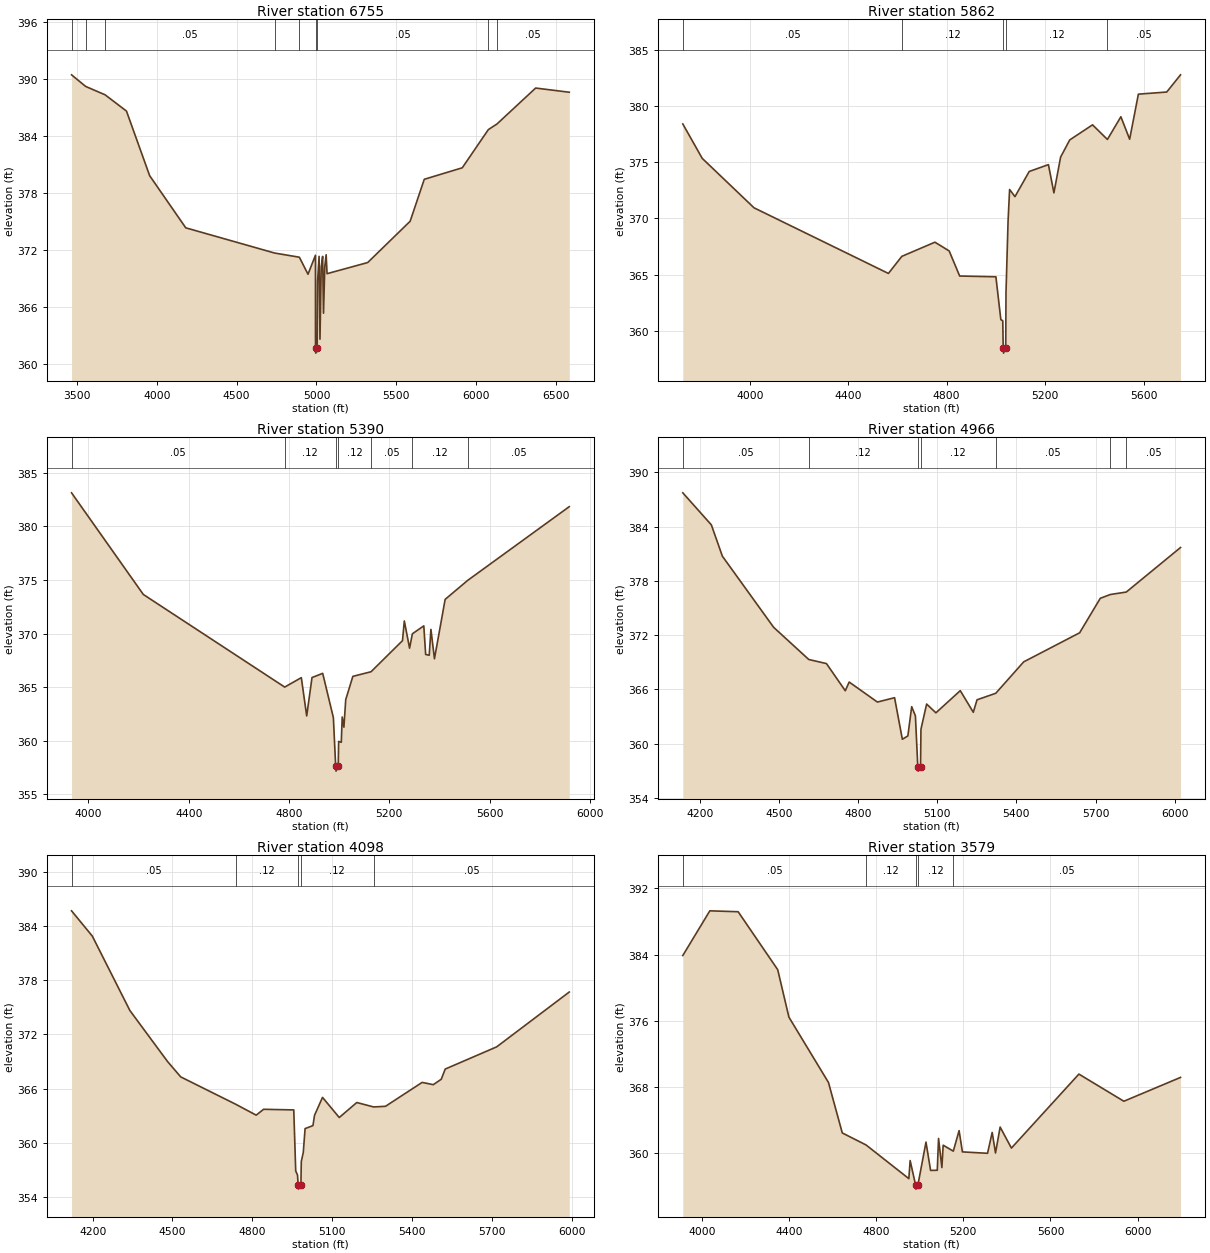
Type RM Length L Ch R = 1 ,6755    ,893,893,893
BEGIN DESCRIPTION:
Mapping XS ca576fd6
END DESCRIPTION:
XS GIS Cut Line= 3
       2661559.7       6867020.3       2660934.7      6868435.23
       2660214.2      6869832.82
#Sta/Elev= 30
  3465.2  390.44  3553.7  389.22  3675.4  388.34  3809.4  386.63  3954.7  379.84
  4180.9  374.36  4737.7  371.71    4893  371.27  4947.1  369.48  4993.7  371.48
  4994.1  361.69  4995.5  361.19  5004.3  361.69    5007  368.71  5016.5  371.36
  5022.1  362.66  5029.8  370.26  5038.7  371.36  5044.3  365.39  5052.3  370.32
  5060.8  371.53  5066.4  369.54  5321.1  370.71  5587.1  375.05  5675.7  379.46
  5913.9  380.67  6077.1  384.68  6131.1  385.27  6373.7  389.05  6584.4  388.61
#Mann= 9 ,-1 , 0
  3465.2     .05       0  3553.7    .075       0  3675.4     .05       0
  4737.7    .075       0    4893     .05       0  4994.1     .03       0
  5004.3     .05       0  6077.1    .075       0  6131.1     .05       0
Bank Sta=4994.1,5004.3
XS Rating Curve= 0 ,0
Exp/Cntr=0.3,0.1

Type RM Length L Ch R = 1 ,5862    ,472,472,472
BEGIN DESCRIPTION:
Little Cottonwood Creek Trib 6 6.0
END DESCRIPTION:
XS GIS Cut Line= 3
      2661121.34      6867107.09      2660451.91      6868188.45
      2660010.64       6868794.9
#Sta/Elev= 30
  3728.2  378.41    3807  375.35  4017.4  370.95  4563.4  365.11  4617.9  366.63
  4752.4  367.89  4810.3  367.11  4852.9  364.88    5000  364.81  5020.1     361
  5027.9   360.9  5029.7  358.52  5031.1  358.02    5040  358.52    5041  363.38
  5049.5   369.8  5055.7  372.58  5077.4  371.94  5135.3  374.18  5213.4  374.79
  5235.7  372.28  5262.9  375.46    5300  376.99  5392.6  378.33    5453  377.03
  5507.7  379.05  5543.3  377.05  5578.8  381.06    5694  381.25    5750  382.78
#Mann= 5 ,-1 , 0
  3728.2     .05       0  4617.9     .12       0  5029.7     .09       0
    5040     .12       0    5453     .05       0
Bank Sta=5029.7,5040
XS Rating Curve= 0 ,0
Exp/Cntr=0.3,0.1

Type RM Length L Ch R = 1 ,5390    ,424,424,424
BEGIN DESCRIPTION:
Little Cottonwood Creek Trib 6 5.0
END DESCRIPTION:
XS GIS Cut Line= 3
      2661143.04      6866963.87        2660426.        6867761.
      2659806.22       6868430.9
#Sta/Elev= 30
  3932.6  383.13  4218.8  373.65  4782.6  365.01  4848.9  365.89  4870.3  362.32
  4891.5   365.9  4934.1  366.29  4976.7  362.16  4985.8  357.67  4987.2  357.17
  4996.1  357.67  4997.7  359.94  5008.2  359.86  5011.9  362.22  5018.7  361.27
    5026  363.84  5054.4  366.01  5126.9  366.44  5252.3  369.34  5259.6  371.18
  5280.6  368.64  5291.7  369.98  5337.3  370.72  5344.7  368.05  5358.9  367.98
  5365.7  370.39  5379.8  367.65  5422.4  373.19  5511.6  374.95  5917.4  381.84
#Mann= 7 ,-1 , 0
  3932.6     .05       0  4782.6     .12       0  4985.8     .09       0
  4996.1     .12       0  5126.9     .05       0  5291.7     .12       0
  5511.6     .05       0
Bank Sta=4985.8,4996.1
XS Rating Curve= 0 ,0
Exp/Cntr=0.3,0.1

Type RM Length L Ch R = 1 ,4966    ,868,868,868
BEGIN DESCRIPTION:
Little Cottonwood Creek Trib 6 4.0
END DESCRIPTION:
XS GIS Cut Line= 3
      2660776.02      6866710.97        2660276.        6867411.
      2659575.99      6868161.01
#Sta/Elev= 30
  4135.8  387.72    4244  384.18  4285.8  380.72  4479.9  372.87  4613.2  369.31
  4680.2  368.86  4751.5  365.86  4766.3  366.82  4873.2  364.61  4938.3  365.09
  4967.8   360.5  4988.7  360.87  5003.2   364.1  5017.3  363.08  5026.3  357.48
  5027.7  356.98  5036.7  357.48  5038.3  361.61  5059.8  364.39    5095  363.42
  5187.3  365.87  5236.7  363.48  5250.8  364.86  5321.9  365.58  5427.7  369.05
  5639.7  372.26  5717.9  376.07  5756.2  376.49  5816.4  376.76    6022  381.68
#Mann= 7 ,-1 , 0
  4135.8     .05       0  4613.2     .12       0  5026.3     .09       0
  5036.7     .12       0  5321.9     .05       0  5756.2     .12       0
  5816.4     .05       0
Bank Sta=5026.3,5036.7
XS Rating Curve= 0 ,0
Exp/Cntr=0.3,0.1

Type RM Length L Ch R = 1 ,4098    ,519,519,519
BEGIN DESCRIPTION:
Little Cottonwood Creek Trib 6 2.0
END DESCRIPTION:
XS GIS Cut Line= 3
        2660426.        6866361.        2659826.        6867011.
      2659272.91       6867826.8
#Sta/Elev= 30
  4120.7   385.7  4198.7   382.9  4339.9  374.65  4481.6  368.99    4531  367.29
  4737.5  364.26  4814.5  363.05  4842.3   363.7  4955.7  363.63    4963  356.87
  4969.8  356.41    4972  355.35  4973.4  354.85  4982.5  355.35    4984  357.92
  4991.4  358.91  4998.2  361.56  5027.7  361.89  5033.8  363.04  5063.7  365.02
  5126.6  362.79  5192.5  364.45  5255.7  363.96  5300.3  364.03    5438  366.68
    5480  366.43  5509.9  367.03  5524.8  368.16  5718.1  370.62  5990.9   376.7
#Mann= 5 ,-1 , 0
  4120.7     .05       0  4737.5     .12       0    4972      .1       0
  4982.5     .12       0  5255.7     .05       0
Bank Sta=4972,4982.5
XS Rating Curve= 0 ,0
Exp/Cntr=0.3,0.1

Type RM Length L Ch R = 1 ,3579    ,98,98,98
BEGIN DESCRIPTION:
Mapping XS 86778db7
END DESCRIPTION:
XS GIS Cut Line= 4
      2660075.31      6865757.31      2659480.71      6866681.76
      2658990.26      6867463.01      2659033.66      6867723.41
#Sta/Elev= 30
  3911.8  383.88  4035.9  389.28    4166  389.17  4347.6  382.17  4399.1  376.43
  4580.7  368.54  4644.1  362.44  4753.1  360.99  4949.8  356.92  4955.8   359.1
  4980.8  356.15  4982.3  355.65  4991.4  356.15  5028.5  361.33  5049.7  357.91
  5080.3  357.93  5086.2  361.77  5101.5  358.26  5107.4  360.96    5154  360.24
  5180.5  362.72  5195.8  360.15  5311.2  359.98  5332.5   362.5  5347.8  360.02
    5369  363.15  5420.8  360.61  5730.7  369.55  5937.2  366.27  6197.4  369.15
#Mann= 5 ,-1 , 0
  3911.8     .05       0  4753.1     .12       0  4980.8      .1       0
  4991.4     .12       0    5154     .05       0
Bank Sta=4980.8,4991.4
XS Rating Curve= 0 ,0
Exp/Cntr=0.3,0.1

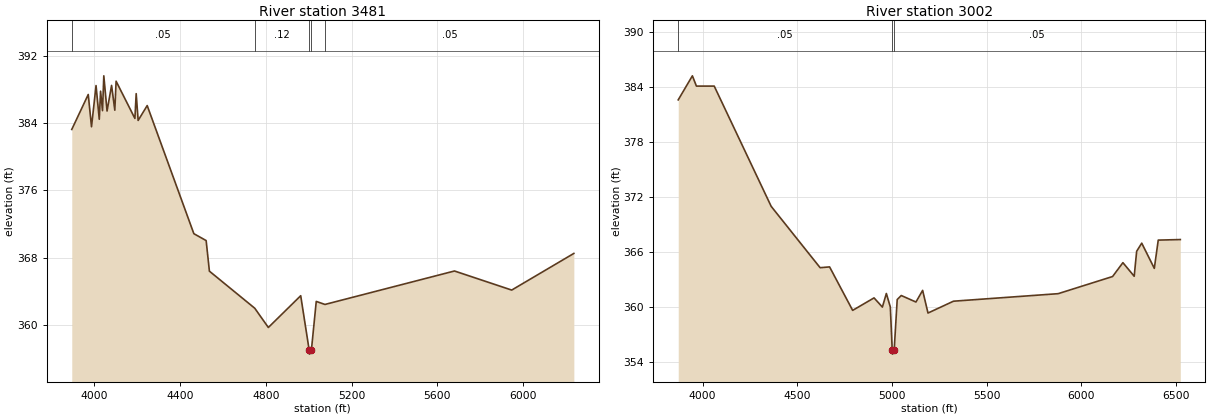
Type RM Length L Ch R = 1 ,3481    ,479,479,479
BEGIN DESCRIPTION:
Mapping XS 842f2fe6
END DESCRIPTION:
XS GIS Cut Line= 5
      2660001.56      6865709.52      2659402.58      6866629.68
      2659068.38      6867137.49      2658916.47      6867410.93
      2659011.49      6867717.59
#Sta/Elev= 30
  3896.3  383.24  3973.1   387.4  3988.3  383.56  4009.4  388.46  4024.5  384.45
  4030.5  387.79  4039.6  385.48  4045.6  389.62  4060.7  385.43  4081.8  388.48
  4096.9  385.53  4102.9  388.98  4190.5  384.55  4196.5   387.5  4205.6  384.31
  4247.8  386.08  4465.2  370.84  4522.5  370.02  4537.7  366.38    4749  361.97
  4812.4  359.68  4963.2  363.46  5002.5  357.01  5003.9  356.51  5013.1  357.01
  5035.6  362.78  5076.2  362.42  5679.8   366.4  5946.4  364.13    6236  368.49
#Mann= 5 ,-1 , 0
  3896.3     .05       0    4749     .12       0  5002.5     .07       0
  5013.1     .12       0  5076.2     .05       0
Bank Sta=5002.5,5013.1
XS Rating Curve= 0 ,0
Exp/Cntr=0.3,0.1

Type RM Length L Ch R = 1 ,3002    ,0,0,0
BEGIN DESCRIPTION:
Little Cottonwood Creek Trib 6 1.0
END DESCRIPTION:
XS GIS Cut Line= 4
      2659953.83      6865713.86       2659039.2      6866374.73
      2658695.12      6866733.84      2658964.22      6867723.46
#Sta/Elev= 30
  3871.6  382.61  3946.3  385.23  3967.6  384.11  4061.6  384.11  4362.4     371
  4620.9  364.31  4670.8   364.4  4792.7  359.66  4905.6  361.02  4949.7  360.02
  4970.6   361.5  4991.6  360.03  5001.5  355.39    5003  354.89  5012.1  355.39
  5027.9  360.84  5049.3  361.28  5126.9  360.57  5162.2  361.84  5190.5  359.37
  5325.1  360.66  5877.8  361.48  6165.2  363.35  6219.8  364.86  6279.4  363.38
  6292.4   366.1  6319.2  366.99  6385.6  364.24  6406.4  367.32  6522.9  367.38
#Mann= 3 ,-1 , 0
  3871.6     .05       0  5001.5     .05       0  5012.1     .05       0
Bank Sta=5001.5,5012.1
XS Rating Curve= 0 ,0
Exp/Cntr=0.3,0.1

Chan Stop Cuts=-1
Use User Specified Reach Order=0
Composite Channel Slope=5