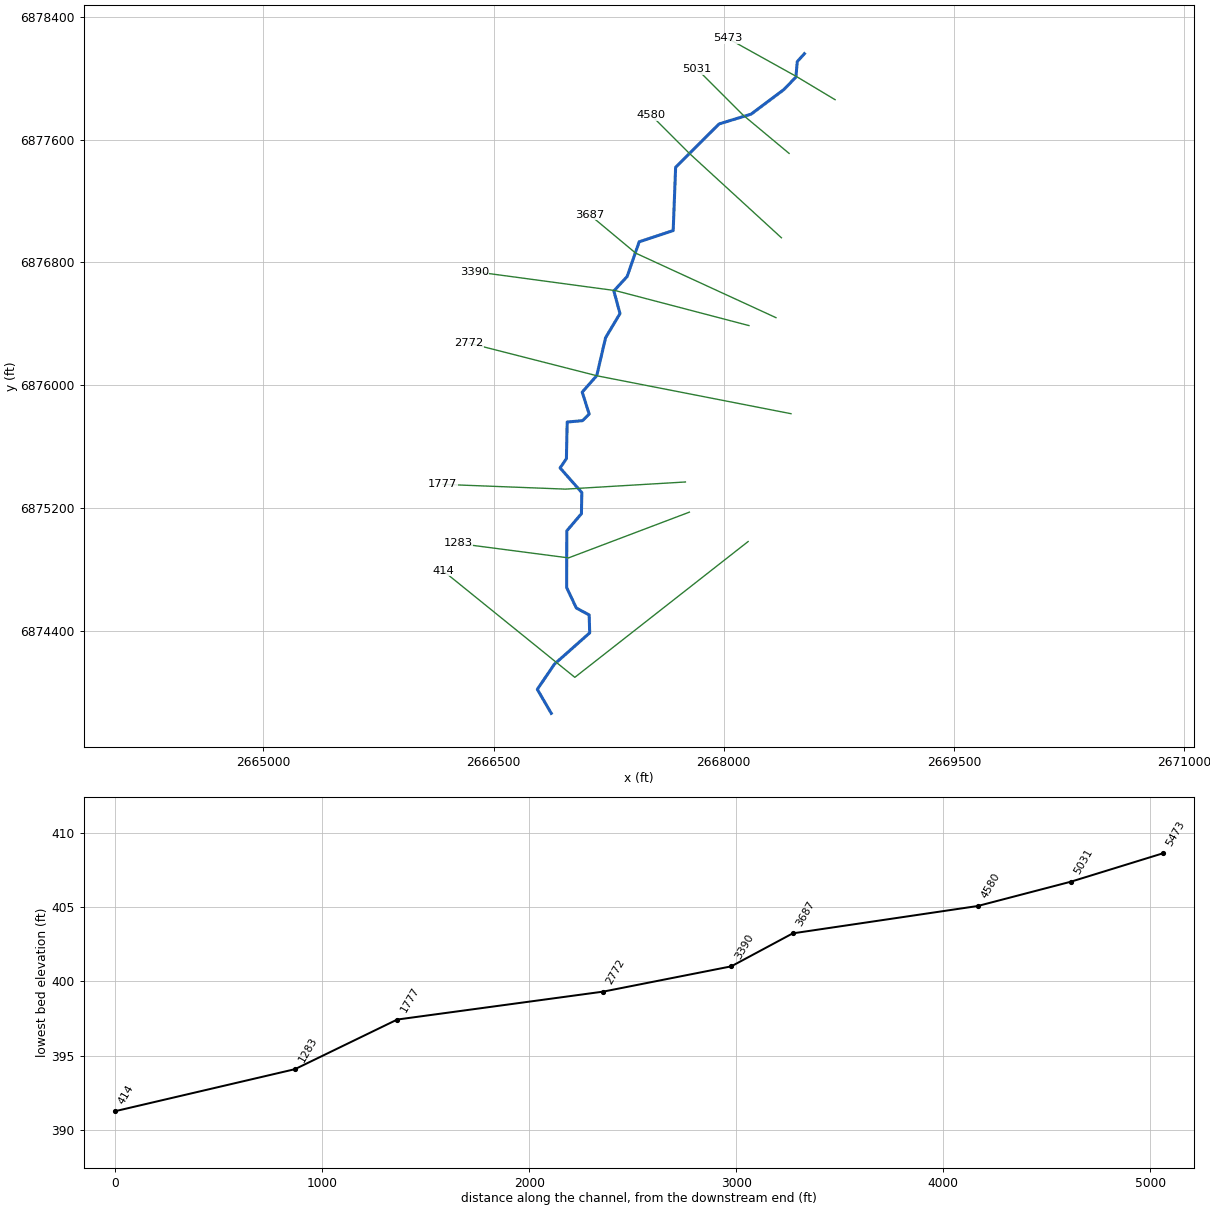
--- Little Cottonwood Creek Trib 6_1.prj (project) ---

Proj Title=Little Cottonwood Creek Trib 6_1 Base Level Engineering
Current Plan=p01
Default Exp/Contr=0.3,0.1
English Units
Geom File=g01
Flow File=f01
Plan File=p01
BEGIN DESCRIPTION:
Little Cottonwood Creek Trib 6_1
END DESCRIPTION:

--- Little Cottonwood Creek Trib 6_1.p01 (plan) ---

Plan Title=Multiple Run
Short Identifier=Multiple
Geom File=g01
Flow File=f01
Subcritical Flow
K Sum by GR= 0
Std Step Tol= 0.01
Critical Tol= 0.01
Num of Std Step Trials= 20
Max Error Tol= 0.3
Flow Tol Ratio= 0.001
Split Flow NTrial= 30
Split Flow Tol= 0.02
Split Flow Ratio= 0.02
Log Output Level= 0
Friction Slope Method= 1
Unsteady Friction Slope Method= 2
Unsteady Bridges Friction Slope Method= 1
Parabolic Critical Depth
Global Vel Dist=  1 , 1 , 1
Global Log Level= 0
CheckData=True
Encroach Param= -1, 0, 0, 0
BEGIN DESCRIPTION:
Multiple Run
END DESCRIPTION:

--- Little Cottonwood Creek Trib 6_1.f01 (steady flow) ---

Flow Title=Multiple
Number of Profiles=7
Profile Names=10-year,25-year,50-year,1pct_min,100-year,1pct_plu,500-year
River Rch & RM= Little Cottonwoo,Reach-1,5473
     501     663     792     469     936    1867    1305
Boundary for River Rch & Prof#=Little Cottonwoo,Reach-1,1
Up Type=0
Dn Type=3
Dn Slope=0.005
Boundary for River Rch & Prof#=Little Cottonwoo,Reach-1,2
Up Type=0
Dn Type=3
Dn Slope=0.005
Boundary for River Rch & Prof#=Little Cottonwoo,Reach-1,3
Up Type=0
Dn Type=3
Dn Slope=0.005
Boundary for River Rch & Prof#=Little Cottonwoo,Reach-1,4
Up Type=0
Dn Type=3
Dn Slope=0.005
Boundary for River Rch & Prof#=Little Cottonwoo,Reach-1,5
Up Type=0
Dn Type=3
Dn Slope=0.005
Boundary for River Rch & Prof#=Little Cottonwoo,Reach-1,6
Up Type=0
Dn Type=3
Dn Slope=0.005
Boundary for River Rch & Prof#=Little Cottonwoo,Reach-1,7
Up Type=0
Dn Type=3
Dn Slope=0.005

--- Little Cottonwood Creek Trib 6_1.g01 (geometry) ---

Geom Title=Existing Conditions

River Reach=Little Cottonwoo,Reach-1
Reach XY= 30
      2668526.00      6878161.00      2668479.39      6878109.59
      2668470.51      6878008.55      2668392.71      6877927.64
      2668178.30      6877766.83      2667969.83      6877703.14
      2667686.48      6877420.80      2667670.54      6877008.00
      2667448.85      6876934.85      2667370.45      6876708.57
      2667283.81      6876614.41      2667323.85      6876466.97
      2667229.83      6876309.42      2667172.38      6876062.50
      2667077.63      6875954.96      2667122.87      6875812.17
      2667079.65      6875768.90      2666979.54      6875760.00
      2666974.61      6875521.43      2666933.32      6875460.90
      2667074.96      6875300.56      2667072.46      6875162.47
      2666977.06      6875050.56      2666976.06      6874681.02
      2667039.55      6874547.46      2667122.92      6874502.69
      2667126.37      6874385.83      2666895.79      6874181.09
      2666784.97      6874017.66      2666876.00      6873861.00

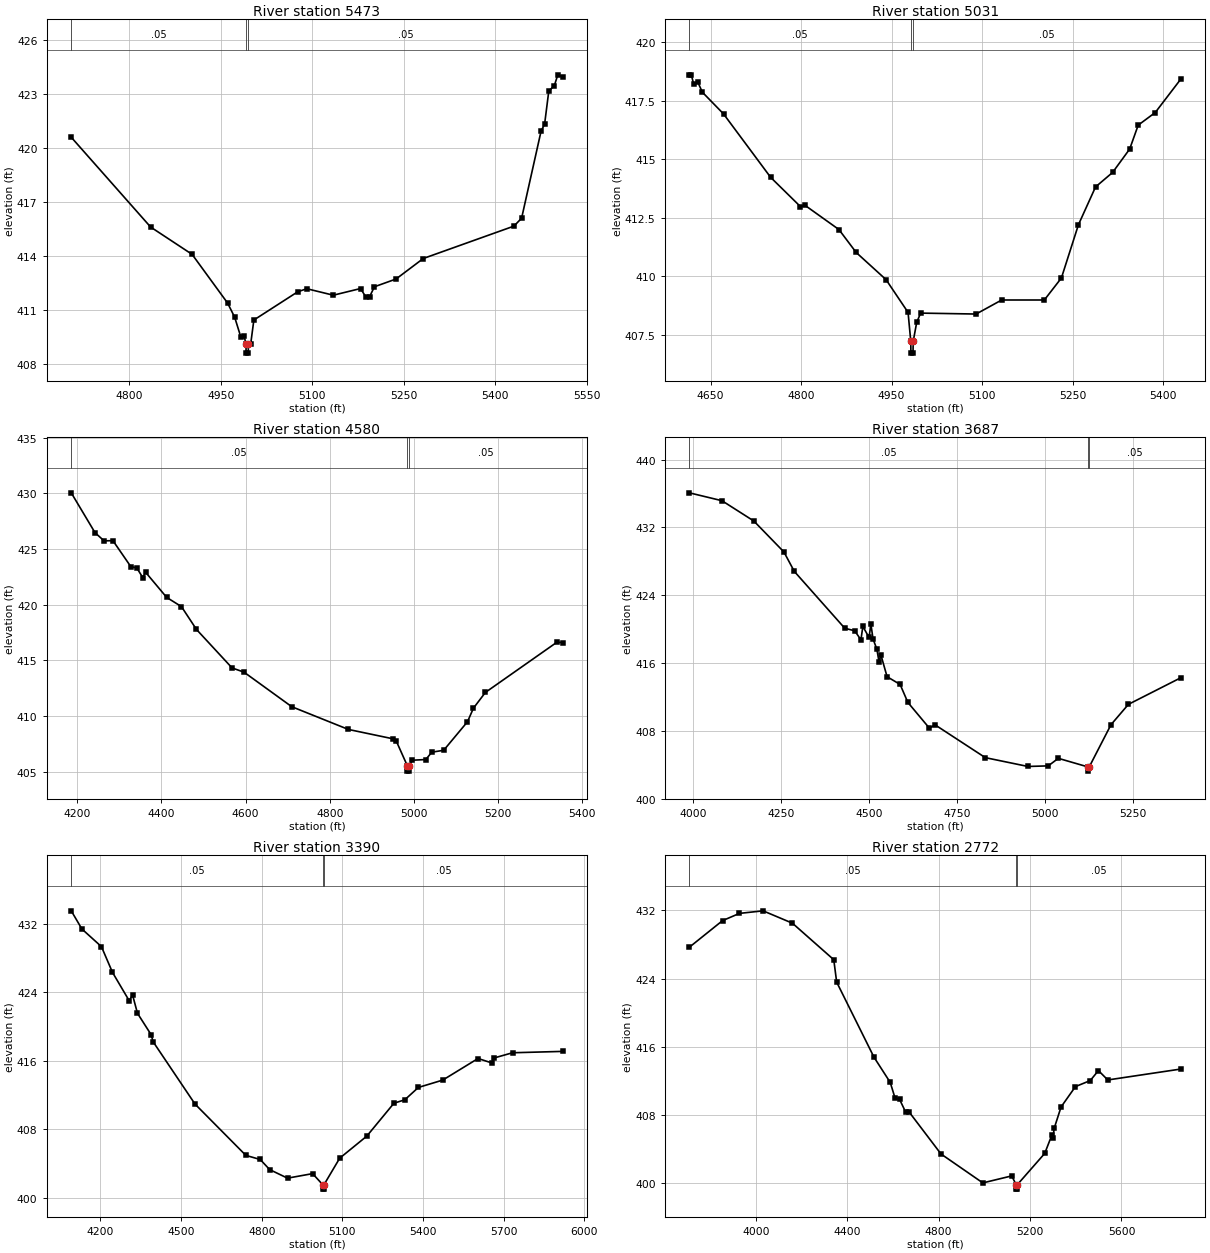
Type RM Length L Ch R = 1,5473,442,442,442
BEGIN DESCRIPTION:
Little Cottonwood Creek Trib 6_1 10.0
END DESCRIPTION:
XS GIS Cut Line= 3
      2668726.02      6877860.99      2668476.00      6878011.00
      2668025.96      6878261.02
#Sta/Elev= 30
  4704.5  420.61  4834.7  415.62  4902.8  414.10  4961.1  411.39  4972.7  410.60
  4982.5  409.53  4988.3  409.54  4991.2  409.11  4991.4  408.61  4994.9  408.61
  4995.2  409.11  4998.9  409.11  5004.1  410.45  5076.1  412.02  5091.0  412.19
  5134.5  411.83  5179.1  412.20  5188.3  411.71  5194.0  411.75  5202.0  412.30
  5237.4  412.73  5282.1  413.87  5430.8  415.67  5443.4  416.11  5475.4  420.96
  5481.1  421.33  5488.0  423.18  5497.1  423.48  5502.8  424.08  5510.9  423.97
#Mann=3,-1,0
  4704.5    0.05       0  4991.2    0.04       0  4995.2    0.05       0
Bank Sta=4991.2,4995.2
Exp/Cntr=0.3,0.1

Type RM Length L Ch R = 1,5031,451,451,451
BEGIN DESCRIPTION:
Little Cottonwood Creek Trib 6_1 9.0
END DESCRIPTION:
XS GIS Cut Line= 3
      2668426.03      6877510.98      2668126.00      6877761.00
      2667826.01      6878060.99
#Sta/Elev= 30
  4614.8  418.60  4618.1  418.60  4622.0  418.20  4628.5  418.31  4636.3  417.86
  4671.5  416.93  4749.6  414.22  4799.0  412.97  4806.8  413.02  4862.8  411.99
  4891.4  411.01  4940.9  409.85  4977.4  408.45  4981.9  407.21  4982.1  406.71
  4985.6  406.71  4985.9  407.21  4991.7  408.02  4998.2  408.42  5090.2  408.38
  5132.6  408.98  5203.3  408.98  5231.6  409.92  5259.9  412.20  5288.2  413.81
  5316.5  414.43  5344.8  415.43  5358.9  416.45  5387.2  416.99  5429.6  418.42
#Mann=3,-1,0
  4614.8    0.05       0  4981.9    0.04       0  4985.9    0.05       0
Bank Sta=4981.9,4985.9
Exp/Cntr=0.3,0.1

Type RM Length L Ch R = 1,4580,893,893,893
BEGIN DESCRIPTION:
Little Cottonwood Creek Trib 6_1 8.0
END DESCRIPTION:
XS GIS Cut Line= 3
      2668376.01      6876960.99      2667776.00      6877511.00
      2667526.01      6877760.99
#Sta/Elev= 30
  4186.0  430.04  4242.4  426.47  4264.0  425.73  4285.0  425.75  4327.5  423.42
  4341.7  423.30  4355.9  422.44  4362.7  422.91  4412.6  420.66  4447.8  419.83
  4483.5  417.78  4568.0  414.33  4596.4  413.95  4709.8  410.85  4844.3  408.81
  4950.3  407.97  4957.7  407.80  4984.1  405.57  4984.3  405.07  4987.8  405.07
  4988.1  405.57  4996.6  406.05  5028.2  406.11  5042.4  406.77  5070.7  406.94
  5127.2  409.50  5141.4  410.72  5169.7  412.13  5339.4  416.63  5353.5  416.61
#Mann=3,-1,0
  4186.0    0.05       0  4984.1    0.04       0  4988.1    0.05       0
Bank Sta=4984.1,4988.1
Exp/Cntr=0.3,0.1

Type RM Length L Ch R = 1,3687,297,297,297
BEGIN DESCRIPTION:
Little Cottonwood Creek Trib 6_1 6.0
END DESCRIPTION:
XS GIS Cut Line= 3
      2668340.24      6876440.53      2667426.00      6876861.00
      2667126.00      6877111.00
#Sta/Elev= 30
  3988.8  436.07  4081.5  435.14  4172.2  432.74  4257.6  429.09  4287.1  426.80
  4430.5  420.09  4458.9  419.79  4476.4  418.72  4481.9  420.30  4499.4  419.01
  4504.9  420.55  4510.8  418.83  4521.8  417.61  4527.9  416.11  4533.4  416.91
  4550.8  414.37  4587.8  413.46  4609.8  411.34  4671.2  408.29  4686.9  408.70
  4830.0  404.82  4951.1  403.78  5008.8  403.85  5037.4  404.74  5121.3  403.73
  5121.6  403.23  5125.3  403.73  5187.1  408.71  5236.6  411.11  5385.6  414.25
#Mann=3,-1,0
  3988.8    0.05       0  5121.3    0.03       0  5125.3    0.05       0
Bank Sta=5121.3,5125.3
Exp/Cntr=0.3,0.1

Type RM Length L Ch R = 1,3390,618,618,618
BEGIN DESCRIPTION:
Mapping XS 8a5fac6e
END DESCRIPTION:
XS GIS Cut Line= 3
      2668164.27      6876388.78      2667294.87      6876616.48
      2666373.73      6876740.68
#Sta/Elev= 30
  4091.5  433.50  4131.1  431.38  4203.8  429.32  4244.8  426.32  4306.8  423.02
  4319.8  423.66  4337.8  421.54  4389.5  419.00  4395.5  418.24  4551.9  410.94
  4741.0  404.95  4794.4  404.47  4829.6  403.29  4896.0  402.29  4989.3  402.82
  5027.4  401.51  5027.7  401.01  5031.2  401.01  5031.4  401.51  5090.0  404.62
  5190.9  407.20  5291.8  411.04  5332.2  411.44  5382.6  412.88  5473.4  413.74
  5604.6  416.26  5655.1  415.75  5665.2  416.33  5732.9  416.93  5919.7  417.09
#Mann=3,-1,0
  4091.5    0.05       0  5027.4    0.03       0  5031.4    0.05       0
Bank Sta=5027.4,5031.4
Exp/Cntr=0.3,0.1

Type RM Length L Ch R = 1,2772,995,995,995
BEGIN DESCRIPTION:
Little Cottonwood Creek Trib 6_1 4.0
END DESCRIPTION:
XS GIS Cut Line= 3
      2668438.53      6875814.35      2667176.00      6876061.00
      2666339.21      6876274.49
#Sta/Elev= 30
  3709.6  427.67  3854.8  430.79  3929.0  431.64  4032.1  431.94  4160.5  430.49
  4341.4  426.21  4354.1  423.58  4517.1  414.79  4588.4  411.82  4609.4  409.99
  4629.2  409.84  4655.8  408.34  4670.0  408.39  4810.5  403.43  4993.5  400.04
  5119.8  400.86  5139.6  399.81  5139.9  399.31  5143.4  399.31  5143.6  399.81
  5264.3  403.50  5294.8  405.61  5299.9  405.27  5305.6  406.44  5335.6  408.94
  5398.5  411.33  5463.4  412.04  5499.1  413.21  5540.0  412.11  5859.6  413.39
#Mann=3,-1,0
  3709.6    0.05       0  5139.6    0.04       0  5143.6    0.05       0
Bank Sta=5139.6,5143.6
Exp/Cntr=0.3,0.1

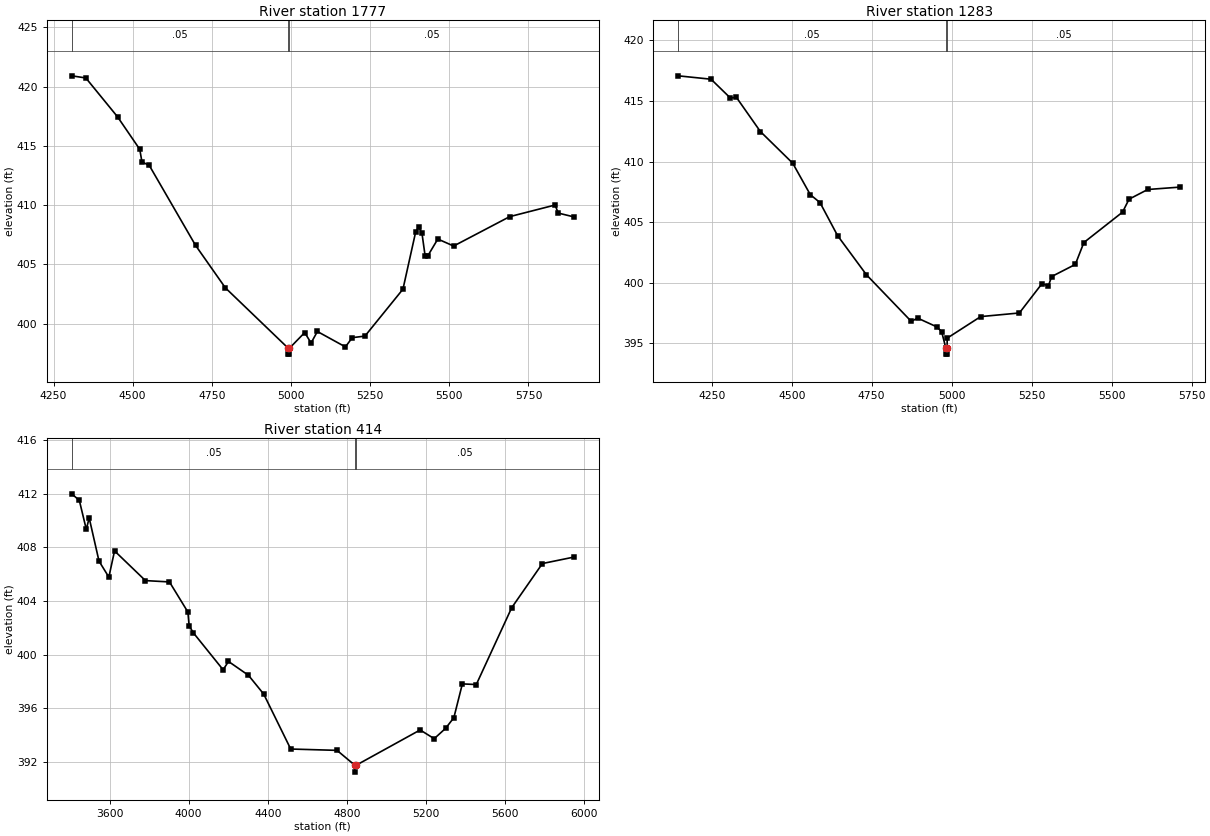
Type RM Length L Ch R = 1,1777,494,494,494
BEGIN DESCRIPTION:
Little Cottonwood Creek Trib 6_1 3.0
END DESCRIPTION:
XS GIS Cut Line= 3
      2667750.32      6875369.30      2666968.84      6875322.72
      2666166.71      6875353.77
#Sta/Elev= 30
  4307.7  420.91  4352.1  420.73  4452.3  417.45  4522.4  414.71  4529.3  413.65
  4552.5  413.35  4698.5  406.61  4792.9  403.02  4991.2  397.93  4991.5  397.43
  4995.0  397.43  4995.2  397.93  5043.3  399.25  5063.4  398.37  5083.4  399.34
  5171.9  398.04  5193.5  398.82  5233.5  398.95  5353.6  402.91  5393.6  407.72
  5403.6  408.16  5413.7  407.62  5423.7  405.70  5431.3  405.69  5463.7  407.14
  5513.7  406.55  5690.7  409.03  5834.0  410.01  5844.0  409.33  5893.3  409.01
#Mann=3,-1,0
  4307.7    0.05       0  4991.2    0.03       0  4995.2    0.05       0
Bank Sta=4991.2,4995.2
Exp/Cntr=0.3,0.1

Type RM Length L Ch R = 1,1283,869,869,869
BEGIN DESCRIPTION:
Little Cottonwood Creek Trib 6_1 2.0
END DESCRIPTION:
XS GIS Cut Line= 3
      2667776.14      6875172.64      2666988.33      6874874.44
      2666267.03      6874968.80
#Sta/Elev= 30
  4145.2  417.08  4247.8  416.80  4308.1  415.25  4327.1  415.30  4402.0  412.48
  4503.2  409.86  4558.2  407.26  4588.4  406.61  4643.4  403.88  4733.8  400.64
  4874.0  396.79  4893.4  397.07  4953.8  396.34  4968.7  395.95  4981.9  394.59
  4982.2  394.09  4985.7  394.09  4985.9  394.59  4986.1  395.41  5090.8  397.19
  5211.8  397.49  5282.4  399.91  5302.5  399.73  5312.8  400.50  5386.7  401.50
  5413.5  403.31  5534.4  405.82  5554.7  406.89  5613.2  407.69  5715.0  407.89
#Mann=3,-1,0
  4145.2    0.05       0  4981.9    0.04       0  4985.9    0.05       0
Bank Sta=4981.9,4985.9
Exp/Cntr=0.3,0.1

Type RM Length L Ch R = 1,414,0,0,0
BEGIN DESCRIPTION:
Little Cottonwood Creek Trib 6_1 1.0
END DESCRIPTION:
XS GIS Cut Line= 3
      2668159.09      6874981.15      2667029.45      6874095.94
      2666171.89      6874789.68
#Sta/Elev= 30
  3409.1  411.98  3447.3  411.49  3482.6  409.33  3497.1  410.19  3546.8  406.97
  3596.5  405.78  3625.4  407.73  3781.5  405.52  3903.0  405.42  3996.1  403.18
  4002.4  402.16  4023.3  401.64  4174.2  398.88  4201.4  399.50  4302.3  398.47
  4379.5  397.07  4515.9  392.98  4750.1  392.88  4841.2  391.76  4841.5  391.26
  4845.2  391.76  5170.3  394.40  5241.4  393.75  5298.9  394.52  5340.6  395.31
  5383.7  397.83  5454.1  397.78  5633.1  403.50  5788.3  406.79  5947.3  407.27
#Mann=3,-1,0
  3409.1    0.05       0  4841.2    0.03       0  4845.2    0.05       0
Bank Sta=4841.2,4845.2
Exp/Cntr=0.3,0.1

Chan Stop Cuts=-1