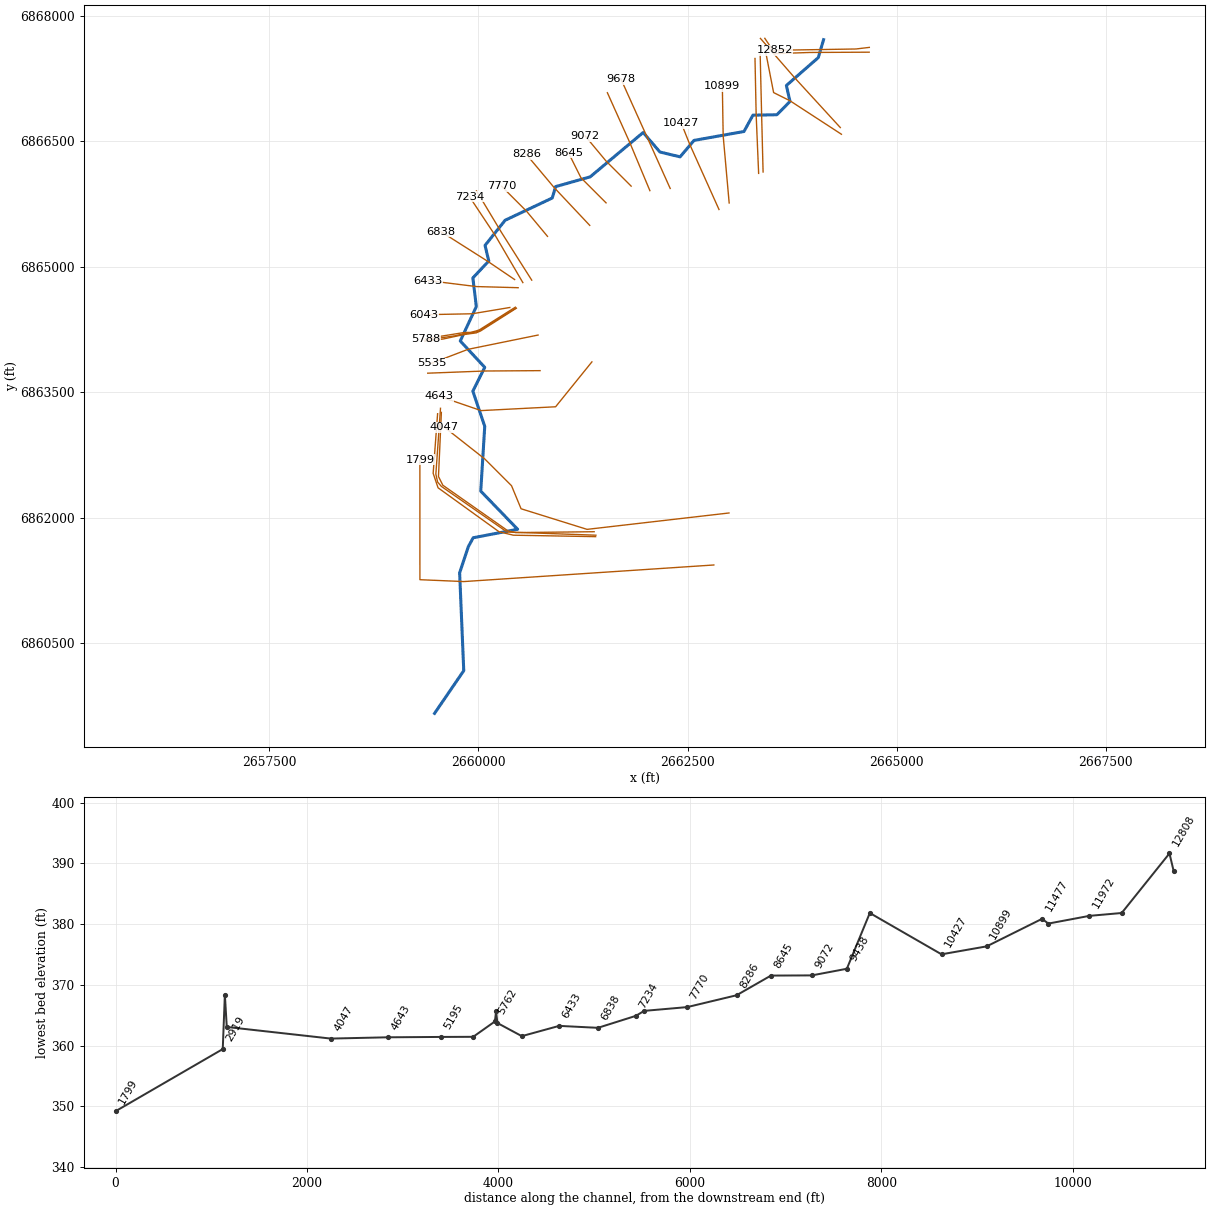
--- Little Cottonwood Creek Trib 7.prj (project) ---

Proj Title=Little Cottonwood Creek Trib 7 Base Level Engineering
Current Plan=p01
Default Exp/Contr=0.3,0.1
English Units
Geom File=g01
Flow File=f01
Plan File=p01
BEGIN DESCRIPTION:
Little Cottonwood Creek Trib 7
END DESCRIPTION:

--- Little Cottonwood Creek Trib 7.p01 (plan) ---

Plan Title=Multiple Run
Short Identifier=Multiple
Geom File=g01
Flow File=f01
Subcritical Flow
K Sum by GR= 0
Std Step Tol= 0.01
Critical Tol= 0.01
Num of Std Step Trials= 20
Max Error Tol= 0.3
Flow Tol Ratio= 0.001
Split Flow NTrial= 30
Split Flow Tol= 0.02
Split Flow Ratio= 0.02
Log Output Level= 0
Friction Slope Method= 1
Unsteady Friction Slope Method= 2
Unsteady Bridges Friction Slope Method= 1
Parabolic Critical Depth
Global Vel Dist=  1 , 1 , 1
Global Log Level= 0
CheckData=True
Encroach Param= -1, 0, 0, 0
BEGIN DESCRIPTION:
Multiple Run
END DESCRIPTION:

--- Little Cottonwood Creek Trib 7.f01 (steady flow) ---

Flow Title=Multiple
Number of Profiles=7
Profile Names=10-year,25-year,50-year,1pct_min,100-year,1pct_plu,500-year
River Rch & RM= Little Cottonwoo,Reach-1,12852
     454     599     714     422     842    1681    1173
River Rch & RM= Little Cottonwoo,Reach-1,9072
     528     701     839     498     993    1981    1391
River Rch & RM= Little Cottonwoo,Reach-1,2961
     600     805     968     578    1153    2300    1635
Boundary for River Rch & Prof#=Little Cottonwoo,Reach-1,1
Up Type=0
Dn Type=3
Dn Slope=0.005
Boundary for River Rch & Prof#=Little Cottonwoo,Reach-1,2
Up Type=0
Dn Type=3
Dn Slope=0.005
Boundary for River Rch & Prof#=Little Cottonwoo,Reach-1,3
Up Type=0
Dn Type=3
Dn Slope=0.005
Boundary for River Rch & Prof#=Little Cottonwoo,Reach-1,4
Up Type=0
Dn Type=3
Dn Slope=0.005
Boundary for River Rch & Prof#=Little Cottonwoo,Reach-1,5
Up Type=0
Dn Type=3
Dn Slope=0.005
Boundary for River Rch & Prof#=Little Cottonwoo,Reach-1,6
Up Type=0
Dn Type=3
Dn Slope=0.005
Boundary for River Rch & Prof#=Little Cottonwoo,Reach-1,7
Up Type=0
Dn Type=3
Dn Slope=0.005

--- Little Cottonwood Creek Trib 7.g01 (geometry) ---

Geom Title=Existing Conditions

River Reach=Little Cottonwoo,Reach-1
Reach XY= 30
      2664126.00      6867711.00      2664062.88      6867497.00
      2663681.40      6867163.43      2663724.83      6866973.01
      2663567.70      6866814.07      2663281.65      6866809.03
      2663174.60      6866614.06      2662577.46      6866507.46
      2662410.91      6866311.19      2662169.55      6866368.74
      2661969.33      6866602.05      2661336.32      6866072.11
      2660923.03      6865955.48      2660882.68      6865819.14
      2660319.50      6865553.27      2660079.28      6865252.58
      2660124.46      6865066.85      2659934.04      6864864.32
      2659975.23      6864521.70      2659783.29      6864110.91
      2660075.76      6863795.78      2659933.53      6863511.01
      2660075.93      6863090.97      2660028.06      6862316.85
      2660468.93      6861860.98      2659937.55      6861759.44
      2659879.55      6861652.51      2659775.72      6861340.82
      2659824.96      6860171.44      2659476.00      6859661.00

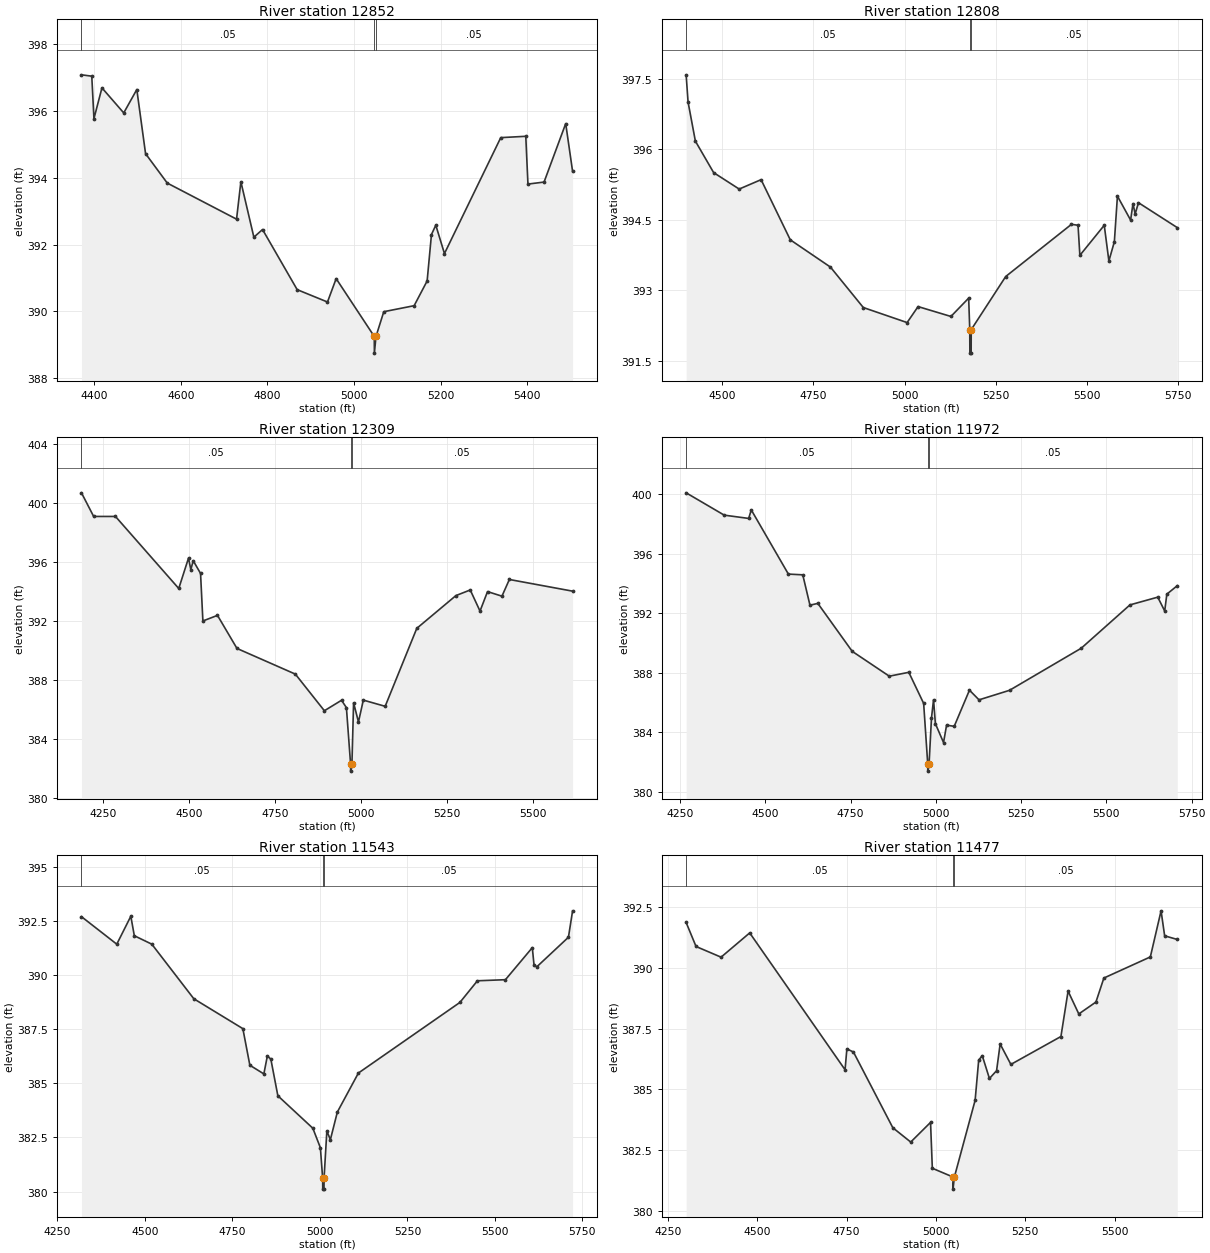
Type RM Length L Ch R = 1,12852,44,44,44
BEGIN DESCRIPTION:
Mapping XS 1920acae
END DESCRIPTION:
XS GIS Cut Line= 3
      2664672.94      6867619.02      2664513.25      6867599.92
      2663540.10      6867584.31
#Sta/Elev= 30
  4370.7  397.08  4394.5  397.04  4399.5  395.77  4418.0  396.69  4468.3  395.94
  4498.5  396.64  4518.7  394.72  4568.8  393.84  4728.8  392.76  4738.8  393.88
  4768.8  392.22  4788.8  392.45  4868.8  390.65  4938.8  390.28  4958.8  390.98
  5046.8  389.25  5047.1  388.75  5050.8  389.25  5068.8  389.99  5138.9  390.17
  5168.9  390.91  5178.9  392.30  5188.9  392.58  5208.9  391.73  5338.9  395.20
  5396.7  395.24  5401.7  393.81  5438.9  393.87  5488.9  395.62  5504.8  394.19
#Mann=3,-1,0
  4370.7    0.05       0  5046.8    0.05       0  5050.8    0.05       0
Bank Sta=5046.8,5050.8
Exp/Cntr=0.3,0.1

Type RM Length L Ch R = 1,12808,499,499,499
BEGIN DESCRIPTION:
Mapping XS 9edc3f8d
END DESCRIPTION:
XS GIS Cut Line= 4
      2664671.26      6867561.73      2663961.17      6867558.26
      2663546.24      6867544.37      2663423.79      6867727.18
#Sta/Elev= 30
  4401.5  397.58  4406.8  397.00  4426.8  396.17  4476.8  395.50  4546.8  395.15
  4606.8  395.35  4686.8  394.07  4796.8  393.49  4886.8  392.63  5006.8  392.31
  5036.8  392.65  5126.8  392.44  5175.4  392.83  5178.4  392.16  5178.7  391.66
  5182.2  391.66  5182.4  392.16  5276.9  393.29  5457.0  394.40  5475.0  394.38
  5480.0  393.74  5546.8  394.38  5559.5  393.62  5574.5  394.03  5582.9  395.00
  5619.0  394.49  5625.5  394.84  5631.5  394.62  5640.5  394.86  5746.8  394.33
#Mann=3,-1,0
  4401.5    0.05       0  5178.4    0.05       0  5182.4    0.05       0
Bank Sta=5178.4,5182.4
Exp/Cntr=0.3,0.1

Type RM Length L Ch R = 1,12309,337,337,337
BEGIN DESCRIPTION:
Little Cottonwood Creek Trib 7 21.0
END DESCRIPTION:
XS GIS Cut Line= 3
      2664326.03      6866660.96      2663776.00      6867261.00
      2663371.22      6867726.28
#Sta/Elev= 30
  4186.0  400.70  4221.5  399.10  4285.0  399.10  4469.4  394.22  4497.8  396.28
  4504.5  395.50  4511.6  396.10  4532.9  395.24  4539.7  392.02  4582.2  392.40
  4639.0  390.16  4809.1  388.42  4893.6  385.94  4943.6  386.65  4957.8  386.15
  4969.9  382.35  4970.2  381.85  4973.9  382.35  4978.7  386.48  4992.9  385.18
  5007.1  386.66  5070.7  386.24  5162.8  391.52  5276.8  393.74  5318.5  394.12
  5347.0  392.69  5368.9  394.01  5410.9  393.70  5432.5  394.83  5616.7  394.04
#Mann=3,-1,0
  4186.0    0.05       0  4969.9    0.03       0  4973.9    0.05       0
Bank Sta=4969.9,4973.9
Exp/Cntr=0.3,0.1

Type RM Length L Ch R = 1,11972,429,429,429
BEGIN DESCRIPTION:
Mapping XS dbc38615
END DESCRIPTION:
XS GIS Cut Line= 4
      2664339.61      6866580.85      2663723.32      6866981.87
      2663528.87      6867079.09      2663435.34      6867557.16
#Sta/Elev= 30
  4268.1  400.08  4379.8  398.58  4451.4  398.36  4459.1  398.93  4567.8  394.62
  4610.0  394.57  4631.1  392.53  4654.2  392.65  4754.9  389.43  4863.6  387.76
  4920.9  388.02  4964.4  385.93  4976.3  381.88  4976.5  381.38  4980.3  381.88
  4987.4  384.96  4993.4  386.18  4998.8  384.57  5022.7  383.30  5031.6  384.47
  5054.0  384.39  5098.7  386.82  5126.7  386.17  5216.1  386.81  5426.5  389.64
  5569.2  392.55  5650.7  393.07  5671.1  392.14  5677.3  393.27  5707.9  393.84
#Mann=3,-1,0
  4268.1    0.05       0  4976.3    0.03       0  4980.3    0.05       0
Bank Sta=4976.3,4980.3
Exp/Cntr=0.3,0.1

Type RM Length L Ch R = 1,11543,66,66,66
BEGIN DESCRIPTION:
Mapping XS 0bd69dfa
END DESCRIPTION:
XS GIS Cut Line= 3
      2663403.01      6866130.09      2663385.65      6866808.91
      2663368.28      6867532.86
#Sta/Elev= 30
  4318.8  392.69  4419.7  391.42  4459.8  392.71  4469.8  391.81  4519.8  391.42
  4639.8  388.90  4779.9  387.52  4799.9  385.83  4839.9  385.43  4849.9  386.26
  4859.9  386.11  4879.9  384.42  4979.9  382.92  5001.4  382.02  5007.9  380.61
  5008.2  380.11  5011.7  380.11  5011.9  380.61  5019.9  382.80  5029.9  382.39
  5049.9  383.67  5110.0  385.47  5400.0  388.73  5450.1  389.73  5530.1  389.78
  5606.9  391.26  5611.9  390.44  5620.1  390.38  5710.1  391.74  5722.0  392.96
#Mann=3,-1,0
  4318.8    0.05       0  5007.9    0.03       0  5011.9    0.05       0
Bank Sta=5007.9,5011.9
Exp/Cntr=0.3,0.1

Type RM Length L Ch R = 1,11477,578,578,578
BEGIN DESCRIPTION:
Mapping XS 3c191aab
END DESCRIPTION:
XS GIS Cut Line= 3
      2663349.75      6866113.37      2663320.24      6866814.75
      2663306.36      6867486.30
#Sta/Elev= 30
  4301.3  391.88  4329.0  390.89  4399.0  390.45  4479.1  391.45  4745.8  385.81
  4750.9  386.67  4769.3  386.54  4879.4  383.42  4929.5  382.83  4984.9  383.64
  4989.9  381.75  5047.6  381.39  5047.8  380.89  5051.6  381.39  5109.6  384.55
  5119.6  386.21  5129.6  386.39  5149.6  385.45  5169.6  385.77  5179.6  386.87
  5209.6  386.03  5349.6  387.18  5369.6  389.05  5399.6  388.11  5447.5  388.60
  5469.7  389.59  5599.7  390.46  5629.7  392.36  5639.7  391.33  5675.0  391.18
#Mann=3,-1,0
  4301.3    0.05       0  5047.6    0.03       0  5051.6    0.05       0
Bank Sta=5047.6,5051.6
Exp/Cntr=0.3,0.1

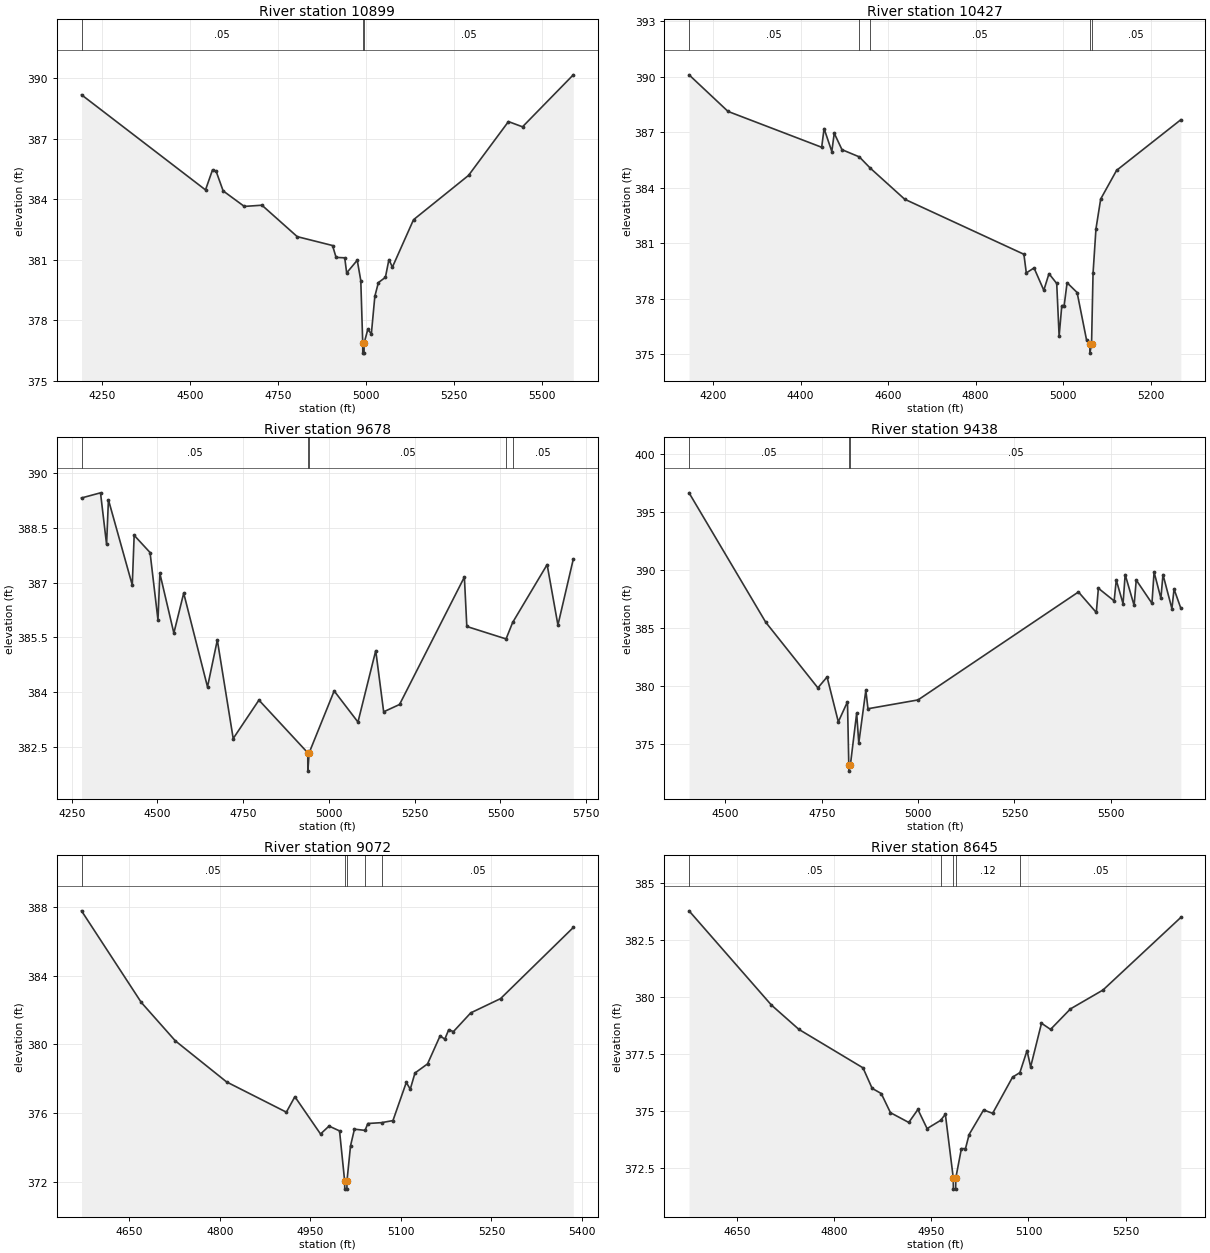
Type RM Length L Ch R = 1,10899,472,472,472
BEGIN DESCRIPTION:
Little Cottonwood Creek Trib 7 18.0
END DESCRIPTION:
XS GIS Cut Line= 3
      2662997.63      6865759.60      2662926.00      6866561.00
      2662916.03      6867155.52
#Sta/Elev= 30
  4191.1  389.18  4543.9  384.46  4564.0  385.46  4574.0  385.39  4594.1  384.41
  4654.3  383.64  4704.5  383.70  4804.9  382.14  4905.3  381.70  4915.4  381.11
  4940.0  381.09  4945.5  380.34  4975.6  380.97  4985.7  379.96  4991.2  376.86
  4991.4  376.36  4994.9  376.36  4995.2  376.86  5005.7  377.54  5015.7  377.31
  5025.7  379.18  5035.7  379.86  5055.7  380.12  5065.7  381.00  5075.7  380.63
  5135.7  382.98  5292.3  385.18  5405.8  387.85  5445.8  387.59  5590.3  390.17
#Mann=3,-1,0
  4191.1    0.05       0  4991.2    0.05       0  4995.2    0.05       0
Bank Sta=4991.2,4995.2
Exp/Cntr=0.3,0.1

Type RM Length L Ch R = 1,10427,749,749,749
BEGIN DESCRIPTION:
Little Cottonwood Creek Trib 7 17.0
END DESCRIPTION:
XS GIS Cut Line= 3
      2662876.10      6865681.51      2662526.00      6866461.00
      2662425.99      6866711.04
#Sta/Elev= 30
  4145.0  390.11  4234.1  388.13  4448.1  386.19  4453.6  387.20  4471.3  385.96
  4476.8  386.95  4494.5  386.06  4534.1  385.67  4559.2  385.06  4637.7  383.38
  4910.2  380.40  4915.7  379.39  4933.4  379.66  4955.7  378.45  4967.5  379.35
  4985.2  378.82  4990.7  375.97  4996.8  377.62  5002.2  377.62  5008.9  378.86
  5031.8  378.33  5053.4  375.76  5060.8  375.55  5061.0  375.05  5064.8  375.55
  5068.2  379.36  5074.9  381.78  5085.7  383.39  5122.0  384.94  5268.8  387.68
#Mann=5,-1,0
  4145.0    0.05       0  4534.1   0.075       0  4559.2    0.05       0
  5060.8    0.03       0  5064.8    0.05       0
Bank Sta=5060.8,5064.8
Exp/Cntr=0.3,0.1

Type RM Length L Ch R = 1,9678,240,240,240
BEGIN DESCRIPTION:
Mapping XS 3497fd78
END DESCRIPTION:
XS GIS Cut Line= 3
      2662292.74      6865933.30      2661995.89      6866592.98
      2661704.23      6867240.53
#Sta/Elev= 30
  4278.7  389.31  4334.1  389.45  4351.8  388.04  4357.2  389.26  4426.7  386.93
  4432.2  388.29  4478.5  387.82  4501.6  385.98  4507.1  387.25  4547.9  385.62
  4576.6  386.71  4646.0  384.15  4674.6  385.43  4720.9  382.74  4795.9  383.79
  4938.3  382.35  4938.5  381.85  4942.3  382.35  5015.2  384.04  5084.6  383.19
  5136.4  385.14  5159.5  383.47  5205.8  383.67  5394.8  387.15  5401.9  385.80
  5516.3  385.46  5535.5  385.91  5636.0  387.49  5667.5  385.84  5712.3  387.64
#Mann=5,-1,0
  4278.7    0.05       0  4938.3    0.04       0  4942.3    0.05       0
  5516.3   0.075       0  5535.5    0.05       0
Bank Sta=4938.3,4942.3
Exp/Cntr=0.3,0.1

Type RM Length L Ch R = 1,9438,366,366,366
BEGIN DESCRIPTION:
Mapping XS ba6ee318
END DESCRIPTION:
XS GIS Cut Line= 3
      2662049.70      6865907.23      2661811.86      6866476.66
      2661541.73      6867077.53
#Sta/Elev= 30
  4405.7  396.67  4604.7  385.51  4740.0  379.85  4763.8  380.79  4793.0  376.92
  4816.8  378.65  4820.2  373.17  4820.5  372.67  4824.2  373.17  4840.6  377.67
  4846.1  375.09  4864.4  379.64  4869.9  378.05  4999.8  378.81  5416.0  388.12
  5462.3  386.35  5467.7  388.44  5508.6  387.35  5514.1  389.15  5531.7  387.11
  5537.2  389.62  5560.4  386.96  5565.9  389.15  5606.7  387.14  5612.2  389.84
  5629.9  387.57  5635.3  389.62  5658.5  386.68  5664.0  388.37  5681.6  386.72
#Mann=3,-1,0
  4405.7    0.05       0  4820.2    0.03       0  4824.2    0.05       0
Bank Sta=4820.2,4824.2
Exp/Cntr=0.3,0.1

Type RM Length L Ch R = 1,9072,427,427,427
BEGIN DESCRIPTION:
Little Cottonwood Creek Trib 7 14.0
END DESCRIPTION:
XS GIS Cut Line= 3
      2661825.99      6865961.01      2661526.00      6866261.00
      2661275.97      6866561.03
#Sta/Elev= 30
  4570.9  387.78  4669.9  382.45  4726.4  380.21  4811.3  377.82  4910.3  376.06
  4924.4  376.96  4966.9  374.79  4981.0  375.25  4998.4  374.97  5006.8  372.08
  5007.1  371.58  5010.6  371.58  5010.8  372.08  5016.6  374.10  5023.1  375.07
  5040.7  375.00  5045.3  375.40  5068.0  375.45  5086.9  375.57  5109.0  377.79
  5115.6  377.40  5123.4  378.34  5144.2  378.87  5165.0  380.50  5172.8  380.31
  5179.3  380.86  5187.1  380.75  5215.8  381.84  5265.2  382.67  5385.7  386.81
#Mann=5,-1,0
  4570.9    0.05       0  5006.8    0.03       0  5010.8    0.05       0
  5040.7    0.12       0  5068.0    0.05       0
Bank Sta=5006.8,5010.8
Exp/Cntr=0.3,0.1

Type RM Length L Ch R = 1,8645,359,359,359
BEGIN DESCRIPTION:
Little Cottonwood Creek Trib 7 13.0
END DESCRIPTION:
XS GIS Cut Line= 3
      2661525.97      6865761.03      2661226.00      6866061.00
      2661076.01      6866360.97
#Sta/Elev= 30
  4575.7  383.78  4702.9  379.64  4745.4  378.57  4844.4  376.88  4858.5  375.98
  4872.6  375.75  4886.8  374.91  4915.1  374.48  4929.2  375.05  4943.4  374.21
  4964.2  374.57  4971.6  374.84  4983.8  372.05  4984.0  371.55  4987.5  371.55
  4987.8  372.05  4996.4  373.33  5002.7  373.33  5008.3  373.95  5030.7  375.03
  5044.6  374.88  5075.4  376.47  5086.7  376.67  5097.8  377.64  5103.3  376.92
  5120.1  378.84  5134.1  378.57  5164.8  379.47  5215.1  380.30  5335.3  383.49
#Mann=5,-1,0
  4575.7    0.05       0  4964.2    0.12       0  4983.8    0.07       0
  4987.8    0.12       0  5086.7    0.05       0
Bank Sta=4983.8,4987.8
Exp/Cntr=0.3,0.1

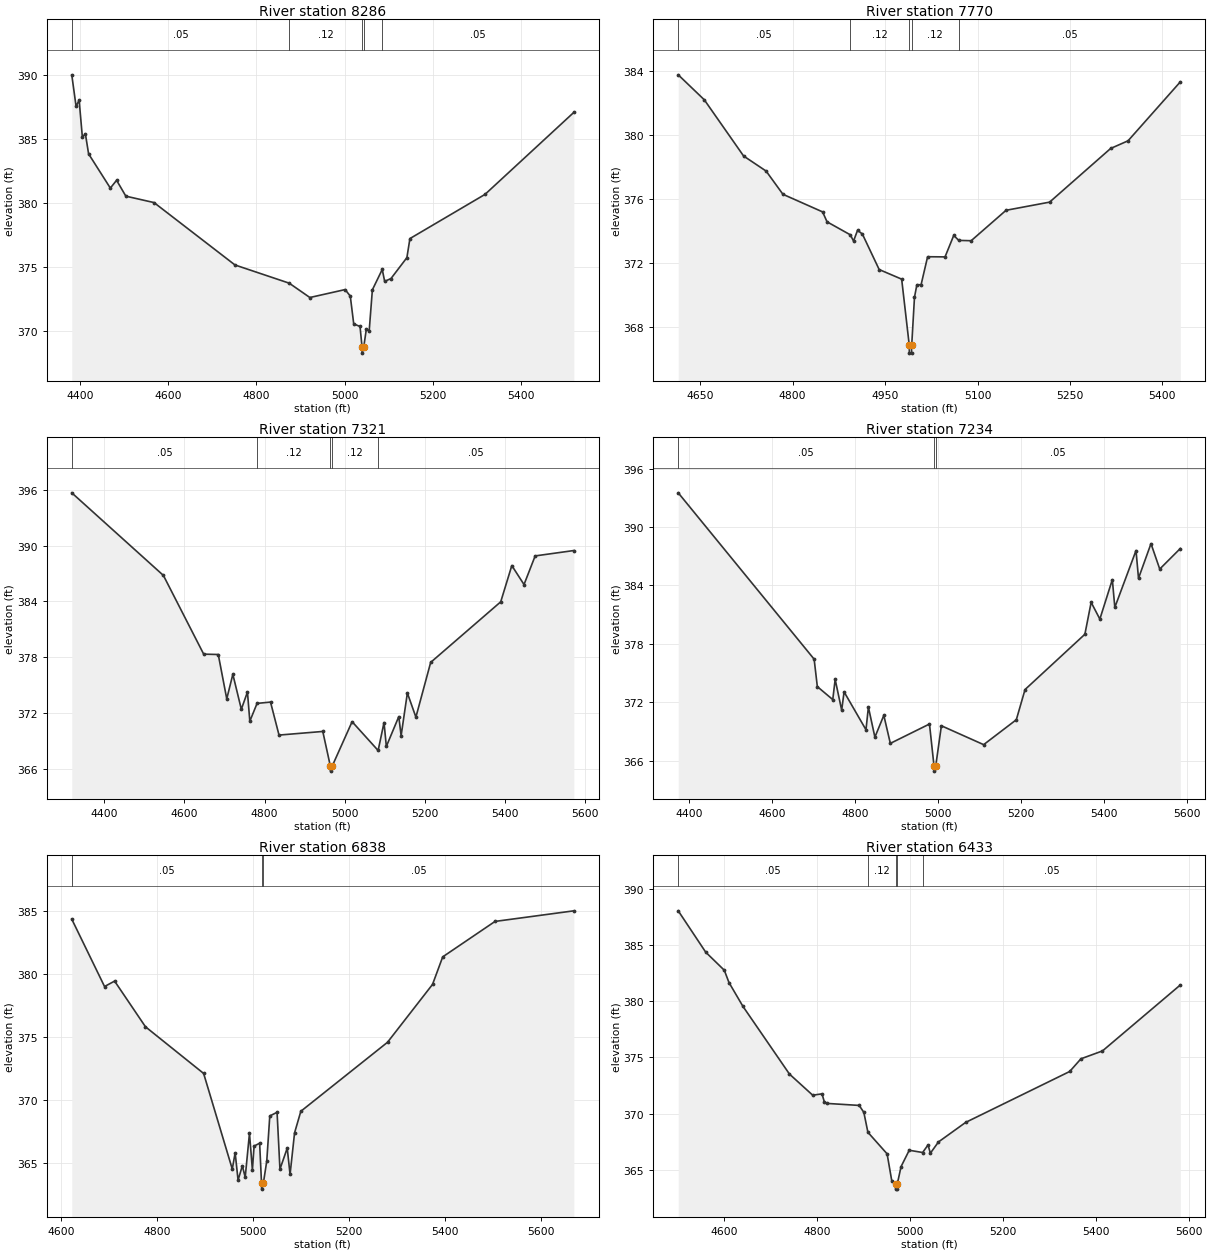
Type RM Length L Ch R = 1,8286,516,516,516
BEGIN DESCRIPTION:
Mapping XS 7760ee27
END DESCRIPTION:
XS GIS Cut Line= 3
      2661330.98      6865492.27      2660905.61      6865943.67
      2660572.25      6866341.27
#Sta/Elev= 30
  4381.0  390.03  4390.8  387.56  4397.7  388.06  4405.0  385.18  4411.9  385.42
  4419.2  383.86  4468.5  381.19  4482.7  381.80  4503.7  380.56  4567.6  380.06
  4751.3  375.19  4874.3  373.77  4921.2  372.65  5001.2  373.27  5012.9  372.76
  5020.7  370.59  5035.0  370.39  5039.5  368.81  5039.7  368.31  5043.5  368.81
  5049.3  370.18  5055.8  370.05  5063.0  373.25  5085.4  374.84  5090.9  373.91
  5105.2  374.13  5141.3  375.76  5148.2  377.25  5318.6  380.70  5520.1  387.10
#Mann=5,-1,0
  4381.0    0.05       0  4874.3    0.12       0  5039.5    0.07       0
  5043.5    0.12       0  5085.4    0.05       0
Bank Sta=5039.5,5043.5
Exp/Cntr=0.3,0.1

Type RM Length L Ch R = 1,7770,449,449,449
BEGIN DESCRIPTION:
Little Cottonwood Creek Trib 7 11.0
END DESCRIPTION:
XS GIS Cut Line= 3
      2660826.03      6865360.97      2660576.00      6865661.00
      2660276.01      6865960.99
#Sta/Elev= 30
  4614.3  383.74  4656.6  382.18  4720.4  378.67  4756.9  377.73  4784.2  376.28
  4848.6  375.18  4855.8  374.56  4893.5  373.75  4898.8  373.36  4905.3  374.03
  4913.1  373.80  4940.4  371.58  4976.9  370.98  4989.2  366.86  4989.4  366.36
  4992.9  366.36  4993.2  366.86  4997.7  369.85  5001.6  370.63  5008.4  370.63
  5019.0  372.38  5047.3  372.37  5061.4  373.71  5069.6  373.40  5089.7  373.38
  5146.3  375.28  5217.0  375.79  5316.0  379.14  5344.3  379.62  5429.1  383.30
#Mann=5,-1,0
  4614.3    0.05       0  4893.5    0.12       0  4989.2    0.07       0
  4993.2    0.12       0  5069.6    0.05       0
Bank Sta=4989.2,4993.2
Exp/Cntr=0.3,0.1

Type RM Length L Ch R = 1,7321,87,87,87
BEGIN DESCRIPTION:
Mapping XS 5cbc1081
END DESCRIPTION:
XS GIS Cut Line= 3
      2660637.36      6864837.80      2660276.27      6865407.21
      2659977.64      6865903.78
#Sta/Elev= 30
  4318.7  395.69  4547.5  386.80  4648.1  378.33  4684.5  378.29  4705.7  373.52
  4720.9  376.16  4742.1  372.40  4757.4  374.25  4763.3  371.11  4781.4  373.03
  4815.0  373.17  4836.2  369.62  4945.5  370.01  4964.6  366.24  4964.9  365.74
  4968.6  366.24  5018.7  371.06  5083.7  367.96  5098.4  370.97  5104.2  368.40
  5135.3  371.61  5141.1  369.55  5156.7  374.15  5178.0  371.55  5214.9  377.44
  5389.8  383.96  5417.5  387.86  5448.0  385.82  5475.8  388.90  5572.4  389.48
#Mann=5,-1,0
  4318.7    0.05       0  4781.4    0.12       0  4964.6    0.07       0
  4968.6    0.12       0  5083.7    0.05       0
Bank Sta=4964.6,4968.6
Exp/Cntr=0.3,0.1

Type RM Length L Ch R = 1,7234,396,396,396
BEGIN DESCRIPTION:
Mapping XS 5360e41c
END DESCRIPTION:
XS GIS Cut Line= 3
      2660531.48      6864808.25      2660205.09      6865365.55
      2659892.62      6865835.99
#Sta/Elev= 30
  4373.2  393.51  4700.9  376.42  4708.6  373.60  4745.8  372.27  4751.6  374.34
  4767.3  371.18  4773.1  373.06  4825.9  369.17  4831.7  371.50  4847.4  368.41
  4868.9  370.65  4884.6  367.77  4979.0  369.76  4990.0  365.42  4990.2  364.92
  4994.0  365.42  5007.7  369.58  5109.6  367.64  5188.4  370.20  5209.4  373.30
  5353.7  378.98  5368.8  382.26  5389.8  380.54  5419.9  384.59  5425.9  381.74
  5477.0  387.58  5483.0  384.73  5513.1  388.29  5534.2  385.68  5583.8  387.79
#Mann=3,-1,0
  4373.2    0.05       0  4990.0    0.03       0  4994.0    0.05       0
Bank Sta=4990,4994
Exp/Cntr=0.3,0.1

Type RM Length L Ch R = 1,6838,405,405,405
BEGIN DESCRIPTION:
Mapping XS c6d15c56
END DESCRIPTION:
XS GIS Cut Line= 3
      2660433.36      6864844.74      2660115.68      6865059.99
      2659554.92      6865415.89
#Sta/Elev= 30
  4621.6  384.35  4690.0  379.01  4711.0  379.44  4775.4  375.82  4896.8  372.12
  4956.6  364.54  4962.6  365.83  4968.7  363.66  4977.6  364.80  4983.6  363.89
  4992.5  367.38  4998.6  364.47  5002.1  366.36  5013.7  366.59  5017.6  363.45
  5017.9  362.95  5021.6  363.45  5028.6  365.18  5034.9  368.75  5050.1  369.04
  5056.1  364.53  5071.3  366.20  5077.2  364.11  5086.6  367.41  5099.7  369.12
  5280.6  374.59  5374.6  379.18  5395.8  381.36  5505.0  384.17  5669.5  385.01
#Mann=3,-1,0
  4621.6    0.05       0  5017.6    0.03       0  5021.6    0.05       0
Bank Sta=5017.6,5021.6
Exp/Cntr=0.3,0.1

Type RM Length L Ch R = 1,6433,390,390,390
BEGIN DESCRIPTION:
Little Cottonwood Creek Trib 7 8.0
END DESCRIPTION:
XS GIS Cut Line= 3
      2660475.08      6864747.49      2659976.00      6864761.00
      2659399.87      6864832.41
#Sta/Elev= 30
  4501.2  388.04  4560.3  384.36  4600.3  382.75  4610.3  381.66  4640.3  379.54
  4740.4  373.51  4790.4  371.63  4810.4  371.75  4815.5  371.02  4820.5  370.90
  4890.4  370.72  4900.4  370.10  4909.1  368.33  4950.4  366.41  4960.4  364.02
  4968.5  363.77  4968.7  363.27  4972.2  363.27  4972.5  363.77  4980.5  365.28
  4998.0  366.73  5026.8  366.53  5038.4  367.20  5043.5  366.47  5060.9  367.47
  5119.4  369.21  5343.1  373.74  5367.3  374.87  5413.6  375.57  5581.0  381.44
#Mann=5,-1,0
  4501.2    0.05       0  4909.1    0.12       0  4968.5    0.07       0
  4972.5    0.12       0  5026.8    0.05       0
Bank Sta=4968.5,4972.5
Exp/Cntr=0.3,0.1

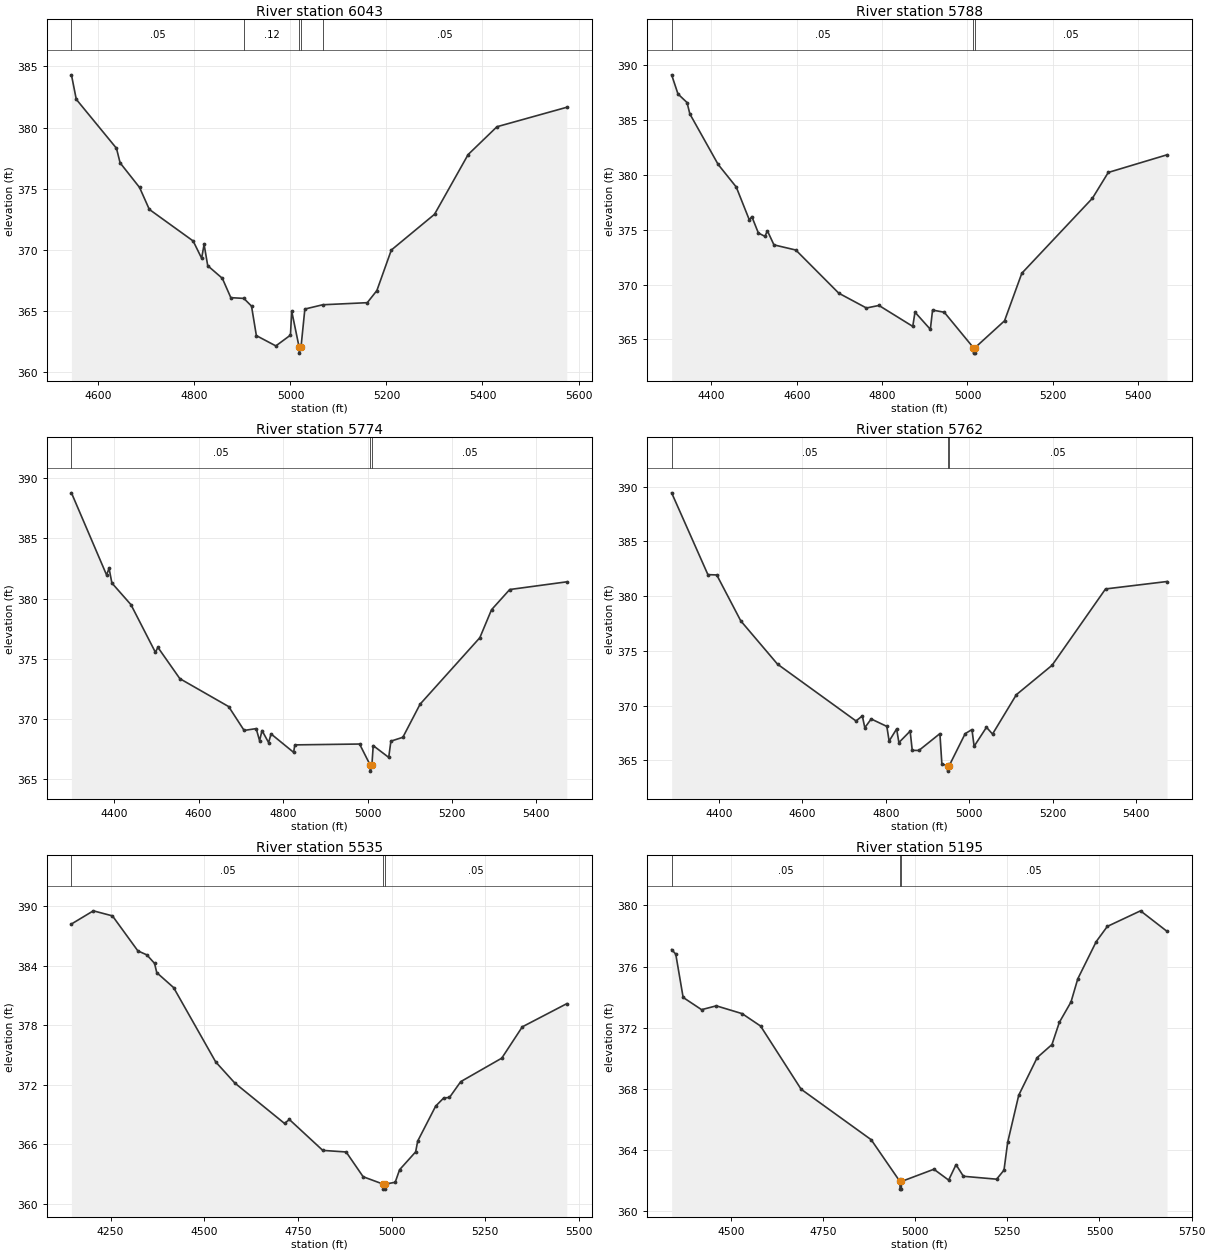
Type RM Length L Ch R = 1,6043,255,255,255
BEGIN DESCRIPTION:
Little Cottonwood Creek Trib 7 7.0
END DESCRIPTION:
XS GIS Cut Line= 3
      2660376.00      6864511.00      2659926.01      6864436.00
      2659350.52      6864424.59
#Sta/Elev= 30
  4543.8  384.31  4553.9  382.31  4637.6  378.31  4645.2  377.12  4685.7  375.11
  4706.0  373.32  4797.3  370.74  4815.0  369.33  4820.1  370.46  4827.7  368.72
  4858.1  367.69  4875.8  366.11  4902.9  366.05  4918.9  365.42  4929.0  363.01
  4969.6  362.17  5000.0  363.05  5002.6  365.01  5018.0  362.08  5018.3  361.58
  5022.0  362.08  5030.0  365.18  5067.2  365.53  5160.0  365.70  5180.0  366.69
  5210.1  370.00  5300.1  372.92  5370.1  377.80  5430.1  380.07  5575.6  381.66
#Mann=5,-1,0
  4543.8    0.05       0  4902.9    0.12       0  5018.0    0.07       0
  5022.0    0.12       0  5067.2    0.05       0
Bank Sta=5018,5022
Exp/Cntr=0.3,0.1

Type RM Length L Ch R = 1,5788,14,14,14
BEGIN DESCRIPTION:
Mapping XS ed22b76c
END DESCRIPTION:
XS GIS Cut Line= 6
      2660442.09      6864514.86      2660014.99      6864245.76
      2659971.58      6864230.13      2659902.14      6864212.77
      2659834.43      6864212.77      2659370.10      6864138.27
#Sta/Elev= 30
  4306.9  389.14  4321.8  387.39  4343.0  386.61  4349.6  385.57  4415.9  380.96
  4458.3  378.90  4488.9  375.90  4494.8  376.20  4510.1  374.70  4525.4  374.40
  4531.3  374.90  4546.6  373.62  4597.8  373.15  4698.5  369.21  4763.2  367.86
  4792.6  368.09  4871.8  366.18  4877.0  367.48  4913.0  365.91  4918.2  367.67
  4945.6  367.47  5013.8  364.24  5014.1  363.74  5017.6  363.74  5017.8  364.24
  5086.8  366.69  5127.3  371.03  5292.8  377.88  5329.8  380.23  5467.4  381.84
#Mann=3,-1,0
  4306.9    0.05       0  5013.8    0.03       0  5017.8    0.05       0
Bank Sta=5013.8,5017.8
Exp/Cntr=0.3,0.1

Type RM Length L Ch R = 1,5774,12,12,12
BEGIN DESCRIPTION:
Mapping XS 4873b110
END DESCRIPTION:
XS GIS Cut Line= 6
      2660447.30      6864502.71      2659995.89      6864224.92
      2659909.08      6864205.83      2659829.22      6864198.88
      2659721.58      6864172.84      2659362.22      6864120.76
#Sta/Elev= 30
  4298.9  388.79  4382.1  381.97  4388.0  382.52  4394.7  381.30  4439.9  379.50
  4497.7  375.55  4503.6  375.96  4555.6  373.36  4671.2  371.04  4707.8  369.06
  4736.4  369.21  4744.4  368.21  4750.2  369.05  4765.8  368.05  4771.6  368.77
  4825.0  367.24  4827.9  367.86  4981.2  367.93  5006.4  366.18  5006.6  365.68
  5010.4  366.18  5013.5  367.80  5050.2  366.82  5055.4  368.17  5083.7  368.49
  5124.5  371.24  5266.0  376.76  5293.6  379.08  5336.7  380.76  5471.9  381.40
#Mann=3,-1,0
  4298.9    0.05       0  5006.4    0.03       0  5010.4    0.05       0
Bank Sta=5006.4,5010.4
Exp/Cntr=0.3,0.1

Type RM Length L Ch R = 1,5762,227,227,227
BEGIN DESCRIPTION:
Mapping XS 3d373c03
END DESCRIPTION:
XS GIS Cut Line= 6
      2660454.23      6864502.71      2660025.40      6864230.13
      2659973.32      6864207.56      2659822.28      6864186.73
      2659580.96      6864134.65      2659359.82      6864107.00
#Sta/Elev= 30
  4286.4  389.45  4373.3  381.97  4394.5  381.94  4452.1  377.74  4540.2  373.78
  4728.2  368.59  4743.4  369.05  4749.3  367.97  4764.6  368.77  4802.1  368.09
  4807.6  366.75  4825.6  367.86  4831.0  366.61  4858.0  367.66  4863.0  365.90
  4878.9  365.89  4929.3  367.43  4934.0  364.66  4947.6  364.50  4947.8  364.00
  4951.6  364.50  4989.9  367.43  5006.1  367.80  5011.3  366.27  5040.9  368.01
  5055.4  367.39  5112.5  370.99  5198.1  373.68  5326.2  380.66  5473.5  381.34
#Mann=3,-1,0
  4286.4    0.05       0  4947.6    0.03       0  4951.6    0.05       0
Bank Sta=4947.6,4951.6
Exp/Cntr=0.3,0.1

Type RM Length L Ch R = 1,5535,340,340,340
BEGIN DESCRIPTION:
Little Cottonwood Creek Trib 7 6.0
END DESCRIPTION:
XS GIS Cut Line= 3
      2660713.33      6864181.70      2659876.00      6864011.00
      2659439.14      6863843.86
#Sta/Elev= 30
  4145.4  388.23  4203.9  389.56  4254.9  389.05  4322.7  385.52  4346.8  385.11
  4367.2  384.26  4373.2  383.32  4418.2  381.81  4530.5  374.31  4581.5  372.18
  4714.2  368.10  4727.1  368.50  4816.3  365.38  4878.7  365.22  4924.1  362.72
  4977.8  361.97  4978.0  361.47  4981.5  361.47  4981.8  361.97  5009.6  362.16
  5021.4  363.43  5064.2  365.23  5069.7  366.32  5117.7  369.85  5139.1  370.67
  5154.5  370.72  5184.6  372.32  5294.1  374.69  5348.9  377.85  5467.7  380.19
#Mann=3,-1,0
  4145.4    0.05       0  4977.8    0.03       0  4981.8    0.05       0
Bank Sta=4977.8,4981.8
Exp/Cntr=0.3,0.1

Type RM Length L Ch R = 1,5195,552,552,552
BEGIN DESCRIPTION:
Mapping XS 80b1159f
END DESCRIPTION:
XS GIS Cut Line= 3
      2660737.22      6863756.35      2660079.66      6863752.01
      2659394.23      6863725.98
#Sta/Elev= 30
  4339.6  377.11  4350.8  376.81  4370.8  373.98  4420.8  373.18  4460.8  373.43
  4530.8  372.92  4580.8  372.11  4690.8  367.98  4880.8  364.68  4958.8  361.95
  4959.1  361.45  4962.6  361.45  4962.8  361.95  5050.9  362.75  5090.9  362.04
  5110.9  363.05  5130.9  362.29  5221.0  362.10  5241.0  362.69  5251.0  364.51
  5281.0  367.59  5331.1  370.05  5371.1  370.90  5391.1  372.35  5422.7  373.68
  5441.2  375.20  5491.2  377.63  5521.2  378.62  5611.3  379.64  5683.1  378.30
#Mann=3,-1,0
  4339.6    0.05       0  4958.8    0.03       0  4962.8    0.05       0
Bank Sta=4958.8,4962.8
Exp/Cntr=0.3,0.1

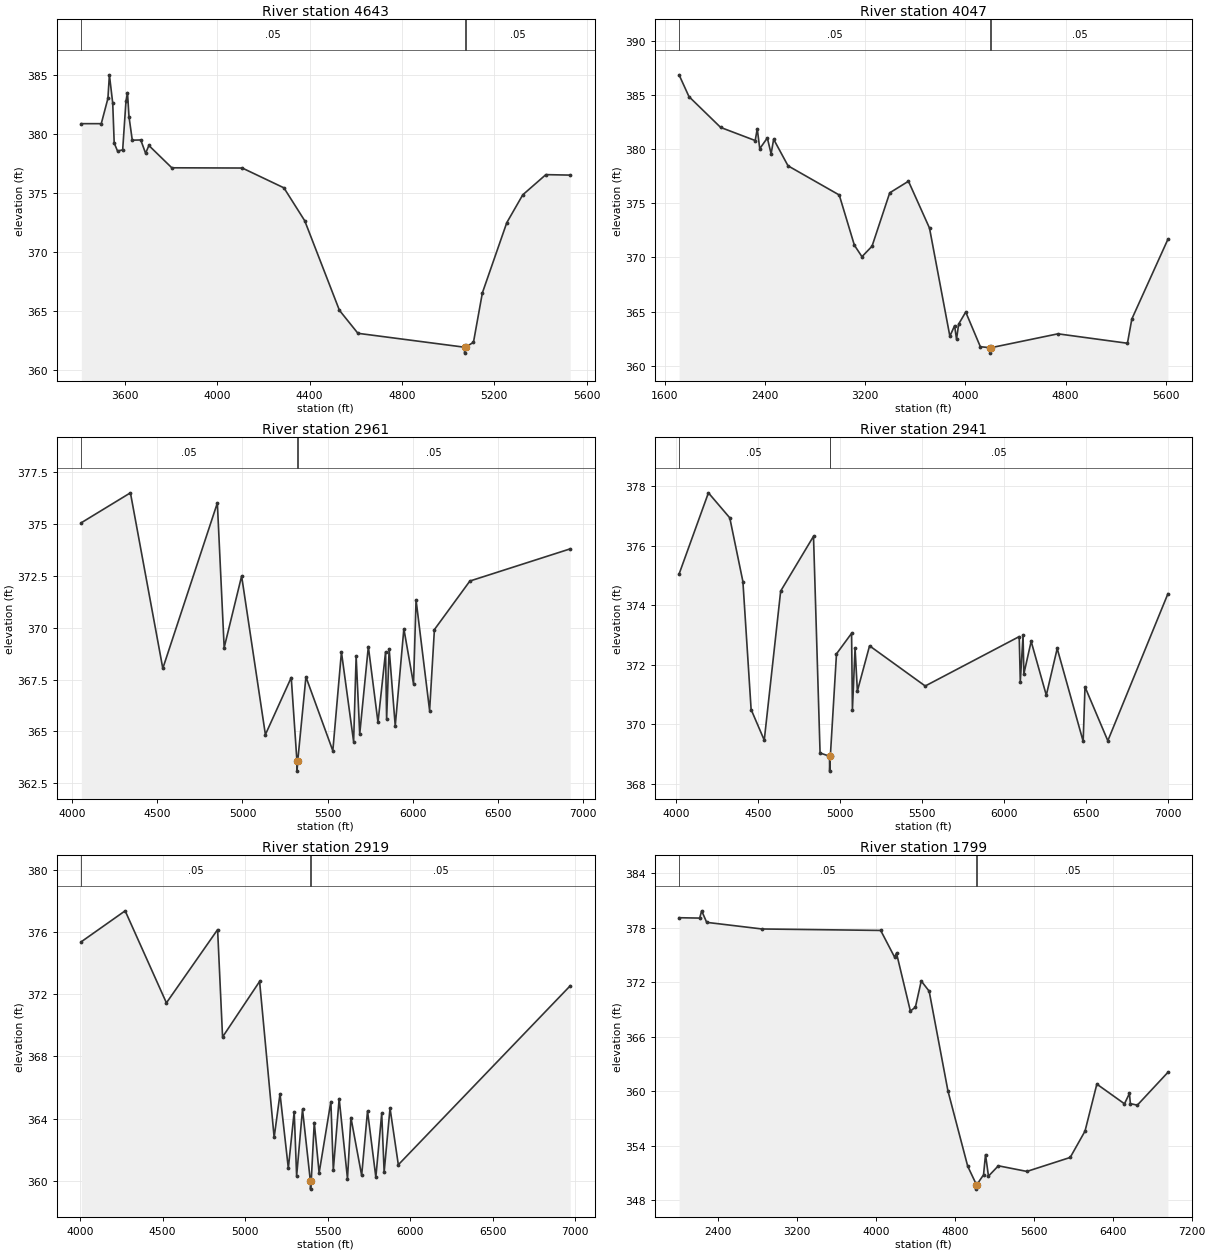
Type RM Length L Ch R = 1,4643,596,596,596
BEGIN DESCRIPTION:
Mapping XS d987cc53
END DESCRIPTION:
XS GIS Cut Line= 4
      2661356.73      6863861.12      2660922.95      6863324.67
      2660031.91      6863278.92      2659526.28      6863452.53
#Sta/Elev= 30
  3412.0  380.84  3498.2  380.84  3527.0  382.98  3533.4  384.98  3547.8  382.58
  3554.2  379.20  3568.6  378.52  3590.9  378.62  3605.1  382.73  3611.7  383.47
  3618.2  381.44  3632.5  379.44  3669.2  379.46  3690.1  378.33  3704.4  378.99
  3803.6  377.10  4108.8  377.08  4289.1  375.40  4379.2  372.61  4529.4  365.02
  4609.5  363.07  5071.3  361.89  5071.5  361.39  5075.3  361.89  5109.8  362.31
  5148.4  366.50  5254.1  372.45  5323.3  374.81  5423.3  376.52  5528.7  376.48
#Mann=3,-1,0
  3412.0    0.05       0  5071.3    0.03       0  5075.3    0.05       0
Bank Sta=5071.3,5075.3
Exp/Cntr=0.3,0.1

Type RM Length L Ch R = 1,4047,1086,1086,1086
BEGIN DESCRIPTION:
Little Cottonwood Creek Trib 7 3.0
END DESCRIPTION:
XS GIS Cut Line= 6
      2662995.59      6862055.54      2661299.17      6861859.80
      2660510.10      6862105.96      2660396.07      6862381.30
      2660076.45      6862700.81      2659592.22      6863081.89
#Sta/Elev= 30
  1715.8  386.84  1794.9  384.83  2047.6  381.99  2323.4  380.78  2339.5  381.87
  2359.6  380.03  2420.0  381.02  2450.2  379.56  2470.4  380.90  2585.2  378.45
  2993.8  375.76  3114.6  371.13  3175.0  370.07  3255.5  371.04  3396.5  375.96
  3546.1  377.03  3713.9  372.71  3876.4  362.74  3914.1  363.71  3929.6  362.47
  3946.6  363.86  4002.9  364.97  4119.6  361.77  4200.0  361.68  4200.2  361.18
  4204.0  361.68  4738.8  362.96  5293.2  362.09  5328.4  364.33  5616.2  371.68
#Mann=3,-1,0
  1715.8    0.05       0  4200.0    0.03       0  4204.0    0.05       0
Bank Sta=4200,4204
Exp/Cntr=0.3,0.1

Type RM Length L Ch R = 1,2961,20,20,20
BEGIN DESCRIPTION:
Mapping XS 87ee06ea
END DESCRIPTION:
XS GIS Cut Line= 6
      2661383.86      6861831.69      2660446.41      6861821.27
      2660352.66      6861842.11      2659574.88      6862387.25
      2659522.80      6862491.41      2659557.46      6863257.42
#Sta/Elev= 30
  4054.9  375.06  4342.8  376.50  4532.8  368.04  4852.8  376.01  4892.8  369.04
  4995.2  372.49  5134.7  364.85  5286.3  367.60  5319.6  363.59  5320.2  363.09
  5324.5  363.59  5372.5  367.63  5530.3  364.07  5580.8  368.83  5652.3  364.51
  5667.1  368.62  5688.1  364.88  5738.7  369.09  5795.3  365.44  5839.8  368.84
  5845.9  365.58  5860.8  368.98  5896.5  365.27  5947.1  369.95  6003.8  367.29
  6018.6  371.34  6098.1  366.01  6126.3  369.91  6334.4  372.25  6923.1  373.80
#Mann=3,-1,0
  4054.9    0.05       0  5319.6    0.04       0  5324.5    0.05       0
Bank Sta=5319.6,5324.5
Exp/Cntr=0.3,0.1

Type RM Length L Ch R = 1,2941,22,22,22
BEGIN DESCRIPTION:
Mapping XS 22753412
END DESCRIPTION:
XS GIS Cut Line= 6
      2661404.79      6861790.02      2660342.24      6861828.22
      2659557.52      6862373.36      2659512.38      6862425.44
      2659491.55      6862519.19      2659547.07      6863306.65
#Sta/Elev= 30
  4019.4  375.04  4198.2  377.77  4328.2  376.93  4408.2  374.79  4458.3  370.49
  4538.3  369.46  4638.3  374.47  4838.3  376.31  4878.3  369.03  4935.9  368.92
  4936.5  368.42  4940.8  368.92  4978.3  372.36  5070.2  373.05  5075.3  370.48
  5091.4  372.55  5105.5  371.11  5179.7  372.63  5518.7  371.28  6091.3  372.94
  6097.9  371.43  6114.6  372.98  6119.7  371.69  6164.0  372.78  6256.3  370.97
  6322.7  372.54  6480.8  369.42  6492.0  371.25  6631.0  369.44  6997.1  374.38
#Mann=3,-1,0
  4019.4    0.05       0  4935.9    0.04       0  4940.8    0.05       0
Bank Sta=4935.9,4940.8
Exp/Cntr=0.3,0.1

Type RM Length L Ch R = 1,2919,1120,1120,1120
BEGIN DESCRIPTION:
Mapping XS be25b283
END DESCRIPTION:
XS GIS Cut Line= 6
      2661401.26      6861772.66      2660418.63      6861790.02
      2660248.07      6861830.34      2659517.82      6862356.60
      2659459.23      6862529.13      2659512.38      6863241.41
#Sta/Elev= 30
  4007.4  375.39  4272.7  377.38  4522.7  371.45  4832.8  376.17  4862.8  369.25
  5087.2  372.83  5175.3  362.78  5210.9  365.59  5261.2  360.80  5296.8  364.44
  5311.5  360.29  5347.1  364.59  5395.0  359.95  5395.6  359.45  5399.9  359.95
  5418.3  363.74  5447.8  360.49  5518.9  365.09  5533.7  360.68  5569.2  365.28
  5619.6  360.12  5640.4  364.06  5705.5  360.33  5741.0  364.48  5791.4  360.22
  5827.0  364.33  5841.7  360.55  5877.3  364.67  5927.6  361.02  6968.9  372.55
#Mann=3,-1,0
  4007.4    0.05       0  5395.0    0.04       0  5399.9    0.05       0
Bank Sta=5395,5399.9
Exp/Cntr=0.3,0.1

Type RM Length L Ch R = 1,1799,0,0,0
BEGIN DESCRIPTION:
Little Cottonwood Creek Trib 7 2.0
END DESCRIPTION:
XS GIS Cut Line= 4
      2662814.51      6861434.24      2659826.38      6861236.00
      2659300.92      6861258.34      2659300.58      6862691.20
#Sta/Elev= 30
  2005.3  379.12  2214.3  379.08  2234.3  379.88  2285.1  378.61  2845.7  377.88
  4048.3  377.72  4188.6  374.79  4208.6  375.21  4349.0  368.84  4399.9  369.26
  4459.2  372.15  4539.4  371.03  4729.8  360.04  4930.2  351.74  5017.9  349.72
  5018.6  349.22  5022.9  349.72  5090.5  350.80  5110.5  353.02  5140.5  350.65
  5240.6  351.79  5529.8  351.17  5968.6  352.71  6118.6  355.61  6238.6  360.79
  6518.6  358.62  6568.6  359.76  6578.6  358.64  6648.6  358.47  6958.8  362.09
#Mann=3,-1,0
  2005.3    0.05       0  5017.9    0.04       0  5022.9    0.05       0
Bank Sta=5017.9,5022.9
Exp/Cntr=0.3,0.1

Chan Stop Cuts=-1