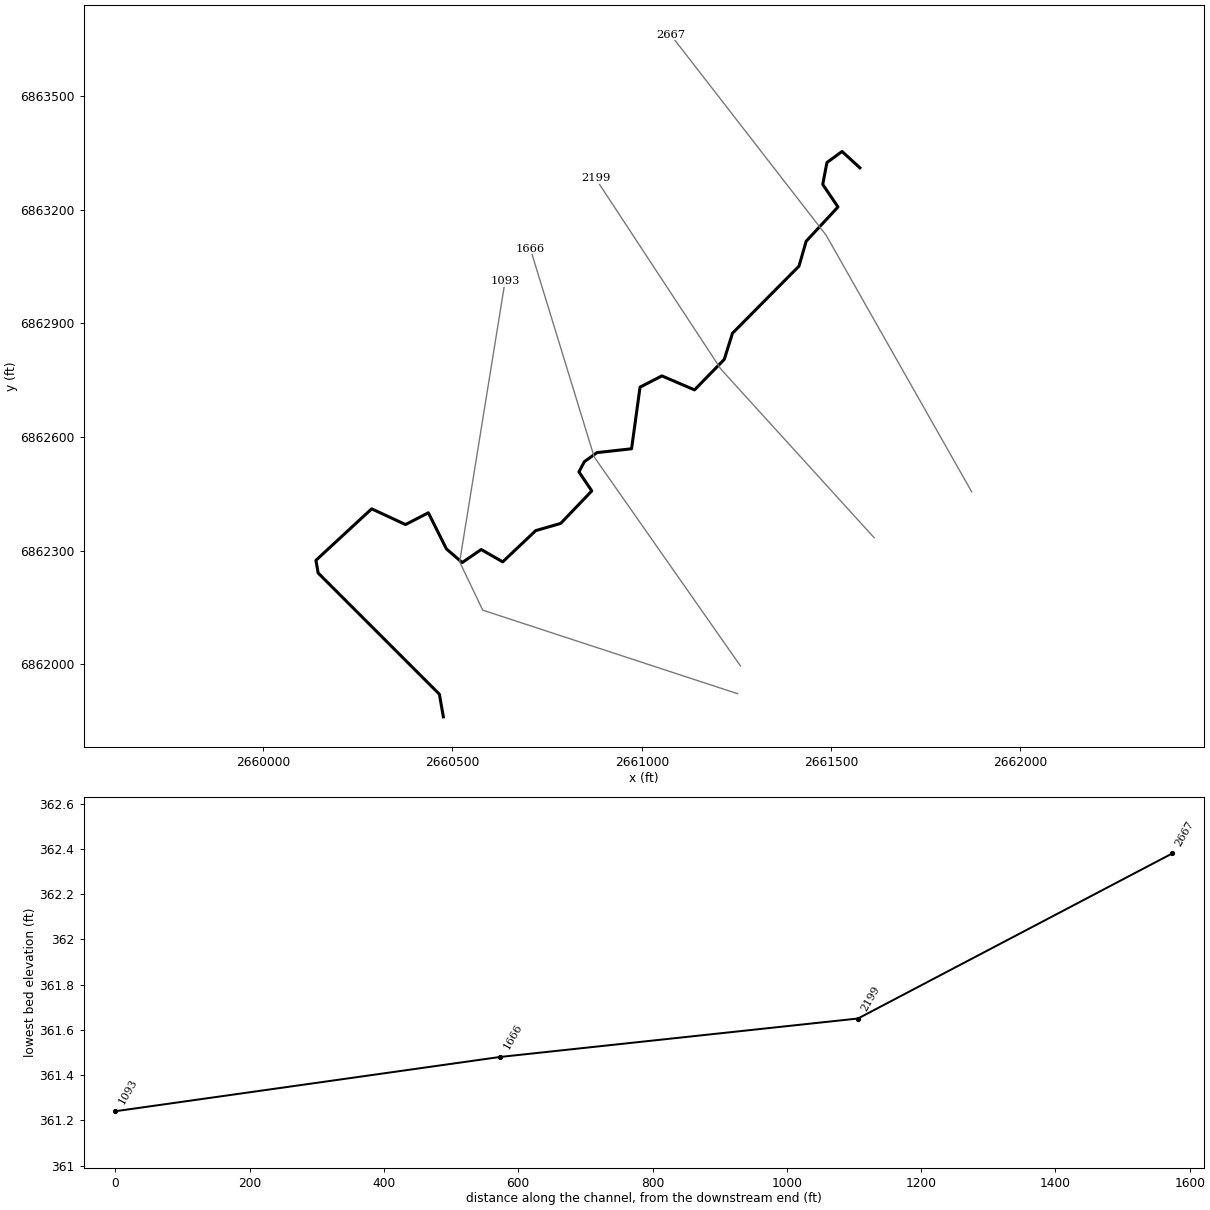
--- Little Cottonwood Creek Trib 7_1.prj (project) ---

Proj Title=Little Cottonwood Creek Trib 7_1 Base Level Engineering
Current Plan=p01
Default Exp/Contr=0.3,0.1
English Units
Geom File=g01
Flow File=f01
Plan File=p01
BEGIN DESCRIPTION:
Little Cottonwood Creek Trib 7_1
END DESCRIPTION:

--- Little Cottonwood Creek Trib 7_1.p01 (plan) ---

Plan Title=Multiple Run
Short Identifier=Multiple
Geom File=g01
Flow File=f01
Subcritical Flow
K Sum by GR= 0
Std Step Tol= 0.01
Critical Tol= 0.01
Num of Std Step Trials= 20
Max Error Tol= 0.3
Flow Tol Ratio= 0.001
Split Flow NTrial= 30
Split Flow Tol= 0.02
Split Flow Ratio= 0.02
Log Output Level= 0
Friction Slope Method= 1
Unsteady Friction Slope Method= 2
Unsteady Bridges Friction Slope Method= 1
Parabolic Critical Depth
Global Vel Dist=  1 , 1 , 1
Global Log Level= 0
CheckData=True
Encroach Param= -1, 0, 0, 0
BEGIN DESCRIPTION:
Multiple Run
END DESCRIPTION:

--- Little Cottonwood Creek Trib 7_1.f01 (steady flow) ---

Flow Title=Multiple
Number of Profiles=7
Profile Names=10-year,25-year,50-year,1pct_min,100-year,1pct_plu,500-year
River Rch & RM= Little Cottonwoo,Reach-1,2667
     350     455     538     316     630    1257     862
Boundary for River Rch & Prof#=Little Cottonwoo,Reach-1,1
Up Type=0
Dn Type=3
Dn Slope=0.005
Boundary for River Rch & Prof#=Little Cottonwoo,Reach-1,2
Up Type=0
Dn Type=3
Dn Slope=0.005
Boundary for River Rch & Prof#=Little Cottonwoo,Reach-1,3
Up Type=0
Dn Type=3
Dn Slope=0.005
Boundary for River Rch & Prof#=Little Cottonwoo,Reach-1,4
Up Type=0
Dn Type=3
Dn Slope=0.005
Boundary for River Rch & Prof#=Little Cottonwoo,Reach-1,5
Up Type=0
Dn Type=3
Dn Slope=0.005
Boundary for River Rch & Prof#=Little Cottonwoo,Reach-1,6
Up Type=0
Dn Type=3
Dn Slope=0.005
Boundary for River Rch & Prof#=Little Cottonwoo,Reach-1,7
Up Type=0
Dn Type=3
Dn Slope=0.005

--- Little Cottonwood Creek Trib 7_1.g01 (geometry) ---

Geom Title=Existing Conditions

River Reach=Little Cottonwoo,Reach-1
Reach XY= 30
      2661576.00      6863311.00      2661529.01      6863354.16
      2661489.02      6863324.95      2661477.98      6863267.11
      2661518.17      6863207.60      2661434.20      6863117.05
      2661415.22      6863051.32      2661239.63      6862874.21
      2661217.84      6862804.91      2661139.40      6862724.53
      2661053.12      6862761.40      2660995.45      6862731.75
      2660973.05      6862568.98      2660881.60      6862558.81
      2660848.33      6862534.81      2660834.08      6862507.87
      2660868.00      6862457.66      2660785.72      6862371.78
      2660719.95      6862352.80      2660632.66      6862270.31
      2660575.99      6862302.94      2660525.79      6862268.45
      2660484.16      6862304.37      2660436.32      6862399.89
      2660376.10      6862368.84      2660286.64      6862410.36
      2660139.41      6862274.33      2660145.21      6862241.00
      2660465.49      6861920.79      2660476.00      6861861.00

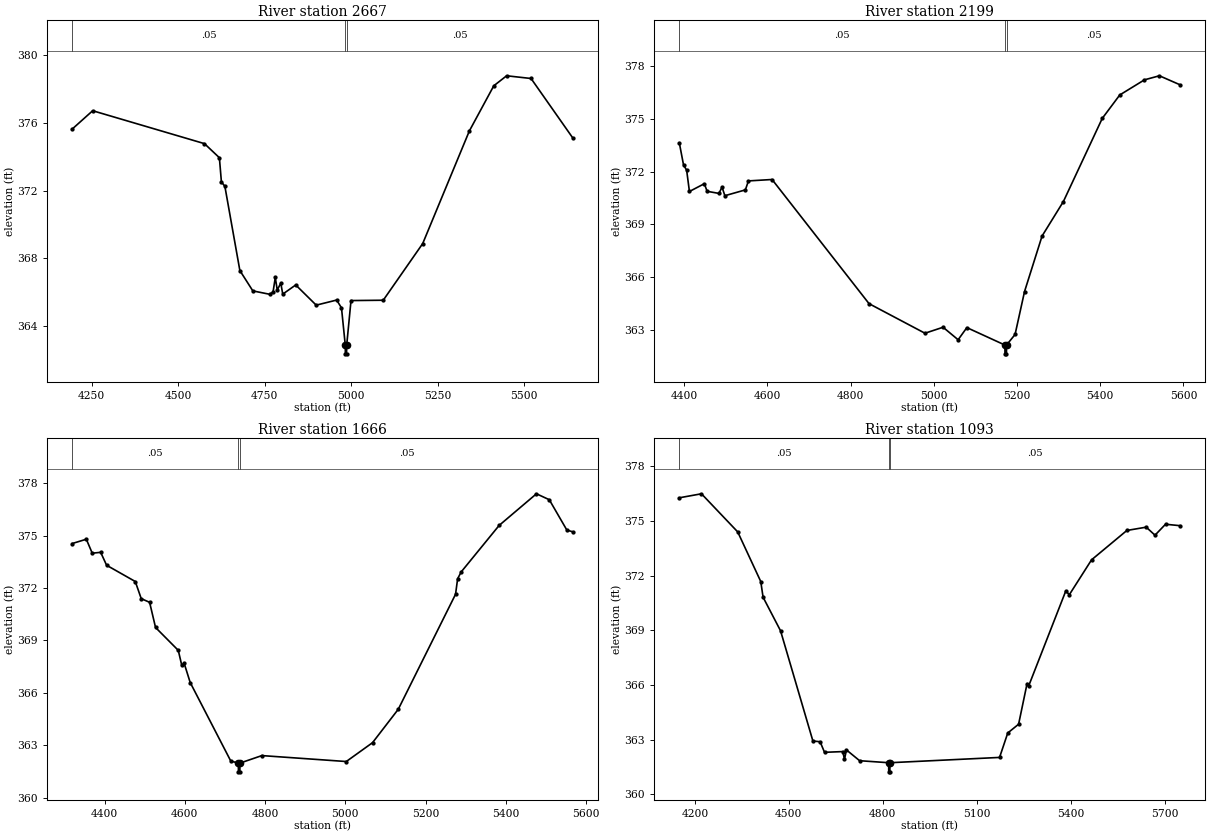
Type RM Length L Ch R = 1,2667,468,468,468
BEGIN DESCRIPTION:
Mapping XS 265b46bf
END DESCRIPTION:
XS GIS Cut Line= 3
      2661871.22      6862455.45      2661486.85      6863133.05
      2661076.60      6863662.09
#Sta/Elev= 30
  4193.3  375.62  4253.0  376.71  4576.1  374.77  4619.3  373.94  4625.1  372.52
  4635.2  372.25  4678.5  367.29  4716.0  366.09  4765.0  365.89  4774.5  366.03
  4780.9  366.88  4786.6  366.14  4796.8  366.55  4802.5  365.90  4840.0  366.44
  4899.2  365.25  4958.3  365.55  4972.3  365.09  4983.3  362.88  4983.5  362.38
  4987.0  362.38  4987.3  362.88  4999.8  365.52  5093.0  365.54  5207.1  368.88
  5342.0  375.52  5412.6  378.18  5449.7  378.77  5520.3  378.61  5641.8  375.08
#Mann=3,-1,0
  4193.3    0.05       0  4983.3    0.03       0  4987.3    0.05       0
Bank Sta=4983.3,4987.3
Exp/Cntr=0.3,0.1

Type RM Length L Ch R = 1,2199,533,533,533
BEGIN DESCRIPTION:
Mapping XS e92b96ed
END DESCRIPTION:
XS GIS Cut Line= 3
      2661613.75      6862334.01      2661209.06      6862779.16
      2660877.98      6863283.14
#Sta/Elev= 30
  4388.0  373.63  4398.1  372.38  4405.6  372.08  4412.3  370.87  4448.1  371.31
  4454.9  370.88  4483.3  370.76  4490.7  371.12  4497.5  370.63  4546.8  370.96
  4554.2  371.47  4611.0  371.55  4844.1  364.50  4978.6  362.82  5022.1  363.16
  5058.3  362.45  5079.3  363.14  5170.7  362.15  5171.0  361.65  5174.5  361.65
  5174.7  362.15  5195.2  362.75  5218.0  365.19  5260.1  368.34  5311.4  370.30
  5404.8  375.02  5446.9  376.35  5506.3  377.21  5542.2  377.44  5592.6  376.92
#Mann=3,-1,0
  4388.0    0.05       0  5170.7    0.03       0  5174.7    0.05       0
Bank Sta=5170.7,5174.7
Exp/Cntr=0.3,0.1

Type RM Length L Ch R = 1,1666,573,573,573
BEGIN DESCRIPTION:
Mapping XS c0243cef
END DESCRIPTION:
XS GIS Cut Line= 3
      2661260.56      6861995.60      2660874.30      6862547.41
      2660705.56      6863097.65
#Sta/Elev= 30
  4318.7  374.54  4354.3  374.79  4369.1  373.99  4390.1  374.04  4404.9  373.30
  4476.4  372.37  4491.2  371.39  4512.1  371.18  4526.9  369.74  4583.6  368.43
  4592.3  367.57  4598.4  367.68  4613.3  366.59  4714.4  362.10  4733.3  361.98
  4733.6  361.48  4737.1  361.48  4737.3  361.98  4792.0  362.41  5002.4  362.07
  5067.9  363.15  5132.0  365.06  5274.8  371.64  5280.0  372.53  5288.9  372.92
  5383.5  375.58  5476.5  377.39  5508.5  377.05  5552.4  375.31  5567.8  375.21
#Mann=3,-1,0
  4318.7    0.05       0  4733.3    0.03       0  4737.3    0.05       0
Bank Sta=4733.3,4737.3
Exp/Cntr=0.3,0.1

Type RM Length L Ch R = 1,1093,0,0,0
BEGIN DESCRIPTION:
Little Cottonwood Creek Trib 7_1 2.0
END DESCRIPTION:
XS GIS Cut Line= 4
      2661253.19      6861922.03      2660580.00      6862142.75
      2660519.05      6862270.17      2660638.86      6863010.95
#Sta/Elev= 30
  4150.3  376.26  4221.0  376.48  4336.8  374.39  4410.4  371.67  4417.8  370.81
  4473.6  368.97  4576.9  362.93  4599.9  362.89  4614.0  362.31  4672.4  362.35
  4677.7  361.93  4684.1  362.44  4726.1  361.85  4818.9  361.74  4819.1  361.24
  4822.6  361.24  4822.9  361.74  5173.0  362.03  5199.2  363.37  5233.8  363.85
  5260.9  366.08  5266.0  365.95  5384.4  371.15  5395.9  370.95  5466.8  372.86
  5579.6  374.47  5641.3  374.65  5669.4  374.21  5703.0  374.81  5750.4  374.73
#Mann=3,-1,0
  4150.3    0.05       0  4818.9    0.03       0  4822.9    0.05       0
Bank Sta=4818.9,4822.9
Exp/Cntr=0.3,0.1

Chan Stop Cuts=-1