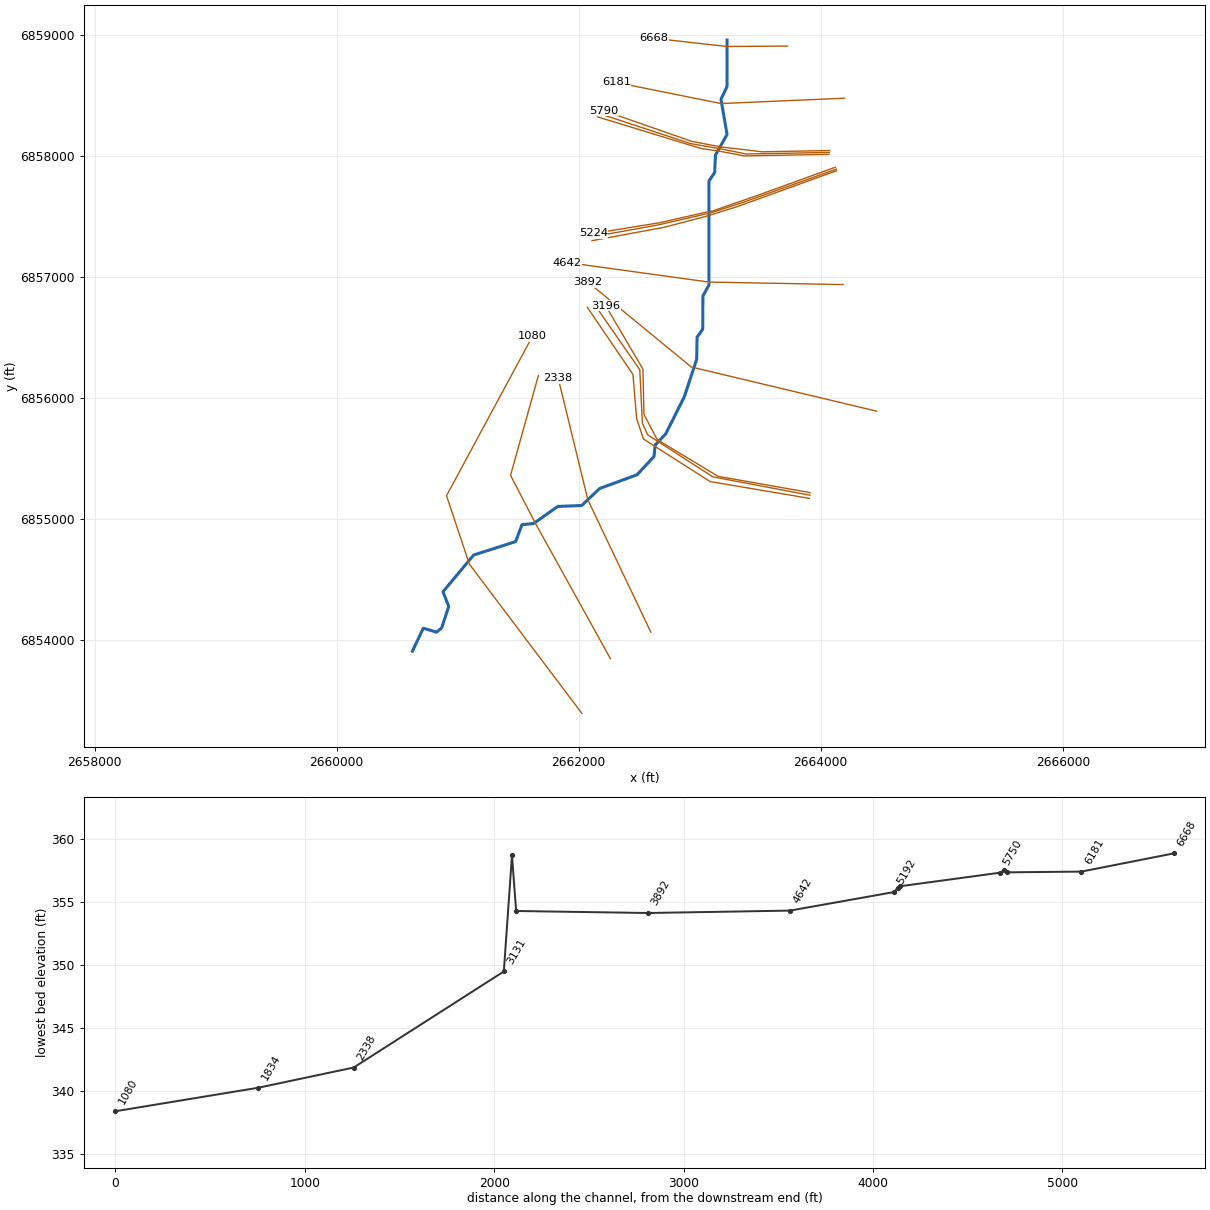
--- Little Cottonwood Creek Trib 8.prj (project) ---

Proj Title=Little Cottonwood Creek Trib 8 Base Level Engineering
Current Plan=p01
Default Exp/Contr=0.3,0.1
English Units
Geom File=g01
Flow File=f01
Plan File=p01
BEGIN DESCRIPTION:
Little Cottonwood Creek Trib 8
END DESCRIPTION:

--- Little Cottonwood Creek Trib 8.p01 (plan) ---

Plan Title=Multiple Run
Short Identifier=Multiple
Geom File=g01
Flow File=f01
Subcritical Flow
K Sum by GR= 0
Std Step Tol= 0.01
Critical Tol= 0.01
Num of Std Step Trials= 20
Max Error Tol= 0.3
Flow Tol Ratio= 0.001
Split Flow NTrial= 30
Split Flow Tol= 0.02
Split Flow Ratio= 0.02
Log Output Level= 0
Friction Slope Method= 1
Unsteady Friction Slope Method= 2
Unsteady Bridges Friction Slope Method= 1
Parabolic Critical Depth
Global Vel Dist=  1 , 1 , 1
Global Log Level= 0
CheckData=True
Encroach Param= -1, 0, 0, 0
BEGIN DESCRIPTION:
Multiple Run
END DESCRIPTION:

--- Little Cottonwood Creek Trib 8.f01 (steady flow) ---

Flow Title=Multiple
Number of Profiles=7
Profile Names=10-year,25-year,50-year,1pct_min,100-year,1pct_plu,500-year
River Rch & RM= Little Cottonwoo,Reach-1,6668
     452     599     717     426     849    1695    1192
River Rch & RM= Little Cottonwoo,Reach-1,5790
     681     921    1117     671    1340    2673    1927
River Rch & RM= Little Cottonwoo,Reach-1,2338
     798    1088    1326     801    1598    3189    2322
Boundary for River Rch & Prof#=Little Cottonwoo,Reach-1,1
Up Type=0
Dn Type=3
Dn Slope=0.005
Boundary for River Rch & Prof#=Little Cottonwoo,Reach-1,2
Up Type=0
Dn Type=3
Dn Slope=0.005
Boundary for River Rch & Prof#=Little Cottonwoo,Reach-1,3
Up Type=0
Dn Type=3
Dn Slope=0.005
Boundary for River Rch & Prof#=Little Cottonwoo,Reach-1,4
Up Type=0
Dn Type=3
Dn Slope=0.005
Boundary for River Rch & Prof#=Little Cottonwoo,Reach-1,5
Up Type=0
Dn Type=3
Dn Slope=0.005
Boundary for River Rch & Prof#=Little Cottonwoo,Reach-1,6
Up Type=0
Dn Type=3
Dn Slope=0.005
Boundary for River Rch & Prof#=Little Cottonwoo,Reach-1,7
Up Type=0
Dn Type=3
Dn Slope=0.005

--- Little Cottonwood Creek Trib 8.g01 (geometry) ---

Geom Title=Existing Conditions

River Reach=Little Cottonwoo,Reach-1
Reach XY= 30
      2663226.00      6858961.00      2663225.48      6858576.22
      2663175.50      6858471.17      2663225.96      6858181.03
      2663129.76      6858009.44      2663123.73      6857866.94
      2663076.52      6857795.78      2663076.20      6856935.92
      2663026.52      6856845.78      2663024.78      6856571.50
      2662978.26      6856505.06      2662974.78      6856321.50
      2662872.17      6856012.58      2662720.15      6855708.71
      2662631.56      6855613.36      2662622.50      6855519.48
      2662482.14      6855368.87      2662173.57      6855255.48
      2662024.54      6855114.54      2661827.55      6855107.25
      2661628.36      6854966.56      2661531.11      6854955.89
      2661478.65      6854816.43      2661131.62      6854705.38
      2660878.96      6854402.38      2660926.27      6854281.19
      2660868.15      6854104.19      2660826.33      6854068.25
      2660716.00      6854100.93      2660626.00      6853911.00

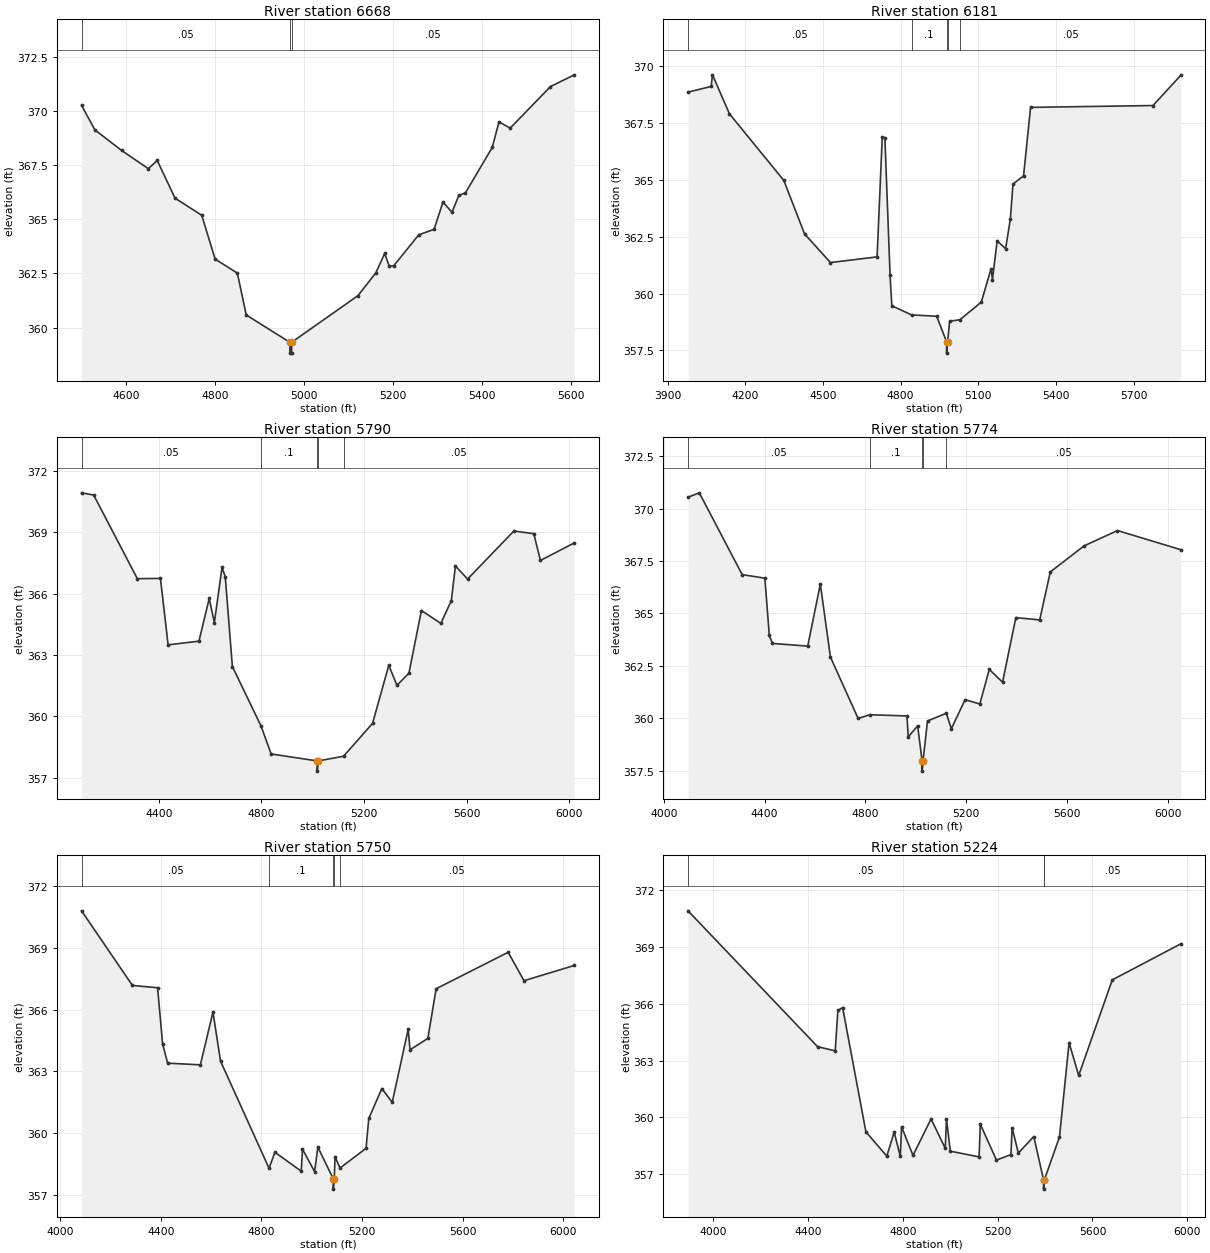
Type RM Length L Ch R = 1,6668,487,487,487
BEGIN DESCRIPTION:
Little Cottonwood Creek Trib 8 11.0
END DESCRIPTION:
XS GIS Cut Line= 3
      2663725.99      6858911.00      2663226.00      6858907.15
      2662622.79      6858974.86
#Sta/Elev= 30
  4500.0  370.25  4530.0  369.12  4590.0  368.17  4650.0  367.33  4670.0  367.71
  4710.0  365.97  4770.0  365.18  4800.0  363.16  4850.0  362.51  4870.0  360.58
  4968.0  359.32  4968.3  358.82  4971.8  358.82  4972.0  359.32  5120.8  361.47
  5161.0  362.52  5181.1  363.42  5191.2  362.83  5201.3  362.85  5257.6  364.28
  5291.8  364.53  5312.0  365.79  5332.1  365.32  5347.7  366.10  5362.3  366.21
  5422.6  368.31  5437.8  369.49  5462.9  369.20  5553.5  371.12  5607.0  371.66
#Mann=3,-1,0
  4500.0    0.05       0  4968.0    0.03       0  4972.0    0.05       0
Bank Sta=4968,4972
Exp/Cntr=0.3,0.1

Type RM Length L Ch R = 1,6181,391,391,391
BEGIN DESCRIPTION:
Little Cottonwood Creek Trib 8 10.0
END DESCRIPTION:
XS GIS Cut Line= 3
      2664195.65      6858480.07      2663175.60      6858436.00
      2662310.67      6858610.20
#Sta/Elev= 30
  3979.0  368.85  4068.5  369.10  4073.5  369.61  4138.8  367.90  4349.0  364.97
  4429.1  362.62  4529.2  361.36  4709.3  361.61  4729.3  366.89  4739.4  366.84
  4759.4  360.81  4766.3  359.46  4842.4  359.06  4939.5  359.00  4977.6  357.88
  4977.8  357.38  4981.6  357.88  4989.6  358.78  5029.2  358.85  5111.8  359.62
  5149.7  361.09  5154.8  360.61  5173.0  362.31  5205.7  361.97  5224.0  363.27
  5234.2  364.81  5275.0  365.17  5302.2  368.18  5774.9  368.26  5882.3  369.59
#Mann=5,-1,0
  3979.0    0.05       0  4842.4     0.1       0  4977.6    0.07       0
  4981.6     0.1       0  5029.2    0.05       0
Bank Sta=4977.6,4981.6
Exp/Cntr=0.3,0.1

Type RM Length L Ch R = 1,5790,16,16,16
BEGIN DESCRIPTION:
Mapping XS b4815dcd
END DESCRIPTION:
XS GIS Cut Line= 5
      2664073.28      6858047.78      2663516.01      6858037.36
      2663182.67      6858076.42      2662935.28      6858123.30
      2662203.49      6858378.51
#Sta/Elev= 30
  4099.4  370.94  4146.7  370.83  4316.7  366.74  4406.7  366.75  4436.7  363.50
  4556.8  363.68  4596.8  365.77  4616.8  364.59  4646.8  367.29  4659.3  366.83
  4687.0  362.44  4798.6  359.53  4838.0  358.16  5017.5  357.82  5017.8  357.32
  5021.5  357.82  5120.2  358.05  5233.3  359.66  5296.4  362.50  5328.1  361.52
  5374.8  362.11  5423.5  365.18  5499.1  364.55  5540.0  365.66  5556.0  367.36
  5603.5  366.72  5783.5  369.07  5861.4  368.94  5887.1  367.63  6019.2  368.49
#Mann=5,-1,0
  4099.4    0.05       0  4798.6     0.1       0  5017.5    0.07       0
  5021.5     0.1       0  5120.2    0.05       0
Bank Sta=5017.5,5021.5
Exp/Cntr=0.3,0.1

Type RM Length L Ch R = 1,5774,24,24,24
BEGIN DESCRIPTION:
Mapping XS b274bb8f
END DESCRIPTION:
XS GIS Cut Line= 5
      2664070.73      6858032.15      2663383.20      6858019.13
      2663164.45      6858063.40      2662924.86      6858105.07
      2662164.42      6858355.08
#Sta/Elev= 30
  4096.3  370.54  4141.0  370.75  4311.1  366.85  4401.1  366.68  4418.7  363.96
  4431.1  363.57  4571.1  363.44  4621.1  366.40  4661.1  362.92  4771.1  359.99
  4817.5  360.17  4964.7  360.11  4969.8  359.11  5007.1  359.64  5024.6  357.98
  5024.9  357.48  5028.6  357.98  5046.2  359.87  5120.7  360.24  5140.8  359.50
  5195.4  360.89  5253.8  360.68  5291.2  362.33  5343.9  361.72  5396.5  364.80
  5491.2  364.69  5533.3  366.98  5667.2  368.22  5799.7  368.95  6050.8  368.04
#Mann=5,-1,0
  4096.3    0.05       0  4817.5     0.1       0  5024.6    0.07       0
  5028.6     0.1       0  5120.7    0.05       0
Bank Sta=5024.6,5028.6
Exp/Cntr=0.3,0.1

Type RM Length L Ch R = 1,5750,526,526,526
BEGIN DESCRIPTION:
Mapping XS 771fb3fd
END DESCRIPTION:
XS GIS Cut Line= 5
      2664068.04      6858016.53      2663367.57      6858003.51
      2663174.86      6858039.97      2663005.59      6858066.01
      2662154.77      6858326.20
#Sta/Elev= 30
  4085.4  370.79  4287.5  367.17  4387.5  367.06  4407.5  364.32  4427.5  363.40
  4557.5  363.32  4607.5  365.88  4637.5  363.50  4830.4  358.30  4853.5  359.08
  4958.2  358.16  4963.2  359.23  5011.3  358.14  5024.2  359.33  5085.4  357.79
  5085.6  357.29  5089.4  357.79  5092.4  358.87  5112.0  358.31  5215.7  359.27
  5226.6  360.72  5278.4  362.17  5319.7  361.50  5383.0  365.04  5390.5  364.05
  5461.3  364.60  5494.1  367.01  5780.4  368.78  5843.1  367.40  6043.1  368.14
#Mann=5,-1,0
  4085.4    0.05       0  4830.4     0.1       0  5085.4    0.07       0
  5089.4     0.1       0  5112.0    0.05       0
Bank Sta=5085.4,5089.4
Exp/Cntr=0.3,0.1

Type RM Length L Ch R = 1,5224,14,14,14
BEGIN DESCRIPTION:
Mapping XS 84ad2307
END DESCRIPTION:
XS GIS Cut Line= 6
      2664120.15      6857909.75      2663487.36      6857680.59
      2663104.55      6857547.78      2663070.70      6857542.57
      2662669.65      6857451.42      2662120.56      6857362.94
#Sta/Elev= 30
  3892.9  370.89  4439.7  363.73  4514.2  363.51  4525.4  365.64  4545.4  365.79
  4643.8  359.24  4731.9  357.96  4763.1  359.22  4788.9  357.95  4794.2  359.50
  4842.6  358.00  4918.7  359.92  4978.7  358.37  4983.8  359.93  5000.0  358.22
  5121.5  357.92  5126.7  359.64  5194.8  357.75  5255.9  358.04  5261.0  359.46
  5287.1  358.12  5352.3  358.99  5393.4  356.72  5393.6  356.22  5397.4  356.72
  5460.8  358.97  5501.4  363.94  5541.9  362.21  5683.7  367.25  5972.8  369.15
#Mann=3,-1,0
  3892.9    0.05       0  5393.4    0.03       0  5397.4    0.05       0
Bank Sta=5393.4,5397.4
Exp/Cntr=0.3,0.1

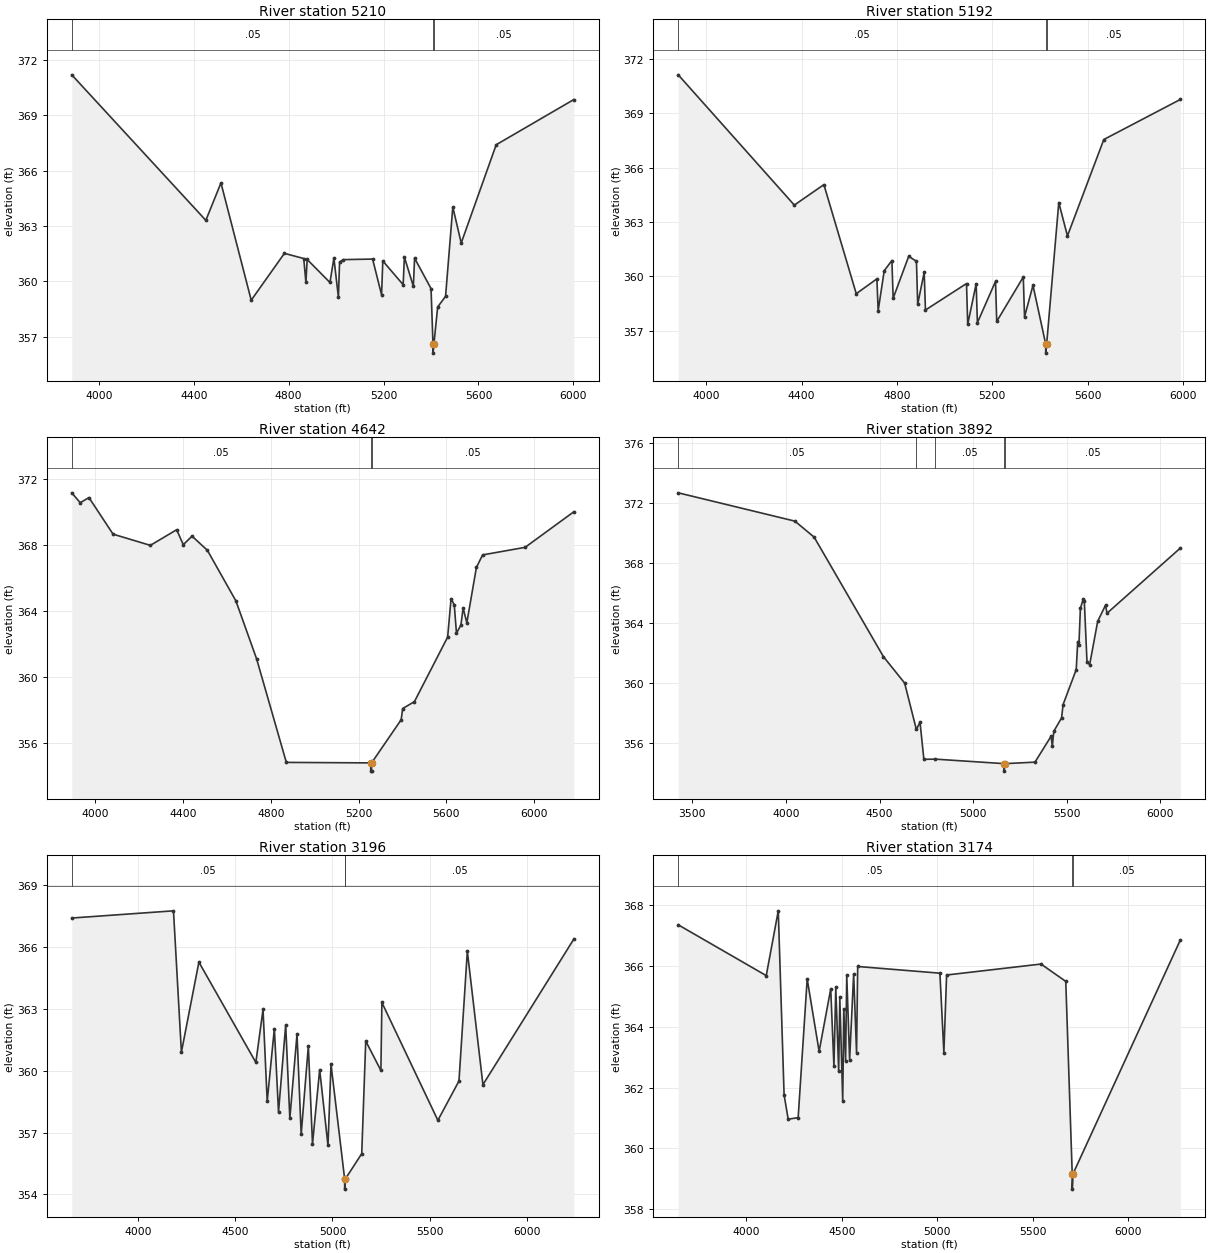
Type RM Length L Ch R = 1,5210,18,18,18
BEGIN DESCRIPTION:
Mapping XS 80daa454
END DESCRIPTION:
XS GIS Cut Line= 5
      2664128.01      6857894.14      2663362.36      6857620.69
      2663088.92      6857532.15      2662656.63      6857433.19
      2662094.13      6857331.63
#Sta/Elev= 30
  3886.3  371.19  4451.2  363.30  4514.9  365.33  4642.4  358.97  4782.2  361.51
  4863.7  361.23  4872.9  359.93  4878.1  361.18  4974.1  359.93  4990.8  361.25
  5009.7  359.14  5014.8  361.04  5030.8  361.17  5153.9  361.20  5191.7  359.26
  5196.8  361.10  5282.6  359.81  5287.8  361.31  5325.6  359.72  5330.7  361.25
  5400.1  359.60  5408.3  356.60  5408.6  356.10  5412.3  356.60  5428.0  358.60
  5461.3  359.18  5491.8  364.02  5527.2  362.07  5674.7  367.40  6001.8  369.85
#Mann=3,-1,0
  3886.3    0.05       0  5408.3    0.03       0  5412.3    0.05       0
Bank Sta=5408.3,5412.3
Exp/Cntr=0.3,0.1

Type RM Length L Ch R = 1,5192,550,550,550
BEGIN DESCRIPTION:
Mapping XS 6f105b53
END DESCRIPTION:
XS GIS Cut Line= 5
      2664130.58      6857881.11      2663310.28      6857584.24
      2663042.05      6857500.90      2662700.90      6857412.36
      2662110.42      6857303.11
#Sta/Elev= 30
  3882.3  371.12  4369.3  363.93  4493.3  365.06  4629.1  359.04  4715.7  359.86
  4721.0  358.10  4746.4  360.31  4778.6  360.87  4783.9  358.79  4849.0  361.10
  4881.6  360.83  4886.8  358.46  4914.1  360.22  4919.4  358.14  5091.6  359.60
  5096.7  357.35  5132.1  359.59  5137.3  357.44  5213.3  359.72  5218.4  357.51
  5329.8  359.96  5335.0  357.76  5370.4  359.50  5423.8  356.26  5424.0  355.76
  5427.8  356.26  5478.7  364.07  5515.0  362.23  5667.6  367.55  5988.5  369.76
#Mann=3,-1,0
  3882.3    0.05       0  5423.8    0.03       0  5427.8    0.05       0
Bank Sta=5423.8,5427.8
Exp/Cntr=0.3,0.1

Type RM Length L Ch R = 1,4642,750,750,750
BEGIN DESCRIPTION:
Little Cottonwood Creek Trib 8 7.0
END DESCRIPTION:
XS GIS Cut Line= 3
      2664184.39      6856940.14      2663076.00      6856961.00
      2661905.76      6857122.43
#Sta/Elev= 30
  3891.8  371.19  3930.2  370.59  3970.2  370.90  4080.2  368.68  4250.2  368.00
  4370.3  368.95  4400.3  368.04  4440.3  368.56  4510.3  367.70  4640.3  364.63
  4735.0  361.10  4870.4  354.82  5255.2  354.79  5255.4  354.29  5258.9  354.29
  5259.2  354.79  5394.1  357.41  5401.0  358.09  5454.6  358.51  5606.1  362.43
  5621.8  364.76  5636.3  364.39  5646.4  362.67  5666.6  363.16  5676.7  364.19
  5693.7  363.30  5737.3  366.66  5765.6  367.42  5959.4  367.88  6181.7  370.04
#Mann=3,-1,0
  3891.8    0.05       0  5255.2    0.03       0  5259.2    0.05       0
Bank Sta=5255.2,5259.2
Exp/Cntr=0.3,0.1

Type RM Length L Ch R = 1,3892,696,696,696
BEGIN DESCRIPTION:
Little Cottonwood Creek Trib 8 6.0
END DESCRIPTION:
XS GIS Cut Line= 3
      2664462.22      6855894.12      2662929.86      6856259.40
      2662075.04      6856961.84
#Sta/Elev= 30
  3424.7  372.68  4047.9  370.79  4150.7  369.72  4520.8  361.74  4633.9  359.98
  4696.5  356.88  4716.1  357.37  4736.7  354.89  4798.8  354.90  5165.3  354.60
  5165.6  354.10  5169.3  354.60  5330.2  354.70  5416.3  356.43  5422.8  355.77
  5430.7  356.76  5472.3  357.66  5480.2  358.54  5550.5  360.88  5558.4  362.75
  5564.8  362.51  5572.7  364.96  5587.1  365.56  5593.5  365.49  5607.9  361.41
  5622.2  361.21  5665.1  364.10  5706.9  365.18  5714.8  364.64  6106.4  368.99
#Mann=5,-1,0
  3424.7    0.05       0  4696.5     0.1       0  4798.8    0.05       0
  5165.3    0.03       0  5169.3    0.05       0
Bank Sta=5165.3,5169.3
Exp/Cntr=0.3,0.1

Type RM Length L Ch R = 1,3196,22,22,22
BEGIN DESCRIPTION:
Mapping XS c1b6e9cb
END DESCRIPTION:
XS GIS Cut Line= 6
      2663910.93      6855221.40      2663151.42      6855355.94
      2662647.95      6855659.76      2662539.45      6855868.09
      2662530.77      6856241.35      2662222.77      6856766.25
#Sta/Elev= 30
  3659.9  367.42  4182.8  367.77  4223.5  360.91  4313.4  365.28  4606.2  360.41
  4643.1  362.98  4664.5  358.52  4701.3  362.05  4722.7  358.00  4759.6  362.23
  4780.9  357.69  4817.8  361.78  4839.2  356.92  4876.0  361.20  4897.4  356.45
  4934.3  360.06  4977.0  356.38  4992.5  360.32  5062.6  354.76  5062.9  354.26
  5066.6  354.76  5150.5  355.98  5171.1  361.45  5249.0  360.02  5254.1  363.32
  5541.9  357.60  5650.4  359.51  5693.4  365.81  5773.5  359.33  6240.9  366.40
#Mann=3,-1,0
  3659.9    0.05       0  5062.6    0.03       0  5066.6    0.05       0
Bank Sta=5062.6,5066.6
Exp/Cntr=0.3,0.1

Type RM Length L Ch R = 1,3174,43,43,43
BEGIN DESCRIPTION:
Mapping XS ec4247d5
END DESCRIPTION:
XS GIS Cut Line= 6
      2663910.97      6855199.69      2663108.02      6855351.60
      2662569.83      6855698.82      2662526.42      6855794.31
      2662504.72      6856237.01      2662148.83      6856749.16
#Sta/Elev= 30
  3643.4  367.35  4104.5  365.68  4167.5  367.81  4198.0  361.76  4219.4  360.96
  4271.7  361.01  4319.0  365.57  4381.5  363.19  4442.3  365.24  4459.1  362.70
  4468.8  365.29  4484.0  362.53  4489.9  364.97  4505.1  361.56  4511.0  364.58
  4520.2  362.88  4526.2  365.70  4541.3  362.92  4562.4  365.73  4577.6  363.15
  4583.6  365.98  5014.3  365.76  5035.1  363.15  5049.4  365.70  5544.0  366.06
  5673.7  365.49  5707.5  359.16  5707.8  358.66  5711.5  359.16  6273.8  366.85
#Mann=3,-1,0
  3643.4    0.05       0  5707.5    0.03       0  5711.5    0.05       0
Bank Sta=5707.5,5711.5
Exp/Cntr=0.3,0.1

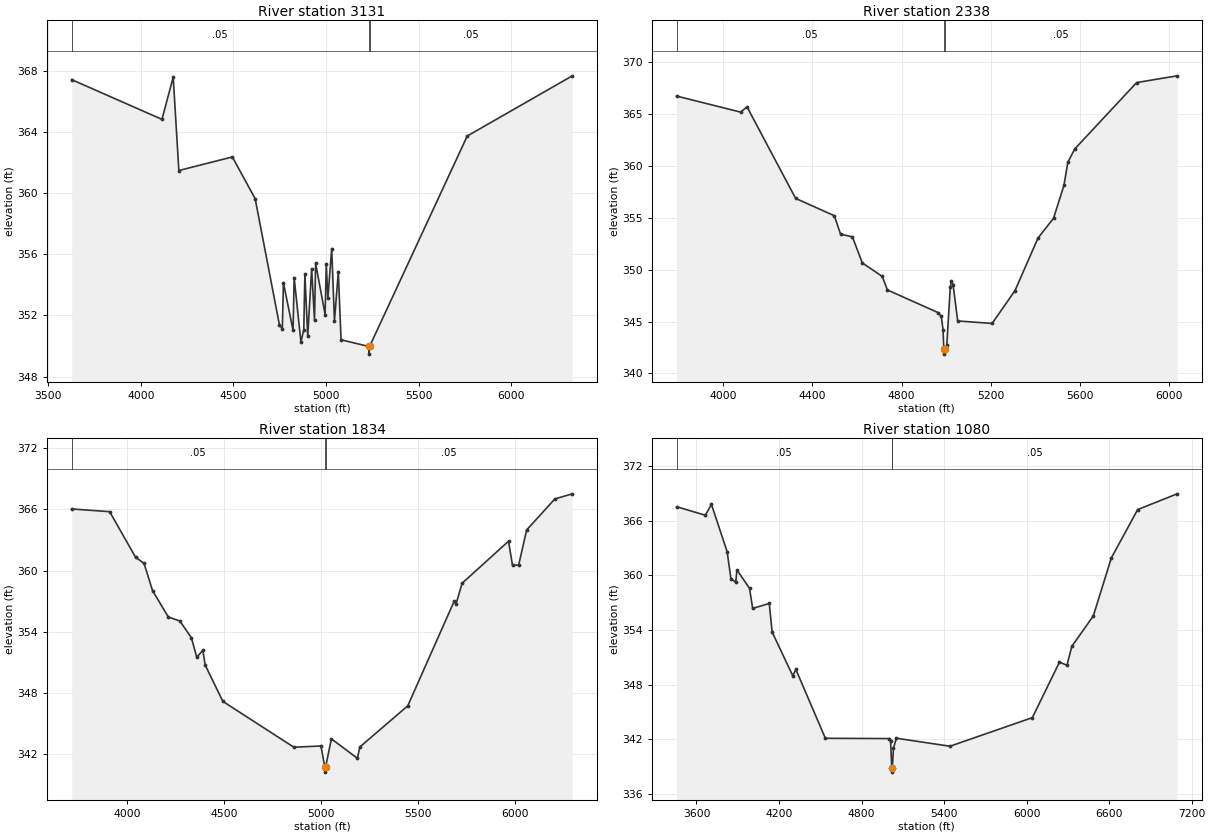
Type RM Length L Ch R = 1,3131,793,793,793
BEGIN DESCRIPTION:
Mapping XS 453b66e0
END DESCRIPTION:
XS GIS Cut Line= 6
      2663906.59      6855173.65      2663086.32      6855312.53
      2662535.11      6855664.10      2662478.68      6855833.37
      2662448.30      6856197.95      2662070.85      6856753.28
#Sta/Elev= 30
  3627.1  367.44  4114.5  364.84  4175.3  367.60  4205.8  361.49  4494.7  362.38
  4618.0  359.64  4749.2  351.37  4764.6  351.14  4770.5  354.14  4822.6  351.03
  4828.4  354.48  4865.1  350.26  4880.5  351.08  4886.4  354.72  4901.8  350.65
  4923.0  355.07  4938.4  351.68  4944.3  355.42  4995.7  352.06  5001.9  355.38
  5010.5  353.14  5031.3  356.38  5046.1  351.64  5066.9  354.84  5081.7  350.41
  5231.8  349.97  5232.0  349.47  5235.8  349.97  5763.3  363.75  6330.6  367.69
#Mann=3,-1,0
  3627.1    0.05       0  5231.8    0.03       0  5235.8    0.05       0
Bank Sta=5231.8,5235.8
Exp/Cntr=0.3,0.1

Type RM Length L Ch R = 1,2338,504,504,504
BEGIN DESCRIPTION:
Little Cottonwood Creek Trib 8 2.0
END DESCRIPTION:
XS GIS Cut Line= 3
      2662595.87      6854068.61      2662076.00      6855161.00
      2661830.25      6856167.54
#Sta/Elev= 30
  3790.5  366.75  4078.3  365.20  4106.6  365.71  4324.7  356.88  4498.2  355.21
  4526.4  353.43  4579.5  353.17  4623.8  350.66  4713.6  349.35  4736.4  348.05
  4963.5  345.87  4978.1  345.51  4986.2  344.22  4989.6  342.36  4990.0  341.86
  4993.8  342.36  5002.9  342.73  5018.5  348.29  5023.7  348.94  5031.2  348.55
  5051.8  345.06  5206.2  344.82  5309.1  347.99  5412.0  353.05  5482.0  354.97
  5528.9  358.17  5545.9  360.36  5576.7  361.64  5854.7  368.05  6036.4  368.70
#Mann=3,-1,0
  3790.5    0.05       0  4989.6    0.03       0  4993.8    0.05       0
Bank Sta=4989.6,4993.8
Exp/Cntr=0.3,0.1

Type RM Length L Ch R = 1,1834,754,754,754
BEGIN DESCRIPTION:
Mapping XS e54d85fc
END DESCRIPTION:
XS GIS Cut Line= 4
      2662261.69      6853849.83      2661636.67      6854978.33
      2661437.02      6855364.62      2661666.60      6856187.64
#Sta/Elev= 30
  3714.7  366.03  3910.4  365.76  4044.1  361.29  4087.6  360.70  4131.1  358.04
  4212.4  355.45  4271.9  355.06  4331.5  353.42  4358.9  351.51  4390.5  352.19
  4402.4  350.75  4493.4  347.19  4859.2  342.70  4998.9  342.82  5018.7  340.76
  5019.0  340.26  5022.9  340.76  5052.8  343.52  5186.8  341.61  5199.1  342.72
  5446.2  346.75  5685.0  356.98  5695.3  356.75  5726.5  358.76  5965.3  362.87
  5986.0  360.50  6017.5  360.53  6058.7  363.97  6204.1  367.01  6294.0  367.51
#Mann=3,-1,0
  3714.7    0.05       0  5018.7    0.04       0  5022.9    0.05       0
Bank Sta=5018.7,5022.9
Exp/Cntr=0.3,0.1

Type RM Length L Ch R = 1,1080,0,0,0
BEGIN DESCRIPTION:
Little Cottonwood Creek Trib 8 1.0
END DESCRIPTION:
XS GIS Cut Line= 4
      2662026.30      6853397.20      2661096.27      6854630.80
      2660908.03      6855196.15      2661619.12      6856515.00
#Sta/Elev= 30
  3455.1  367.52  3664.9  366.58  3708.6  367.78  3823.0  362.58  3850.2  359.64
  3885.7  359.22  3893.9  360.59  3985.8  358.55  4008.4  356.36  4129.1  356.90
  4149.9  353.77  4299.8  348.98  4322.7  349.66  4536.9  342.11  5002.7  342.08
  5010.8  341.84  5019.5  338.90  5019.8  338.40  5023.8  338.90  5031.8  341.01
  5053.3  342.12  5442.9  341.24  6041.7  344.38  6238.8  350.47  6293.1  350.12
  6328.5  352.20  6484.5  355.53  6615.9  361.90  6807.2  367.20  7094.2  368.93
#Mann=3,-1,0
  3455.1    0.05       0  5019.5    0.04       0  5023.8    0.05       0
Bank Sta=5019.5,5023.8
Exp/Cntr=0.3,0.1

Chan Stop Cuts=-1