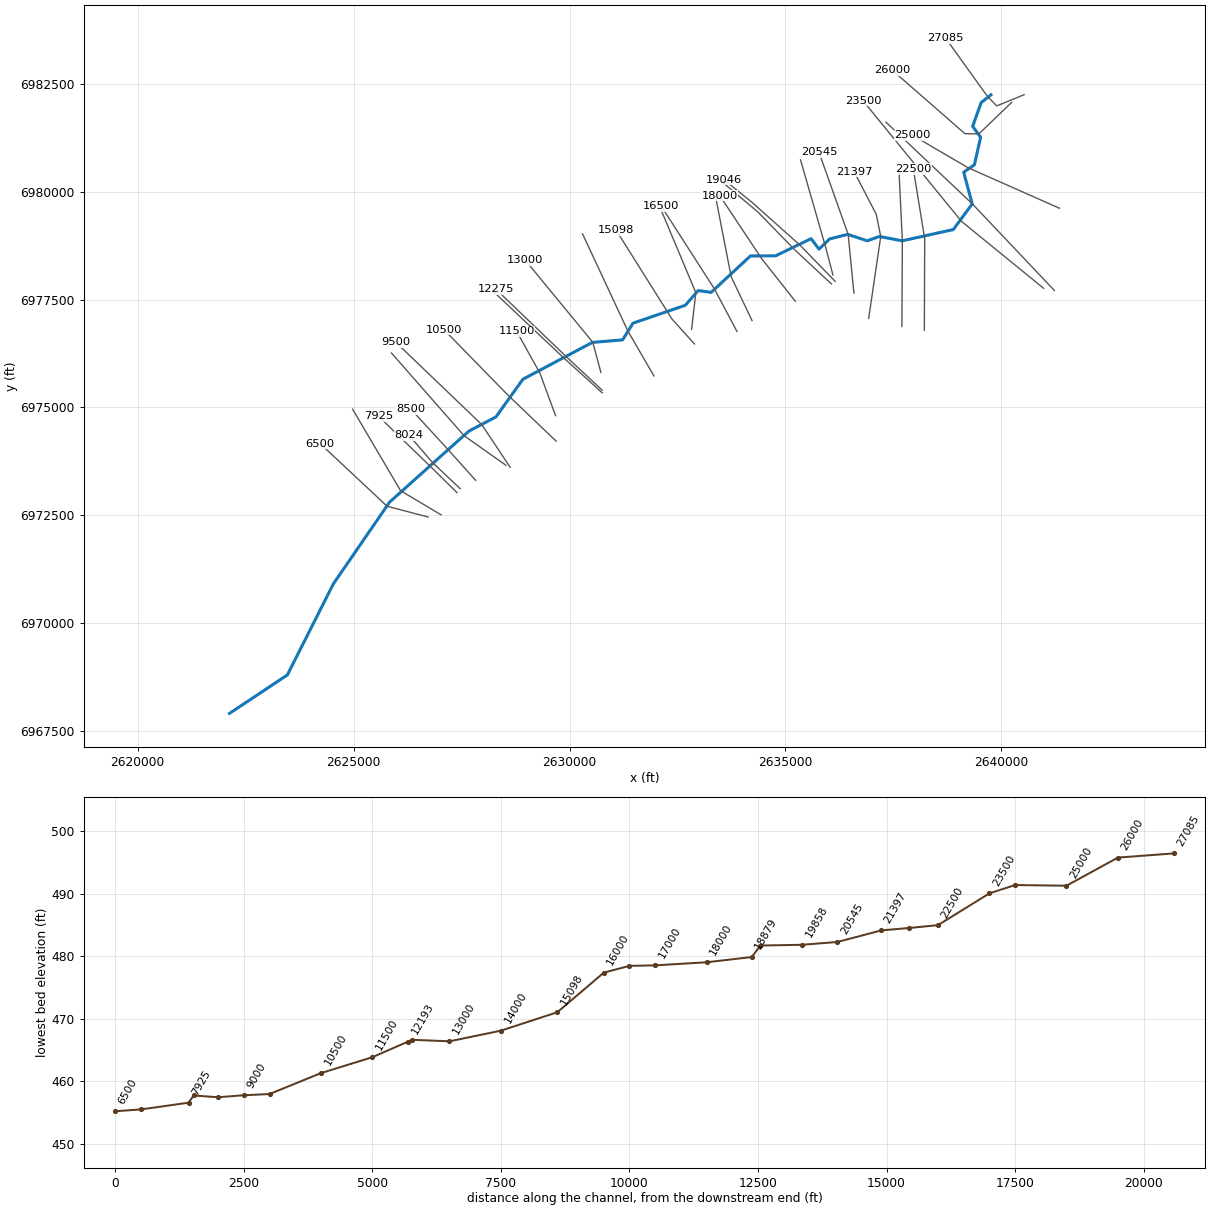
--- Little High Point Creek.prj (project) ---

Proj Title=Little High Point Creek Base Level Engineering
Current Plan=p01
Default Exp/Contr=0.3,0.1
English Units
Geom File=g01
Flow File=f01
Plan File=p01
BEGIN DESCRIPTION:
Little High Point Creek
END DESCRIPTION:

--- Little High Point Creek.p01 (plan) ---

Plan Title=Multiple Run
Short Identifier=Multiple
Geom File=g01
Flow File=f01
Subcritical Flow
K Sum by GR= 0
Std Step Tol= 0.01
Critical Tol= 0.01
Num of Std Step Trials= 20
Max Error Tol= 0.3
Flow Tol Ratio= 0.001
Split Flow NTrial= 30
Split Flow Tol= 0.02
Split Flow Ratio= 0.02
Log Output Level= 0
Friction Slope Method= 1
Unsteady Friction Slope Method= 2
Unsteady Bridges Friction Slope Method= 1
Parabolic Critical Depth
Global Vel Dist=  1 , 1 , 1
Global Log Level= 0
CheckData=True
Encroach Param= -1, 0, 0, 0
BEGIN DESCRIPTION:
Multiple Run
END DESCRIPTION:

--- Little High Point Creek.f01 (steady flow) ---

Flow Title=Multiple
Number of Profiles=7
Profile Names=10-year,25-year,50-year,1pct_min,100-year,1pct_plu,500-year
River Rch & RM= Little High Poin,Reach-1,27085
     401     521     614     359     717    1431     977
River Rch & RM= Little High Poin,Reach-1,25000
    1002    1373    1677    1015    2024    4039    2949
River Rch & RM= Little High Poin,Reach-1,22500
    1324    1838    2266    1381    2755    5497    4076
River Rch & RM= Little High Poin,Reach-1,19858
    1542    2148    2654    1621    3233    6452    4802
River Rch & RM= Little High Poin,Reach-1,16000
    1706    2389    2961    1813    3618    7218    5403
River Rch & RM= Little High Poin,Reach-1,12275
    1934    2722    3387    2081    4151    8283    6241
River Rch & RM= Little High Poin,Reach-1,10500
    2117    2986    3720    2287    4563    9104    6872
River Rch & RM= Little High Poin,Reach-1,6500
    2245    3168    3948    2427    4843    9664    7294
Boundary for River Rch & Prof#=Little High Poin,Reach-1,1
Up Type=0
Dn Type=3
Dn Slope=0.005
Boundary for River Rch & Prof#=Little High Poin,Reach-1,2
Up Type=0
Dn Type=3
Dn Slope=0.005
Boundary for River Rch & Prof#=Little High Poin,Reach-1,3
Up Type=0
Dn Type=3
Dn Slope=0.005
Boundary for River Rch & Prof#=Little High Poin,Reach-1,4
Up Type=0
Dn Type=3
Dn Slope=0.005
Boundary for River Rch & Prof#=Little High Poin,Reach-1,5
Up Type=0
Dn Type=3
Dn Slope=0.005
Boundary for River Rch & Prof#=Little High Poin,Reach-1,6
Up Type=0
Dn Type=3
Dn Slope=0.005
Boundary for River Rch & Prof#=Little High Poin,Reach-1,7
Up Type=0
Dn Type=3
Dn Slope=0.005

--- Little High Point Creek.g01 (geometry) ---

Geom Title=Existing Conditions

River Reach=Little High Poin,Reach-1
Reach XY= 30
      2639759.00      6982244.70      2639531.15      6982063.58
      2639333.79      6981514.03      2639518.75      6981260.70
      2639374.37      6980622.81      2639126.55      6980450.37
      2639323.75      6979716.95      2638885.71      6979121.70
      2637701.12      6978860.71      2637175.66      6978961.92
      2636891.39      6978861.08      2636441.27      6979010.62
      2636023.42      6978905.29      2635775.89      6978668.31
      2635591.47      6978911.01      2634769.96      6978512.62
      2634187.74      6978509.91      2633278.43      6977666.40
      2632977.47      6977707.46      2632678.68      6977366.42
      2631469.81      6976953.14      2631228.58      6976565.97
      2630527.55      6976507.25      2628919.52      6975653.31
      2628296.09      6974780.79      2627666.32      6974450.24
      2625831.62      6972805.38      2624531.48      6970913.44
      2623465.23      6968801.30      2622126.00      6967911.00

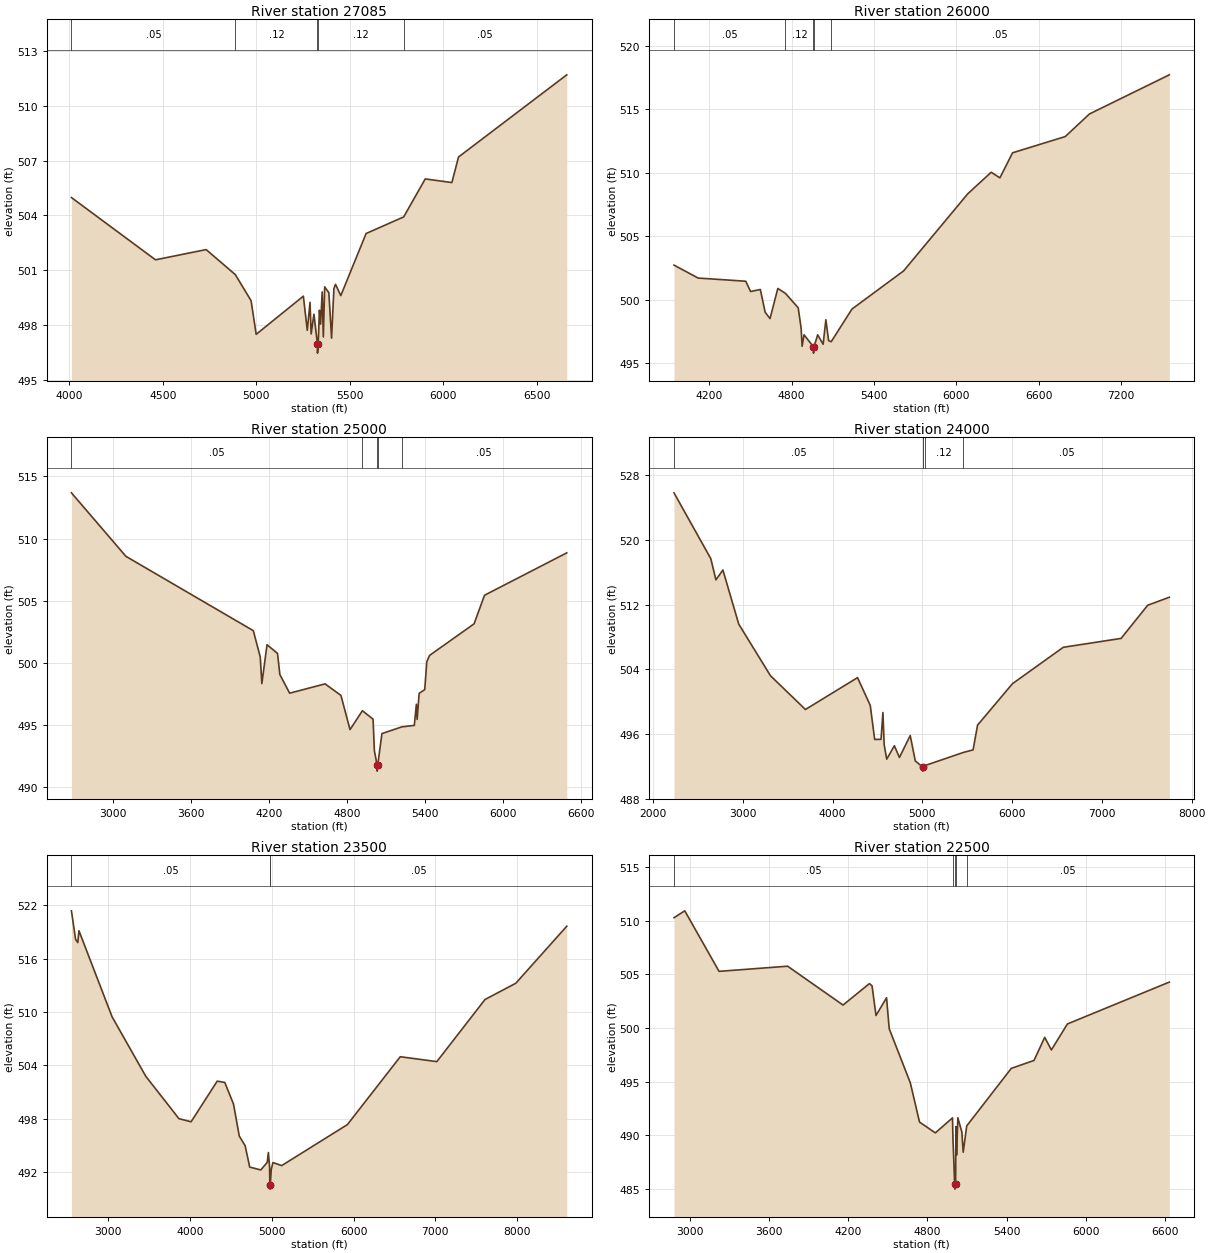
Type RM Length L Ch R = 1,27085,1085,1085,1085
BEGIN DESCRIPTION:
Little High Point Creek 53.0
END DESCRIPTION:
XS GIS Cut Line= 4
      2640526.29      6982246.55      2639891.29      6981987.16
      2639679.14      6982204.43      2638710.89      6983552.92
#Sta/Elev= 30
  4010.4  504.98  4460.2  501.57  4731.0  502.13  4887.1  500.76  4971.5  499.33
  4998.7  497.49  5251.1  499.58  5272.0  497.71  5286.7  499.24  5292.8  497.51
  5307.6  498.59  5326.5  496.96  5326.7  496.46  5330.5  496.96  5337.0  498.81
  5343.2  498.05  5351.8  499.81  5357.9  497.35  5365.1  500.09  5387.4  499.77
  5402.0  497.28  5414.4  499.99  5423.0  500.23  5451.3  499.61  5586.7  503.01
  5787.8  503.92  5903.1  506.00  6045.5  505.80  6081.1  507.20  6660.1  511.70
#Mann=5,-1,0
  4010.4    0.05       0  4887.1    0.12       0  5326.5    0.07       0
  5330.5    0.12       0  5787.8    0.05       0
Bank Sta=5326.5,5330.5
Exp/Cntr=0.3,0.1

Type RM Length L Ch R = 1,26000,1000,1000,1000
BEGIN DESCRIPTION:
Little High Point Creek 52.0
END DESCRIPTION:
XS GIS Cut Line= 4
      2640237.18      6982068.56      2639476.09      6981337.09
      2639153.88      6981344.63      2637476.03      6982810.97
#Sta/Elev= 30
  3944.4  502.72  4120.3  501.70  4466.9  501.45  4502.1  500.64  4572.9  500.80
  4608.4  499.00  4643.6  498.51  4700.2  500.88  4755.3  500.50  4848.7  499.36
  4870.0  497.75  4877.0  496.33  4891.1  497.23  4959.9  496.29  4960.1  495.79
  4963.9  496.29  4990.2  497.23  5030.1  496.49  5050.1  498.42  5070.1  496.77
  5088.9  496.69  5240.2  499.26  5615.7  502.26  6083.7  508.34  6253.6  510.03
  6317.2  509.59  6409.2  511.56  6792.7  512.84  6969.3  514.62  7550.6  517.70
#Mann=5,-1,0
  3944.4    0.05       0  4755.3    0.12       0  4959.9    0.07       0
  4963.9    0.12       0  5088.9    0.05       0
Bank Sta=4959.9,4963.9
Exp/Cntr=0.3,0.1

Type RM Length L Ch R = 1,25000,1000,1000,1000
BEGIN DESCRIPTION:
Little High Point Creek 50.0
END DESCRIPTION:
XS GIS Cut Line= 3
      2641343.57      6979616.16      2639224.86      6980555.73
      2637940.91      6981308.80
#Sta/Elev= 30
  2682.3  513.68  3101.0  508.57  4079.9  502.59  4133.2  500.48  4145.5  498.33
  4185.2  501.46  4266.0  500.76  4283.8  499.06  4359.1  497.56  4631.5  498.31
  4753.3  497.38  4823.1  494.63  4918.3  496.15  5000.0  495.47  5010.3  492.93
  5030.8  491.79  5031.6  491.29  5036.2  491.79  5068.2  494.31  5220.9  494.85
  5317.1  494.97  5332.8  496.67  5338.6  495.45  5354.3  497.55  5397.2  497.85
  5412.9  500.09  5434.4  500.60  5776.3  503.14  5856.6  505.44  6488.5  508.85
#Mann=5,-1,0
  2682.3    0.05       0  4918.3    0.12       0  5030.8    0.07       0
  5036.2    0.12       0  5220.9    0.05       0
Bank Sta=5030.8,5036.2
Exp/Cntr=0.3,0.1

Type RM Length L Ch R = 1,24000,500,500,500
BEGIN DESCRIPTION:
Little High Point Creek 48.0
END DESCRIPTION:
XS GIS Cut Line= 3
      2641226.01      6977710.99      2639324.44      6979719.94
      2637326.03      6981610.97
#Sta/Elev= 30
  2233.8  525.81  2644.2  517.66  2700.8  515.05  2778.5  516.27  2955.3  509.57
  3308.9  503.19  3698.0  499.02  4278.1  502.96  4419.7  499.54  4469.1  495.32
  4539.8  495.33  4560.9  498.65  4575.0  494.65  4603.4  492.88  4688.3  494.54
  4744.9  493.09  4865.1  495.80  4921.7  492.66  5003.9  491.90  5004.8  491.40
  5009.7  491.90  5025.0  492.07  5457.1  493.71  5565.4  494.03  5615.2  497.09
  6004.0  502.21  6569.9  506.71  7213.9  507.81  7510.8  511.91  7751.3  512.90
#Mann=5,-1,0
  2233.8    0.05       0  5003.9    0.05       0  5009.7    0.05       0
  5025.0    0.12       0  5457.1    0.05       0
Bank Sta=5003.9,5009.7
Exp/Cntr=0.3,0.1

Type RM Length L Ch R = 1,23500,1000,1000,1000
BEGIN DESCRIPTION:
Little High Point Creek 47.0
END DESCRIPTION:
XS GIS Cut Line= 3
      2640976.01      6977760.99      2639076.31      6979311.29
      2636795.29      6982106.88
#Sta/Elev= 30
  2548.0  521.38  2598.3  518.19  2625.6  517.80  2639.9  519.14  3045.6  509.45
  3457.7  502.76  3863.4  497.99  4012.0  497.64  4331.5  502.21  4424.1  502.07
  4531.1  499.63  4601.5  496.03  4673.3  494.94  4729.3  492.54  4865.0  492.22
  4943.3  493.07  4957.6  494.18  4972.0  492.59  4975.5  490.56  4976.5  490.06
  4981.3  490.56  4992.8  492.29  5013.7  493.05  5120.7  492.71  5924.1  497.32
  6571.1  504.96  7018.4  504.41  7607.9  511.40  7984.8  513.23  8608.1  519.65
#Mann=3,-1,0
  2548.0    0.05       0  4975.5    0.03       0  4981.3    0.05       0
Bank Sta=4975.5,4981.3
Exp/Cntr=0.3,0.1

Type RM Length L Ch R = 1,22500,571,571,571
BEGIN DESCRIPTION:
Little High Point Creek 45.0
END DESCRIPTION:
XS GIS Cut Line= 3
      2638215.50      6976789.27      2638223.63      6978910.55
      2637960.30      6980523.60
#Sta/Elev= 30
  2878.7  510.27  2960.4  510.91  3220.4  505.27  3740.4  505.75  4160.4  502.13
  4360.4  504.13  4380.4  503.92  4410.4  501.16  4490.4  502.81  4510.4  499.93
  4670.4  494.89  4740.4  491.23  4860.4  490.22  4990.4  491.62  4994.1  489.57
  5006.8  485.48  5008.0  484.98  5014.3  485.48  5016.0  490.81  5021.1  488.15
  5030.9  491.63  5061.2  490.30  5071.4  488.42  5098.2  490.87  5436.1  496.23
  5608.4  496.97  5689.5  499.12  5740.1  497.95  5861.7  500.37  6634.4  504.27
#Mann=5,-1,0
  2878.7    0.05       0  4994.1    0.12       0  5006.8    0.07       0
  5014.3    0.12       0  5098.2    0.05       0
Bank Sta=5006.8,5014.3
Exp/Cntr=0.3,0.1

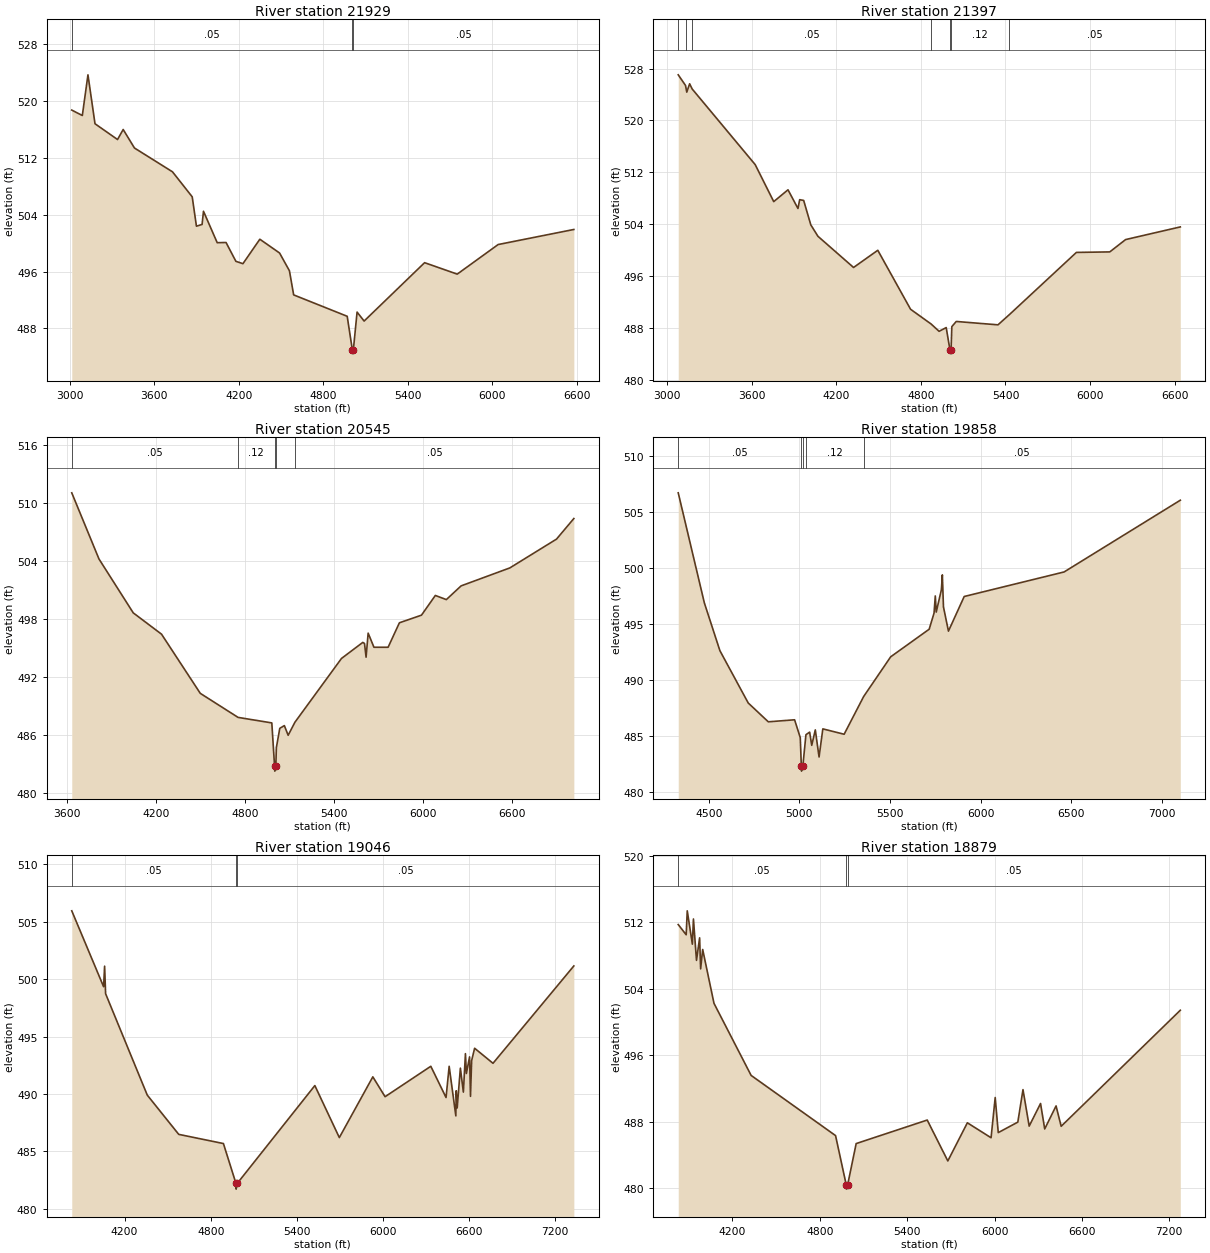
Type RM Length L Ch R = 1,21929,532,532,532
BEGIN DESCRIPTION:
Little High Point Creek 44.0
END DESCRIPTION:
XS GIS Cut Line= 3
      2637695.54      6976876.09      2637706.02      6978860.96
      2637630.51      6980437.76
#Sta/Elev= 30
  3015.1  518.70  3090.0  517.94  3130.0  523.66  3180.0  516.78  3340.0  514.56
  3380.0  515.97  3460.0  513.37  3730.0  510.02  3870.0  506.50  3900.0  502.37
  3940.0  502.62  3950.0  504.47  4047.4  500.05  4110.0  500.08  4180.0  497.43
  4230.0  497.10  4350.0  500.54  4490.0  498.60  4560.0  496.10  4590.0  492.71
  4970.0  489.70  5006.2  485.02  5007.3  484.52  5013.9  485.02  5040.1  490.29
  5090.1  489.03  5519.3  497.24  5750.9  495.63  6041.2  499.79  6578.6  501.91
#Mann=3,-1,0
  3015.1    0.05       0  5006.2    0.03       0  5013.9    0.05       0
Bank Sta=5006.2,5013.9
Exp/Cntr=0.3,0.1

Type RM Length L Ch R = 1,21397,852,852,852
BEGIN DESCRIPTION:
Little High Point Creek 43.0
END DESCRIPTION:
XS GIS Cut Line= 4
      2636926.00      6977061.03      2637205.75      6978961.15
      2637101.35      6979474.94      2636588.76      6980465.48
#Sta/Elev= 30
  3079.4  527.03  3131.1  525.39  3140.0  524.36  3160.2  525.65  3178.2  524.85
  3625.2  513.19  3756.6  507.49  3857.7  509.31  3928.4  506.43  3940.6  507.79
  3968.9  507.67  4019.4  503.91  4069.9  502.15  4322.6  497.34  4494.5  499.99
  4726.9  490.90  4873.0  488.62  4929.1  487.50  4979.6  488.08  5006.2  484.64
  5007.4  484.14  5014.0  484.64  5019.5  488.23  5050.9  489.02  5346.8  488.50
  5427.8  490.08  5902.7  499.66  6139.5  499.74  6251.7  501.64  6639.6  503.59
#Mann=7,-1,0
  3079.4    0.05       0  3131.1   0.075       0  3178.2    0.05       0
  4873.0    0.12       0  5006.2    0.07       0  5014.0    0.12       0
  5427.8    0.05       0
Bank Sta=5006.2,5014
Exp/Cntr=0.3,0.1

Type RM Length L Ch R = 1,20545,687,687,687
BEGIN DESCRIPTION:
Little High Point Creek 41.0
END DESCRIPTION:
XS GIS Cut Line= 3
      2636584.43      6977648.62      2636451.00      6979011.40
      2635775.99      6980911.04
#Sta/Elev= 30
  3630.7  511.09  3814.0  504.25  4045.1  498.67  4236.0  496.46  4497.2  490.34
  4752.1  487.85  4979.5  487.28  4998.2  482.79  4999.5  482.29  5006.6  482.79
  5010.2  484.72  5033.3  486.72  5064.1  487.00  5089.7  486.00  5135.4  487.35
  5449.3  493.95  5592.9  495.61  5604.5  495.50  5615.1  494.08  5629.1  496.57
  5668.2  495.11  5763.7  495.11  5839.8  497.64  5988.7  498.43  6082.1  500.47
  6156.3  500.04  6255.8  501.46  6584.5  503.32  6899.2  506.30  7016.0  508.43
#Mann=5,-1,0
  3630.7    0.05       0  4752.1    0.12       0  4998.2    0.07       0
  5006.6    0.12       0  5135.4    0.05       0
Bank Sta=4998.2,5006.6
Exp/Cntr=0.3,0.1

Type RM Length L Ch R = 1,19858,812,812,812
BEGIN DESCRIPTION:
Little High Point Creek 40.0
END DESCRIPTION:
XS GIS Cut Line= 3
      2636098.30      6978069.67      2635928.71      6978716.40
      2635347.85      6980737.49
#Sta/Elev= 30
  4331.4  506.67  4475.4  496.86  4561.3  492.59  4717.7  487.92  4828.6  486.24
  4973.7  486.42  5005.0  484.83  5010.8  482.34  5012.0  481.84  5019.6  482.34
  5036.3  485.09  5056.8  485.32  5068.3  484.14  5088.0  485.52  5108.8  483.10
  5129.6  485.61  5247.2  485.13  5355.1  488.50  5504.2  492.04  5716.6  494.50
  5743.5  495.94  5750.4  497.47  5755.6  496.03  5784.1  498.03  5789.3  499.35
  5795.5  496.49  5823.0  494.33  5910.0  497.42  6461.5  499.61  7102.9  506.01
#Mann=5,-1,0
  4331.4    0.05       0  5010.8    0.03       0  5019.6    0.05       0
  5036.3    0.12       0  5355.1    0.05       0
Bank Sta=5010.8,5019.6
Exp/Cntr=0.3,0.1

Type RM Length L Ch R = 1,19046,167,167,167
BEGIN DESCRIPTION:
Mapping XS 186e915c
END DESCRIPTION:
XS GIS Cut Line= 4
      2636150.43      6977922.02      2635336.64      6978759.45
      2634214.64      6979762.33      2633572.31      6980278.80
#Sta/Elev= 30
  3832.3  505.96  4054.0  499.35  4061.0  501.14  4068.0  498.74  4358.1  489.91
  4577.3  486.49  4888.5  485.69  4975.8  482.22  4977.1  481.72  4984.9  482.22
  5525.3  490.74  5695.8  486.21  5929.1  491.50  6014.4  489.77  6332.9  492.42
  6439.0  489.70  6460.7  492.42  6507.2  488.10  6510.1  490.29  6516.6  488.79
  6538.9  492.26  6559.7  490.17  6574.1  493.52  6580.6  491.79  6602.9  493.24
  6609.3  489.80  6617.3  492.92  6638.1  493.99  6766.1  492.68  7329.1  501.16
#Mann=3,-1,0
  3832.3    0.05       0  4975.8    0.03       0  4984.9    0.05       0
Bank Sta=4975.8,4984.9
Exp/Cntr=0.3,0.1

Type RM Length L Ch R = 1,18879,879,879,879
BEGIN DESCRIPTION:
Mapping XS 1f9cdd8d
END DESCRIPTION:
XS GIS Cut Line= 4
      2636063.62      6977861.27      2635206.02      6978660.96
      2634362.21      6979527.96      2633546.24      6980213.72
#Sta/Elev= 30
  3827.4  511.71  3882.0  510.48  3889.3  513.36  3924.5  509.35  3931.8  512.38
  3952.8  507.40  3974.3  510.11  3981.2  506.38  3995.3  508.71  4073.0  502.23
  4328.0  493.56  4907.9  486.32  4981.5  480.38  4982.9  479.88  4990.7  480.38
  5049.5  485.36  5537.5  488.19  5679.0  483.27  5813.2  487.86  5976.0  486.06
  6004.3  490.90  6025.4  486.68  6159.7  487.94  6195.2  491.85  6237.7  487.46
  6315.8  490.18  6344.4  487.12  6422.4  489.89  6457.5  487.44  7275.7  501.40
#Mann=3,-1,0
  3827.4    0.05       0  4981.5    0.03       0  4990.7    0.05       0
Bank Sta=4981.5,4990.7
Exp/Cntr=0.3,0.1

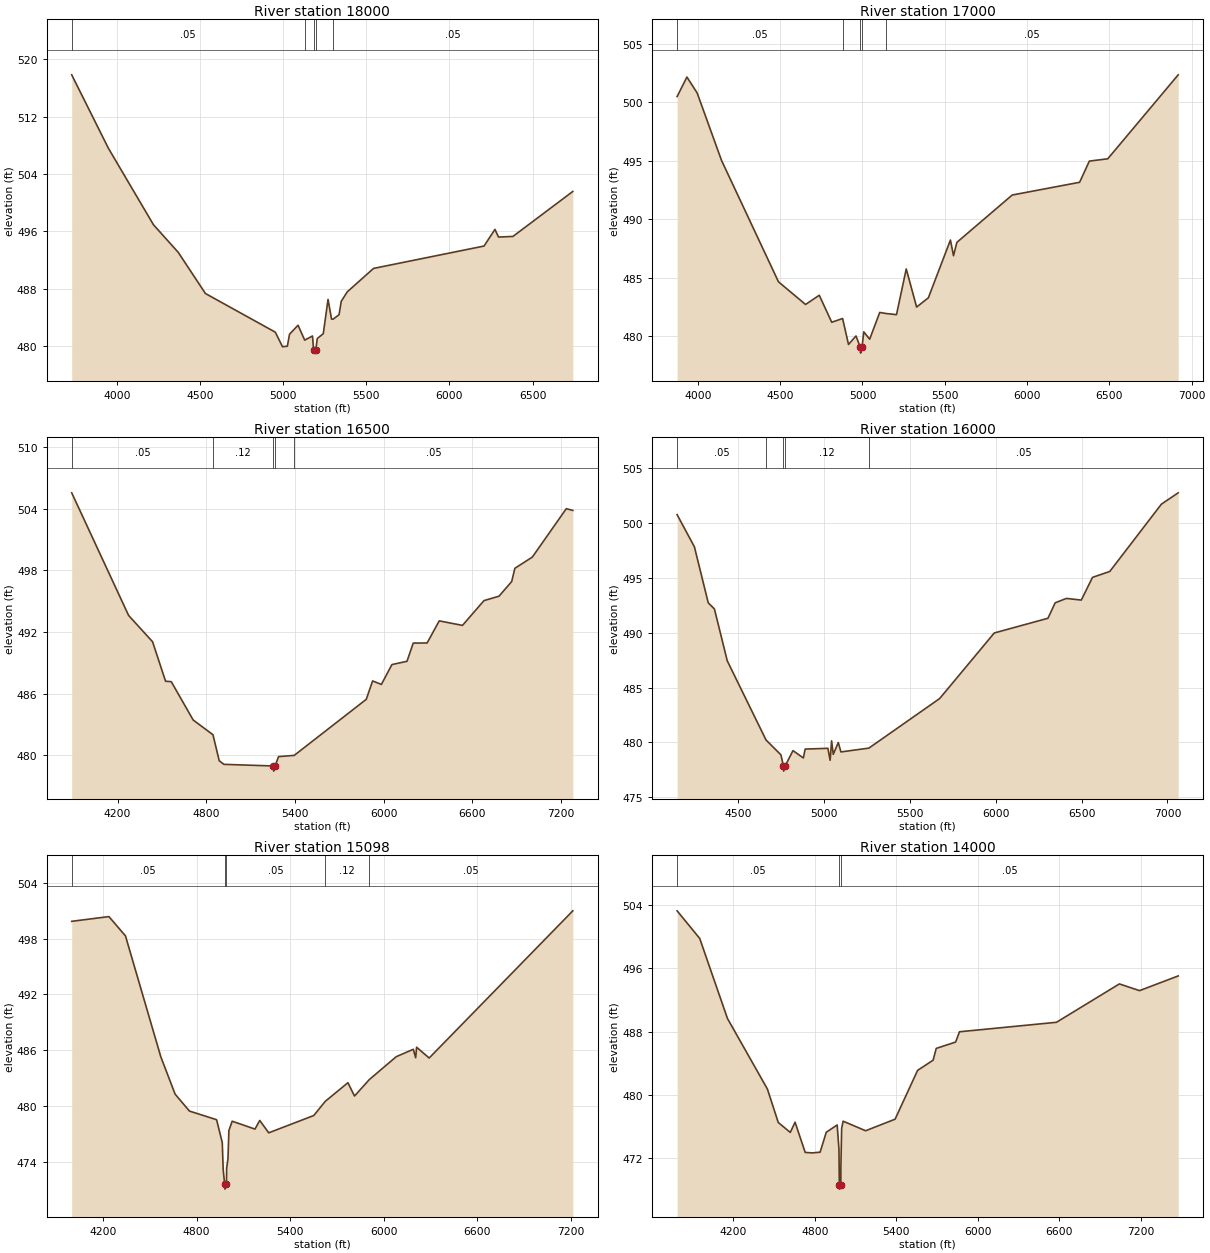
Type RM Length L Ch R = 1,18000,1000,1000,1000
BEGIN DESCRIPTION:
Little High Point Creek 36.0
END DESCRIPTION:
XS GIS Cut Line= 3
      2635225.97      6977461.03      2634439.43      6978459.93
      2633475.99      6979911.02
#Sta/Elev= 30
  3728.6  517.84  3949.0  507.61  4220.1  496.94  4369.2  493.09  4532.7  487.35
  4952.9  481.96  4996.2  479.93  5025.3  480.01  5038.3  481.67  5089.4  482.93
  5129.6  480.85  5176.6  481.43  5182.6  479.60  5187.1  479.54  5188.4  479.04
  5196.3  479.54  5205.3  481.08  5241.3  481.75  5269.9  486.53  5290.9  483.79
  5300.1  483.77  5336.0  484.39  5349.4  486.27  5385.4  487.58  5543.5  490.85
  6208.0  493.97  6273.6  496.29  6295.2  495.22  6381.7  495.31  6741.8  501.58
#Mann=5,-1,0
  3728.6    0.05       0  5129.6    0.12       0  5187.1    0.03       0
  5196.3    0.12       0  5300.1    0.05       0
Bank Sta=5187.1,5196.3
Exp/Cntr=0.3,0.1

Type RM Length L Ch R = 1,17000,500,500,500
BEGIN DESCRIPTION:
Little High Point Creek 34.0
END DESCRIPTION:
XS GIS Cut Line= 3
      2634226.01      6977010.98      2633742.47      6978027.98
      2633375.99      6979911.05
#Sta/Elev= 30
  3873.9  500.49  3933.5  502.16  3995.7  500.80  4143.5  495.04  4489.8  484.65
  4654.3  482.71  4737.6  483.50  4813.3  481.19  4879.4  481.51  4915.3  479.29
  4960.7  480.02  4987.2  479.05  4988.6  478.55  4997.4  479.05  5007.9  480.37
  5043.8  479.74  5105.0  482.03  5142.4  481.94  5206.8  481.84  5266.1  485.75
  5329.1  482.49  5400.4  483.28  5534.5  488.22  5553.2  486.88  5573.6  488.02
  5909.8  492.07  6319.4  493.16  6378.4  494.97  6490.5  495.17  6918.4  502.35
#Mann=5,-1,0
  3873.9    0.05       0  4879.4    0.12       0  4987.2    0.07       0
  4997.4    0.12       0  5142.4    0.05       0
Bank Sta=4987.2,4997.4
Exp/Cntr=0.3,0.1

Type RM Length L Ch R = 1,16500,500,500,500
BEGIN DESCRIPTION:
Little High Point Creek 33.0
END DESCRIPTION:
XS GIS Cut Line= 3
      2633875.99      6976761.02      2633356.88      6977741.81
      2632125.99      6979661.01
#Sta/Elev= 30
  3890.3  505.53  4275.0  493.61  4437.2  491.05  4525.2  487.21  4563.6  487.17
  4711.9  483.44  4845.8  482.01  4888.0  479.48  4919.9  479.13  5254.9  478.97
  5256.4  478.47  5265.8  478.97  5289.4  479.88  5395.4  480.00  5882.8  485.45
  5925.7  487.24  5985.1  486.90  6056.4  488.83  6158.3  489.15  6200.6  490.92
  6294.4  490.93  6376.4  493.08  6533.6  492.64  6679.0  495.05  6781.0  495.48
  6866.7  496.91  6888.0  498.19  7006.1  499.28  7236.0  503.99  7280.0  503.82
#Mann=5,-1,0
  3890.3    0.05       0  4845.8    0.12       0  5254.9    0.07       0
  5265.8    0.12       0  5395.4    0.05       0
Bank Sta=5254.9,5265.8
Exp/Cntr=0.3,0.1

Type RM Length L Ch R = 1,16000,902,902,902
BEGIN DESCRIPTION:
Little High Point Creek 32.0
END DESCRIPTION:
XS GIS Cut Line= 3
      2632826.00      6976811.03      2632923.99      6977658.98
      2632126.01      6979560.97
#Sta/Elev= 30
  4146.4  500.77  4247.0  497.84  4327.6  492.73  4363.5  492.17  4438.3  487.44
  4663.9  480.22  4750.4  478.87  4765.0  477.88  4766.5  477.38  4775.9  477.88
  4820.8  479.25  4881.2  478.58  4891.6  479.39  5023.9  479.46  5036.9  478.37
  5045.6  480.14  5055.2  478.91  5084.4  479.99  5099.8  479.13  5262.7  479.48
  5674.4  484.00  5992.2  489.98  6304.5  491.32  6346.6  492.73  6412.0  493.13
  6498.7  492.98  6563.9  495.05  6664.4  495.59  6965.0  501.73  7062.6  502.76
#Mann=5,-1,0
  4146.4    0.05       0  4663.9    0.12       0  4765.0    0.07       0
  4775.9    0.12       0  5262.7    0.05       0
Bank Sta=4765,4775.9
Exp/Cntr=0.3,0.1

Type RM Length L Ch R = 1,15098,1098,1098,1098
BEGIN DESCRIPTION:
Little High Point Creek 30.0
END DESCRIPTION:
XS GIS Cut Line= 3
      2632892.16      6976470.31      2632371.76      6977048.40
      2631075.98      6979111.03
#Sta/Elev= 30
  3999.2  499.87  4237.8  500.38  4344.0  498.30  4570.4  485.30  4662.4  481.27
  4754.3  479.45  4928.3  478.52  4964.8  476.05  4970.7  473.13  4980.4  471.55
  4982.0  471.05  4991.5  471.55  4992.7  473.31  5001.3  474.32  5007.2  477.36
  5028.4  478.36  5174.5  477.51  5205.1  478.44  5262.8  477.11  5551.4  478.97
  5625.4  480.50  5770.5  482.50  5812.9  481.07  5907.8  482.84  6080.3  485.30
  6189.8  486.10  6205.1  485.19  6211.0  486.32  6291.7  485.16  7212.9  501.00
#Mann=5,-1,0
  3999.2    0.05       0  4980.4    0.03       0  4991.5    0.05       0
  5625.4    0.12       0  5907.8    0.05       0
Bank Sta=4980.4,4991.5
Exp/Cntr=0.3,0.1

Type RM Length L Ch R = 1,14000,1000,1000,1000
BEGIN DESCRIPTION:
Little High Point Creek 28.0
END DESCRIPTION:
XS GIS Cut Line= 3
      2631953.34      6975730.24      2631345.47      6976780.05
      2630300.34      6979023.12
#Sta/Elev= 30
  3786.9  503.28  3953.3  499.79  4157.5  489.67  4451.2  480.76  4531.5  476.52
  4619.8  475.27  4655.0  476.56  4729.5  472.74  4781.5  472.68  4839.3  472.77
  4884.5  475.29  4964.8  476.21  4978.0  473.14  4980.8  468.60  4982.3  468.10
  4992.0  468.60  4992.1  470.79  4997.7  475.75  5008.6  476.69  5174.2  475.48
  5391.1  476.94  5556.7  483.11  5671.0  484.40  5693.9  485.89  5836.6  486.69
  5865.0  487.99  6578.7  489.19  7041.7  494.04  7189.9  493.19  7474.6  495.05
#Mann=3,-1,0
  3786.9    0.05       0  4980.8    0.03       0  4992.0    0.05       0
Bank Sta=4980.8,4992
Exp/Cntr=0.3,0.1

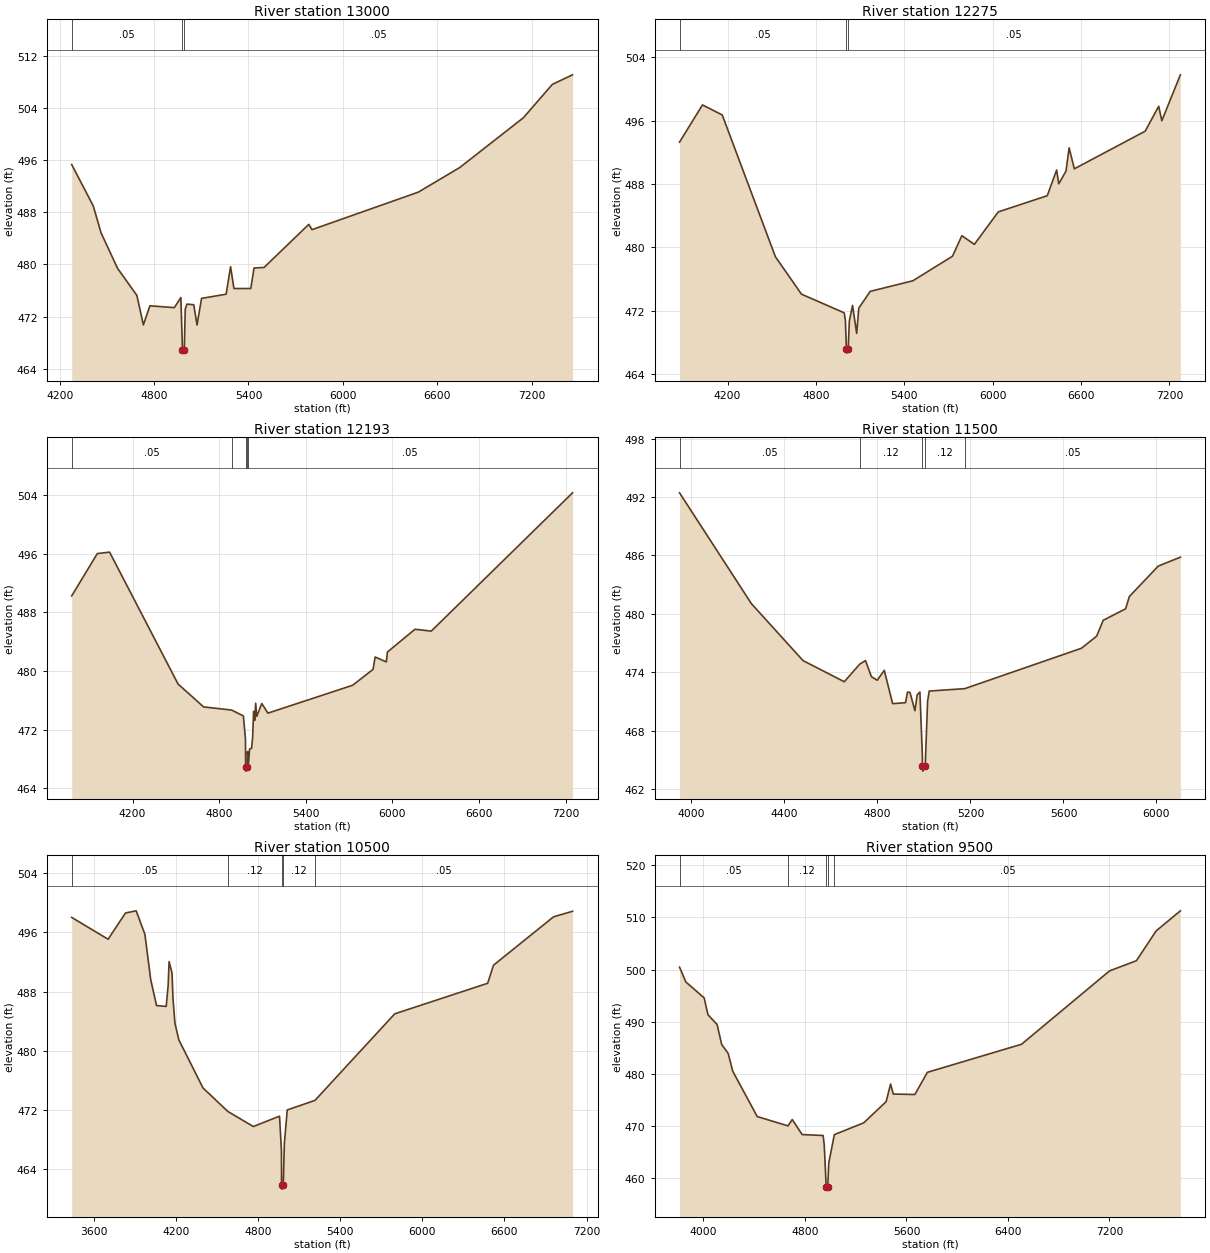
Type RM Length L Ch R = 1,13000,725,725,725
BEGIN DESCRIPTION:
Little High Point Creek 26.0
END DESCRIPTION:
XS GIS Cut Line= 3
      2630726.00      6975811.01      2630537.54      6976509.95
      2628975.98      6978411.03
#Sta/Elev= 30
  4276.1  495.33  4413.2  488.98  4462.5  484.86  4567.7  479.40  4690.4  475.26
  4731.8  470.73  4773.2  473.66  4928.6  473.38  4970.0  474.93  4980.4  466.90
  4982.0  466.40  4991.8  466.90  4998.0  473.18  5009.1  473.92  5052.1  473.82
  5072.9  470.72  5101.6  474.80  5258.0  475.44  5286.1  479.66  5307.6  476.31
  5414.5  476.31  5435.3  479.46  5499.1  479.54  5783.3  486.15  5804.1  485.34
  6479.3  491.09  6742.6  494.86  7148.0  502.51  7331.7  507.62  7460.2  509.09
#Mann=3,-1,0
  4276.1    0.05       0  4980.4    0.03       0  4991.8    0.05       0
Bank Sta=4980.4,4991.8
Exp/Cntr=0.3,0.1

Type RM Length L Ch R = 1,12275,82,82,82
BEGIN DESCRIPTION:
Mapping XS f561f02a
END DESCRIPTION:
XS GIS Cut Line= 3
      2630755.44      6975400.35      2629932.18      6976168.83
      2628290.56      6977743.71
#Sta/Elev= 30
  3873.8  493.29  4029.5  497.99  4163.8  496.72  4524.9  478.81  4701.7  474.09
  4991.9  471.73  5000.0  470.81  5007.1  467.14  5008.7  466.64  5018.8  467.14
  5027.1  470.73  5048.5  472.66  5076.8  469.13  5090.9  472.32  5168.6  474.44
  5458.5  475.78  5727.4  478.88  5791.0  481.47  5875.9  480.38  6038.5  484.48
  6370.9  486.52  6434.7  489.77  6448.8  488.02  6498.2  489.63  6519.3  492.56
  6554.8  489.92  7035.7  494.67  7127.8  497.82  7148.9  495.99  7274.9  501.79
#Mann=3,-1,0
  3873.8    0.05       0  5007.1    0.03       0  5018.8    0.05       0
Bank Sta=5007.1,5018.8
Exp/Cntr=0.3,0.1

Type RM Length L Ch R = 1,12193,693,693,693
BEGIN DESCRIPTION:
Mapping XS 847c5530
END DESCRIPTION:
XS GIS Cut Line= 3
      2630755.42      6975339.60      2629851.19      6976160.99
      2628216.38      6977705.03
#Sta/Elev= 30
  3778.4  490.23  3955.8  495.99  4040.9  496.19  4515.3  478.22  4692.3  475.10
  4886.7  474.67  4968.0  473.87  4982.2  470.78  4983.8  466.85  4985.4  466.35
  4995.6  466.85  4996.7  469.02  5003.8  467.43  5010.7  469.35  5024.8  469.46
  5032.1  470.94  5039.0  474.49  5046.3  473.26  5053.1  475.61  5060.4  473.81
  5095.6  475.56  5138.1  474.25  5725.1  478.05  5866.7  480.22  5880.9  481.90
  5958.5  481.23  5965.8  482.57  6156.8  485.68  6270.0  485.43  7248.7  504.27
#Mann=5,-1,0
  3778.4    0.05       0  4886.7    0.12       0  4983.8    0.03       0
  4995.6    0.12       0  4996.7    0.05       0
Bank Sta=4983.8,4995.6
Exp/Cntr=0.3,0.1

Type RM Length L Ch R = 1,11500,1000,1000,1000
BEGIN DESCRIPTION:
Little High Point Creek 23.0
END DESCRIPTION:
XS GIS Cut Line= 3
      2629675.99      6974811.02      2629312.40      6975797.55
      2628776.00      6976761.00
#Sta/Elev= 30
  3948.6  492.43  4257.6  481.05  4479.8  475.20  4657.2  473.03  4723.7  474.84
  4748.5  475.20  4773.6  473.56  4798.7  473.18  4829.2  474.20  4865.1  470.78
  4920.5  470.88  4929.1  471.96  4939.7  471.94  4961.0  470.05  4970.7  471.68
  4982.4  471.97  4993.0  465.44  4993.2  464.35  4994.8  463.85  5005.2  464.35
  5015.4  471.00  5022.3  472.07  5175.2  472.32  5677.4  476.47  5742.6  477.71
  5770.8  479.34  5867.2  480.52  5883.2  481.78  6007.8  484.91  6102.7  485.82
#Mann=5,-1,0
  3948.6    0.05       0  4723.7    0.12       0  4993.2    0.07       0
  5005.2    0.12       0  5175.2    0.05       0
Bank Sta=4993.2,5005.2
Exp/Cntr=0.3,0.1

Type RM Length L Ch R = 1,10500,1000,1000,1000
BEGIN DESCRIPTION:
Little High Point Creek 21.0
END DESCRIPTION:
XS GIS Cut Line= 3
      2629689.17      6974218.44      2628561.60      6975297.06
      2627096.23      6976797.38
#Sta/Elev= 30
  3439.6  498.03  3705.5  495.08  3832.5  498.63  3910.5  498.92  3974.1  495.75
  4016.5  489.63  4059.0  486.12  4129.7  486.00  4143.9  488.81  4150.8  492.06
  4172.2  490.53  4179.1  487.16  4193.3  483.75  4221.6  481.50  4398.6  474.98
  4579.6  471.81  4766.3  469.77  4957.2  471.17  4971.3  466.54  4972.5  461.81
  4974.2  461.31  4984.7  461.81  4992.7  467.52  5013.8  472.01  5216.1  473.30
  5798.8  485.00  6477.6  489.13  6520.0  491.57  6958.5  498.11  7097.2  498.86
#Mann=5,-1,0
  3439.6    0.05       0  4579.6    0.12       0  4972.5    0.07       0
  4984.7    0.12       0  5216.1    0.05       0
Bank Sta=4972.5,4984.7
Exp/Cntr=0.3,0.1

Type RM Length L Ch R = 1,9500,500,500,500
BEGIN DESCRIPTION:
Little High Point Creek 19.0
END DESCRIPTION:
XS GIS Cut Line= 3
      2628626.02      6973610.97      2627967.97      6974601.04
      2625976.00      6976511.00
#Sta/Elev= 30
  3811.2  500.47  3860.8  497.64  4005.1  494.59  4035.2  491.37  4107.4  489.48
  4143.4  485.67  4194.6  483.95  4230.6  480.54  4423.6  471.86  4666.6  470.07
  4699.6  471.29  4777.8  468.41  4943.1  468.23  4951.9  466.45  4967.1  458.46
  4968.8  457.96  4979.4  458.46  4987.9  463.02  5031.8  468.40  5263.1  470.65
  5439.9  474.71  5475.1  478.08  5496.5  476.17  5666.3  476.08  5765.1  480.33
  6507.9  485.71  7201.0  499.75  7413.3  501.71  7568.6  507.41  7759.7  511.26
#Mann=5,-1,0
  3811.2    0.05       0  4666.6    0.12       0  4967.1    0.07       0
  4979.4    0.12       0  5031.8    0.05       0
Bank Sta=4967.1,4979.4
Exp/Cntr=0.3,0.1

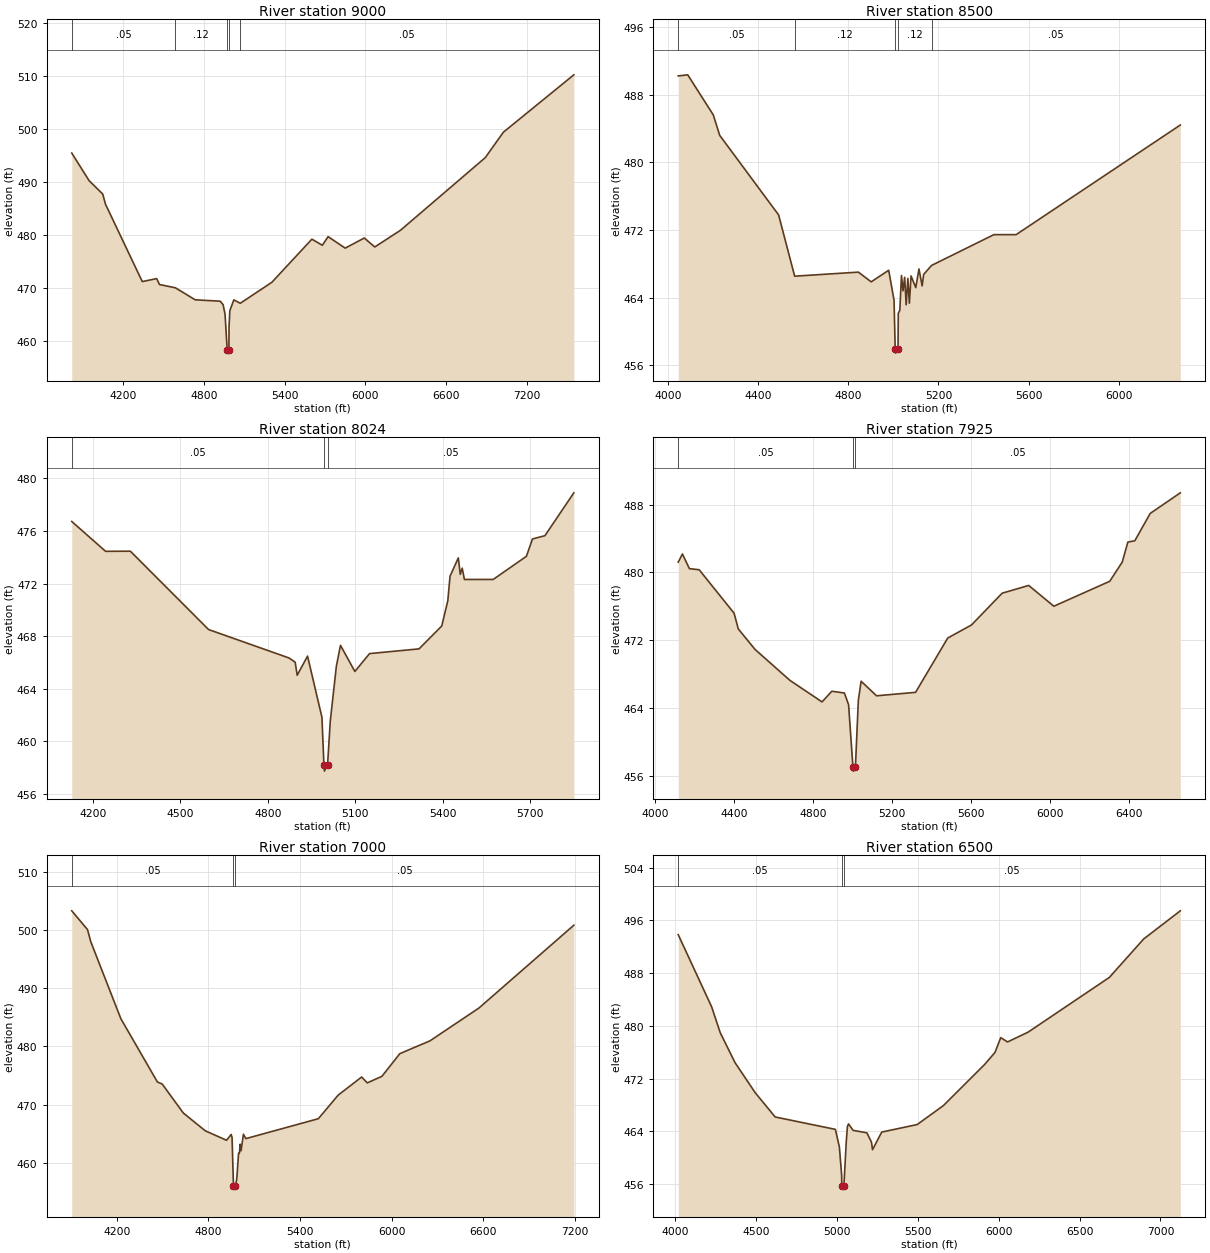
Type RM Length L Ch R = 1,9000,500,500,500
BEGIN DESCRIPTION:
Little High Point Creek 18.0
END DESCRIPTION:
XS GIS Cut Line= 3
      2628525.98      6973661.02      2627558.82      6974343.83
      2625875.98      6976261.02
#Sta/Elev= 30
  3816.1  495.52  3945.4  490.30  4046.3  487.79  4067.2  485.86  4340.6  471.27
  4447.7  471.83  4468.6  470.72  4587.5  470.09  4734.2  467.83  4920.5  467.57
  4942.2  466.90  4956.2  465.13  4972.7  458.27  4974.5  457.77  4985.2  458.27
  4985.8  462.65  4991.9  465.77  5021.6  467.82  5069.7  467.18  5304.4  471.13
  5602.4  479.27  5680.2  478.12  5722.9  479.75  5850.0  477.58  5992.4  479.49
  6070.2  477.80  6260.9  480.94  6891.9  494.65  7026.7  499.45  7551.0  510.28
#Mann=5,-1,0
  3816.1    0.05       0  4587.5    0.12       0  4972.7    0.07       0
  4985.2    0.12       0  5069.7    0.05       0
Bank Sta=4972.7,4985.2
Exp/Cntr=0.3,0.1

Type RM Length L Ch R = 1,8500,476,476,476
BEGIN DESCRIPTION:
Little High Point Creek 17.0
END DESCRIPTION:
XS GIS Cut Line= 3
      2627825.97      6973311.03      2627187.25      6974022.21
      2626326.00      6974961.00
#Sta/Elev= 30
  4044.1  490.20  4086.3  490.33  4199.9  485.59  4228.3  483.18  4489.9  473.78
  4561.2  466.54  4844.3  467.02  4901.1  465.87  4978.8  467.24  5002.6  463.70
  5007.7  457.95  5009.5  457.45  5020.2  457.95  5021.4  462.15  5028.2  462.51
  5035.6  466.62  5042.3  464.81  5049.7  466.41  5056.5  463.16  5063.9  466.28
  5070.7  463.35  5078.1  466.57  5099.1  465.19  5113.3  467.40  5127.4  465.40
  5134.2  466.75  5169.2  467.81  5446.2  471.45  5544.9  471.45  6274.0  484.40
#Mann=5,-1,0
  4044.1    0.05       0  4561.2    0.12       0  5007.7    0.07       0
  5020.2    0.12       0  5169.2    0.05       0
Bank Sta=5007.7,5020.2
Exp/Cntr=0.3,0.1

Type RM Length L Ch R = 1,8024,99,99,99
BEGIN DESCRIPTION:
Little High Point Creek 16.0
END DESCRIPTION:
XS GIS Cut Line= 3
      2627467.05      6973117.65      2626832.49      6973717.49
      2626275.97      6974361.03
#Sta/Elev= 30
  4126.8  476.72  4243.0  474.45  4328.0  474.46  4596.6  468.50  4872.5  466.34
  4893.9  466.02  4900.8  465.02  4936.4  466.48  4985.8  461.83  4992.6  458.23
  4994.4  457.73  5005.2  458.23  5014.4  461.52  5035.3  465.70  5049.5  467.30
  5098.9  465.31  5149.3  466.67  5319.3  467.03  5397.2  468.77  5418.1  470.70
  5425.7  472.56  5454.1  473.95  5460.8  472.70  5467.4  473.17  5475.1  472.31
  5573.8  472.31  5687.9  474.07  5708.7  475.39  5751.5  475.64  5850.8  478.90
#Mann=3,-1,0
  4126.8    0.05       0  4992.6    0.03       0  5005.2    0.05       0
Bank Sta=4992.6,5005.2
Exp/Cntr=0.3,0.1

Type RM Length L Ch R = 1,7925,925,925,925
BEGIN DESCRIPTION:
Little High Point Creek 15.0
END DESCRIPTION:
XS GIS Cut Line= 3
      2627392.40      6973027.37      2626762.68      6973647.64
      2625570.09      6974800.76
#Sta/Elev= 30
  4116.1  481.22  4137.4  482.18  4172.7  480.45  4222.2  480.32  4399.0  475.20
  4420.1  473.35  4505.0  470.93  4681.8  467.28  4844.4  464.74  4894.0  466.00
  4957.6  465.79  4978.8  464.42  5000.9  457.08  5002.6  456.58  5013.5  457.08
  5028.3  464.93  5042.4  467.18  5120.4  465.46  5318.2  465.87  5481.0  472.27
  5601.2  473.81  5756.8  477.56  5891.1  478.47  6018.4  476.02  6301.4  478.96
  6364.9  481.23  6393.2  483.58  6428.5  483.74  6506.4  486.96  6658.9  489.39
#Mann=3,-1,0
  4116.1    0.05       0  5000.9    0.03       0  5013.5    0.05       0
Bank Sta=5000.9,5013.5
Exp/Cntr=0.3,0.1

Type RM Length L Ch R = 1,7000,500,500,500
BEGIN DESCRIPTION:
Little High Point Creek 14.0
END DESCRIPTION:
XS GIS Cut Line= 3
      2627025.98      6972511.01      2626086.18      6973071.61
      2624976.01      6974960.99
#Sta/Elev= 30
  3905.7  503.28  4008.8  500.06  4030.2  497.97  4226.8  484.77  4466.2  473.89
  4497.4  473.55  4635.6  468.57  4779.6  465.51  4918.7  463.89  4948.9  464.88
  4954.7  464.38  4963.9  456.00  4965.7  455.50  4976.7  456.00  4985.9  457.33
  4997.2  461.65  5002.5  461.65  5007.7  463.21  5013.5  462.08  5029.1  464.92
  5044.8  464.17  5519.4  467.59  5648.8  471.63  5802.6  474.75  5839.7  473.74
  5935.5  474.87  6052.7  478.76  6250.0  480.96  6570.3  486.59  7191.4  500.81
#Mann=3,-1,0
  3905.7    0.05       0  4963.9    0.03       0  4976.7    0.05       0
Bank Sta=4963.9,4976.7
Exp/Cntr=0.3,0.1

Type RM Length L Ch R = 1,6500,500,500,500
BEGIN DESCRIPTION:
Little High Point Creek 13.0
END DESCRIPTION:
XS GIS Cut Line= 3
      2626725.99      6972461.00      2625775.68      6972710.43
      2624225.96      6974161.03
#Sta/Elev= 30
  4017.5  493.83  4224.3  482.87  4277.3  478.95  4369.0  474.40  4493.1  469.86
  4617.1  466.16  4989.3  464.28  5014.1  461.62  5028.3  457.26  5029.2  455.71
  5031.0  455.21  5042.1  455.71  5056.6  462.37  5063.9  464.75  5070.8  465.10
  5099.1  464.13  5184.1  463.76  5212.4  462.36  5219.3  461.20  5276.0  463.87
  5495.3  465.01  5657.9  467.90  5912.9  474.14  5976.4  475.95  6012.1  478.20
  6054.3  477.55  6181.6  479.04  6684.2  487.35  6896.2  493.18  7122.7  497.45
#Mann=3,-1,0
  4017.5    0.05       0  5029.2    0.03       0  5042.1    0.05       0
Bank Sta=5029.2,5042.1
Exp/Cntr=0.3,0.1