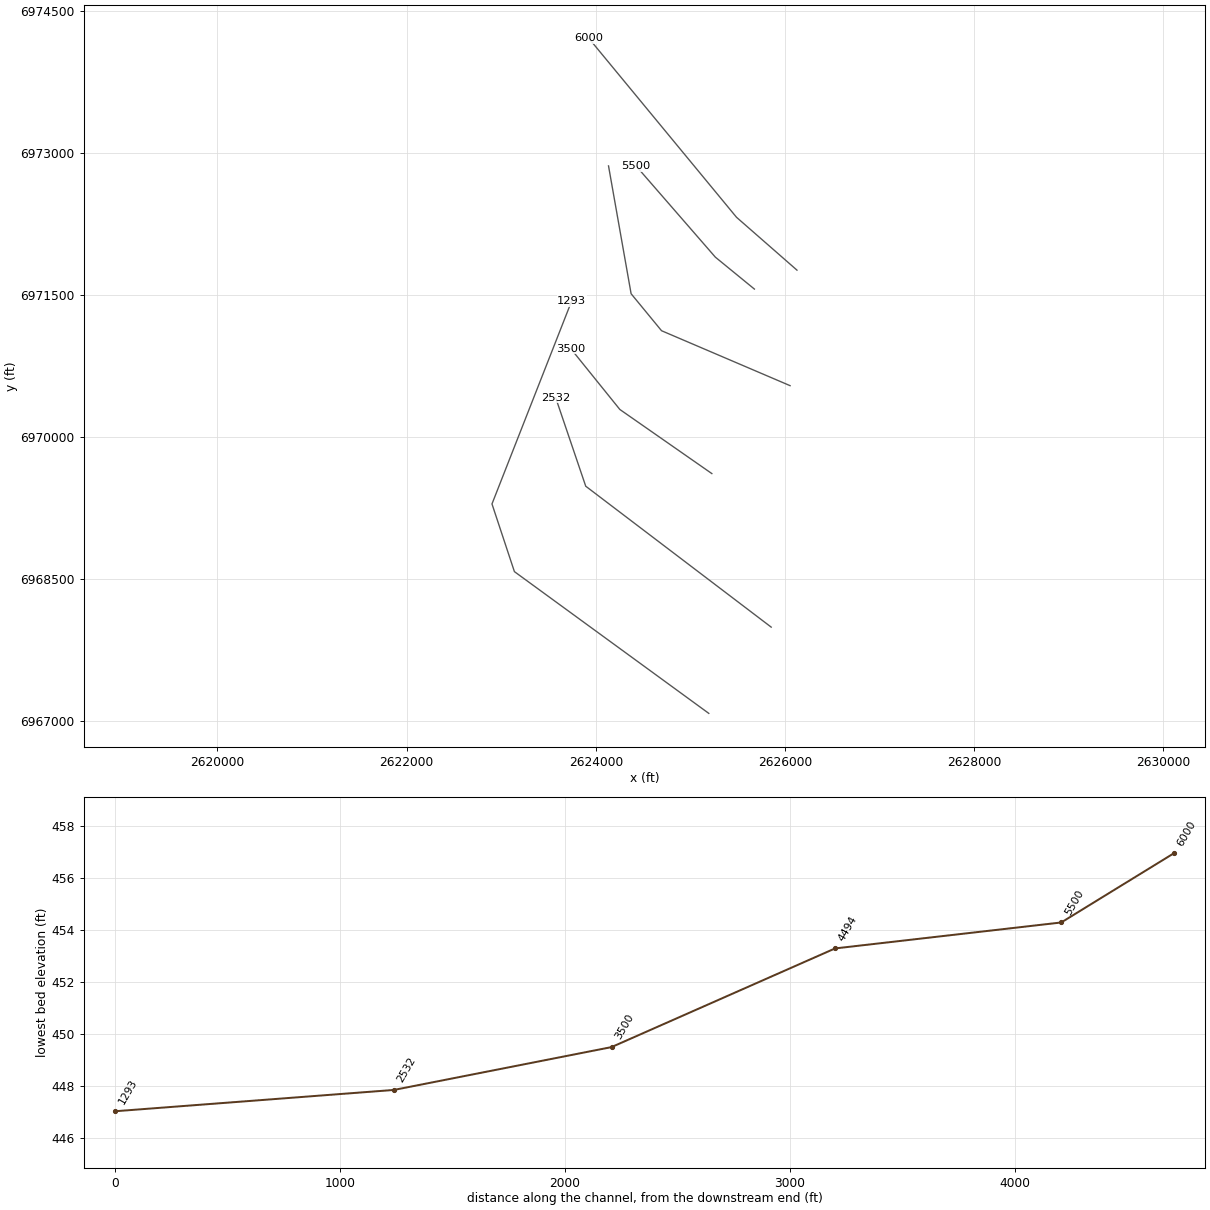
HEC-RAS study Little High Point Creek.prj: Little High Point Creek Base Level Engineering

--- Little High Point Creek.g01 (geometry) --- (continued)

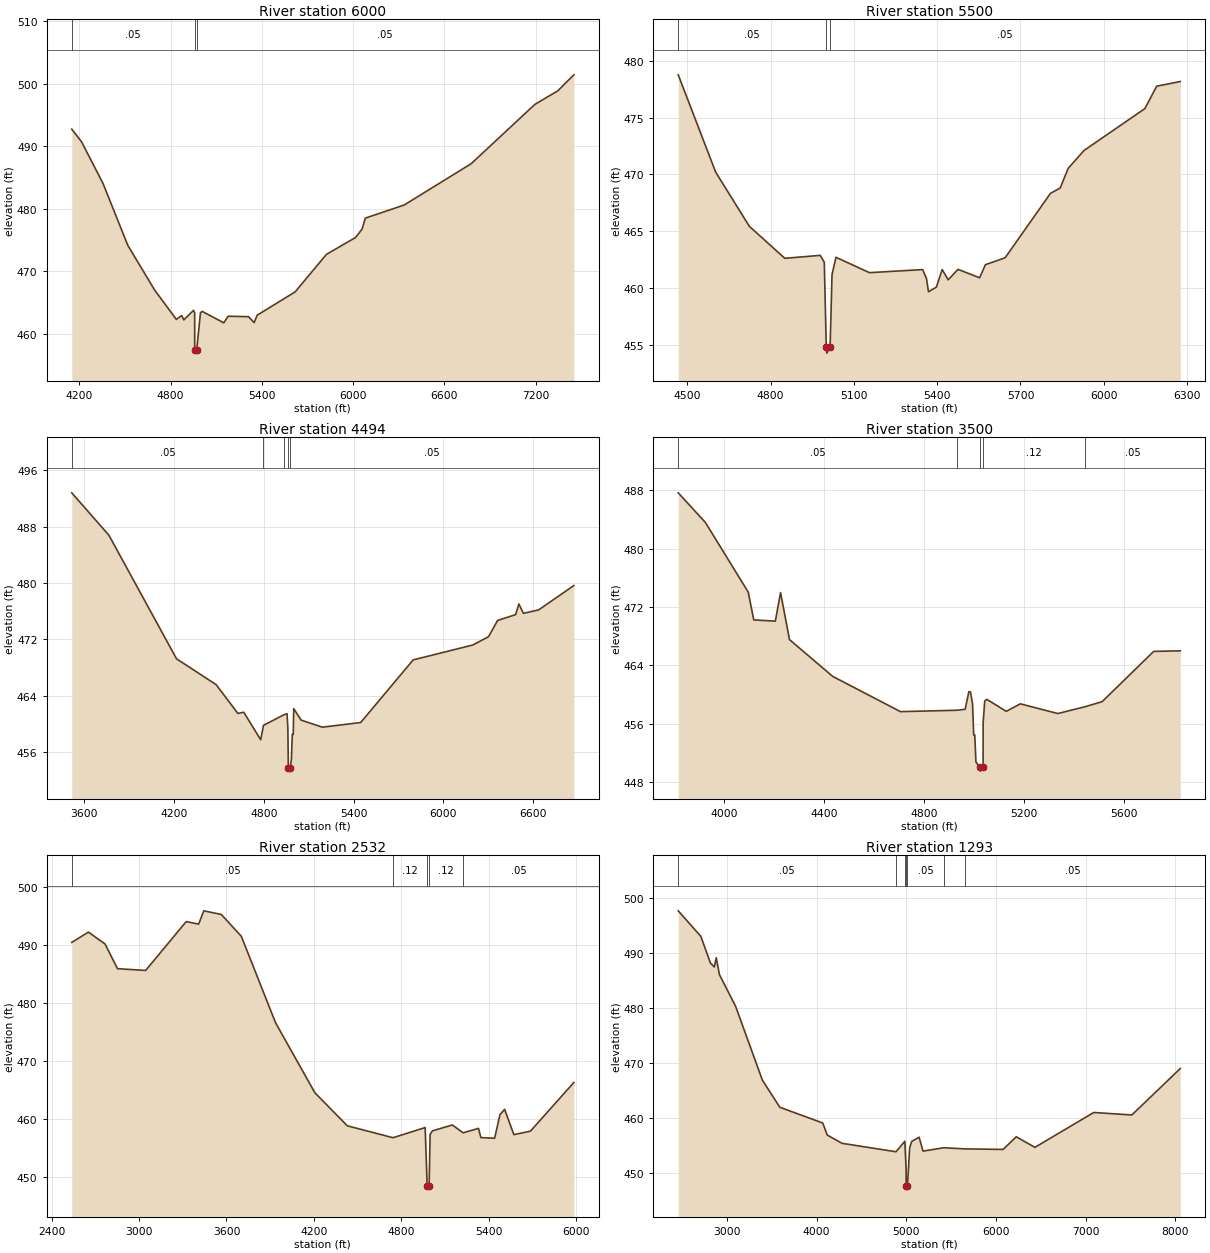
Type RM Length L Ch R = 1,6000,500,500,500
BEGIN DESCRIPTION:
Little High Point Creek 12.0
END DESCRIPTION:
XS GIS Cut Line= 3
      2626125.97      6971761.03      2625486.67      6972319.99
      2623925.97      6974211.03
#Sta/Elev= 30
  4150.8  492.73  4214.8  490.73  4356.3  484.06  4519.5  474.16  4696.1  467.02
  4838.4  462.35  4873.5  462.96  4887.8  462.27  4951.4  463.80  4959.0  463.39
  4959.2  457.46  4961.0  456.96  4972.1  457.46  4997.1  463.41  5008.3  463.63
  5150.4  461.80  5179.0  462.85  5313.2  462.78  5349.7  461.83  5370.5  463.03
  5619.4  466.74  5825.2  472.73  6016.7  475.43  6059.8  476.78  6080.6  478.52
  6336.8  480.62  6777.6  487.23  7195.8  496.69  7345.7  498.84  7451.9  501.41
#Mann=3,-1,0
  4150.8    0.05       0  4959.2    0.03       0  4972.1    0.05       0
Bank Sta=4959.2,4972.1
Exp/Cntr=0.3,0.1

Type RM Length L Ch R = 1,5500,1006,1006,1006
BEGIN DESCRIPTION:
Little High Point Creek 11.0
END DESCRIPTION:
XS GIS Cut Line= 3
      2625675.97      6971561.02      2625263.23      6971898.27
      2624425.97      6972861.03
#Sta/Elev= 30
  4467.0  478.75  4601.9  470.20  4723.3  465.44  4851.0  462.63  4978.8  462.89
  4993.2  462.28  5000.4  454.80  5002.2  454.30  5013.3  454.80  5014.4  455.07
  5021.1  461.20  5035.3  462.72  5155.9  461.37  5347.7  461.64  5361.4  460.85
  5368.6  459.69  5397.1  460.10  5418.0  461.64  5439.8  460.74  5474.9  461.66
  5552.8  460.92  5573.7  462.07  5644.9  462.68  5808.2  468.34  5843.3  468.81
  5871.8  470.53  5928.8  472.10  6148.1  475.78  6190.9  477.75  6275.9  478.16
#Mann=3,-1,0
  4467.0    0.05       0  5000.4    0.03       0  5013.3    0.05       0
Bank Sta=5000.4,5013.3
Exp/Cntr=0.3,0.1

Type RM Length L Ch R = 1,4494,994,994,994
BEGIN DESCRIPTION:
Little High Point Creek 9.0
END DESCRIPTION:
XS GIS Cut Line= 4
      2626053.20      6970540.10      2624694.38      6971120.81
      2624372.72      6971511.78      2624133.92      6972862.85
#Sta/Elev= 30
  3516.1  492.81  3764.4  486.79  4216.3  469.25  4480.9  465.58  4626.5  461.49
  4665.8  461.66  4779.0  457.75  4797.6  459.80  4933.0  461.29  4955.1  461.46
  4960.5  459.39  4963.8  453.80  4965.6  453.30  4976.7  453.80  4984.1  454.98
  4990.2  458.51  4996.5  458.51  4999.8  462.17  5049.3  460.54  5191.4  459.54
  5447.3  460.20  5798.0  469.09  6197.2  471.21  6301.5  472.38  6362.5  474.69
  6483.0  475.52  6504.6  477.03  6535.1  475.70  6636.7  476.19  6872.1  479.65
#Mann=5,-1,0
  3516.1    0.05       0  4797.6    0.12       0  4933.0    0.05       0
  4963.8    0.03       0  4976.7    0.05       0
Bank Sta=4963.8,4976.7
Exp/Cntr=0.3,0.1

Type RM Length L Ch R = 1,3500,968,968,968
BEGIN DESCRIPTION:
Little High Point Creek 7.0
END DESCRIPTION:
XS GIS Cut Line= 3
      2625226.01      6969610.99      2624253.59      6970288.56
      2623735.49      6970930.72
#Sta/Elev= 30
  3814.8  487.67  3923.5  483.61  4095.1  474.05  4117.2  470.24  4203.6  470.07
  4224.5  473.99  4260.3  467.54  4433.0  462.50  4704.5  457.66  4931.6  457.85
  4963.6  457.98  4978.4  460.40  4984.9  460.36  4993.2  458.72  4997.8  454.45
  5002.1  454.45  5006.8  450.76  5022.3  450.00  5024.1  449.50  5035.4  450.00
  5035.6  456.14  5042.0  459.10  5050.0  459.35  5128.4  457.70  5184.4  458.73
  5334.7  457.40  5442.7  458.32  5512.2  459.03  5718.5  465.92  5825.1  466.00
#Mann=5,-1,0
  3814.8    0.05       0  4931.6    0.12       0  5022.3    0.07       0
  5035.4    0.12       0  5442.7    0.05       0
Bank Sta=5022.3,5035.4
Exp/Cntr=0.3,0.1

Type RM Length L Ch R = 1,2532,1239,1239,1239
BEGIN DESCRIPTION:
Little High Point Creek 6.0
END DESCRIPTION:
XS GIS Cut Line= 3
      2625853.51      6967988.04      2623893.04      6969477.51
      2623575.99      6970411.04
#Sta/Elev= 30
  2537.9  490.46  2652.2  492.25  2766.5  490.19  2851.8  485.93  3045.2  485.62
  3323.8  494.06  3409.1  493.62  3444.5  495.92  3565.1  495.29  3702.3  491.52
  3937.3  476.59  4207.7  464.49  4430.2  458.79  4743.9  456.73  4964.7  458.48
  4978.9  448.35  4980.8  447.85  4992.0  448.35  4998.8  457.28  5014.2  457.91
  5151.5  458.93  5225.6  457.58  5331.1  458.34  5347.7  456.75  5441.8  456.64
  5478.9  460.72  5510.6  461.63  5574.0  457.26  5687.7  457.86  5985.9  466.27
#Mann=5,-1,0
  2537.9    0.05       0  4743.9    0.12       0  4978.9    0.07       0
  4992.0    0.12       0  5225.6    0.05       0
Bank Sta=4978.9,4992
Exp/Cntr=0.3,0.1

Type RM Length L Ch R = 1,1293,0,0,0
BEGIN DESCRIPTION:
Little High Point Creek 3.0
END DESCRIPTION:
XS GIS Cut Line= 4
      2625193.84      6967076.54      2623139.16      6968574.75
      2622902.14      6969290.11      2623744.15      6971434.20
#Sta/Elev= 30
  2457.1  497.58  2709.5  492.94  2816.1  488.09  2860.1  487.39  2881.0  489.06
  2916.5  486.00  3096.5  480.26  3395.4  466.84  3590.1  461.90  4069.1  459.04
  4119.3  456.85  4284.6  455.35  4885.9  453.82  4984.7  455.73  4998.9  450.57
  4999.9  447.53  5001.8  447.03  5013.3  447.53  5038.2  454.51  5061.1  455.69
  5143.5  456.46  5187.9  453.93  5418.9  454.55  5654.6  454.34  6080.5  454.24
  6227.3  456.54  6435.6  454.62  7091.6  460.95  7516.5  460.50  8057.1  468.94
#Mann=7,-1,0
  2457.1    0.05       0  4885.9    0.12       0  4984.7    0.05       0
  4999.9    0.03       0  5013.3    0.05       0  5418.9     0.1       0
  5654.6    0.05       0
Bank Sta=4999.9,5013.3
Exp/Cntr=0.3,0.1

Chan Stop Cuts=-1