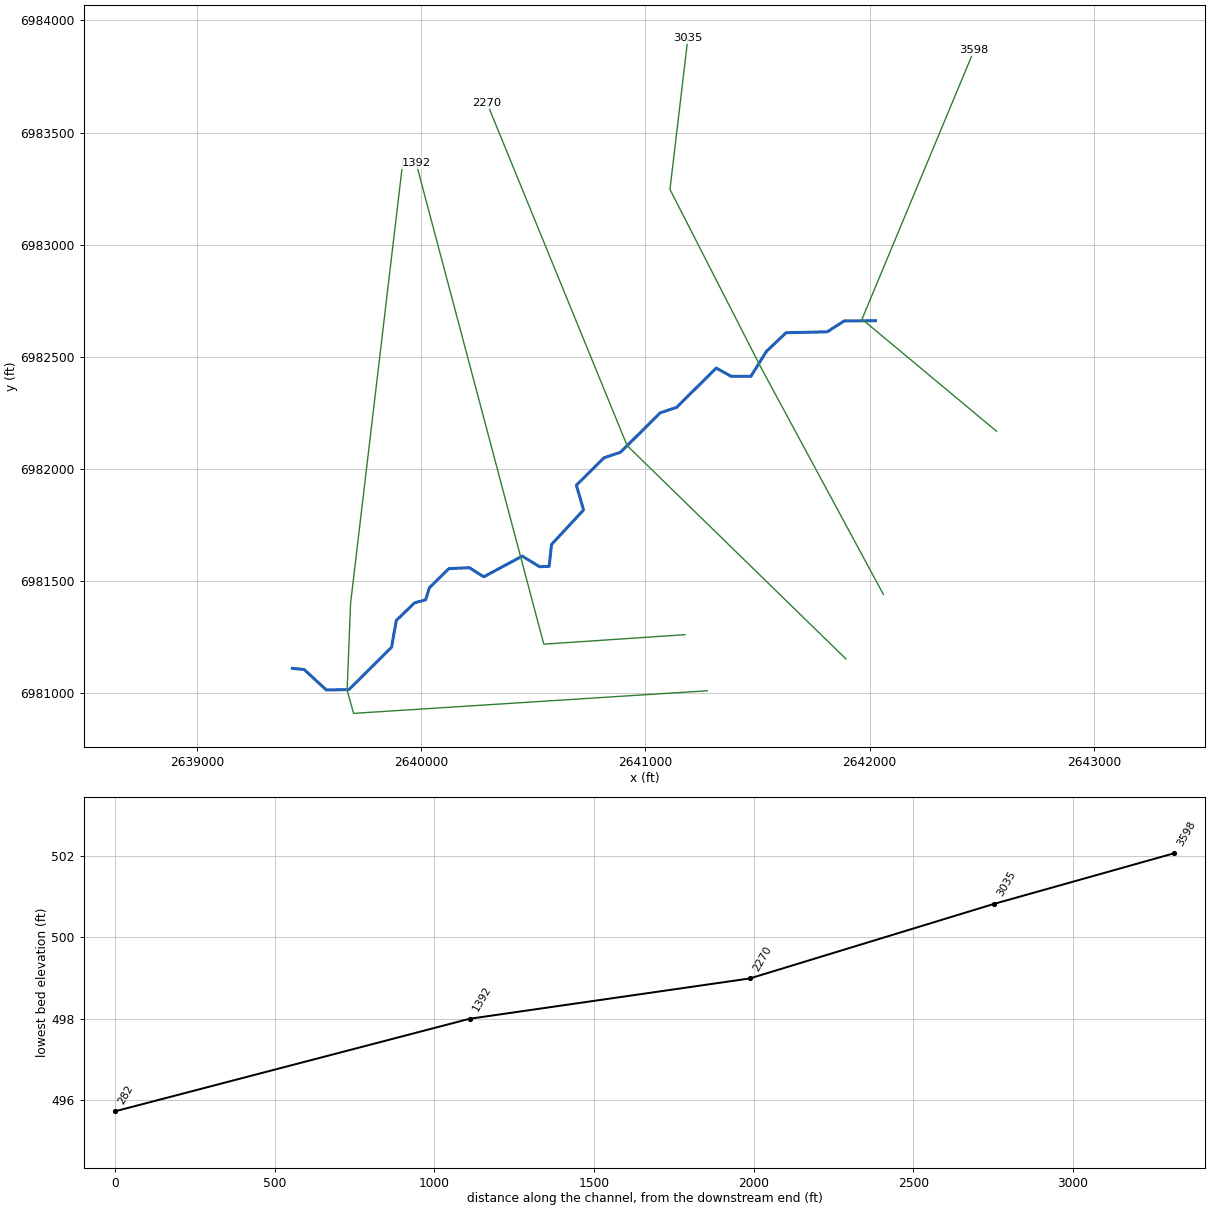
--- Little High Point Creek Trib 1.prj (project) ---

Proj Title=Little High Point Creek Trib 1 Base Level Engineering
Current Plan=p01
Default Exp/Contr=0.3,0.1
English Units
Geom File=g01
Flow File=f01
Plan File=p01
BEGIN DESCRIPTION:
Little High Point Creek Trib 1
END DESCRIPTION:

--- Little High Point Creek Trib 1.p01 (plan) ---

Plan Title=Multiple Run
Short Identifier=Multiple
Geom File=g01
Flow File=f01
Subcritical Flow
K Sum by GR= 0
Std Step Tol= 0.01
Critical Tol= 0.01
Num of Std Step Trials= 20
Max Error Tol= 0.3
Flow Tol Ratio= 0.001
Split Flow NTrial= 30
Split Flow Tol= 0.02
Split Flow Ratio= 0.02
Log Output Level= 0
Friction Slope Method= 1
Unsteady Friction Slope Method= 2
Unsteady Bridges Friction Slope Method= 1
Parabolic Critical Depth
Global Vel Dist=  1 , 1 , 1
Global Log Level= 0
CheckData=True
Encroach Param= -1, 0, 0, 0
BEGIN DESCRIPTION:
Multiple Run
END DESCRIPTION:

--- Little High Point Creek Trib 1.f01 (steady flow) ---

Flow Title=Multiple
Number of Profiles=7
Profile Names=10-year,25-year,50-year,1pct_min,100-year,1pct_plu,500-year
River Rch & RM= Little High Poin,Reach-1,3598
     572     763     915     545    1088    2171    1535
River Rch & RM= Little High Poin,Reach-1,3035
     638     854    1028     614    1225    2444    1736
River Rch & RM= Little High Poin,Reach-1,1392
     645     863    1037     619    1234    2463    1746
Boundary for River Rch & Prof#=Little High Poin,Reach-1,1
Up Type=0
Dn Type=3
Dn Slope=0.005
Boundary for River Rch & Prof#=Little High Poin,Reach-1,2
Up Type=0
Dn Type=3
Dn Slope=0.005
Boundary for River Rch & Prof#=Little High Poin,Reach-1,3
Up Type=0
Dn Type=3
Dn Slope=0.005
Boundary for River Rch & Prof#=Little High Poin,Reach-1,4
Up Type=0
Dn Type=3
Dn Slope=0.005
Boundary for River Rch & Prof#=Little High Poin,Reach-1,5
Up Type=0
Dn Type=3
Dn Slope=0.005
Boundary for River Rch & Prof#=Little High Poin,Reach-1,6
Up Type=0
Dn Type=3
Dn Slope=0.005
Boundary for River Rch & Prof#=Little High Poin,Reach-1,7
Up Type=0
Dn Type=3
Dn Slope=0.005

--- Little High Point Creek Trib 1.g01 (geometry) ---

Geom Title=Existing Conditions

River Reach=Little High Poin,Reach-1
Reach XY= 30
      2642026.00      6982661.00      2641886.48      6982659.83
      2641810.78      6982611.52      2641627.45      6982607.47
      2641539.62      6982524.23      2641470.29      6982412.89
      2641381.90      6982413.37      2641315.94      6982449.90
      2641139.21      6982274.63      2641066.32      6982250.22
      2640889.21      6982074.63      2640816.32      6982050.22
      2640692.30      6981927.70      2640724.34      6981817.05
      2640581.55      6981663.35      2640570.75      6981565.63
      2640528.17      6981564.19      2640451.01      6981611.40
      2640279.32      6981519.05      2640215.51      6981559.74
      2640123.56      6981555.60      2640036.88      6981470.44
      2640020.38      6981416.62      2639970.23      6981402.72
      2639889.40      6981324.33      2639868.14      6981204.83
      2639678.43      6981016.40      2639577.50      6981014.46
      2639478.51      6981105.67      2639426.00      6981111.00

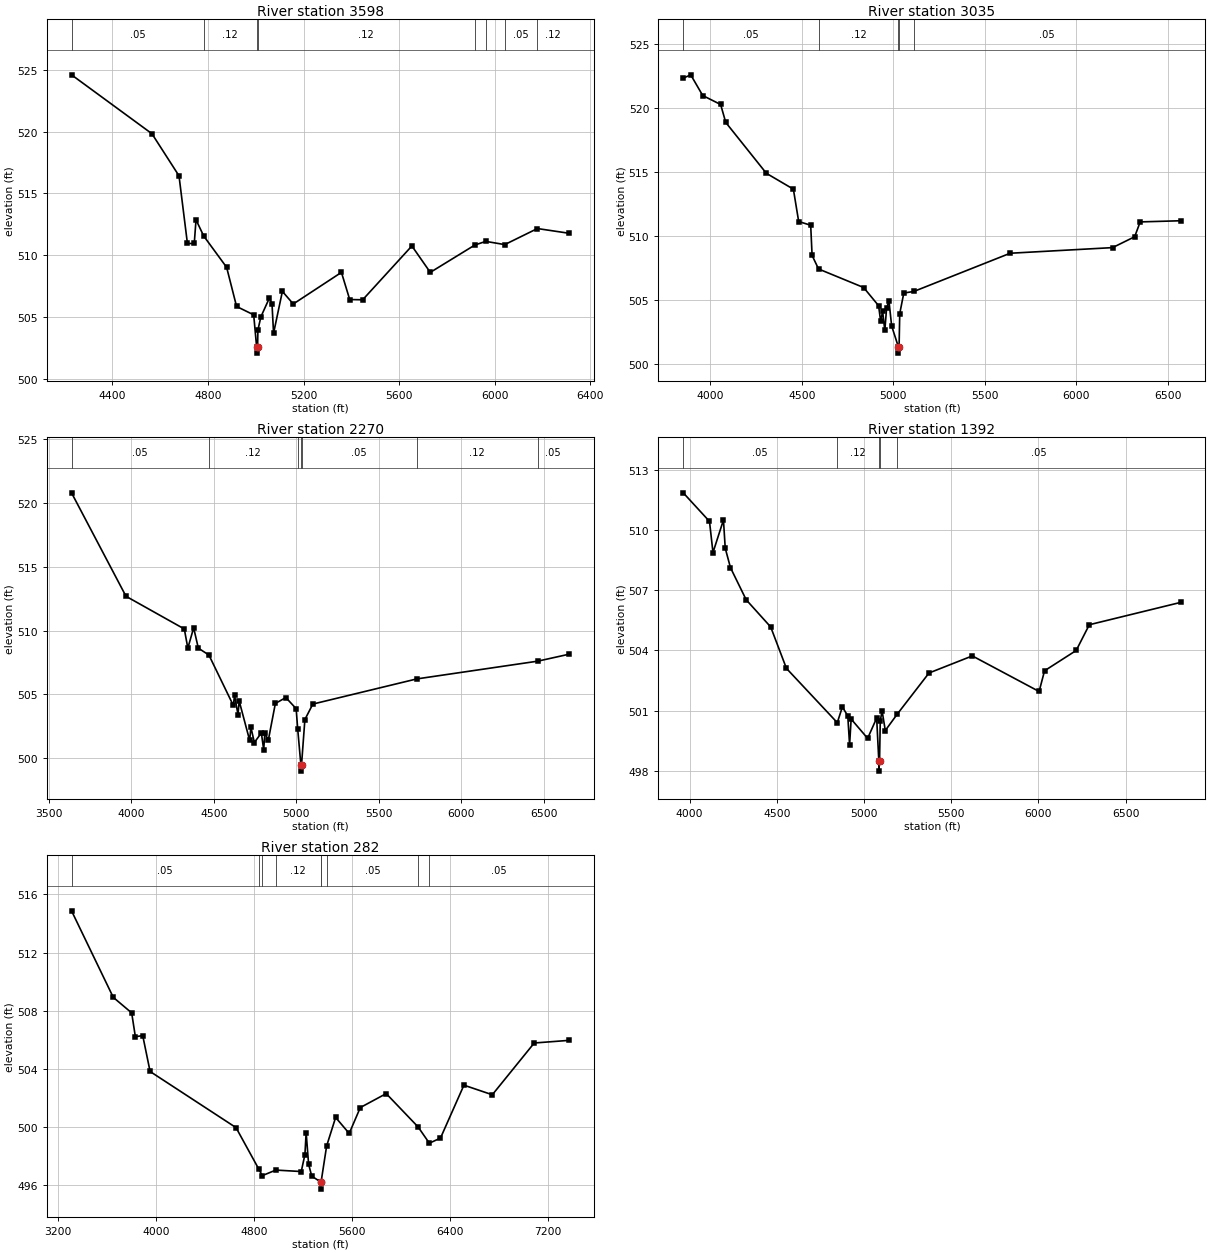
Type RM Length L Ch R = 1,3598,563,563,563
BEGIN DESCRIPTION:
Little High Point Creek Trib 1 5.0
END DESCRIPTION:
XS GIS Cut Line= 3
      2642565.98      6982167.93      2641965.96      6982667.94
      2642465.56      6983866.98
#Sta/Elev= 30
  4229.6  524.60  4565.9  519.83  4679.1  516.42  4714.3  510.94  4742.9  510.94
  4750.3  512.86  4782.3  511.55  4878.3  509.01  4919.9  505.84  4991.5  505.16
  5003.8  502.56  5004.1  502.06  5007.8  502.56  5009.1  503.93  5021.6  505.00
  5057.3  506.53  5068.1  506.05  5074.6  503.67  5111.5  507.06  5157.0  506.04
  5358.5  508.60  5393.1  506.40  5447.3  506.38  5653.1  510.74  5730.1  508.60
  5916.9  510.82  5962.2  511.11  6041.6  510.85  6178.1  512.15  6309.6  511.77
#Mann=8,-1,0
  4229.6    0.05       0  4782.3    0.12       0  5003.8    0.07       0
  5007.8    0.12       0  5916.9    0.05       0  5962.2    0.12       0
  6041.6    0.05       0  6178.1    0.12       0
Bank Sta=5003.8,5007.8
Exp/Cntr=0.3,0.1

Type RM Length L Ch R = 1,3035,765,765,765
BEGIN DESCRIPTION:
Mapping XS bf57712e
END DESCRIPTION:
XS GIS Cut Line= 4
      2642060.97      6981441.01      2641515.85      6982451.40
      2641109.60      6983246.54      2641189.46      6983920.15
#Sta/Elev= 30
  3851.8  522.32  3892.7  522.58  3958.4  520.96  4056.3  520.26  4084.1  518.86
  4306.3  514.88  4454.0  513.64  4483.0  511.11  4548.7  510.82  4556.3  508.46
  4591.6  507.40  4838.1  505.95  4919.9  504.53  4931.4  503.30  4941.9  504.09
  4954.0  502.59  4963.8  504.35  4976.7  504.90  4991.4  502.94  5028.0  501.32
  5028.2  500.82  5032.0  501.32  5035.6  503.91  5057.8  505.52  5112.3  505.64
  5639.5  508.63  6199.4  509.07  6320.2  509.92  6350.4  511.08  6571.1  511.17
#Mann=5,-1,0
  3851.8    0.05       0  4591.6    0.12       0  5028.0    0.07       0
  5032.0    0.12       0  5112.3    0.05       0
Bank Sta=5028,5032
Exp/Cntr=0.3,0.1

Type RM Length L Ch R = 1,2270,878,878,878
BEGIN DESCRIPTION:
Mapping XS 037de5b5
END DESCRIPTION:
XS GIS Cut Line= 3
      2641894.33      6981152.78      2640918.63      6982104.17
      2640293.64      6983631.91
#Sta/Elev= 30
  3637.9  520.78  3967.9  512.68  4321.3  510.12  4342.6  508.62  4377.9  510.21
  4406.2  508.62  4470.3  508.08  4618.4  504.13  4625.6  504.92  4646.7  503.41
  4653.8  504.48  4717.4  501.39  4724.6  502.43  4745.7  501.23  4788.1  501.98
  4802.3  500.67  4809.3  501.95  4830.6  501.43  4873.0  504.29  4936.6  504.75
  4999.0  503.88  5008.2  502.31  5027.6  499.49  5027.9  498.99  5031.6  499.49
  5051.9  503.03  5100.0  504.24  5730.0  506.21  6462.9  507.60  6651.3  508.14
#Mann=7,-1,0
  3637.9    0.05       0  4470.3    0.12       0  5008.2    0.05       0
  5027.6    0.07       0  5031.6    0.05       0  5730.0    0.12       0
  6462.9    0.05       0
Bank Sta=5027.6,5031.6
Exp/Cntr=0.3,0.1

Type RM Length L Ch R = 1,1392,1110,1110,1110
BEGIN DESCRIPTION:
Little High Point Creek Trib 1 2.0
END DESCRIPTION:
XS GIS Cut Line= 3
      2641176.03      6981261.00      2640547.10      6981218.76
      2639977.67      6983364.55
#Sta/Elev= 30
  3963.8  511.84  4114.2  510.42  4134.2  508.87  4194.3  510.49  4204.4  509.09
  4234.4  508.12  4324.6  506.52  4465.0  505.17  4555.2  503.11  4846.7  500.41
  4875.8  501.19  4906.8  500.75  4917.2  499.30  4926.1  500.59  5020.7  499.63
  5072.4  500.64  5084.8  498.50  5085.1  498.00  5088.9  498.50  5093.1  500.50
  5103.4  501.00  5121.9  500.02  5190.0  500.83  5372.4  502.88  5620.7  503.73
  6003.5  501.96  6034.6  502.99  6216.0  504.00  6291.2  505.28  6814.2  506.39
#Mann=5,-1,0
  3963.8    0.05       0  4846.7    0.12       0  5084.8    0.07       0
  5088.9    0.12       0  5190.0    0.05       0
Bank Sta=5084.8,5088.9
Exp/Cntr=0.3,0.1

Type RM Length L Ch R = 1,282,0,0,0
BEGIN DESCRIPTION:
Little High Point Creek Trib 1 1.0
END DESCRIPTION:
XS GIS Cut Line= 5
      2641276.02      6981011.00      2639699.02      6980910.17
      2639670.11      6981012.96      2639685.50      6981400.88
      2639918.63      6983371.51
#Sta/Elev= 30
  3313.0  514.87  3653.7  508.92  3804.0  507.85  3834.1  506.21  3894.2  506.29
  3954.3  503.82  4655.8  499.96  4840.2  497.13  4870.5  496.66  4980.9  497.04
  5188.2  496.94  5218.2  498.11  5228.2  499.62  5248.2  497.45  5274.0  496.62
  5346.2  496.23  5346.6  495.73  5350.4  496.23  5395.5  498.70  5468.9  500.66
  5579.7  499.56  5670.3  501.34  5881.8  502.30  6141.8  500.01  6234.0  498.89
  6324.8  499.24  6516.2  502.88  6747.8  502.22  7090.1  505.78  7372.6  505.96
#Mann=9,-1,0
  3313.0    0.05       0  4840.2    0.12       0  4870.5    0.05       0
  4980.9    0.12       0  5346.2    0.07       0  5350.4    0.12       0
  5395.5    0.05       0  6141.8    0.12       0  6234.0    0.05       0
Bank Sta=5346.2,5350.4
Exp/Cntr=0.3,0.1

Chan Stop Cuts=-1