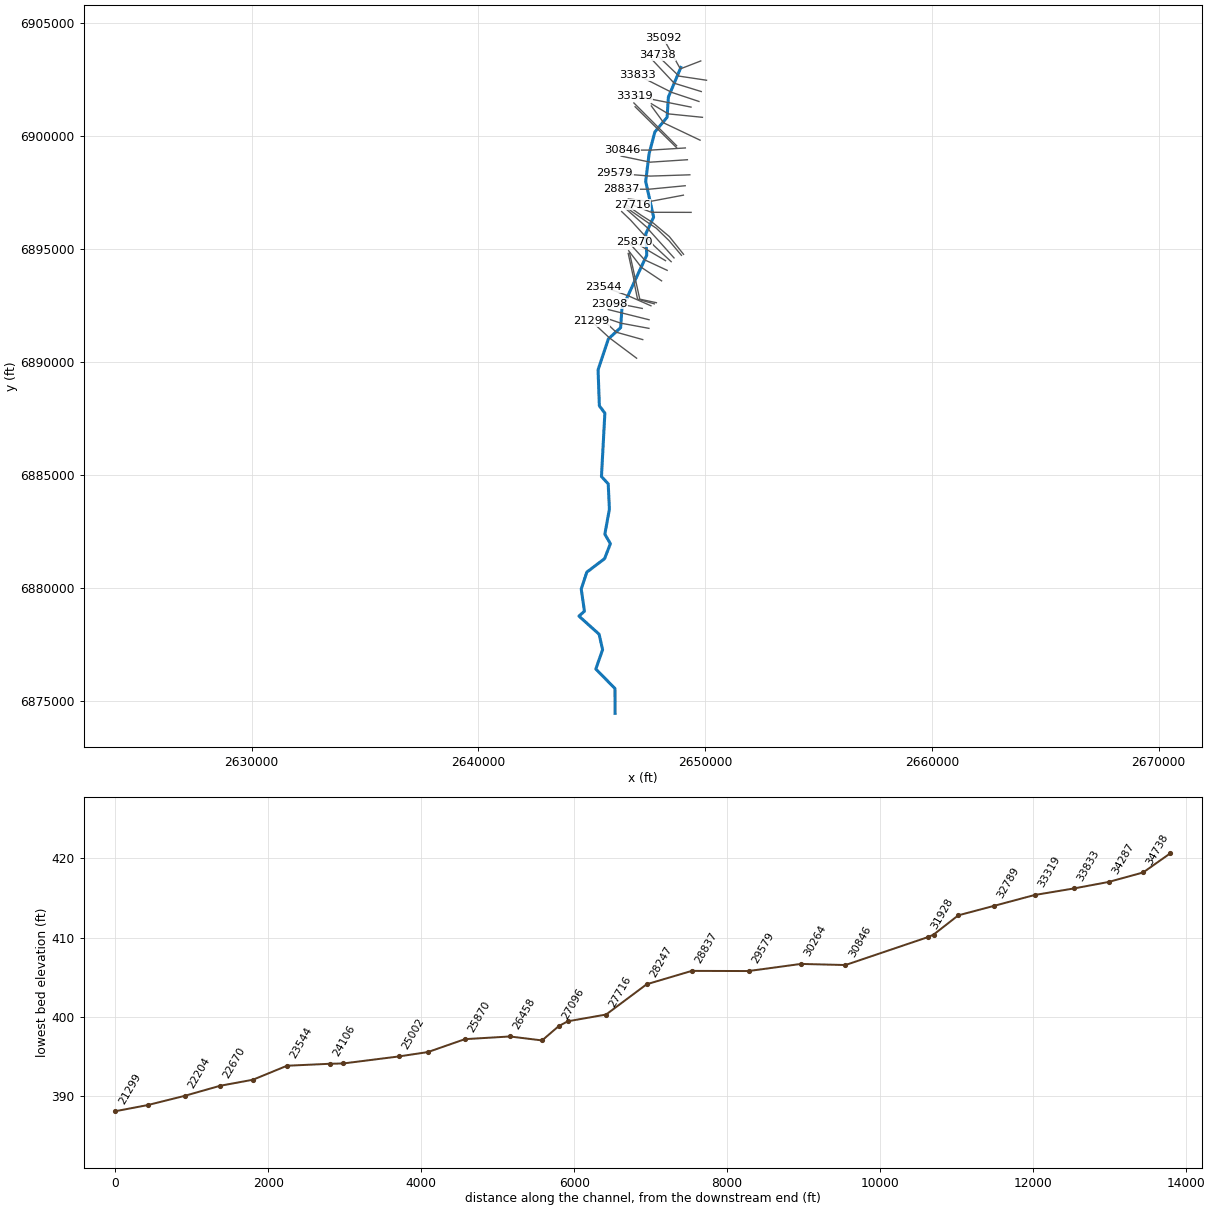
--- Prairie Branch.prj (project) ---

Proj Title=Prairie Branch Base Level Engineering
Current Plan=p01
Default Exp/Contr=0.3,0.1
English Units
Geom File=g01
Flow File=f01
Plan File=p01
BEGIN DESCRIPTION:
Prairie Branch
END DESCRIPTION:

--- Prairie Branch.p01 (plan) ---

Plan Title=Multiple Run
Short Identifier=Multiple
Geom File=g01
Flow File=f01
Subcritical Flow
K Sum by GR= 0
Std Step Tol= 0.01
Critical Tol= 0.01
Num of Std Step Trials= 20
Max Error Tol= 0.3
Flow Tol Ratio= 0.001
Split Flow NTrial= 30
Split Flow Tol= 0.02
Split Flow Ratio= 0.02
Log Output Level= 0
Friction Slope Method= 1
Unsteady Friction Slope Method= 2
Unsteady Bridges Friction Slope Method= 1
Parabolic Critical Depth
Global Vel Dist=  1 , 1 , 1
Global Log Level= 0
CheckData=True
Encroach Param= -1, 0, 0, 0
BEGIN DESCRIPTION:
Multiple Run
END DESCRIPTION:

--- Prairie Branch.f01 (steady flow) ---

Flow Title=Multiple
Number of Profiles=7
Profile Names=10-year,25-year,50-year,1pct_min,100-year,1pct_plu,500-year
River Rch & RM= Prairie Branch,Reach-1,35092
     221     279     322     186     371     739     488
River Rch & RM= Prairie Branch,Reach-1,33319
     622     836    1009     603    1204    2401    1713
River Rch & RM= Prairie Branch,Reach-1,29579
     789    1068    1295     777    1550    3092    2222
River Rch & RM= Prairie Branch,Reach-1,23544
    1552    2184    2717    1670    3331    6647    5016
River Rch & RM= Prairie Branch,Reach-1,19449
    1753    2480    3097    1910    3811    7603    5778
River Rch & RM= Prairie Branch,Reach-1,18559
    1787    2529    3158    1948    3886    7754    5893
River Rch & RM= Prairie Branch,Reach-1,16677
    1957    2775    3469    2140    4271    8521    6484
River Rch & RM= Prairie Branch,Reach-1,12192
    2149    3055    3825    2363    4716    9409    7179
River Rch & RM= Prairie Branch,Reach-1,8995
    2225    3156    3946    2433    4855    9687    7363
Boundary for River Rch & Prof#=Prairie Branch,Reach-1,1
Up Type=0
Dn Type=3
Dn Slope=0.005
Boundary for River Rch & Prof#=Prairie Branch,Reach-1,2
Up Type=0
Dn Type=3
Dn Slope=0.005
Boundary for River Rch & Prof#=Prairie Branch,Reach-1,3
Up Type=0
Dn Type=3
Dn Slope=0.005
Boundary for River Rch & Prof#=Prairie Branch,Reach-1,4
Up Type=0
Dn Type=3
Dn Slope=0.005
Boundary for River Rch & Prof#=Prairie Branch,Reach-1,5
Up Type=0
Dn Type=3
Dn Slope=0.005
Boundary for River Rch & Prof#=Prairie Branch,Reach-1,6
Up Type=0
Dn Type=3
Dn Slope=0.005
Boundary for River Rch & Prof#=Prairie Branch,Reach-1,7
Up Type=0
Dn Type=3
Dn Slope=0.005

--- Prairie Branch.g01 (geometry) ---

Geom Title=Existing Conditions

River Reach=Prairie Branch,Reach-1
Reach XY= 30
      2648926.00      6903011.00      2648378.23      6901705.10
      2648322.17      6900812.58      2647779.76      6900159.44
      2647527.20      6899200.50      2647375.48      6897981.06
      2647726.80      6896395.87      2647377.22      6895650.50
      2647423.74      6894716.94      2646327.62      6892349.17
      2646272.46      6891512.46      2645731.54      6891013.37
      2645276.50      6889645.80      2645333.67      6888057.30
      2645576.36      6887731.15      2645425.93      6884930.98
      2645723.86      6884605.04      2645776.39      6883490.87
      2645575.79      6882381.05      2645818.91      6881961.00
      2645562.59      6881297.61      2644778.63      6880702.52
      2644533.33      6879960.90      2644675.34      6878976.83
      2644433.07      6878761.00      2645322.25      6877959.45
      2645476.19      6877276.87      2645176.87      6876421.33
      2646022.54      6875559.75      2646026.00      6874461.00

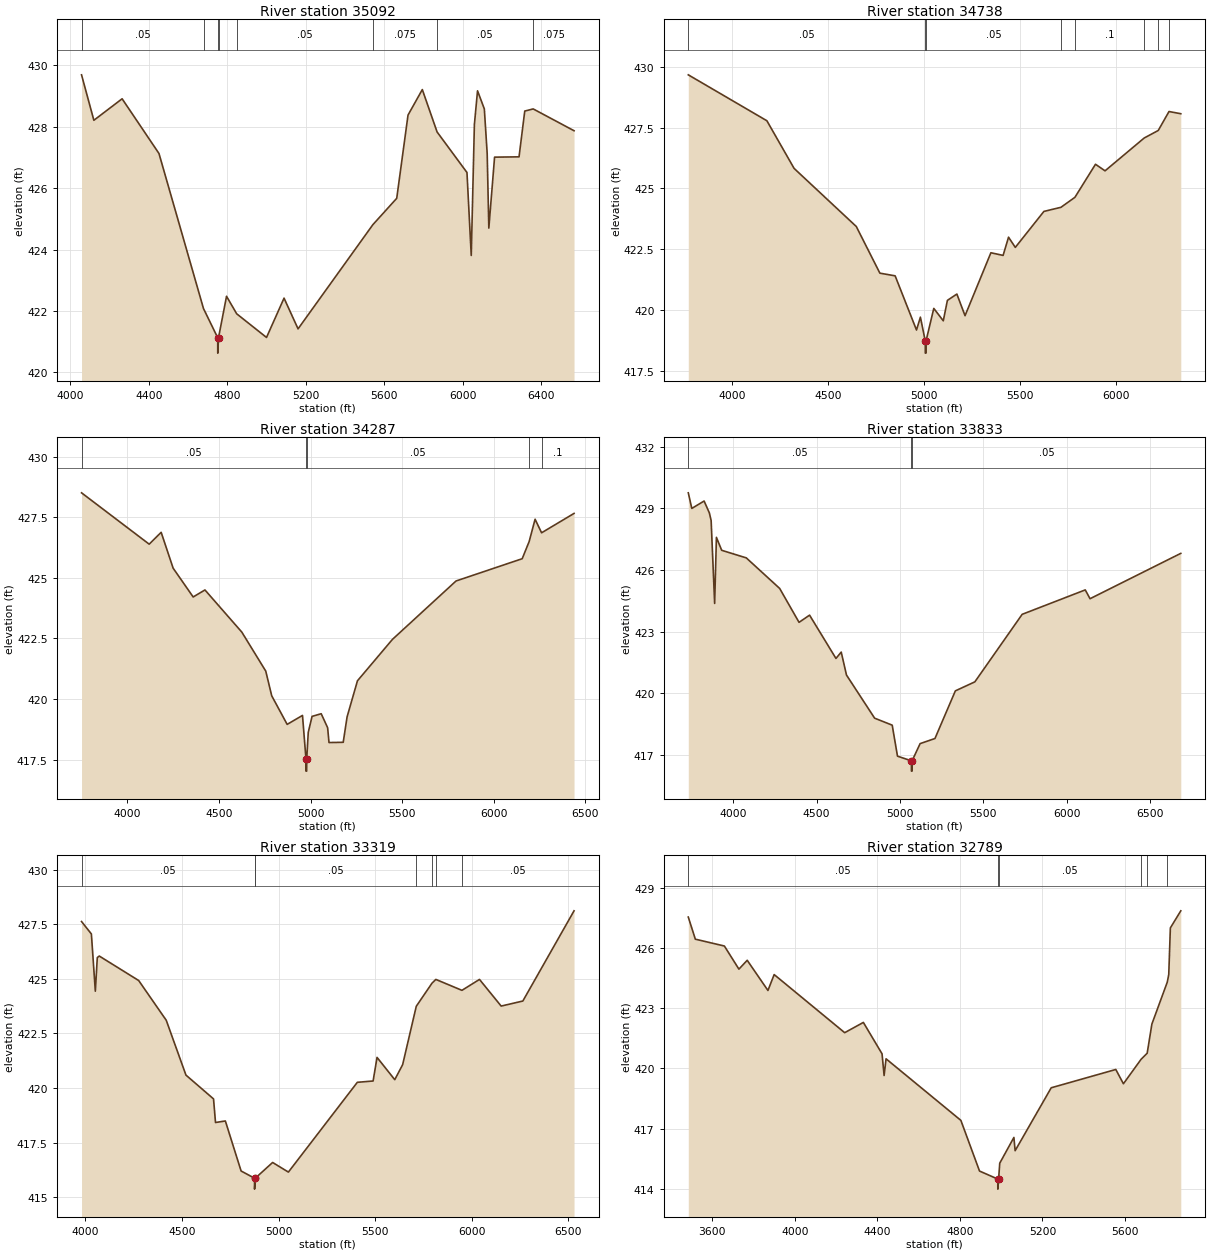
Type RM Length L Ch R = 1,35092,354,354,354
BEGIN DESCRIPTION:
Prairie Branch 71.0
END DESCRIPTION:
XS GIS Cut Line= 3
      2649804.73      6903300.60      2648904.69      6902950.58
      2648154.67      6904300.62
#Sta/Elev= 30
  4057.2  429.69  4120.0  428.21  4264.0  428.91  4451.8  427.13  4678.8  422.08
  4751.3  421.13  4751.5  420.63  4755.3  421.13  4796.2  422.48  4848.0  421.91
  5000.0  421.14  5089.3  422.42  5160.7  421.42  5541.8  424.81  5663.6  425.67
  5721.2  428.38  5794.0  429.21  5869.3  427.83  6021.6  426.51  6043.4  423.81
  6059.4  428.07  6075.4  429.17  6110.1  428.58  6124.6  427.13  6133.0  424.70
  6162.3  427.01  6287.0  427.02  6316.1  428.51  6359.2  428.58  6567.3  427.87
#Mann=8,-1,0
  4057.2    0.05       0  4678.8    0.12       0  4751.3    0.03       0
  4755.3    0.12       0  4848.0    0.05       0  5541.8   0.075       0
  5869.3    0.05       0  6359.2   0.075       0
Bank Sta=4751.3,4755.3
Exp/Cntr=0.3,0.1

Type RM Length L Ch R = 1,34738,451,451,451
BEGIN DESCRIPTION:
Prairie Branch 70.0
END DESCRIPTION:
XS GIS Cut Line= 3
      2650060.56      6902448.41      2648846.48      6902630.80
      2647883.52      6903556.00
#Sta/Elev= 30
  3772.3  429.67  4181.4  427.78  4323.0  425.82  4646.6  423.43  4769.4  421.51
  4848.8  421.40  4960.0  419.17  4980.3  419.70  5005.6  418.72  5005.8  418.22
  5009.3  418.22  5009.6  418.72  5050.0  420.06  5099.4  419.55  5120.8  420.39
  5170.1  420.65  5212.6  419.76  5347.2  422.35  5410.7  422.24  5439.0  422.99
  5474.2  422.57  5623.0  424.05  5711.8  424.22  5784.4  424.63  5891.5  425.99
  5941.2  425.72  6144.9  427.07  6218.0  427.38  6274.1  428.16  6335.4  428.07
#Mann=8,-1,0
  3772.3    0.05       0  5005.6    0.03       0  5009.6    0.05       0
  5711.8   0.075       0  5784.4     0.1       0  6144.9   0.075       0
  6218.0     0.1       0  6274.1   0.075       0
Bank Sta=5005.6,5009.6
Exp/Cntr=0.3,0.1

Type RM Length L Ch R = 1,34287,454,454,454
BEGIN DESCRIPTION:
Prairie Branch 69.0
END DESCRIPTION:
XS GIS Cut Line= 3
      2649827.95      6901948.39      2648634.18      6902317.06
      2647652.09      6903367.19
#Sta/Elev= 30
  3750.6  428.51  4119.7  426.39  4185.0  426.88  4250.3  425.40  4359.7  424.21
  4424.0  424.50  4625.1  422.76  4755.7  421.15  4788.3  420.13  4872.5  418.95
  4956.2  419.32  4975.2  417.52  4975.4  417.02  4978.9  417.02  4979.2  417.52
  4987.6  418.62  5008.4  419.28  5058.3  419.39  5093.4  418.81  5100.8  418.20
  5178.4  418.21  5199.5  419.26  5256.1  420.75  5447.1  422.46  5793.9  424.87
  6154.9  425.79  6193.0  426.50  6225.3  427.42  6260.7  426.86  6437.8  427.66
#Mann=5,-1,0
  3750.6    0.05       0  4975.2    0.03       0  4979.2    0.05       0
  6193.0   0.075       0  6260.7     0.1       0
Bank Sta=4975.2,4979.2
Exp/Cntr=0.3,0.1

Type RM Length L Ch R = 1,33833,514,514,514
BEGIN DESCRIPTION:
Prairie Branch 68.0
END DESCRIPTION:
XS GIS Cut Line= 3
      2649726.02      6901510.99      2648526.00      6901911.00
      2647020.84      6902675.69
#Sta/Elev= 30
  3731.0  429.76  3752.1  429.00  3825.9  429.36  3857.5  428.78  3868.0  428.41
  3889.1  424.37  3899.7  427.59  3931.3  426.96  4078.9  426.59  4279.1  425.10
  4395.1  423.45  4458.3  423.80  4616.5  421.69  4648.1  422.00  4679.7  420.88
  4848.4  418.78  4953.8  418.44  4985.4  416.93  5069.0  416.70  5069.3  416.20
  5072.8  416.20  5073.0  416.70  5121.1  417.54  5210.2  417.79  5332.4  420.11
  5449.4  420.55  5733.1  423.84  6111.4  425.03  6140.0  424.60  6684.2  426.81
#Mann=3,-1,0
  3731.0    0.05       0  5069.0    0.03       0  5073.0    0.05       0
Bank Sta=5069,5073
Exp/Cntr=0.3,0.1

Type RM Length L Ch R = 1,33319,530,530,530
BEGIN DESCRIPTION:
Prairie Branch 66.0
END DESCRIPTION:
XS GIS Cut Line= 3
      2649376.00      6901261.00      2648376.00      6901461.00
      2646876.01      6901761.00
#Sta/Elev= 30
  3980.2  427.62  4031.2  427.05  4051.6  424.43  4061.8  425.97  4072.0  426.04
  4275.9  424.92  4418.7  423.10  4520.7  420.59  4663.5  419.50  4673.7  418.42
  4724.7  418.49  4806.2  416.20  4875.6  415.87  4875.9  415.37  4879.6  415.87
  4969.4  416.59  5051.0  416.15  5407.9  420.26  5489.5  420.32  5509.9  421.40
  5601.7  420.38  5642.5  421.07  5713.0  423.74  5794.6  424.80  5814.4  424.97
  5949.4  424.47  6040.2  424.97  6152.4  423.75  6264.6  423.98  6529.7  428.11
#Mann=7,-1,0
  3980.2    0.05       0  4875.6    0.03       0  4879.6    0.05       0
  5713.0   0.075       0  5794.6    0.05       0  5814.4   0.075       0
  5949.4    0.05       0
Bank Sta=4875.6,4879.6
Exp/Cntr=0.3,0.1

Type RM Length L Ch R = 1,32789,468,468,468
BEGIN DESCRIPTION:
Prairie Branch 64.0
END DESCRIPTION:
XS GIS Cut Line= 3
      2649880.03      6900809.51      2648376.00      6900961.00
      2647625.99      6901411.01
#Sta/Elev= 30
  3484.1  427.53  3518.3  426.43  3659.0  426.09  3729.4  424.94  3769.6  425.38
  3870.1  423.88  3900.2  424.67  4241.9  421.78  4332.4  422.29  4422.9  420.73
  4432.9  419.65  4442.4  420.48  4804.8  417.42  4895.2  414.90  4983.7  414.50
  4983.9  414.00  4987.7  414.50  4993.2  415.29  5061.8  416.57  5067.7  415.91
  5242.6  419.04  5555.5  419.95  5592.4  419.24  5678.3  420.46  5707.6  420.76
  5730.4  422.21  5804.8  424.29  5812.1  424.67  5819.9  426.99  5870.4  427.84
#Mann=6,-1,0
  3484.1    0.05       0  4983.7    0.03       0  4987.7    0.05       0
  5678.3   0.075       0  5707.6    0.05       0  5804.8   0.075       0
Bank Sta=4983.7,4987.7
Exp/Cntr=0.3,0.1

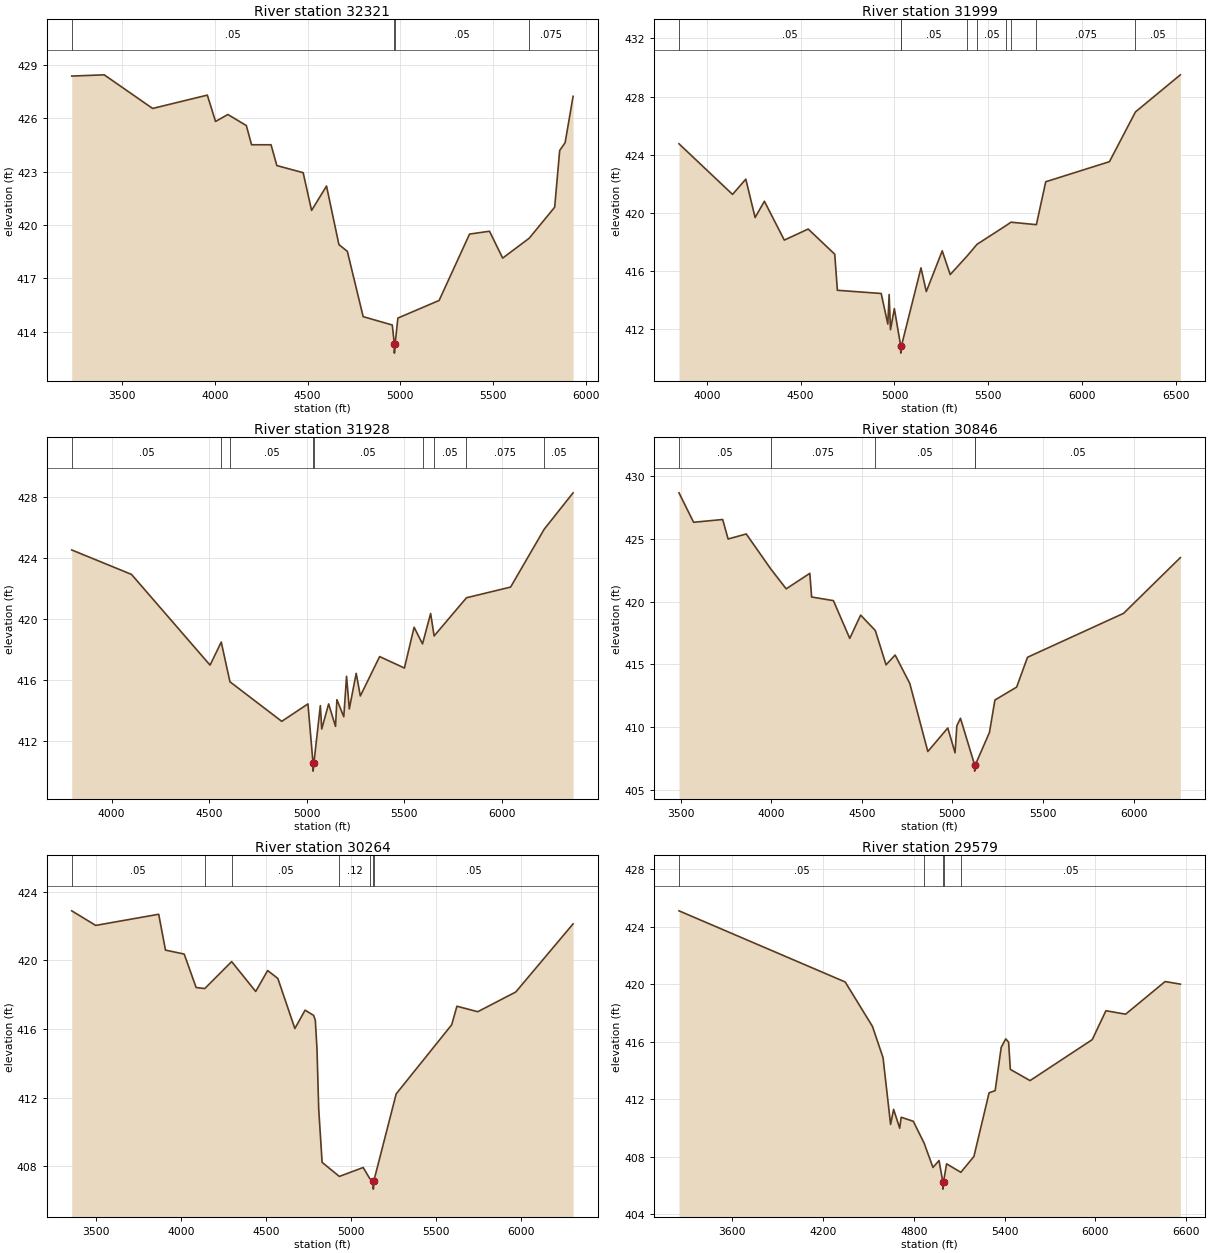
Type RM Length L Ch R = 1,32321,322,322,322
BEGIN DESCRIPTION:
Prairie Branch 63.0
END DESCRIPTION:
XS GIS Cut Line= 3
      2649775.80      6899799.11      2648176.00      6900561.00
      2647626.01      6901310.99
#Sta/Elev= 30
  3228.5  428.37  3403.6  428.44  3664.5  426.55  3959.3  427.30  4003.6  425.82
  4070.1  426.21  4169.5  425.59  4197.8  424.51  4302.7  424.51  4334.0  423.34
  4475.8  422.94  4521.2  420.82  4601.7  422.19  4668.5  418.90  4713.9  418.52
  4799.2  414.85  4956.2  414.38  4967.2  413.30  4967.4  412.80  4971.2  413.30
  4986.3  414.77  5208.5  415.76  5372.5  419.49  5480.1  419.65  5551.2  418.14
  5694.3  419.26  5831.3  421.00  5858.4  424.19  5887.7  424.63  5930.5  427.23
#Mann=4,-1,0
  3228.5    0.05       0  4967.2    0.03       0  4971.2    0.05       0
  5694.3   0.075       0
Bank Sta=4967.2,4971.2
Exp/Cntr=0.3,0.1

Type RM Length L Ch R = 1,31999,71,71,71
BEGIN DESCRIPTION:
Mapping XS 6388923d
END DESCRIPTION:
XS GIS Cut Line= 3
      2648741.08      6899552.60      2647930.17      6900365.21
      2646855.66      6901444.96
#Sta/Elev= 30
  3852.0  424.76  4137.3  421.28  4208.0  422.33  4257.5  419.69  4307.0  420.81
  4413.1  418.14  4540.4  418.90  4681.8  417.17  4695.9  414.69  4929.3  414.47
  4964.6  412.37  4971.7  414.40  4978.8  411.98  4999.4  413.43  5033.3  410.87
  5033.6  410.37  5037.3  410.87  5141.4  416.23  5169.7  414.60  5254.5  417.40
  5297.0  415.77  5386.8  417.04  5439.9  417.85  5596.1  419.15  5621.0  419.37
  5756.2  419.20  5806.1  422.15  6145.5  423.53  6284.1  426.95  6523.3  429.50
#Mann=9,-1,0
  3852.0    0.05       0  5033.3    0.03       0  5037.3    0.05       0
  5386.8     0.1       0  5439.9    0.05       0  5596.1   0.075       0
  5621.0    0.05       0  5756.2   0.075       0  6284.1    0.05       0
Bank Sta=5033.3,5037.3
Exp/Cntr=0.3,0.1

Type RM Length L Ch R = 1,31928,1082,1082,1082
BEGIN DESCRIPTION:
Mapping XS 0d000c1f
END DESCRIPTION:
XS GIS Cut Line= 3
      2648737.63      6899469.24      2647879.68      6900314.95
      2646908.92      6901277.12
#Sta/Elev= 30
  3795.3  424.54  4101.8  422.94  4504.8  417.00  4562.2  418.51  4606.8  415.91
  4872.5  413.32  5006.9  414.46  5033.1  410.56  5033.4  410.06  5037.1  410.56
  5070.5  414.35  5077.6  412.82  5113.0  414.46  5148.3  412.99  5155.4  414.74
  5190.7  413.62  5204.9  416.27  5219.0  414.13  5254.4  416.46  5275.6  414.98
  5374.6  417.56  5501.8  416.81  5551.4  419.48  5594.6  418.39  5636.2  420.38
  5654.1  418.91  5820.1  421.41  6046.4  422.11  6218.8  425.90  6366.8  428.28
#Mann=9,-1,0
  3795.3    0.05       0  4562.2   0.075       0  4606.8    0.05       0
  5033.1    0.03       0  5037.1    0.05       0  5594.6   0.075       0
  5654.1    0.05       0  5820.1   0.075       0  6218.8    0.05       0
Bank Sta=5033.1,5037.1
Exp/Cntr=0.3,0.1

Type RM Length L Ch R = 1,30846,582,582,582
BEGIN DESCRIPTION:
Mapping XS fdd8cb01
END DESCRIPTION:
XS GIS Cut Line= 3
      2649126.48      6899455.35      2647629.99      6899361.60
      2646362.62      6899358.13
#Sta/Elev= 30
  3491.6  428.64  3572.2  426.30  3732.6  426.52  3762.6  424.97  3862.8  425.37
  3998.6  422.58  4083.2  421.01  4213.5  422.24  4223.5  420.36  4343.8  420.07
  4433.9  417.07  4494.0  418.92  4574.9  417.70  4634.3  414.97  4684.4  415.75
  4765.2  413.49  4864.8  408.08  4975.0  409.95  5015.0  407.98  5025.0  410.13
  5045.0  410.72  5123.0  407.02  5123.3  406.52  5127.0  407.02  5205.0  409.60
  5235.0  412.17  5355.0  413.20  5415.0  415.57  5945.0  419.06  6258.4  423.49
#Mann=5,-1,0
  3491.6    0.05       0  3998.6   0.075       0  4574.9    0.05       0
  5123.0    0.03       0  5127.0    0.05       0
Bank Sta=5123,5127
Exp/Cntr=0.3,0.1

Type RM Length L Ch R = 1,30264,685,685,685
BEGIN DESCRIPTION:
Prairie Branch 58.0
END DESCRIPTION:
XS GIS Cut Line= 3
      2649216.76      6898934.52      2647575.92      6898826.39
      2646296.66      6899094.24
#Sta/Elev= 30
  3355.6  422.88  3496.7  422.03  3867.5  422.68  3907.6  420.59  4017.8  420.36
  4087.9  418.41  4138.6  418.35  4297.1  419.92  4438.7  418.18  4508.9  419.40
  4569.0  418.94  4669.2  416.02  4729.3  417.09  4779.4  416.79  4789.5  416.51
  4799.5  414.83  4809.5  411.34  4829.6  408.22  4931.0  407.40  5071.4  407.92
  5110.5  407.27  5130.7  407.16  5131.0  406.66  5134.7  407.16  5265.6  412.21
  5592.5  416.24  5623.1  417.32  5745.8  417.00  5969.7  418.15  6307.0  422.12
#Mann=7,-1,0
  3355.6    0.05       0  4138.6   0.075       0  4297.1    0.05       0
  4931.0    0.12       0  5110.5    0.05       0  5130.7    0.07       0
  5134.7    0.05       0
Bank Sta=5130.7,5134.7
Exp/Cntr=0.3,0.1

Type RM Length L Ch R = 1,29579,742,742,742
BEGIN DESCRIPTION:
Prairie Branch 57.0
END DESCRIPTION:
XS GIS Cut Line= 3
      2649324.40      6898267.85      2647576.00      6898211.00
      2646015.42      6898337.29
#Sta/Elev= 30
  3246.9  425.12  4345.9  420.17  4526.0  417.08  4596.0  414.91  4646.0  410.26
  4666.0  411.31  4706.1  410.00  4716.1  410.76  4796.1  410.48  4867.7  408.96
  4926.2  407.27  4966.2  407.75  4991.6  406.26  4991.9  405.76  4995.9  406.26
  5016.3  407.52  5110.4  406.93  5196.9  408.03  5297.2  412.46  5337.3  412.61
  5377.5  415.63  5407.6  416.21  5426.4  415.98  5437.7  414.09  5568.1  413.31
  5979.4  416.16  6069.7  418.17  6200.1  417.93  6461.0  420.20  6561.9  420.02
#Mann=5,-1,0
  3246.9    0.05       0  4867.7    0.12       0  4991.6    0.07       0
  4995.9    0.12       0  5110.4    0.05       0
Bank Sta=4991.6,4995.9
Exp/Cntr=0.3,0.1

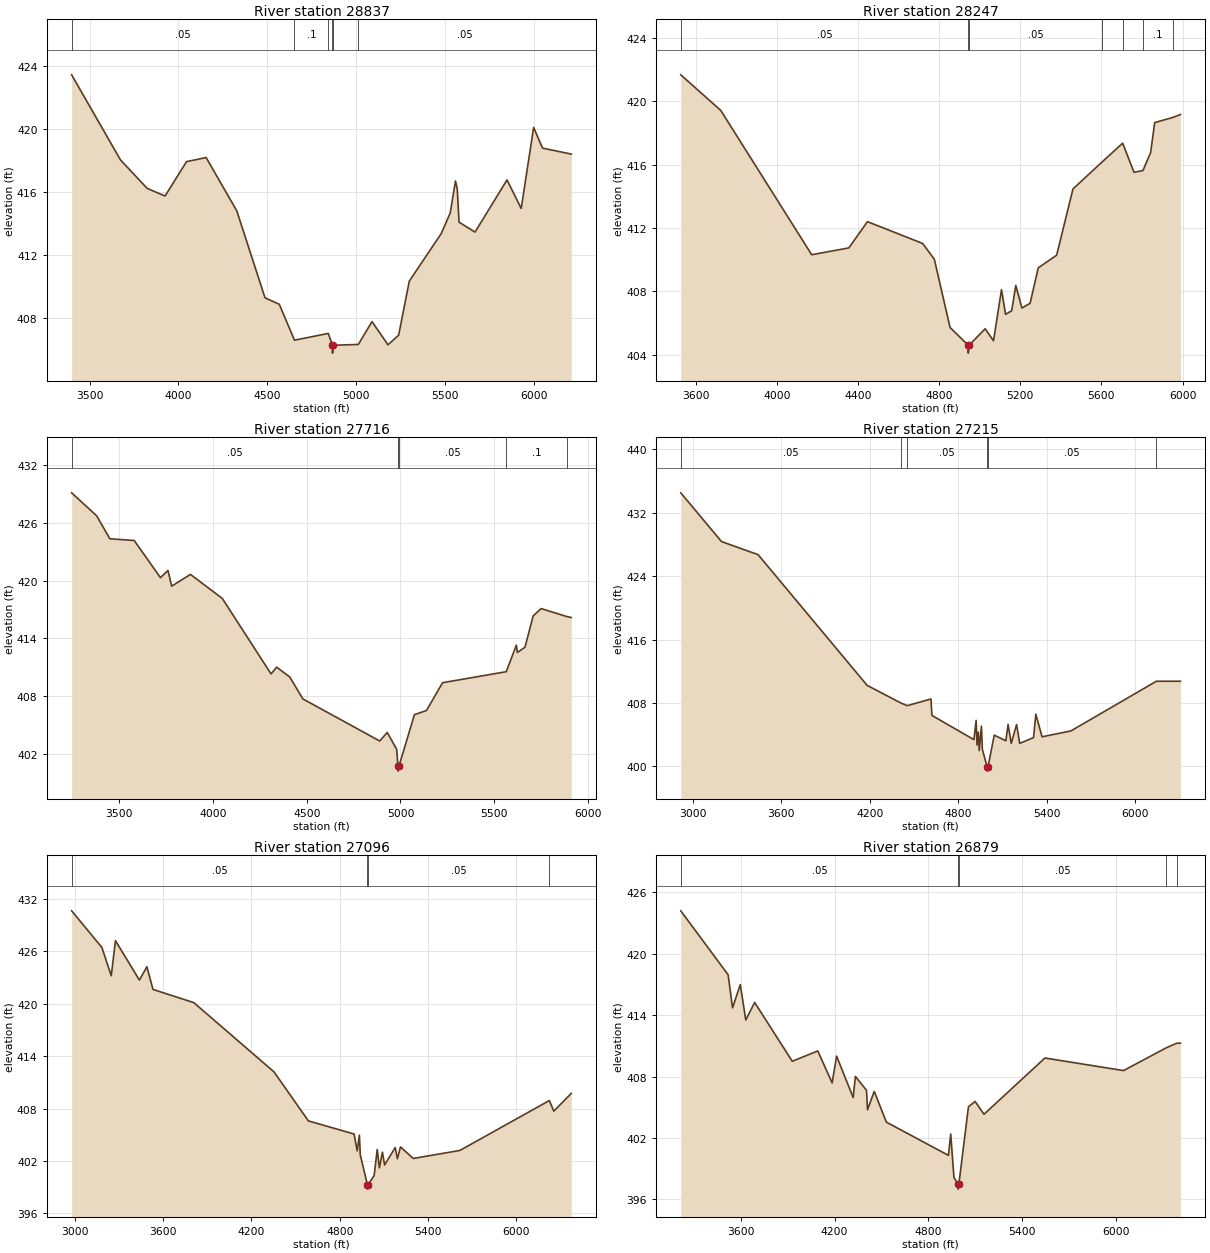
Type RM Length L Ch R = 1,28837,590,590,590
BEGIN DESCRIPTION:
Prairie Branch 56.0
END DESCRIPTION:
XS GIS Cut Line= 3
      2649119.59      6897785.21      2647525.93      6897631.03
      2646314.03      6897628.96
#Sta/Elev= 30
  3398.9  423.44  3673.8  418.04  3824.5  416.23  3924.9  415.75  4045.5  417.93
  4156.0  418.19  4328.6  414.81  4487.5  409.29  4567.9  408.88  4653.4  406.60
  4843.6  407.03  4867.1  406.28  4867.5  405.78  4871.5  406.28  5012.8  406.33
  5089.9  407.78  5179.9  406.31  5239.9  406.92  5299.9  410.35  5479.9  413.37
  5529.9  414.66  5559.9  416.70  5569.9  416.19  5579.9  414.09  5669.9  413.46
  5849.9  416.77  5929.9  414.96  5999.9  420.10  6049.9  418.79  6211.9  418.41
#Mann=6,-1,0
  3398.9    0.05       0  4653.4     0.1       0  4843.6    0.12       0
  4867.1    0.07       0  4871.5    0.12       0  5012.8    0.05       0
Bank Sta=4867.1,4871.5
Exp/Cntr=0.3,0.1

Type RM Length L Ch R = 1,28247,531,531,531
BEGIN DESCRIPTION:
Mapping XS 3566b5ca
END DESCRIPTION:
XS GIS Cut Line= 3
      2649039.69      6897368.54      2647574.44      6897090.77
      2646610.06      6897201.78
#Sta/Elev= 30
  3527.3  421.68  3724.4  419.43  4172.3  410.31  4355.5  410.74  4447.1  412.40
  4719.5  411.02  4776.8  410.02  4854.2  405.71  4943.6  404.59  4944.0  404.09
  4948.1  404.59  5027.1  405.63  5068.4  404.87  5107.7  408.10  5127.8  406.54
  5158.0  406.77  5178.1  408.37  5208.3  406.94  5248.6  407.24  5288.9  409.48
  5379.5  410.28  5460.0  414.47  5604.9  416.19  5704.8  417.36  5760.5  415.52
  5804.7  415.63  5842.5  416.76  5862.6  418.66  5950.4  418.98  5989.4  419.17
#Mann=7,-1,0
  3527.3    0.05       0  4943.6    0.03       0  4948.1    0.05       0
  5604.9     0.1       0  5704.8    0.05       0  5804.7     0.1       0
  5950.4    0.05       0
Bank Sta=4943.6,4948.1
Exp/Cntr=0.3,0.1

Type RM Length L Ch R = 1,27716,501,501,501
BEGIN DESCRIPTION:
Prairie Branch 54.0
END DESCRIPTION:
XS GIS Cut Line= 3
      2649379.95      6896608.13      2647626.00      6896611.00
      2646775.82      6896941.47
#Sta/Elev= 30
  3245.6  429.09  3379.5  426.70  3449.5  424.33  3579.5  424.15  3719.5  420.30
  3759.5  421.05  3779.5  419.42  3879.5  420.64  4049.5  418.15  4309.5  410.33
  4339.5  411.03  4409.5  410.01  4479.5  407.74  4889.5  403.38  4929.5  404.27
  4979.5  402.54  4987.2  400.76  4987.7  400.26  4991.9  400.76  5074.7  406.11
  5139.0  406.54  5224.9  409.42  5564.6  410.56  5618.5  413.31  5623.9  412.55
  5664.7  413.10  5708.2  416.33  5750.6  417.10  5886.3  416.28  5911.7  416.17
#Mann=5,-1,0
  3245.6    0.05       0  4987.2    0.03       0  4991.9    0.05       0
  5564.6     0.1       0  5886.3    0.05       0
Bank Sta=4987.2,4991.9
Exp/Cntr=0.3,0.1

Type RM Length L Ch R = 1,27215,119,119,119
BEGIN DESCRIPTION:
Mapping XS 99897f12
END DESCRIPTION:
XS GIS Cut Line= 6
      2649046.66      6894753.96      2648418.19      6895538.68
      2647727.21      6896122.02      2647560.55      6896236.60
      2647187.29      6896473.98      2646504.97      6896955.37
#Sta/Elev= 30
  2917.7  434.52  3194.0  428.37  3442.1  426.72  4181.8  410.23  4409.2  408.02
  4453.4  407.67  4614.8  408.51  4621.3  406.44  4906.3  403.38  4921.2  405.81
  4927.3  402.70  4936.1  404.33  4942.2  402.01  4957.1  405.09  4963.2  402.17
  4996.6  399.91  4997.2  399.41  5001.5  399.91  5044.0  403.95  5122.8  403.24
  5138.0  405.31  5159.2  402.91  5195.6  405.29  5216.8  402.91  5310.8  403.64
  5326.0  406.60  5368.3  403.74  5563.8  404.48  6144.0  410.75  6307.0  410.75
#Mann=6,-1,0
  2917.7    0.05       0  4409.2   0.075       0  4453.4    0.05       0
  4996.6    0.03       0  5001.5    0.05       0  6144.0   0.075       0
Bank Sta=4996.6,5001.5
Exp/Cntr=0.3,0.1

Type RM Length L Ch R = 1,27096,217,217,217
BEGIN DESCRIPTION:
Mapping XS 475be1bb
END DESCRIPTION:
XS GIS Cut Line= 6
      2648952.89      6894708.84      2648414.71      6895351.18
      2647844.84      6895907.58      2647542.76      6896108.10
      2646750.43      6896657.56      2646405.07      6896916.58
#Sta/Elev= 30
  2979.7  430.65  3184.9  426.46  3248.7  423.22  3277.3  427.23  3439.9  422.72
  3490.6  424.25  3532.3  421.65  3809.4  420.14  4354.1  412.21  4587.4  406.60
  4897.7  405.10  4918.8  403.17  4933.8  404.97  4939.8  402.70  4988.2  399.29
  4988.8  398.79  4993.1  399.29  5034.0  400.34  5054.9  403.33  5069.3  401.22
  5090.2  403.02  5105.1  401.56  5176.9  403.55  5191.8  402.27  5212.8  403.62
  5299.4  402.30  5616.4  403.22  6223.7  408.93  6254.0  407.72  6372.8  409.75
#Mann=4,-1,0
  2979.7    0.05       0  4988.2    0.05       0  4993.1    0.05       0
  6223.7   0.075       0
Bank Sta=4988.2,4993.1
Exp/Cntr=0.3,0.1

Type RM Length L Ch R = 1,26879,421,421,421
BEGIN DESCRIPTION:
Mapping XS d614740c
END DESCRIPTION:
XS GIS Cut Line= 4
      2648626.52      6894594.24      2647558.38      6895787.26
      2647446.09      6895930.96      2646388.37      6896867.28
#Sta/Elev= 30
  3216.3  424.20  3519.2  417.95  3547.5  414.71  3596.9  416.99  3632.1  413.53
  3688.9  415.24  3929.6  409.49  4092.6  410.50  4184.6  407.38  4213.0  409.99
  4319.1  405.95  4333.3  408.01  4404.4  406.65  4411.1  404.75  4453.7  406.55
  4531.5  403.54  4928.7  400.29  4943.1  402.38  4963.9  398.12  4990.4  397.49
  4991.0  396.99  4995.4  397.49  5056.5  405.04  5099.2  405.56  5156.1  404.31
  5545.9  409.81  6048.5  408.58  6321.2  410.80  6389.8  411.26  6412.6  411.26
#Mann=5,-1,0
  3216.3    0.05       0  4990.4    0.03       0  4995.4    0.05       0
  6321.2   0.075       0  6389.8    0.05       0
Bank Sta=4990.4,4995.4
Exp/Cntr=0.3,0.1

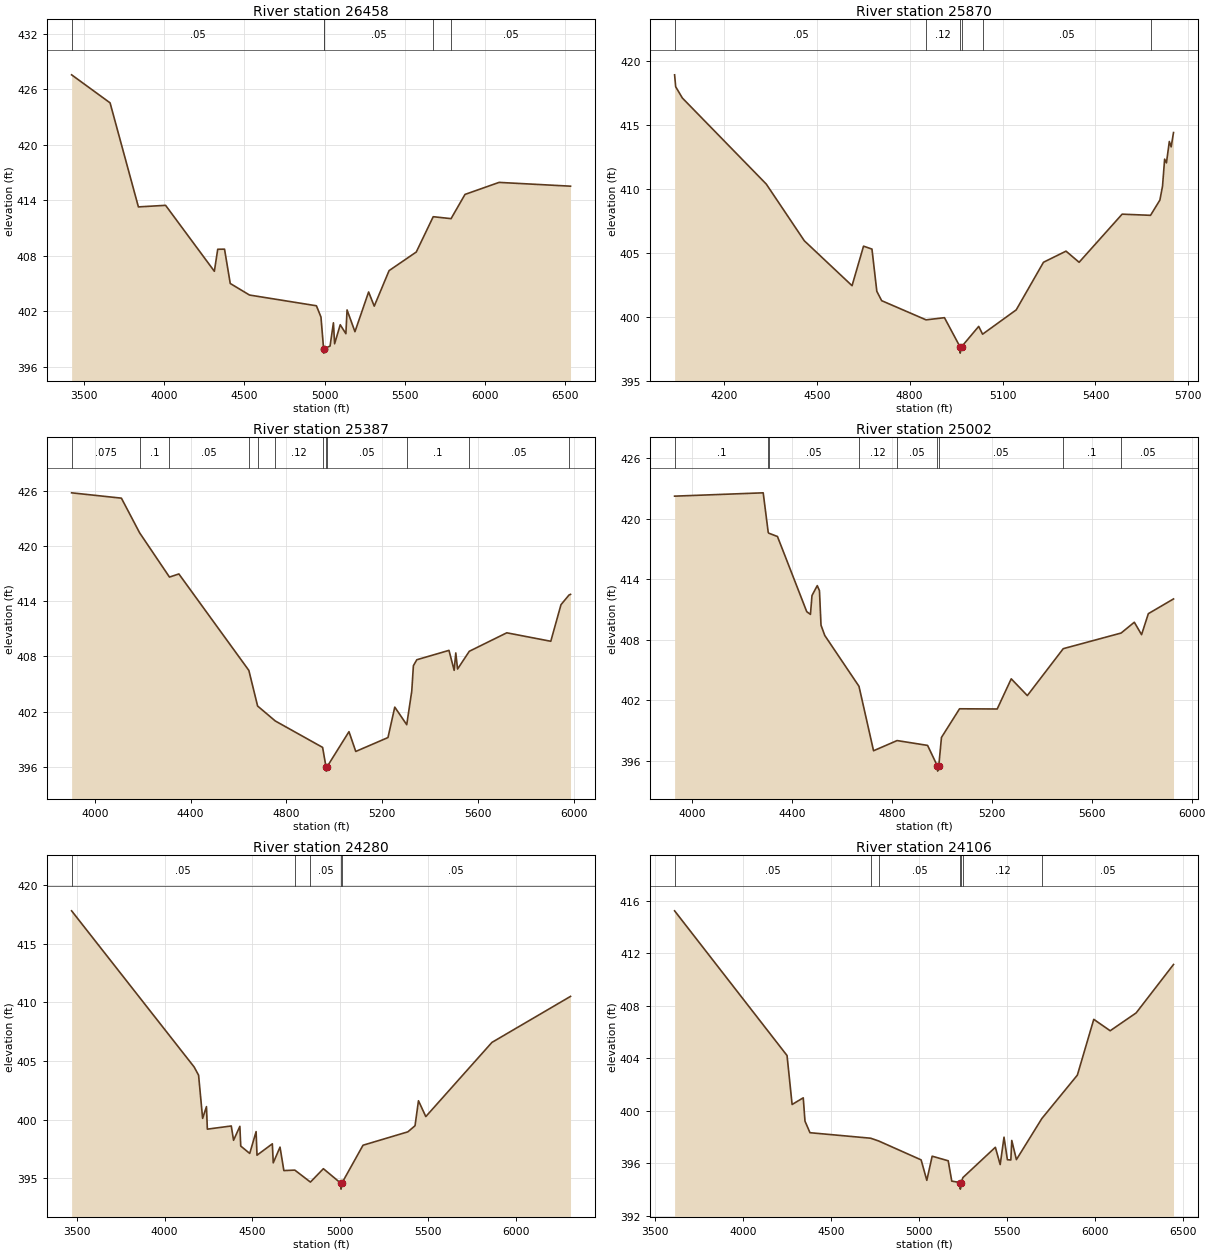
Type RM Length L Ch R = 1,26458,588,588,588
BEGIN DESCRIPTION:
Mapping XS 90ef55b0
END DESCRIPTION:
XS GIS Cut Line= 5
      2648501.49      6894427.60      2647748.49      6895130.62
      2647375.95      6895532.97      2646708.38      6896267.73
      2646317.49      6896642.85
#Sta/Elev= 30
  3421.5  427.58  3661.5  424.55  3838.3  413.30  4007.9  413.47  4312.2  406.34
  4333.2  408.72  4375.7  408.73  4411.4  405.02  4531.7  403.77  4949.0  402.61
  4977.4  401.39  4993.7  397.99  4994.4  397.49  4998.8  397.99  5034.1  398.25
  5055.1  400.77  5062.5  398.50  5097.6  400.56  5132.8  399.59  5140.2  402.16
  5189.5  399.81  5274.7  404.10  5309.8  402.57  5402.4  406.41  5572.0  408.42
  5677.8  412.24  5789.1  412.03  5876.1  414.65  6088.7  415.95  6534.5  415.54
#Mann=5,-1,0
  3421.5    0.05       0  4993.7    0.05       0  4998.8    0.05       0
  5677.8   0.075       0  5789.1    0.05       0
Bank Sta=4993.7,4998.8
Exp/Cntr=0.3,0.1

Type RM Length L Ch R = 1,25870,483,483,483
BEGIN DESCRIPTION:
Prairie Branch 50.0
END DESCRIPTION:
XS GIS Cut Line= 3
      2648251.52      6894472.71      2647426.00      6894961.00
      2646876.04      6895310.98
#Sta/Elev= 30
  4040.9  418.90  4044.4  417.97  4065.9  417.09  4337.0  410.36  4459.8  405.93
  4613.9  402.42  4651.0  405.51  4678.2  405.28  4693.9  401.98  4709.5  401.25
  4852.9  399.75  4912.3  399.92  4962.4  397.65  4963.1  397.15  4967.6  397.65
  5022.9  399.24  5035.4  398.63  5144.0  400.53  5232.0  404.25  5304.8  405.12
  5347.1  404.25  5486.0  408.01  5577.7  407.92  5607.9  409.11  5616.4  410.19
  5623.2  412.31  5629.1  412.02  5638.4  413.69  5644.3  413.27  5651.9  414.39
#Mann=6,-1,0
  4040.9    0.05       0  4852.9    0.12       0  4962.4    0.07       0
  4967.6    0.12       0  5035.4    0.05       0  5577.7     0.1       0
Bank Sta=4962.4,4967.6
Exp/Cntr=0.3,0.1

Type RM Length L Ch R = 1,25387,385,385,385
BEGIN DESCRIPTION:
Prairie Branch 49.0
END DESCRIPTION:
XS GIS Cut Line= 3
      2648324.42      6894045.64      2647326.00      6894511.00
      2646664.97      6895236.32
#Sta/Elev= 30
  3903.0  425.78  4110.9  425.20  4187.0  421.43  4311.6  416.62  4350.8  416.96
  4643.0  406.47  4679.5  402.60  4753.5  400.97  4950.9  398.10  4964.8  396.02
  4965.6  395.52  4970.1  396.02  5061.0  399.81  5089.3  397.66  5223.8  399.17
  5252.2  402.48  5302.1  400.57  5323.1  404.22  5329.9  406.98  5344.1  407.63
  5478.5  408.65  5500.1  406.48  5506.9  408.37  5514.3  406.62  5563.3  408.55
  5719.7  410.56  5903.5  409.64  5946.1  413.62  5979.7  414.67  5985.9  414.74
#Mann=12,-1,0
  3903.0   0.075       0  4187.0     0.1       0  4311.6    0.05       0
  4643.0    0.12       0  4679.5    0.05       0  4753.5    0.12       0
  4950.9    0.05       0  4964.8    0.03       0  4970.1    0.05       0
  5302.1     0.1       0  5563.3    0.05       0  5979.7   0.075       0
Bank Sta=4964.8,4970.1
Exp/Cntr=0.3,0.1

Type RM Length L Ch R = 1,25002,722,722,722
BEGIN DESCRIPTION:
Prairie Branch 48.0
END DESCRIPTION:
XS GIS Cut Line= 3
      2648077.87      6893580.38      2647189.40      6894174.30
      2646626.02      6894910.97
#Sta/Elev= 30
  3931.3  422.22  4285.8  422.55  4305.9  418.63  4308.1  418.55  4342.9  418.22
  4460.0  410.77  4474.8  410.50  4481.0  412.37  4502.1  413.35  4510.9  412.85
  4517.1  409.43  4532.1  408.41  4669.0  403.37  4727.3  396.98  4821.5  397.99
  4943.5  397.51  4982.9  395.46  4983.7  394.96  4988.2  395.46  4999.0  398.30
  5071.4  401.14  5222.0  401.12  5278.2  404.11  5342.6  402.45  5486.3  407.10
  5717.8  408.65  5770.6  409.72  5799.6  408.49  5826.7  410.57  5927.4  412.03
#Mann=9,-1,0
  3931.3     0.1       0  4305.9   0.075       0  4308.1    0.05       0
  4669.0    0.12       0  4821.5    0.05       0  4982.9    0.03       0
  4988.2    0.05       0  5486.3     0.1       0  5717.8    0.05       0
Bank Sta=4982.9,4988.2
Exp/Cntr=0.3,0.1

Type RM Length L Ch R = 1,24280,174,174,174
BEGIN DESCRIPTION:
Mapping XS e6003fea
END DESCRIPTION:
XS GIS Cut Line= 5
      2647848.74      6892615.07      2647116.10      6892771.32
      2646949.44      6893528.27      2646786.24      6894267.85
      2646664.77      6894816.19
#Sta/Elev= 30
  3470.2  417.79  4168.3  404.49  4193.8  403.79  4216.8  400.11  4238.7  401.11
  4243.8  399.19  4380.1  399.46  4393.1  398.24  4429.0  399.43  4434.1  397.75
  4485.2  397.12  4521.6  398.98  4526.7  396.97  4614.1  397.94  4619.3  396.32
  4657.9  397.66  4679.8  395.66  4742.2  395.70  4831.2  394.68  4905.0  395.82
  5004.7  394.58  5005.5  394.08  5010.1  394.58  5130.9  397.82  5386.3  398.96
  5427.3  399.48  5446.9  401.61  5488.7  400.26  5865.5  406.58  6313.4  410.50
#Mann=5,-1,0
  3470.2    0.05       0  4742.2    0.12       0  4831.2    0.05       0
  5004.7    0.03       0  5010.1    0.05       0
Bank Sta=5004.7,5010.1
Exp/Cntr=0.3,0.1

Type RM Length L Ch R = 1,24106,562,562,562
BEGIN DESCRIPTION:
Mapping XS 1fe9d95c
END DESCRIPTION:
XS GIS Cut Line= 5
      2647758.43      6892563.00      2647017.41      6892772.94
      2646893.23      6893377.43      2646845.54      6893689.61
      2646605.69      6894792.12
#Sta/Elev= 30
  3612.7  415.25  4250.9  404.22  4279.6  400.49  4342.8  401.00  4352.7  399.22
  4381.0  398.34  4725.4  397.92  4770.8  397.71  5011.7  396.27  5044.1  394.71
  5074.4  396.55  5165.5  396.20  5185.7  394.65  5233.5  394.54  5234.3  394.04
  5239.0  394.54  5248.9  394.92  5433.1  397.23  5460.5  395.91  5482.2  398.00
  5501.4  396.28  5521.0  396.26  5526.2  397.75  5552.6  396.29  5696.9  399.42
  5898.5  402.73  5991.6  406.98  6084.7  406.11  6232.1  407.47  6444.1  411.16
#Mann=7,-1,0
  3612.7    0.05       0  4725.4    0.12       0  4770.8    0.05       0
  5233.5    0.03       0  5239.0    0.05       0  5248.9    0.12       0
  5696.9    0.05       0
Bank Sta=5233.5,5239
Exp/Cntr=0.3,0.1

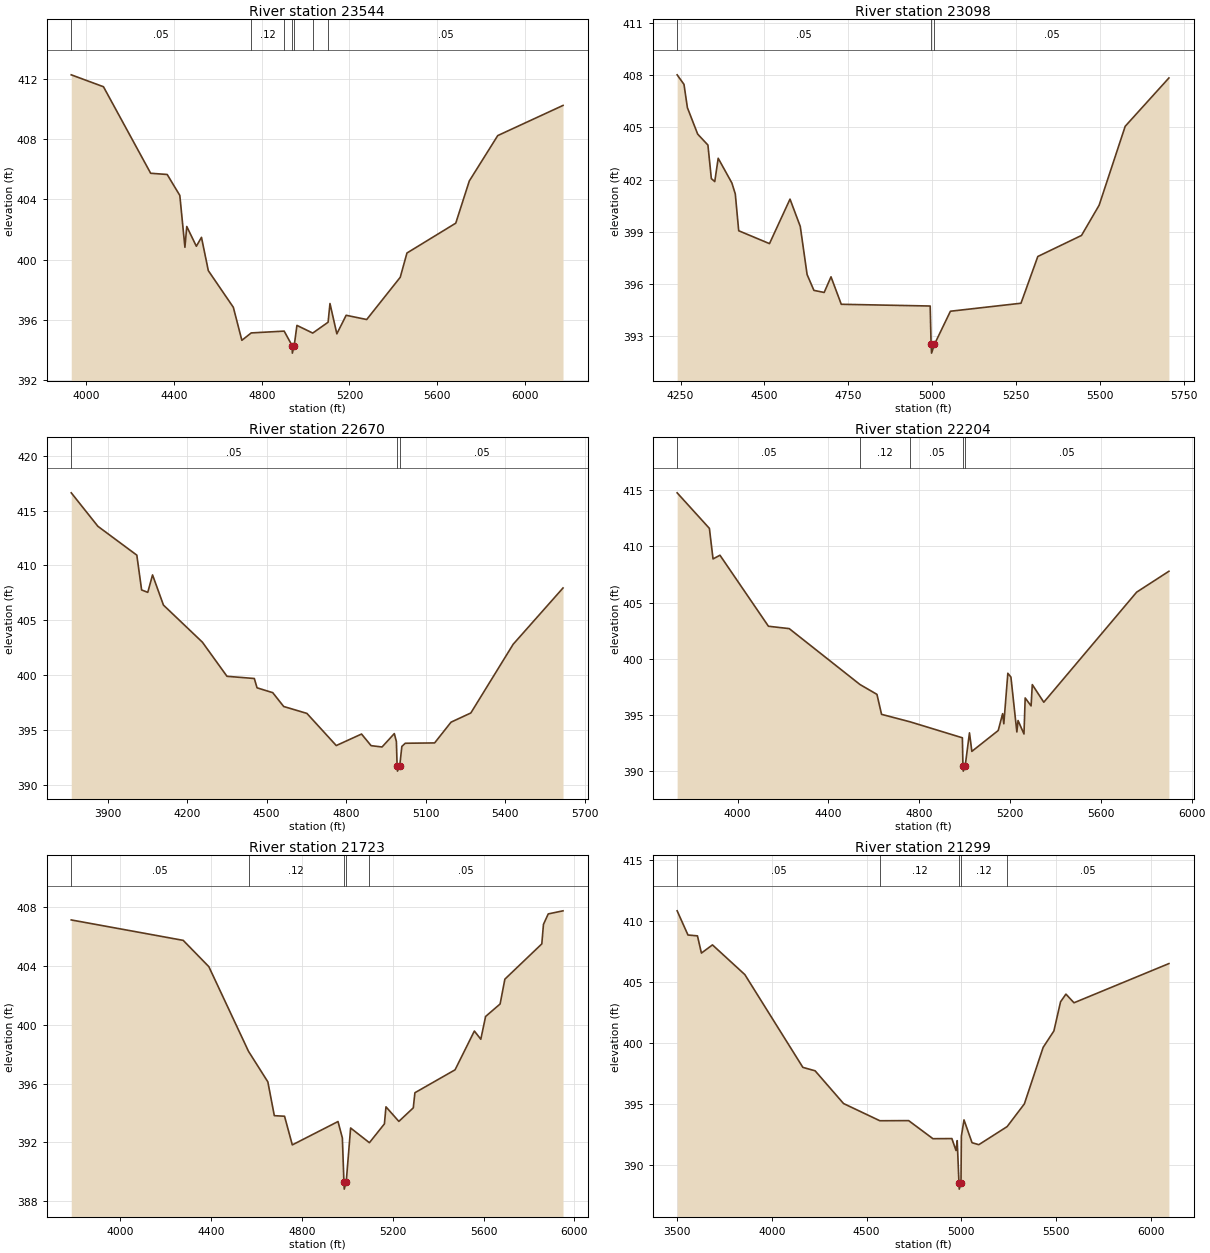
Type RM Length L Ch R = 1,23544,446,446,446
BEGIN DESCRIPTION:
Prairie Branch 45.0
END DESCRIPTION:
XS GIS Cut Line= 3
      2647608.31      6892477.91      2646626.00      6892911.00
      2645526.02      6893310.99
#Sta/Elev= 30
  3930.6  412.25  4077.6  411.46  4293.0  405.72  4368.4  405.64  4426.0  404.25
  4449.3  400.81  4457.7  402.19  4501.4  400.88  4524.8  401.47  4556.1  399.26
  4670.2  396.83  4709.1  394.64  4751.8  395.13  4902.2  395.25  4938.3  394.29
  4939.6  393.79  4948.0  394.29  4960.4  395.63  5032.5  395.12  5102.6  395.84
  5111.2  397.08  5142.5  395.07  5185.0  396.30  5278.8  396.02  5431.8  398.82
  5462.4  400.43  5685.1  402.41  5747.0  405.21  5876.7  408.22  6174.6  410.22
#Mann=7,-1,0
  3930.6    0.05       0  4751.8    0.12       0  4902.2    0.05       0
  4938.3    0.05       0  4948.0    0.05       0  5032.5    0.12       0
  5102.6    0.05       0
Bank Sta=4938.3,4948
Exp/Cntr=0.3,0.1

Type RM Length L Ch R = 1,23098,428,428,428
BEGIN DESCRIPTION:
Prairie Branch 44.0
END DESCRIPTION:
XS GIS Cut Line= 3
      2647226.03      6892360.99      2646476.00      6892511.00
      2645775.96      6892561.00
#Sta/Elev= 30
  4239.8  408.03  4260.2  407.48  4270.4  406.14  4301.0  404.62  4331.6  403.99
  4341.8  402.06  4352.0  401.89  4362.2  403.23  4403.0  401.81  4413.2  401.18
  4423.4  399.06  4515.2  398.32  4576.4  400.88  4607.0  399.31  4627.4  396.54
  4647.7  395.63  4678.3  395.51  4698.7  396.41  4729.3  394.83  4994.5  394.73
  4997.2  392.52  4998.6  392.02  5007.1  392.52  5054.8  394.43  5265.3  394.89
  5315.5  397.58  5445.8  398.79  5498.4  400.53  5576.1  405.07  5706.5  407.85
#Mann=3,-1,0
  4239.8    0.05       0  4997.2    0.03       0  5007.1    0.05       0
Bank Sta=4997.2,5007.1
Exp/Cntr=0.3,0.1

Type RM Length L Ch R = 1,22670,466,466,466
BEGIN DESCRIPTION:
Prairie Branch 43.0
END DESCRIPTION:
XS GIS Cut Line= 3
      2647526.04      6891860.99      2646326.00      6892161.00
      2645726.04      6892310.99
#Sta/Elev= 30
  3763.1  416.62  3863.6  413.57  4010.5  410.94  4028.6  407.77  4051.8  407.55
  4069.8  409.14  4111.0  406.39  4257.9  403.01  4350.7  399.90  4453.8  399.70
  4464.1  398.85  4523.3  398.41  4564.6  397.15  4652.2  396.52  4763.0  393.59
  4858.3  394.64  4894.4  393.58  4935.7  393.46  4982.0  394.68  4989.8  393.96
  4992.5  391.76  4993.9  391.26  5002.5  391.76  5010.4  393.51  5023.3  393.80
  5134.1  393.83  5195.9  395.72  5270.7  396.56  5430.4  402.82  5618.5  407.95
#Mann=3,-1,0
  3763.1    0.05       0  4992.5    0.03       0  5002.5    0.05       0
Bank Sta=4992.5,5002.5
Exp/Cntr=0.3,0.1

Type RM Length L Ch R = 1,22204,481,481,481
BEGIN DESCRIPTION:
Prairie Branch 42.0
END DESCRIPTION:
XS GIS Cut Line= 3
      2647521.43      6891480.24      2646276.00      6891711.00
      2645424.26      6892001.06
#Sta/Elev= 30
  3733.4  414.78  3875.5  411.61  3891.5  408.89  3922.0  409.22  4135.6  402.89
  4227.1  402.68  4538.7  397.70  4613.6  396.82  4633.9  395.04  4760.2  394.37
  4989.9  392.95  4992.4  390.48  4993.9  389.98  5002.5  390.48  5021.2  393.39
  5031.7  391.74  5147.9  393.60  5167.2  395.10  5172.5  394.20  5190.2  398.70
  5203.8  398.36  5229.9  393.47  5235.2  394.49  5261.3  393.29  5266.6  396.50
  5292.6  395.79  5297.9  397.69  5348.6  396.12  5757.7  405.93  5899.8  407.79
#Mann=5,-1,0
  3733.4    0.05       0  4538.7    0.12       0  4760.2    0.05       0
  4992.4    0.03       0  5002.5    0.05       0
Bank Sta=4992.4,5002.5
Exp/Cntr=0.3,0.1

Type RM Length L Ch R = 1,21723,424,424,424
BEGIN DESCRIPTION:
Prairie Branch 41.0
END DESCRIPTION:
XS GIS Cut Line= 3
      2647247.13      6890983.71      2646076.00      6891311.00
      2645386.05      6891962.87
#Sta/Elev= 30
  3784.3  407.14  4277.2  405.75  4390.1  403.96  4564.7  398.20  4649.9  396.12
  4678.4  393.82  4723.4  393.78  4757.6  391.83  4958.8  393.42  4978.0  392.30
  4984.8  389.32  4986.3  388.82  4995.0  389.32  5014.3  392.98  5097.0  391.98
  5163.1  393.26  5170.0  394.42  5226.7  393.43  5290.2  394.35  5297.4  395.38
  5474.2  396.94  5559.2  399.58  5587.5  399.02  5608.6  400.57  5672.5  401.42
  5693.5  403.11  5856.1  405.51  5863.4  406.84  5884.5  407.55  5949.5  407.76
#Mann=5,-1,0
  3784.3    0.05       0  4564.7    0.12       0  4984.8    0.07       0
  4995.0    0.12       0  5097.0    0.05       0
Bank Sta=4984.8,4995
Exp/Cntr=0.3,0.1

Type RM Length L Ch R = 1,21299,433,433,433
BEGIN DESCRIPTION:
Prairie Branch 40.0
END DESCRIPTION:
XS GIS Cut Line= 3
      2646975.97      6890161.03      2645776.00      6891061.00
      2644973.19      6891806.31
#Sta/Elev= 30
  3499.8  410.83  3557.0  408.85  3607.0  408.78  3627.9  407.37  3686.2  408.04
  3857.0  405.61  4163.3  398.01  4227.9  397.73  4377.9  395.05  4569.6  393.64
  4721.6  393.65  4849.8  392.17  4949.8  392.18  4971.6  391.20  4977.9  392.01
  4987.2  388.54  4988.6  388.04  4997.8  388.54  4999.8  392.37  5013.7  393.71
  5056.2  391.84  5091.9  391.68  5241.4  393.16  5332.3  395.02  5431.5  399.65
  5488.1  400.99  5523.3  403.38  5551.7  404.01  5594.2  403.30  6095.2  406.51
#Mann=5,-1,0
  3499.8    0.05       0  4569.6    0.12       0  4987.2    0.07       0
  4997.8    0.12       0  5241.4    0.05       0
Bank Sta=4987.2,4997.8
Exp/Cntr=0.3,0.1