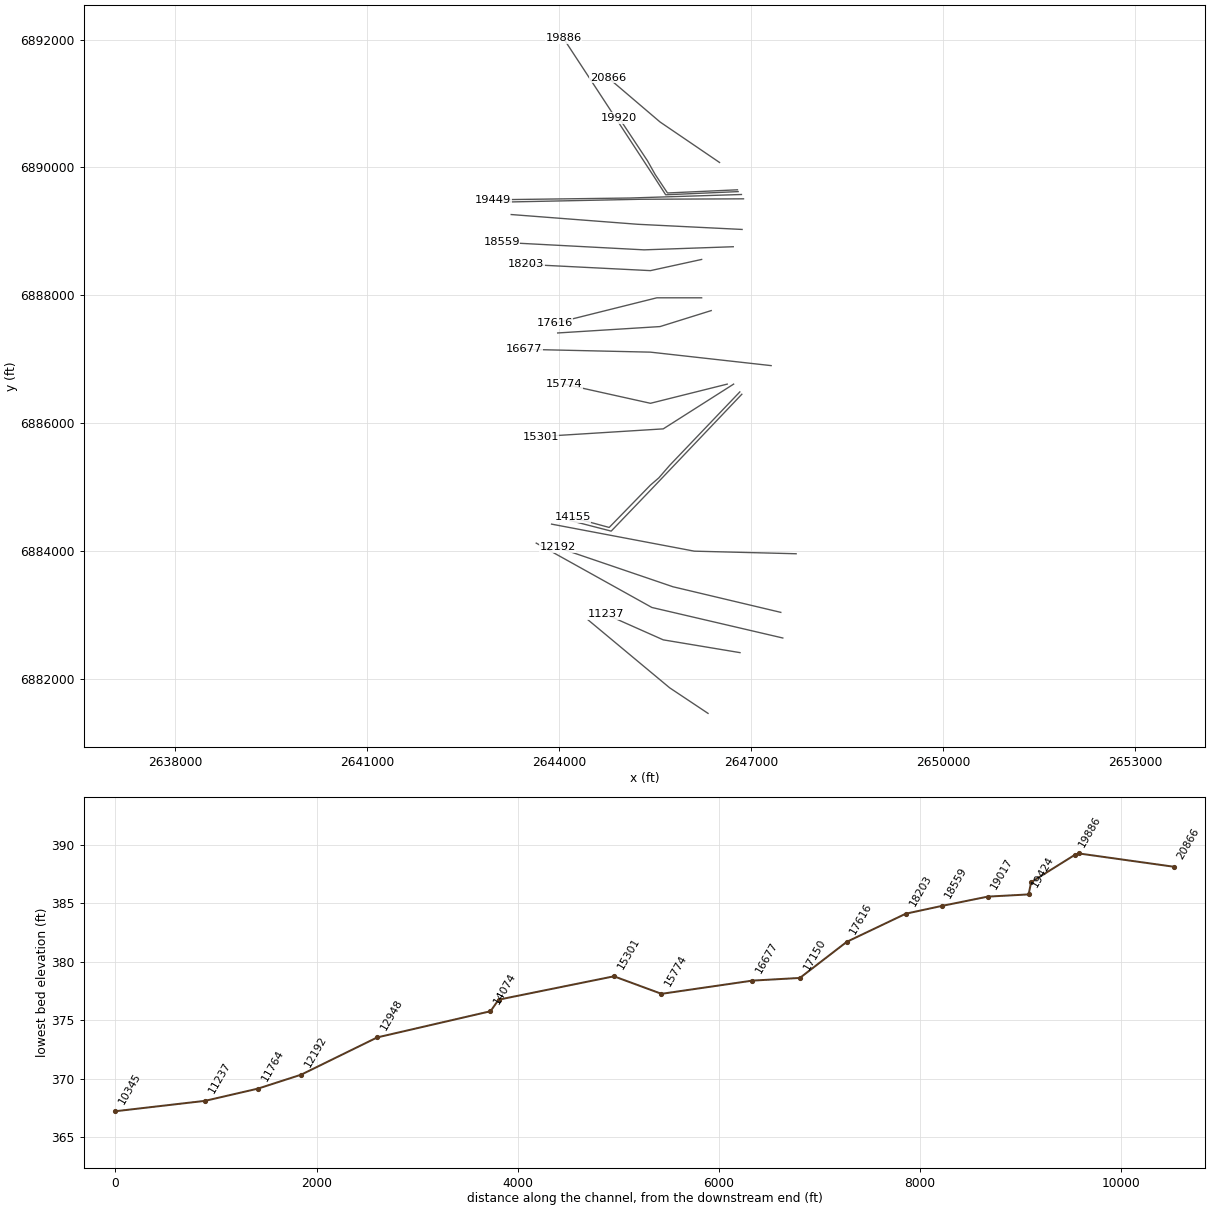
HEC-RAS study Prairie Branch.prj: Prairie Branch Base Level Engineering

--- Prairie Branch.g01 (geometry) --- (continued)

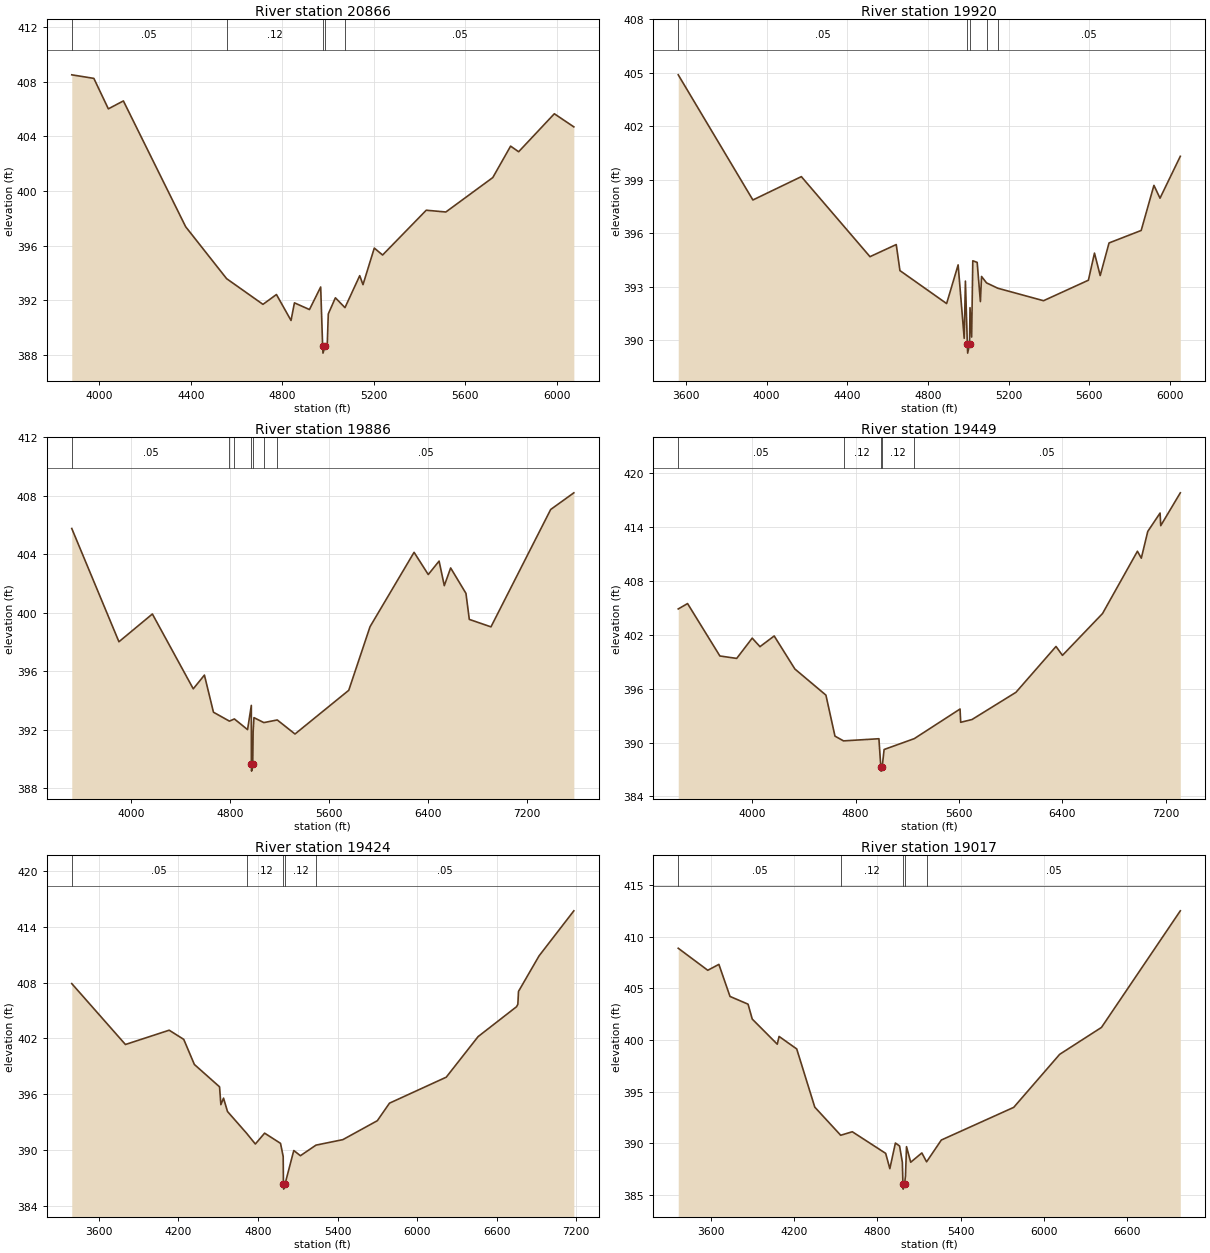
Type RM Length L Ch R = 1,20866,946,946,946
BEGIN DESCRIPTION:
Prairie Branch 39.0
END DESCRIPTION:
XS GIS Cut Line= 3
      2646505.88      6890077.74      2645576.00      6890711.00
      2644761.06      6891405.88
#Sta/Elev= 30
  3879.1  408.51  3975.7  408.25  4039.1  406.02  4104.9  406.60  4377.3  397.39
  4556.4  393.59  4715.4  391.71  4774.3  392.43  4838.1  390.53  4853.0  391.82
  4918.8  391.33  4967.8  392.98  4976.4  388.64  4977.9  388.14  4987.0  388.64
  4996.7  388.85  5001.1  391.01  5032.1  392.19  5074.1  391.47  5138.6  393.81
  5152.9  393.15  5202.3  395.83  5238.6  395.32  5429.6  398.60  5515.3  398.47
  5720.6  400.99  5798.5  403.29  5833.7  402.88  5989.8  405.66  6075.1  404.70
#Mann=5,-1,0
  3879.1    0.05       0  4556.4    0.12       0  4976.4    0.07       0
  4987.0    0.12       0  5074.1    0.05       0
Bank Sta=4976.4,4987
Exp/Cntr=0.3,0.1

Type RM Length L Ch R = 1,19920,34,34,34
BEGIN DESCRIPTION:
Mapping XS f5d1f0d2
END DESCRIPTION:
XS GIS Cut Line= 6
      2646785.84      6889650.23      2645733.29      6889602.49
      2645692.06      6889600.32      2645498.92      6889891.11
      2645379.56      6890103.79      2644936.86      6890772.18
#Sta/Elev= 30
  3561.9  404.89  3932.1  397.87  4172.4  399.18  4512.7  394.69  4642.9  395.37
  4661.2  393.91  4892.7  392.06  4949.8  394.23  4979.9  390.11  4985.9  393.32
  4995.5  389.78  4997.0  389.28  5006.4  389.78  5008.7  391.83  5016.8  390.18
  5022.5  394.46  5044.2  394.37  5060.2  392.17  5065.9  393.58  5090.7  393.22
  5146.5  392.92  5373.2  392.22  5595.8  393.37  5625.9  394.89  5654.3  393.63
  5698.1  395.46  5857.5  396.16  5920.7  398.69  5950.8  397.97  6051.5  400.32
#Mann=5,-1,0
  3561.9    0.05       0  4995.5    0.03       0  5006.4    0.05       0
  5090.7    0.12       0  5146.5    0.05       0
Bank Sta=4995.5,5006.4
Exp/Cntr=0.3,0.1

Type RM Length L Ch R = 1,19886,437,437,437
BEGIN DESCRIPTION:
Mapping XS bb793393
END DESCRIPTION:
XS GIS Cut Line= 4
      2646796.69      6889622.02      2645663.85      6889572.10
      2645477.21      6889862.90      2644066.42      6892019.33
#Sta/Elev= 30
  3521.6  405.77  3902.7  398.02  4172.9  399.92  4503.2  394.80  4593.3  395.74
  4666.4  393.20  4795.4  392.59  4835.3  392.74  4941.9  392.01  4972.3  393.67
  4972.8  389.67  4974.3  389.17  4983.7  389.67  4986.9  391.87  4993.5  392.83
  5073.6  392.49  5181.8  392.67  5325.2  391.71  5759.5  394.70  5931.3  399.05
  6287.2  404.14  6401.8  402.62  6489.3  403.54  6531.4  401.86  6582.7  403.07
  6706.4  401.33  6733.5  399.55  6908.4  399.04  7390.9  407.07  7578.0  408.21
#Mann=7,-1,0
  3521.6    0.05       0  4795.4    0.12       0  4835.3    0.05       0
  4972.8    0.03       0  4983.7    0.05       0  5073.6    0.12       0
  5181.8    0.05       0
Bank Sta=4972.8,4983.7
Exp/Cntr=0.3,0.1

Type RM Length L Ch R = 1,19449,25,25,25
BEGIN DESCRIPTION:
Mapping XS 656691a8
END DESCRIPTION:
XS GIS Cut Line= 4
      2646848.17      6889576.81      2645339.62      6889529.36
      2645116.34      6889521.83      2642964.22      6889493.98
#Sta/Elev= 30
  3427.0  404.89  3499.2  405.49  3749.3  399.65  3879.4  399.38  3999.4  401.64
  4059.5  400.69  4169.5  401.88  4329.6  398.20  4569.7  395.29  4639.8  390.72
  4705.9  390.19  4979.9  390.43  4994.4  387.32  4995.9  386.82  5005.4  387.32
  5020.0  389.23  5253.5  390.44  5607.6  393.74  5612.6  392.26  5700.1  392.57
  6040.1  395.60  6350.1  400.71  6400.1  399.72  6710.2  404.38  6980.2  411.32
  7010.2  410.55  7060.2  413.53  7155.5  415.58  7160.5  414.17  7312.0  417.83
#Mann=5,-1,0
  3427.0    0.05       0  4705.9    0.12       0  4994.4    0.07       0
  5005.4    0.12       0  5253.5    0.05       0
Bank Sta=4994.4,5005.4
Exp/Cntr=0.3,0.1

Type RM Length L Ch R = 1,19424,407,407,407
BEGIN DESCRIPTION:
Prairie Branch 36.0
END DESCRIPTION:
XS GIS Cut Line= 3
      2646880.75      6889509.10      2645275.97      6889502.15
      2643093.83      6889457.45
#Sta/Elev= 30
  3395.2  407.91  3800.0  401.35  4130.0  402.89  4240.0  401.90  4320.0  399.20
  4510.0  396.79  4520.0  394.87  4540.0  395.57  4570.0  394.13  4713.4  391.80
  4780.0  390.63  4850.0  391.80  4970.0  390.70  4990.0  389.29  4992.0  386.27
  4993.5  385.77  5003.0  386.27  5070.0  389.93  5120.0  389.37  5237.5  390.51
  5440.1  391.10  5700.1  393.14  5791.9  395.03  6220.2  397.83  6460.3  402.20
  6750.3  405.42  6760.2  405.68  6765.2  407.07  6920.4  410.90  7182.6  415.75
#Mann=5,-1,0
  3395.2    0.05       0  4713.4    0.12       0  4992.0    0.07       0
  5003.0    0.12       0  5237.5    0.05       0
Bank Sta=4992,5003
Exp/Cntr=0.3,0.1

Type RM Length L Ch R = 1,19017,458,458,458
BEGIN DESCRIPTION:
Prairie Branch 35.0
END DESCRIPTION:
XS GIS Cut Line= 3
      2646858.41      6889030.16      2645226.00      6889111.00
      2643249.67      6889263.31
#Sta/Elev= 30
  3365.2  408.88  3577.9  406.75  3658.0  407.32  3738.1  404.22  3868.2  403.47
  3898.3  402.03  4078.5  399.60  4091.6  400.35  4218.7  399.14  4348.8  393.51
  4535.4  390.79  4619.1  391.13  4859.4  389.04  4889.5  387.56  4929.5  390.04
  4959.6  389.75  4979.6  388.18  4983.8  386.08  4985.4  385.58  4995.3  386.08
  5002.1  386.83  5009.6  389.69  5039.7  388.18  5120.0  389.08  5154.1  388.22
  5260.4  390.33  5781.9  393.49  6112.9  398.62  6413.8  401.22  6981.8  412.50
#Mann=5,-1,0
  3365.2    0.05       0  4535.4    0.12       0  4983.8    0.07       0
  4995.3    0.12       0  5154.1    0.05       0
Bank Sta=4983.8,4995.3
Exp/Cntr=0.3,0.1

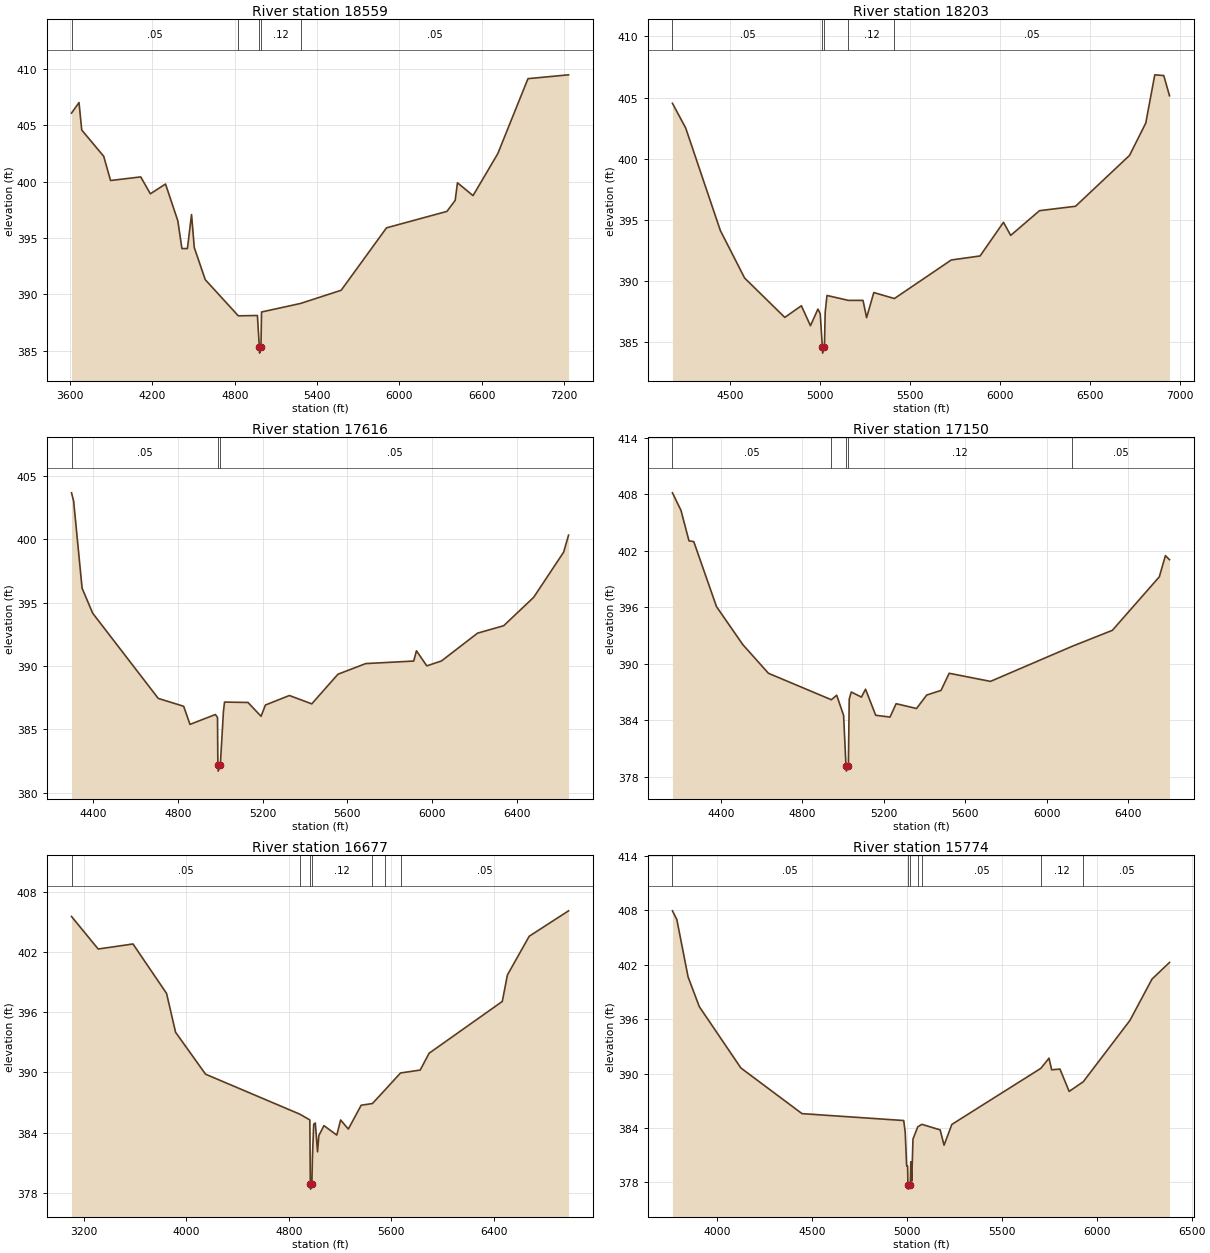
Type RM Length L Ch R = 1,18559,356,356,356
BEGIN DESCRIPTION:
Prairie Branch 34.0
END DESCRIPTION:
XS GIS Cut Line= 3
      2646720.52      6888759.80      2645326.00      6888711.00
      2643100.49      6888828.69
#Sta/Elev= 30
  3609.6  406.08  3664.2  407.02  3684.2  404.58  3844.3  402.25  3894.3  400.10
  4114.4  400.42  4184.5  398.92  4294.9  399.79  4384.6  396.53  4414.6  394.06
  4454.6  394.06  4484.7  397.08  4504.7  394.15  4584.7  391.30  4825.7  388.09
  4965.0  388.12  4979.2  385.28  4980.8  384.78  4990.8  385.28  4995.0  388.43
  5279.9  389.19  5575.8  390.36  5906.2  395.90  6346.8  397.36  6406.9  398.34
  6423.6  399.90  6537.1  398.76  6717.4  402.48  6937.7  409.14  7233.6  409.48
#Mann=5,-1,0
  3609.6    0.05       0  4825.7    0.12       0  4979.2    0.07       0
  4990.8    0.12       0  5279.9    0.05       0
Bank Sta=4979.2,4990.8
Exp/Cntr=0.3,0.1

Type RM Length L Ch R = 1,18203,587,587,587
BEGIN DESCRIPTION:
Prairie Branch 33.0
END DESCRIPTION:
XS GIS Cut Line= 3
      2646226.01      6888561.00      2645426.03      6888385.99
      2643484.28      6888483.66
#Sta/Elev= 30
  4181.1  404.53  4254.6  402.52  4447.3  394.14  4582.1  390.26  4805.5  387.04
  4897.7  387.99  4948.4  386.36  4989.8  387.72  5002.6  387.34  5014.3  384.62
  5015.9  384.12  5025.9  384.62  5030.1  387.45  5040.1  388.83  5159.2  388.43
  5240.3  388.43  5260.4  387.02  5300.4  389.07  5414.8  388.58  5731.0  391.73
  5891.2  392.06  6021.3  394.81  6061.4  393.74  6221.6  395.76  6421.8  396.12
  6722.2  400.28  6812.3  402.92  6862.4  406.86  6912.4  406.80  6944.2  405.15
#Mann=5,-1,0
  4181.1    0.05       0  5014.3    0.03       0  5025.9    0.05       0
  5159.2    0.12       0  5414.8    0.05       0
Bank Sta=5014.3,5025.9
Exp/Cntr=0.3,0.1

Type RM Length L Ch R = 1,17616,466,466,466
BEGIN DESCRIPTION:
Prairie Branch 32.0
END DESCRIPTION:
XS GIS Cut Line= 3
      2646225.99      6887961.00      2645526.00      6887961.00
      2643926.03      6887561.01
#Sta/Elev= 30
  4296.3  403.68  4306.3  403.03  4346.3  396.15  4396.3  394.18  4706.3  387.45
  4826.3  386.83  4856.3  385.40  4976.3  386.18  4986.3  385.94  4988.0  382.21
  4989.6  381.71  4999.6  382.21  5014.3  386.42  5019.5  387.16  5130.3  387.13
  5192.1  386.04  5212.8  386.93  5326.1  387.68  5431.8  387.02  5555.5  389.36
  5686.9  390.20  5913.7  390.40  5926.6  391.21  5975.5  390.02  6045.1  390.41
  6215.2  392.60  6338.9  393.19  6480.6  395.43  6622.3  399.00  6645.5  400.34
#Mann=3,-1,0
  4296.3    0.05       0  4988.0    0.03       0  4999.6    0.05       0
Bank Sta=4988,4999.6
Exp/Cntr=0.3,0.1

Type RM Length L Ch R = 1,17150,473,473,473
BEGIN DESCRIPTION:
Prairie Branch 31.0
END DESCRIPTION:
XS GIS Cut Line= 3
      2646375.98      6887760.99      2645576.00      6887511.00
      2643975.95      6887411.00
#Sta/Elev= 30
  4161.9  408.17  4203.8  406.31  4243.1  403.07  4266.6  402.99  4378.2  396.09
  4507.6  392.05  4633.3  389.01  4942.3  386.20  4968.6  386.68  5002.5  384.54
  5014.3  379.12  5015.9  378.62  5025.9  379.12  5030.1  386.26  5040.1  387.02
  5090.2  386.48  5110.2  387.32  5160.3  384.55  5230.5  384.36  5260.5  385.78
  5360.7  385.27  5410.8  386.70  5481.0  387.19  5521.0  389.01  5723.9  388.15
  6125.8  391.88  6322.6  393.57  6553.1  399.25  6583.1  401.50  6603.2  401.07
#Mann=5,-1,0
  4161.9    0.05       0  4942.3    0.12       0  5014.3    0.07       0
  5025.9    0.12       0  6125.8    0.05       0
Bank Sta=5014.3,5025.9
Exp/Cntr=0.3,0.1

Type RM Length L Ch R = 1,16677,903,903,903
BEGIN DESCRIPTION:
Prairie Branch 30.0
END DESCRIPTION:
XS GIS Cut Line= 3
      2647312.47      6886900.32      2645426.00      6887111.00
      2643449.40      6887155.50
#Sta/Elev= 30
  3106.2  405.53  3314.0  402.29  3585.6  402.79  3847.2  397.87  3917.7  394.00
  4151.3  389.83  4886.3  385.85  4964.3  385.28  4968.2  378.89  4969.9  378.39
  4980.2  378.89  4984.3  381.49  4994.3  384.85  5006.9  384.97  5024.4  382.10
  5034.4  383.72  5074.4  384.71  5174.4  383.77  5204.4  385.27  5264.5  384.37
  5364.5  386.74  5452.4  386.91  5550.1  388.26  5671.3  389.95  5824.6  390.24
  5894.6  391.92  6464.8  397.07  6504.8  399.71  6674.8  403.56  6981.5  406.09
#Mann=7,-1,0
  3106.2    0.05       0  4886.3    0.12       0  4968.2    0.07       0
  4980.2    0.12       0  5452.4    0.05       0  5550.1    0.12       0
  5671.3    0.05       0
Bank Sta=4968.2,4980.2
Exp/Cntr=0.3,0.1

Type RM Length L Ch R = 1,15774,473,473,473
BEGIN DESCRIPTION:
Prairie Branch 28.0
END DESCRIPTION:
XS GIS Cut Line= 3
      2646626.04      6886611.01      2645426.00      6886311.00
      2644076.01      6886611.00
#Sta/Elev= 30
  3763.3  407.93  3786.5  406.96  3845.8  400.64  3905.1  397.36  4124.1  390.61
  4446.2  385.58  4982.2  384.82  4990.0  383.58  4997.7  379.82  5002.8  379.82
  5004.4  377.76  5006.1  377.26  5016.6  377.76  5019.5  380.27  5024.6  378.15
  5031.0  382.78  5056.5  384.13  5077.7  384.40  5174.4  383.79  5194.9  382.10
  5235.9  384.39  5705.0  390.57  5748.1  391.69  5762.2  390.41  5805.7  390.49
  5854.4  388.03  5928.5  389.09  6174.5  395.85  6291.0  400.41  6383.2  402.24
#Mann=7,-1,0
  3763.3    0.05       0  5004.4    0.03       0  5016.6    0.05       0
  5056.5    0.12       0  5077.7    0.05       0  5705.0    0.12       0
  5928.5    0.05       0
Bank Sta=5004.4,5016.6
Exp/Cntr=0.3,0.1

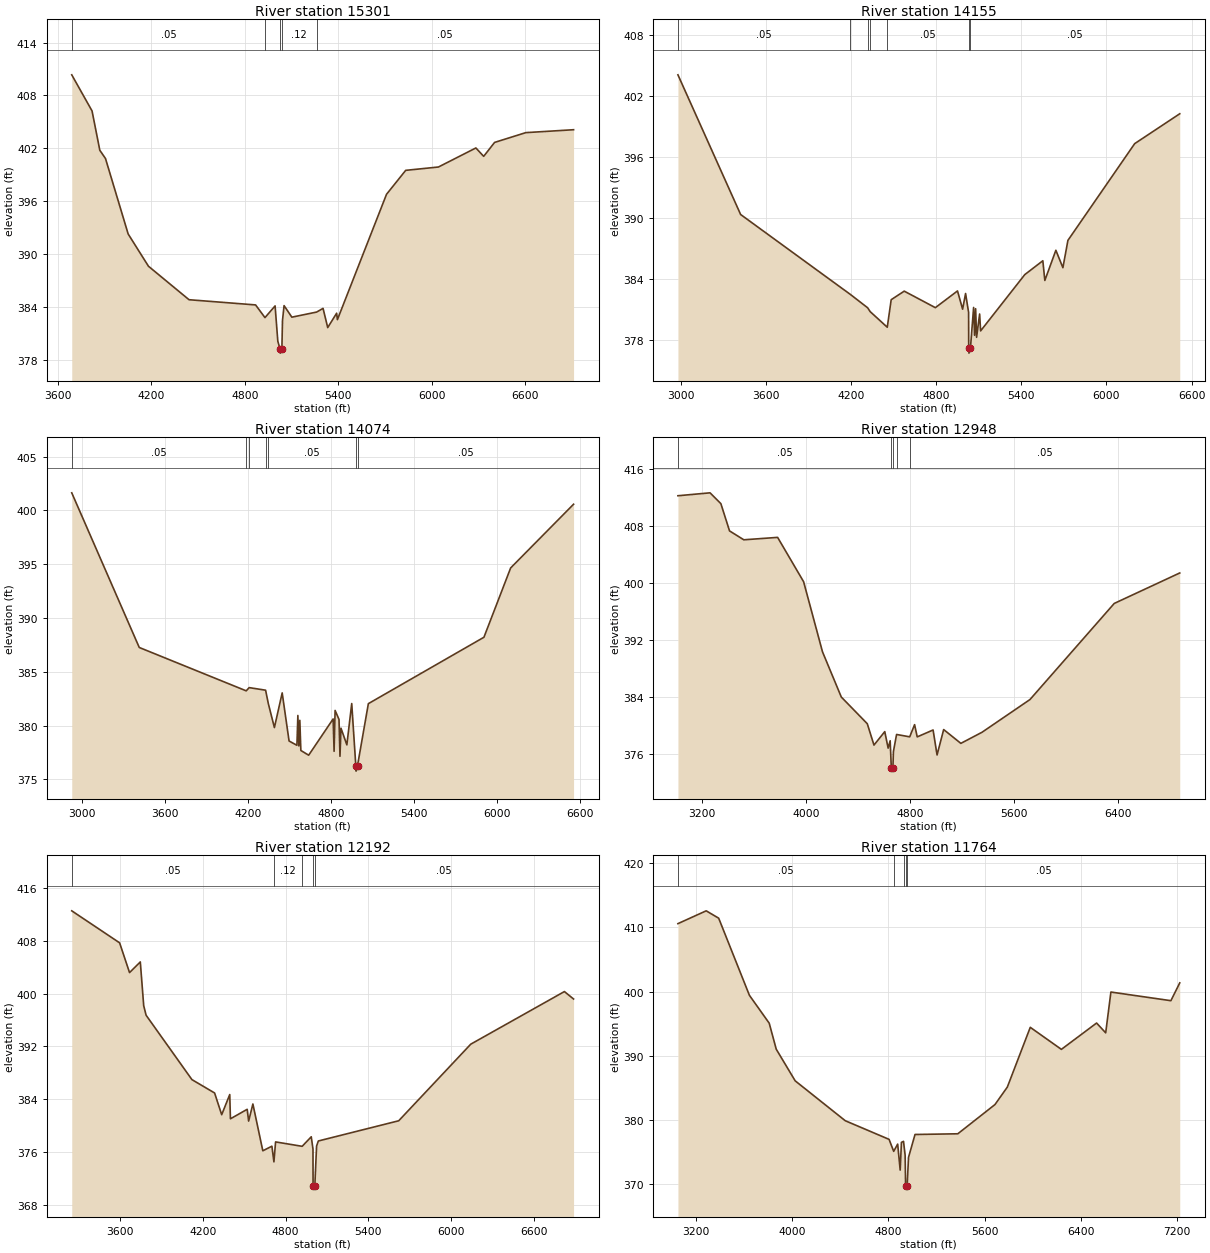
Type RM Length L Ch R = 1,15301,1146,1146,1146
BEGIN DESCRIPTION:
Prairie Branch 27.0
END DESCRIPTION:
XS GIS Cut Line= 3
      2646726.01      6886611.01      2645626.00      6885911.00
      2643709.60      6885791.04
#Sta/Elev= 30
  3688.5  410.34  3818.9  406.24  3868.8  401.78  3905.3  400.84  4050.9  392.28
  4181.3  388.62  4442.0  384.82  4869.6  384.23  4929.8  382.79  4994.9  384.12
  5012.4  380.11  5026.3  379.26  5028.0  378.76  5038.5  379.26  5042.4  382.46
  5052.5  384.15  5102.6  382.84  5261.9  383.42  5303.0  383.84  5333.0  381.66
  5390.3  383.29  5395.3  382.56  5710.7  396.78  5834.0  399.50  6044.4  399.88
  6284.9  402.04  6335.0  401.09  6405.1  402.67  6605.5  403.78  6912.5  404.11
#Mann=5,-1,0
  3688.5    0.05       0  4929.8    0.12       0  5026.3    0.07       0
  5038.5    0.12       0  5261.9    0.05       0
Bank Sta=5026.3,5038.5
Exp/Cntr=0.3,0.1

Type RM Length L Ch R = 1,14155,81,81,81
BEGIN DESCRIPTION:
Mapping XS e767261e
END DESCRIPTION:
XS GIS Cut Line= 6
      2646822.87      6886488.90      2645726.98      6885340.91
      2645557.21      6885145.12      2645425.52      6885031.13
      2644781.17      6884369.08      2644209.60      6884524.96
#Sta/Elev= 30
  2979.6  404.06  3421.4  390.36  4194.7  382.52  4316.4  381.21  4334.6  380.83
  4454.9  379.30  4482.6  382.00  4574.5  382.84  4793.9  381.22  4949.9  382.86
  4986.0  381.07  5006.8  382.61  5028.1  380.76  5029.0  377.26  5030.7  376.76
  5041.2  377.26  5063.4  381.24  5070.4  378.51  5077.6  381.12  5084.5  378.31
  5105.8  380.60  5112.8  378.94  5424.0  384.46  5551.3  385.82  5565.5  383.89
  5643.2  386.85  5692.8  385.14  5728.1  387.82  6198.7  397.31  6516.3  400.24
#Mann=7,-1,0
  2979.6    0.05       0  4194.7    0.12       0  4316.4    0.05       0
  4334.6    0.12       0  4454.9    0.05       0  5029.0    0.03       0
  5041.2    0.05       0
Bank Sta=5029,5041.2
Exp/Cntr=0.3,0.1

Type RM Length L Ch R = 1,14074,1126,1126,1126
BEGIN DESCRIPTION:
Mapping XS 39ce9258
END DESCRIPTION:
XS GIS Cut Line= 4
      2646854.07      6886452.39      2645425.25      6884950.33
      2644812.42      6884311.78      2644166.62      6884478.44
#Sta/Elev= 30
  2926.9  401.63  3414.5  387.26  4187.1  383.23  4208.7  383.53  4327.2  383.29
  4347.0  382.04  4390.8  379.82  4447.1  383.04  4496.8  378.57  4553.4  378.17
  4560.3  380.94  4567.6  378.11  4574.5  380.49  4581.8  377.69  4638.4  377.25
  4815.1  380.62  4822.0  377.61  4829.3  381.41  4857.6  380.57  4864.5  377.15
  4871.8  379.76  4914.2  378.21  4949.4  382.05  4978.9  376.27  4980.6  375.77
  4991.1  376.27  5069.6  382.04  5904.5  388.21  6097.5  394.65  6552.0  400.57
#Mann=7,-1,0
  2926.9    0.05       0  4187.1    0.12       0  4208.7    0.05       0
  4327.2    0.12       0  4347.0    0.05       0  4978.9    0.03       0
  4991.1    0.05       0
Bank Sta=4978.9,4991.1
Exp/Cntr=0.3,0.1

Type RM Length L Ch R = 1,12948,756,756,756
BEGIN DESCRIPTION:
Prairie Branch 24.0
END DESCRIPTION:
XS GIS Cut Line= 3
      2647703.06      6883957.62      2646111.47      6883998.21
      2643880.60      6884421.07
#Sta/Elev= 30
  3014.9  412.22  3262.0  412.63  3345.4  411.11  3412.1  407.28  3522.1  406.03
  3782.2  406.37  3982.3  400.14  4127.7  390.29  4272.4  383.94  4472.4  380.19
  4523.9  377.19  4607.0  379.08  4632.9  376.76  4648.5  377.80  4657.3  374.03
  4659.0  373.53  4669.7  374.03  4673.6  376.29  4697.8  378.68  4799.0  378.35
  4836.5  380.06  4856.8  378.34  4979.0  379.31  5009.5  375.80  5060.4  379.37
  5192.7  377.43  5355.6  378.99  5724.9  383.59  6373.4  397.09  6877.6  401.37
#Mann=5,-1,0
  3014.9    0.05       0  4657.3    0.05       0  4669.7    0.05       0
  4697.8    0.12       0  4799.0    0.05       0
Bank Sta=4657.3,4669.7
Exp/Cntr=0.3,0.1

Type RM Length L Ch R = 1,12192,428,428,428
BEGIN DESCRIPTION:
Prairie Branch 22.0
END DESCRIPTION:
XS GIS Cut Line= 3
      2647463.50      6883040.94      2645777.99      6883441.32
      2643974.77      6884056.27
#Sta/Elev= 30
  3250.2  412.60  3597.1  407.74  3669.0  403.22  3747.1  404.84  3771.8  398.19
  3789.3  396.74  4121.3  386.97  4285.7  384.94  4337.1  381.64  4395.4  384.70
  4400.5  381.02  4521.9  382.46  4532.4  380.67  4563.2  383.27  4635.2  376.16
  4701.0  376.86  4715.7  374.48  4727.7  377.51  4920.4  376.84  4986.3  378.29
  4998.8  376.43  4999.5  370.84  5001.3  370.34  5012.1  370.84  5024.9  376.88
  5037.5  377.65  5620.3  380.72  6142.5  392.35  6821.4  400.34  6887.8  399.21
#Mann=5,-1,0
  3250.2    0.05       0  4715.7    0.12       0  4920.4    0.05       0
  4999.5    0.03       0  5012.1    0.05       0
Bank Sta=4999.5,5012.1
Exp/Cntr=0.3,0.1

Type RM Length L Ch R = 1,11764,527,527,527
BEGIN DESCRIPTION:
Prairie Branch 21.0
END DESCRIPTION:
XS GIS Cut Line= 3
      2647494.68      6882639.92      2645448.24      6883117.47
      2643640.79      6884124.15
#Sta/Elev= 30
  3051.4  410.60  3286.2  412.60  3390.1  411.45  3645.4  399.41  3809.9  395.06
  3868.3  391.00  4025.6  386.06  4441.9  379.83  4806.0  376.92  4844.5  375.05
  4877.5  376.18  4898.4  372.12  4908.7  376.45  4926.0  376.61  4939.5  374.45
  4943.4  369.65  4945.1  369.15  4956.1  369.65  4967.7  374.11  5021.6  377.68
  5377.2  377.79  5685.9  382.35  5788.8  385.08  5979.5  394.41  6238.1  390.97
  6530.7  395.08  6606.2  393.55  6649.6  399.92  7148.0  398.57  7221.7  401.35
#Mann=5,-1,0
  3051.4    0.05       0  4844.5    0.12       0  4926.0    0.05       0
  4943.4    0.03       0  4956.1    0.05       0
Bank Sta=4943.4,4956.1
Exp/Cntr=0.3,0.1

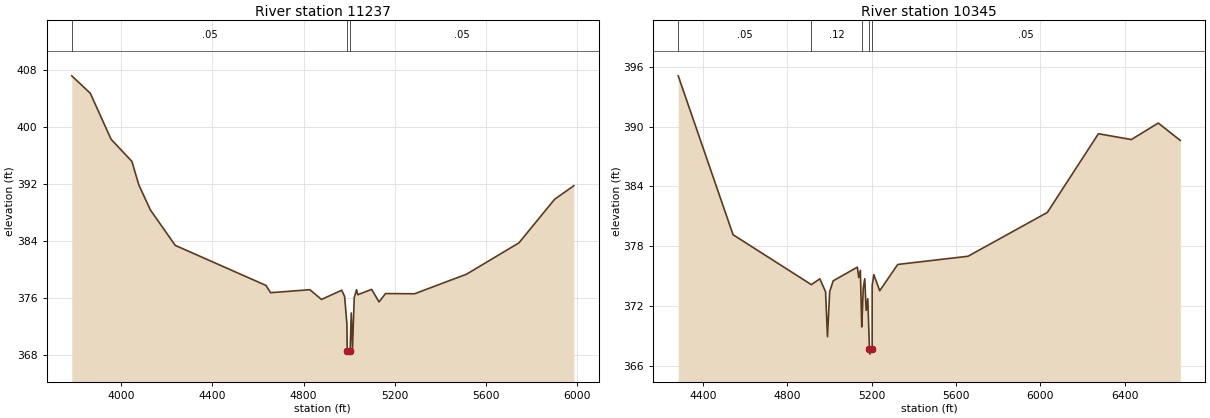
Type RM Length L Ch R = 1,11237,892,892,892
BEGIN DESCRIPTION:
Prairie Branch 20.0
END DESCRIPTION:
XS GIS Cut Line= 3
      2646826.03      6882411.00      2645626.00      6882611.00
      2644725.97      6883011.01
#Sta/Elev= 30
  3783.9  407.20  3865.0  404.76  3956.3  398.29  4047.5  395.18  4077.9  391.88
  4128.6  388.36  4237.6  383.38  4635.5  377.75  4655.8  376.73  4828.1  377.15
  4878.8  375.78  4967.5  377.08  4980.2  376.21  4990.3  372.38  4991.6  368.60
  4993.3  368.10  5004.3  368.60  5009.4  373.88  5014.8  368.86  5022.4  376.01
  5032.6  377.15  5038.1  376.45  5099.0  377.20  5131.1  375.43  5159.8  376.61
  5287.1  376.58  5514.8  379.33  5744.6  383.73  5901.2  389.86  5985.4  391.76
#Mann=3,-1,0
  3783.9    0.05       0  4991.6    0.03       0  5004.3    0.05       0
Bank Sta=4991.6,5004.3
Exp/Cntr=0.3,0.1

Type RM Length L Ch R = 1,10345,1350,1350,1350
BEGIN DESCRIPTION:
Prairie Branch 18.0
END DESCRIPTION:
XS GIS Cut Line= 3
      2646325.97      6881461.02      2645726.00      6881861.00
      2644451.06      6882923.18
#Sta/Elev= 30
  4283.4  395.08  4543.3  379.17  4914.5  374.17  4954.9  374.75  4981.9  373.46
  4991.0  368.96  5001.5  373.47  5018.1  374.55  5132.7  375.92  5139.2  374.88
  5147.0  375.60  5153.5  369.93  5156.7  371.66  5160.7  373.83  5167.8  374.76
  5174.4  371.59  5182.2  372.76  5190.1  367.71  5191.9  367.21  5202.9  367.71
  5203.0  374.11  5210.8  375.17  5238.8  373.56  5324.1  376.19  5657.3  377.01
  6033.5  381.40  6275.6  389.28  6431.8  388.70  6559.4  390.35  6663.9  388.61
#Mann=5,-1,0
  4283.4    0.05       0  4914.5    0.12       0  5156.7    0.05       0
  5190.1    0.07       0  5202.9    0.05       0
Bank Sta=5190.1,5202.9
Exp/Cntr=0.3,0.1