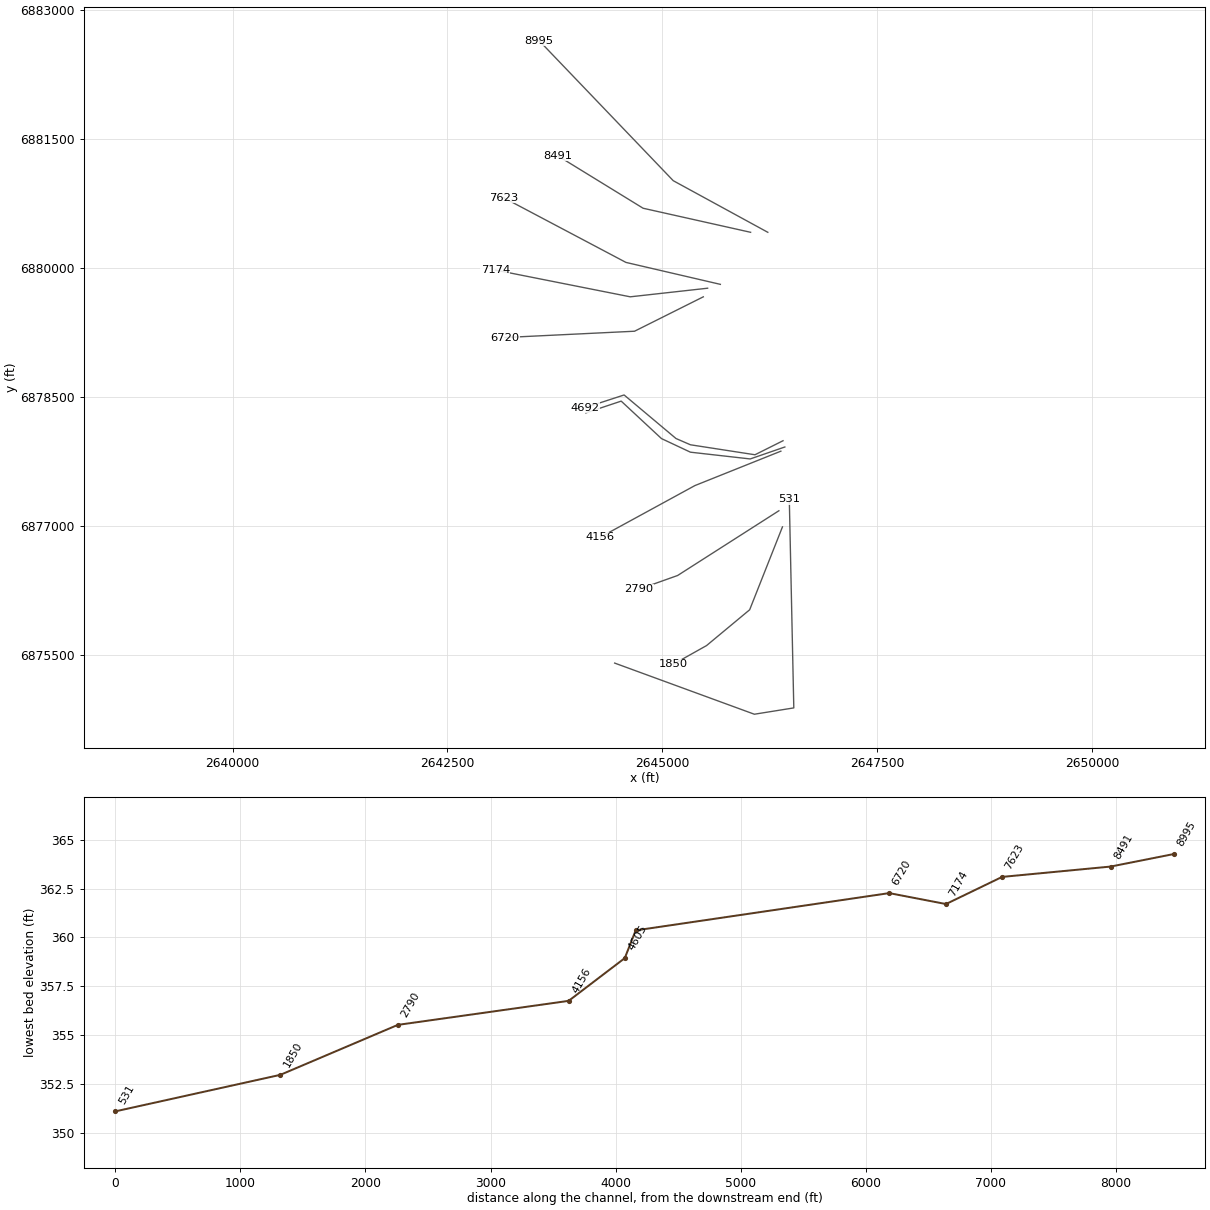
HEC-RAS study Prairie Branch.prj: Prairie Branch Base Level Engineering

--- Prairie Branch.g01 (geometry) --- (continued)

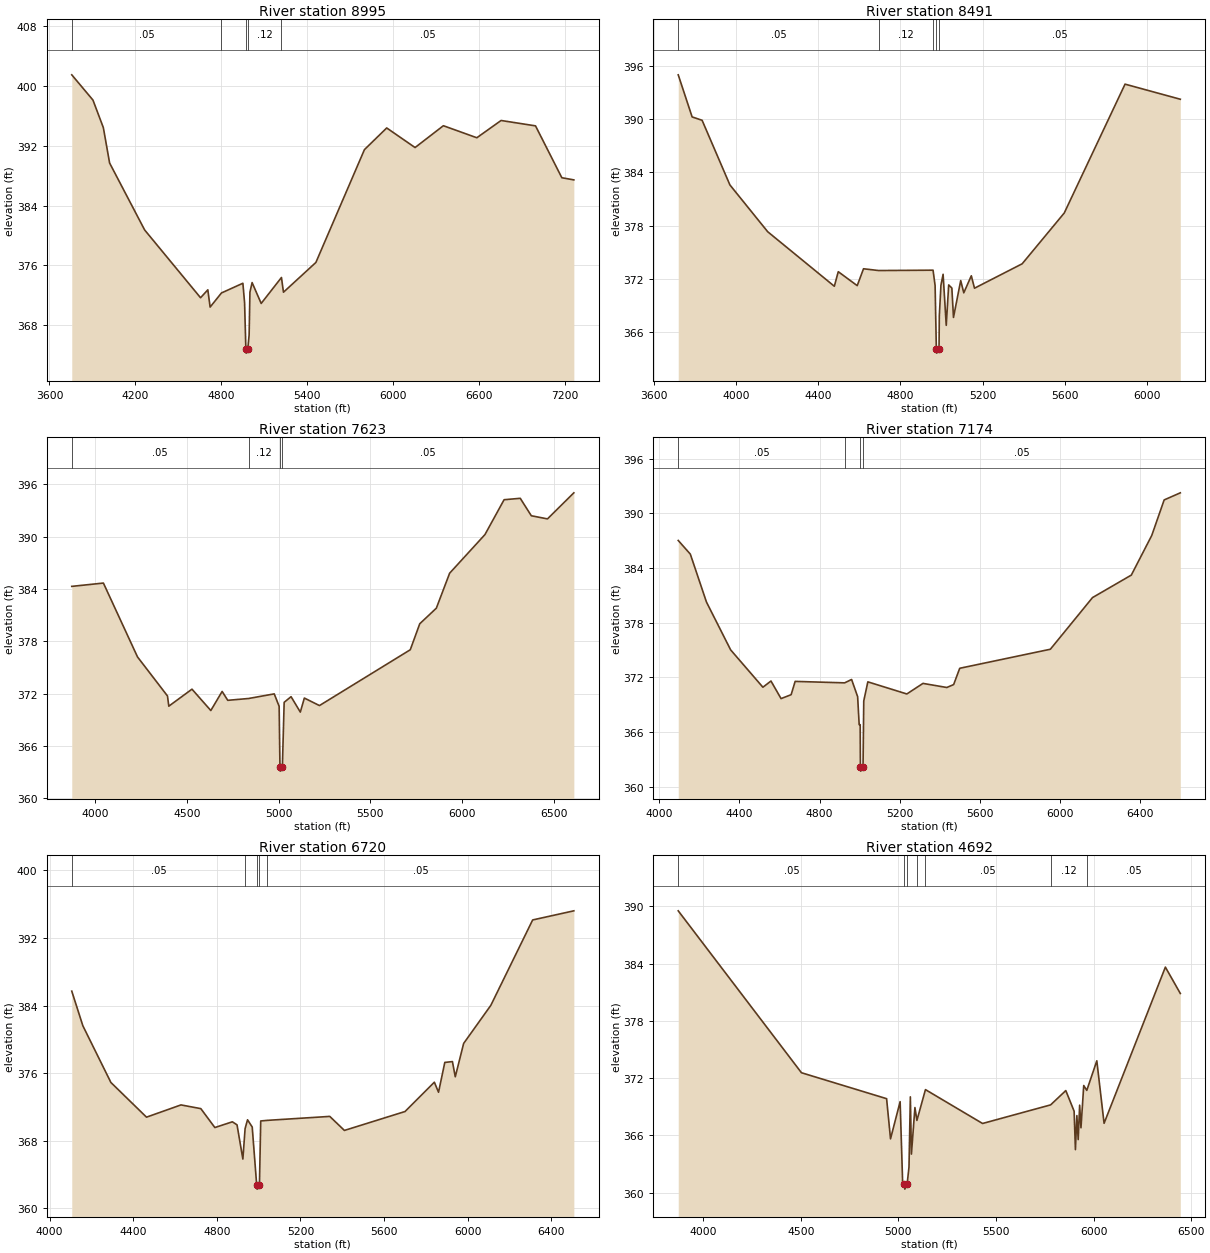
Type RM Length L Ch R = 1,8995,504,504,504
BEGIN DESCRIPTION:
Prairie Branch 16.0
END DESCRIPTION:
XS GIS Cut Line= 3
      2646226.03      6880410.98      2645126.00      6881011.00
      2643565.63      6882639.33
#Sta/Elev= 30
  3755.7  401.51  3903.8  398.13  3976.4  394.44  4020.1  389.71  4265.0  380.75
  4655.6  371.68  4706.4  372.74  4722.5  370.43  4801.6  372.32  4951.3  373.62
  4963.2  371.04  4972.3  364.77  4974.1  364.27  4985.4  364.77  4995.0  366.70
  5000.7  372.43  5015.8  373.71  5079.3  370.92  5220.9  374.39  5235.0  372.42
  5461.4  376.40  5800.8  391.50  5956.4  394.40  6154.6  391.78  6352.4  394.70
  6586.1  393.09  6755.6  395.40  6996.2  394.68  7180.1  387.74  7264.0  387.45
#Mann=5,-1,0
  3755.7    0.05       0  4801.6    0.12       0  4972.3    0.07       0
  4985.4    0.12       0  5220.9    0.05       0
Bank Sta=4972.3,4985.4
Exp/Cntr=0.3,0.1

Type RM Length L Ch R = 1,8491,868,868,868
BEGIN DESCRIPTION:
Prairie Branch 15.0
END DESCRIPTION:
XS GIS Cut Line= 3
      2646025.99      6880411.00      2644775.68      6880690.66
      2643785.36      6881298.92
#Sta/Elev= 30
  3718.8  394.97  3786.4  390.23  3835.0  389.85  3970.3  382.57  4154.2  377.30
  4478.5  371.16  4497.6  372.80  4589.8  371.23  4620.5  373.13  4694.1  372.93
  4958.9  372.97  4968.9  371.24  4974.9  364.13  4976.8  363.63  4988.0  364.13
  4989.4  367.83  4997.3  371.27  5007.8  372.51  5023.1  366.76  5035.0  371.31
  5050.4  370.96  5058.3  367.65  5093.5  371.80  5108.4  370.42  5145.1  372.34
  5160.6  370.94  5392.6  373.69  5597.4  379.41  5893.3  393.92  6162.2  392.22
#Mann=5,-1,0
  3718.8    0.05       0  4694.1    0.12       0  4958.9    0.05       0
  4974.9    0.03       0  4988.0    0.05       0
Bank Sta=4974.9,4988
Exp/Cntr=0.3,0.1

Type RM Length L Ch R = 1,7623,449,449,449
BEGIN DESCRIPTION:
Prairie Branch 14.0
END DESCRIPTION:
XS GIS Cut Line= 3
      2645674.21      6879805.89      2644576.00      6880061.00
      2643153.40      6880812.82
#Sta/Elev= 30
  3872.5  384.29  4044.9  384.67  4230.8  376.20  4394.2  371.72  4401.4  370.55
  4527.7  372.50  4630.4  370.05  4692.0  372.24  4722.8  371.22  4835.9  371.43
  4976.1  371.96  5002.8  370.53  5007.2  363.60  5009.1  363.10  5020.4  363.60
  5030.1  370.99  5067.8  371.64  5118.2  369.87  5140.2  371.48  5222.6  370.62
  5717.5  377.02  5769.1  380.00  5859.6  381.79  5932.0  385.80  6124.5  390.23
  6228.9  394.23  6316.9  394.39  6377.3  392.39  6465.3  392.03  6609.0  395.02
#Mann=4,-1,0
  3872.5    0.05       0  4835.9    0.12       0  5007.2    0.07       0
  5020.4    0.05       0
Bank Sta=5007.2,5020.4
Exp/Cntr=0.3,0.1

Type RM Length L Ch R = 1,7174,454,454,454
BEGIN DESCRIPTION:
Prairie Branch 13.0
END DESCRIPTION:
XS GIS Cut Line= 3
      2645526.05      6879761.01      2644626.00      6879661.00
      2643056.20      6879972.54
#Sta/Elev= 30
  4094.5  387.03  4154.9  385.53  4235.4  380.27  4356.1  375.02  4517.1  370.92
  4557.4  371.60  4607.7  369.67  4658.0  370.10  4678.1  371.56  4925.2  371.40
  4959.8  371.77  4990.0  369.88  4997.6  366.81  5002.6  366.81  5003.7  362.21
  5005.5  361.71  5016.9  362.21  5020.5  369.41  5040.9  371.51  5235.5  370.18
  5316.1  371.34  5435.1  370.89  5469.1  371.21  5499.6  373.00  5951.9  375.09
  6162.3  380.76  6356.0  383.23  6458.0  387.58  6519.9  391.48  6600.5  392.26
#Mann=4,-1,0
  4094.5    0.05       0  4925.2    0.12       0  5003.7    0.07       0
  5016.9    0.05       0
Bank Sta=5003.7,5016.9
Exp/Cntr=0.3,0.1

Type RM Length L Ch R = 1,6720,2028,2028,2028
BEGIN DESCRIPTION:
Prairie Branch 12.0
END DESCRIPTION:
XS GIS Cut Line= 3
      2645475.98      6879660.99      2644676.00      6879261.00
      2643169.17      6879187.92
#Sta/Elev= 30
  4105.7  385.71  4158.8  381.61  4292.9  374.90  4463.4  370.79  4628.4  372.24
  4723.4  371.80  4790.5  369.56  4874.3  370.24  4896.7  369.88  4924.6  365.83
  4935.3  369.44  4947.0  370.48  4969.4  369.62  4990.7  362.77  4992.6  362.27
  5003.9  362.77  5010.1  370.34  5040.9  370.41  5340.5  370.88  5410.6  369.22
  5700.9  371.46  5841.1  374.93  5861.1  373.74  5891.1  377.27  5927.6  377.37
  5941.2  375.57  5981.3  379.52  6111.4  384.03  6311.6  394.14  6508.7  395.22
#Mann=5,-1,0
  4105.7    0.05       0  4935.3    0.12       0  4990.7    0.07       0
  5003.9    0.12       0  5040.9    0.05       0
Bank Sta=4990.7,5003.9
Exp/Cntr=0.3,0.1

Type RM Length L Ch R = 1,4692,87,87,87
BEGIN DESCRIPTION:
Mapping XS 8990bb99
END DESCRIPTION:
XS GIS Cut Line= 6
      2646403.24      6877988.13      2646076.82      6877824.92
      2645325.94      6877940.97      2645157.99      6878013.92
      2644554.69      6878519.99      2644104.62      6878373.54
#Sta/Elev= 30
  3872.3  389.53  4503.5  372.56  4939.7  369.84  4959.8  365.63  5009.0  369.53
  5021.7  361.16  5031.2  360.86  5033.1  360.36  5044.7  360.86  5054.4  362.67
  5061.4  370.03  5066.8  364.03  5084.8  368.91  5095.0  367.56  5138.7  370.79
  5431.3  367.24  5780.0  369.19  5857.7  370.69  5900.3  368.53  5907.0  364.50
  5914.4  368.07  5921.2  365.55  5928.6  369.16  5935.4  366.79  5949.6  371.22
  5965.2  370.71  6016.6  373.81  6053.8  367.26  6367.8  383.63  6444.3  380.87
#Mann=7,-1,0
  3872.3    0.05       0  5031.2    0.03       0  5044.7    0.05       0
  5095.0    0.12       0  5138.7    0.05       0  5780.0    0.12       0
  5965.2    0.05       0
Bank Sta=5031.2,5044.7
Exp/Cntr=0.3,0.1

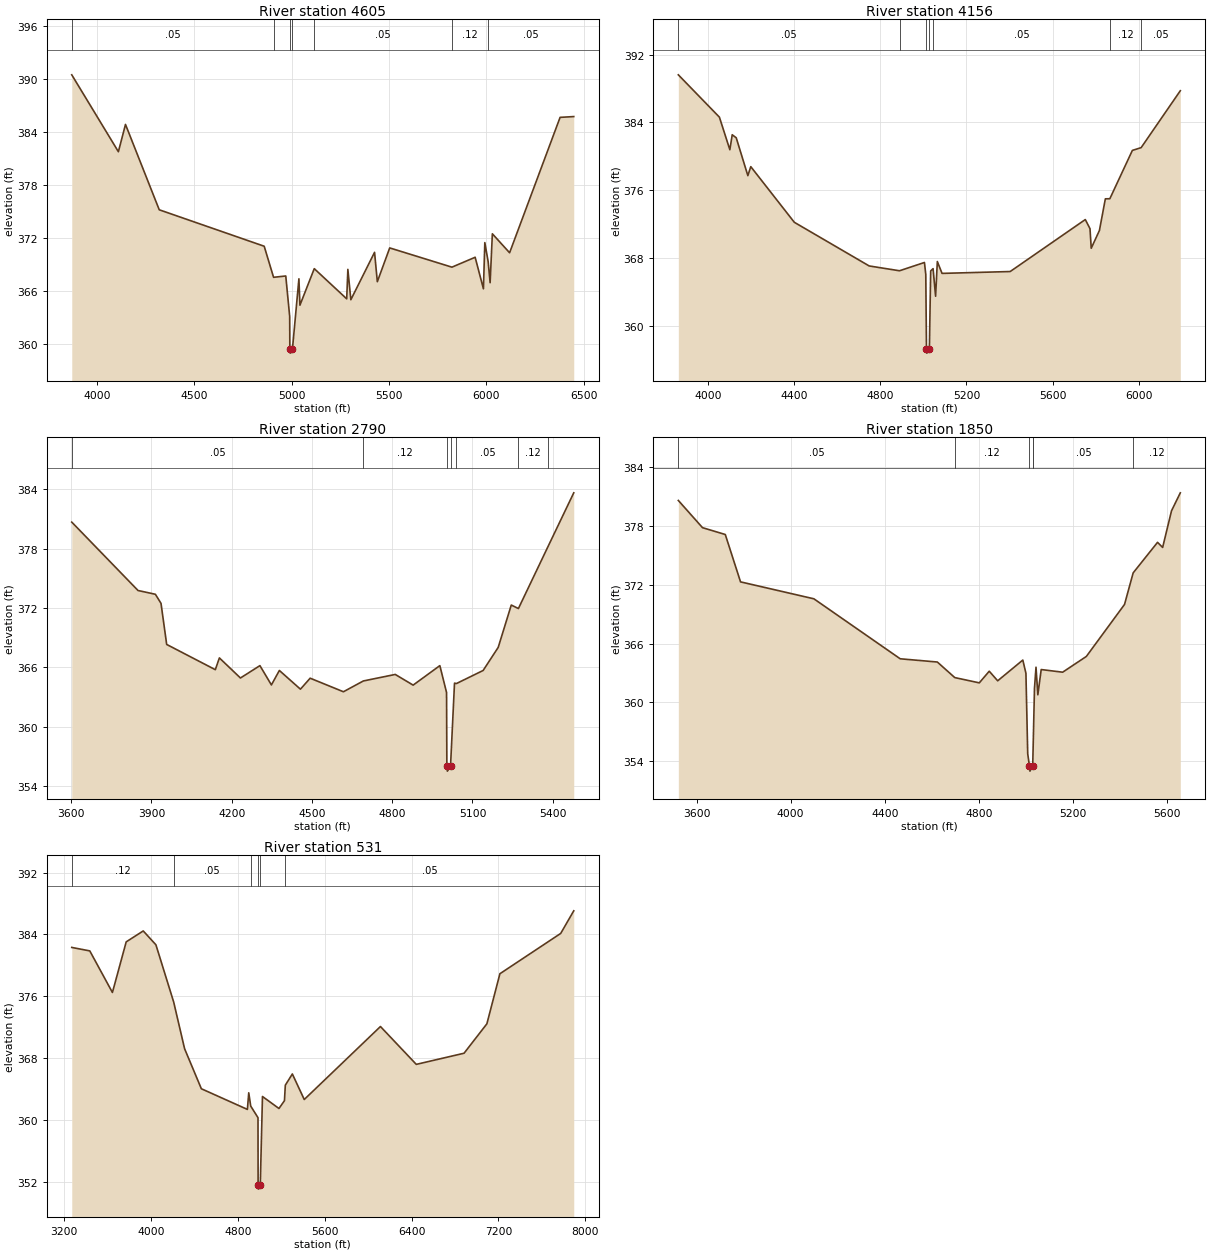
Type RM Length L Ch R = 1,4605,449,449,449
BEGIN DESCRIPTION:
Mapping XS 435f0b7c
END DESCRIPTION:
XS GIS Cut Line= 6
      2646424.04      6877915.20      2646021.26      6877776.31
      2645326.08      6877854.89      2644989.41      6878012.88
      2644520.68      6878448.57      2644109.50      6878311.51
#Sta/Elev= 30
  3871.0  390.47  4110.4  381.76  4146.9  384.85  4320.2  375.18  4859.1  371.05
  4907.2  367.53  4969.9  367.68  4990.0  363.09  4990.8  359.44  4992.7  358.94
  5004.3  359.44  5037.4  367.36  5042.6  364.37  5116.2  368.51  5282.8  365.09
  5288.7  368.43  5304.0  364.99  5425.8  370.36  5440.0  367.03  5503.6  370.86
  5823.1  368.68  5942.3  369.80  5984.8  366.23  5992.0  371.46  6009.1  369.30
  6019.2  366.92  6030.7  372.46  6119.2  370.31  6378.5  385.65  6448.6  385.74
#Mann=7,-1,0
  3871.0    0.05       0  4907.2    0.12       0  4990.8    0.07       0
  5004.3    0.12       0  5116.2    0.05       0  5823.1    0.12       0
  6009.1    0.05       0
Bank Sta=4990.8,5004.3
Exp/Cntr=0.3,0.1

Type RM Length L Ch R = 1,4156,1366,1366,1366
BEGIN DESCRIPTION:
Prairie Branch 6.0
END DESCRIPTION:
XS GIS Cut Line= 3
      2646378.08      6877866.69      2645378.07      6877466.69
      2644279.51      6876867.48
#Sta/Elev= 30
  3863.5  389.63  4054.0  384.63  4102.5  380.78  4113.5  382.55  4132.1  382.19
  4186.0  377.72  4199.6  378.78  4401.4  372.21  4748.7  367.05  4889.5  366.48
  5005.1  367.46  5011.3  366.04  5014.5  357.25  5016.4  356.75  5028.0  357.25
  5034.0  366.46  5045.1  366.73  5056.8  363.47  5064.9  367.57  5086.7  366.17
  5402.8  366.39  5751.2  372.53  5773.0  371.45  5778.7  369.14  5816.7  371.24
  5844.2  374.98  5865.0  374.99  5969.5  380.70  6010.3  381.03  6191.9  387.75
#Mann=7,-1,0
  3863.5    0.05       0  4889.5    0.12       0  5014.5    0.07       0
  5028.0    0.12       0  5045.1    0.05       0  5865.0    0.12       0
  6010.3    0.05       0
Bank Sta=5014.5,5028
Exp/Cntr=0.3,0.1

Type RM Length L Ch R = 1,2790,940,940,940
BEGIN DESCRIPTION:
Prairie Branch 4.0
END DESCRIPTION:
XS GIS Cut Line= 3
      2646354.77      6877173.93      2645176.87      6876421.33
      2644726.03      6876261.01
#Sta/Elev= 30
  3602.2  380.68  3849.9  373.77  3914.7  373.39  3935.8  372.47  3957.0  368.32
  4138.8  365.77  4154.0  366.96  4232.7  364.93  4305.5  366.18  4348.4  364.23
  4378.2  365.69  4456.9  363.80  4493.3  364.91  4617.6  363.54  4692.1  364.63
  4811.3  365.29  4878.2  364.21  4978.0  366.18  5003.1  363.46  5004.2  356.02
  5006.2  355.52  5017.9  356.02  5032.8  364.41  5040.1  364.37  5139.8  365.69
  5196.1  368.02  5245.0  372.30  5271.7  371.95  5380.9  378.13  5478.5  383.64
#Mann=7,-1,0
  3602.2    0.05       0  4692.1    0.12       0  5004.2    0.07       0
  5017.9    0.12       0  5040.1    0.05       0  5271.7    0.12       0
  5380.9    0.05       0
Bank Sta=5004.2,5017.9
Exp/Cntr=0.3,0.1

Type RM Length L Ch R = 1,1850,1319,1319,1319
BEGIN DESCRIPTION:
Prairie Branch 2.0
END DESCRIPTION:
XS GIS Cut Line= 4
      2646396.46      6876986.47      2646014.98      6876022.97
      2645513.68      6875606.83      2645125.62      6875389.22
#Sta/Elev= 30
  3522.7  380.62  3625.4  377.84  3722.2  377.14  3787.0  372.30  4098.6  370.57
  4465.4  364.44  4623.0  364.11  4697.2  362.52  4801.4  361.98  4843.6  363.17
  4879.5  362.19  4986.3  364.31  4999.5  362.95  5007.1  354.73  5014.6  353.46
  5016.6  352.96  5028.3  353.46  5031.6  356.96  5035.8  361.41  5042.3  363.58
  5050.1  360.76  5064.4  363.34  5155.6  363.07  5256.2  364.68  5418.3  369.99
  5455.1  373.22  5558.6  376.34  5580.3  375.82  5618.0  379.56  5655.4  381.40
#Mann=6,-1,0
  3522.7    0.05       0  4697.2    0.12       0  5014.6    0.07       0
  5028.3    0.12       0  5031.6    0.05       0  5455.1    0.12       0
Bank Sta=5014.6,5028.3
Exp/Cntr=0.3,0.1

Type RM Length L Ch R = 1,531,0,0,0
BEGIN DESCRIPTION:
Prairie Branch 1.0
END DESCRIPTION:
XS GIS Cut Line= 4
      2644445.03      6875403.12      2646069.59      6874808.69
      2646528.39      6874882.27      2646476.00      6877311.04
#Sta/Elev= 30
  3270.1  382.32  3436.3  381.87  3644.6  376.50  3771.6  383.04  3928.5  384.45
  4045.3  382.66  4208.8  375.27  4309.4  369.23  4463.8  364.06  4887.9  361.39
  4900.3  363.54  4918.5  361.82  4985.5  360.32  4986.6  351.59  4988.6  351.09
  5000.4  351.59  5006.5  351.59  5026.7  363.06  5178.7  361.51  5229.3  362.52
  5237.2  364.52  5302.0  365.97  5411.6  362.67  6113.5  372.10  6443.6  367.21
  6883.7  368.65  7093.8  372.45  7213.8  378.92  7773.9  384.13  7894.0  387.05
#Mann=6,-1,0
  3270.1    0.12       0  4208.8    0.05       0  4918.5    0.12       0
  4986.6    0.07       0  5000.4    0.12       0  5237.2    0.05       0
Bank Sta=4986.6,5000.4
Exp/Cntr=0.3,0.1

Chan Stop Cuts=-1