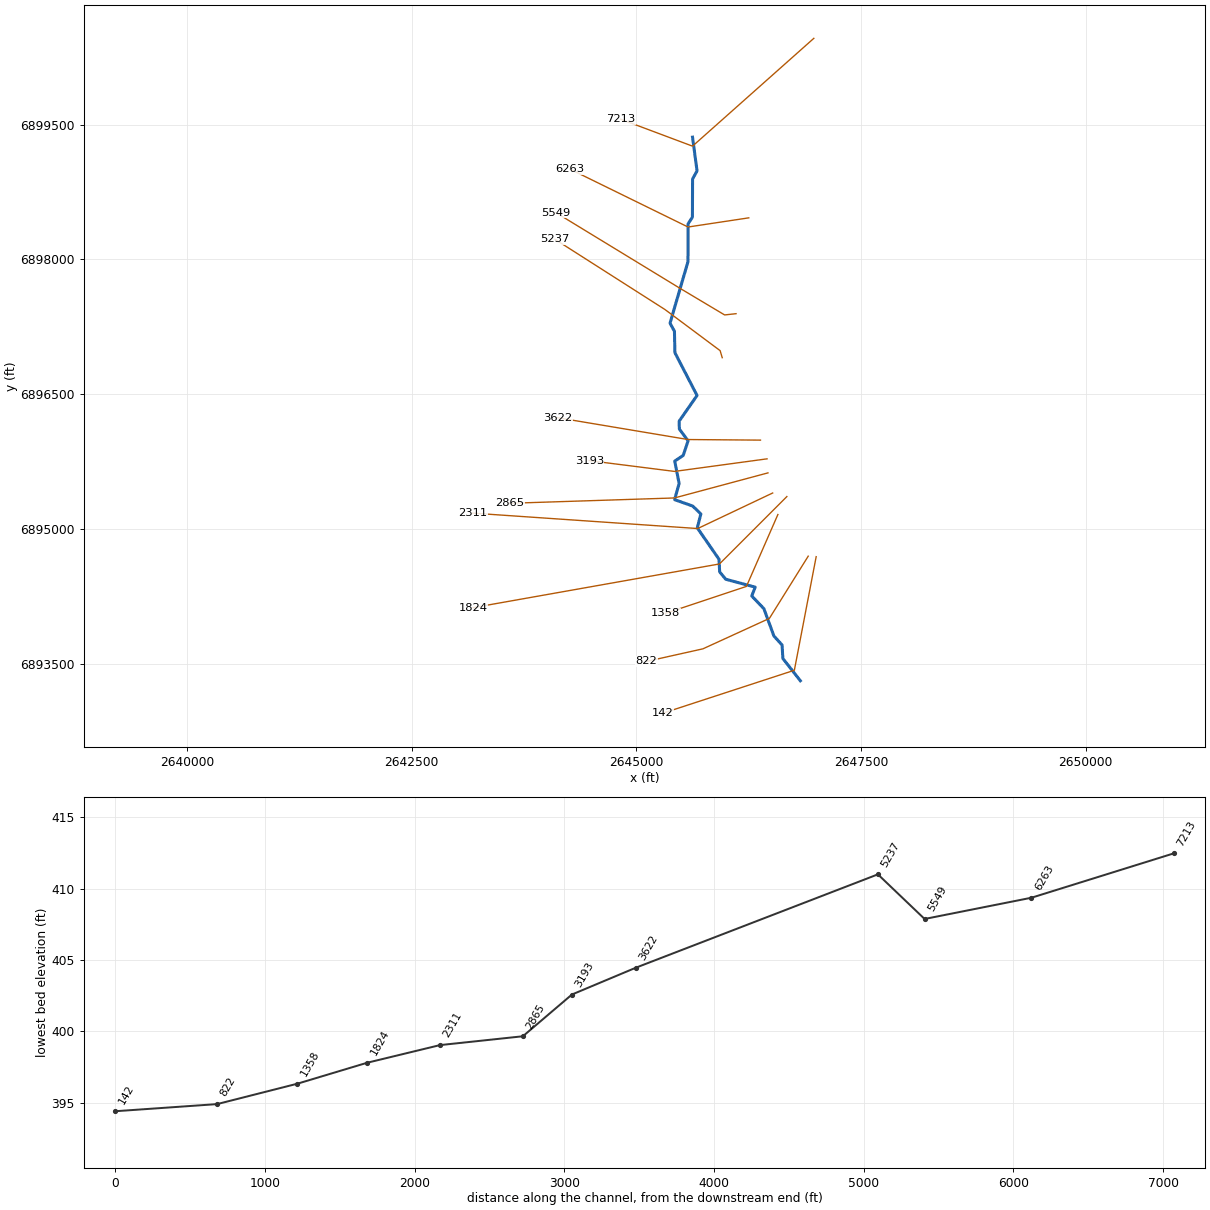
--- Prairie Branch Trib 1.prj (project) ---

Proj Title=Prairie Branch Trib 1 Base Level Engineering
Current Plan=p01
Default Exp/Contr=0.3,0.1
English Units
Geom File=g01
Flow File=f01
Plan File=p01
BEGIN DESCRIPTION:
Prairie Branch Trib 1
END DESCRIPTION:

--- Prairie Branch Trib 1.p01 (plan) ---

Plan Title=Multiple Run
Short Identifier=Multiple
Geom File=g01
Flow File=f01
Subcritical Flow
K Sum by GR= 0
Std Step Tol= 0.01
Critical Tol= 0.01
Num of Std Step Trials= 20
Max Error Tol= 0.3
Flow Tol Ratio= 0.001
Split Flow NTrial= 30
Split Flow Tol= 0.02
Split Flow Ratio= 0.02
Log Output Level= 0
Friction Slope Method= 1
Unsteady Friction Slope Method= 2
Unsteady Bridges Friction Slope Method= 1
Parabolic Critical Depth
Global Vel Dist=  1 , 1 , 1
Global Log Level= 0
CheckData=True
Encroach Param= -1, 0, 0, 0
BEGIN DESCRIPTION:
Multiple Run
END DESCRIPTION:

--- Prairie Branch Trib 1.f01 (steady flow) ---

Flow Title=Multiple
Number of Profiles=7
Profile Names=10-year,25-year,50-year,1pct_min,100-year,1pct_plu,500-year
River Rch & RM= Prairie Branch T,Reach-1,7213
     455     602     720     427     852    1701    1195
River Rch & RM= Prairie Branch T,Reach-1,6263
     689     934    1135     683    1363    2719    1967
River Rch & RM= Prairie Branch T,Reach-1,3622
     864    1184    1446     875    1745    3482    2543
Boundary for River Rch & Prof#=Prairie Branch T,Reach-1,1
Up Type=0
Dn Type=3
Dn Slope=0.005
Boundary for River Rch & Prof#=Prairie Branch T,Reach-1,2
Up Type=0
Dn Type=3
Dn Slope=0.005
Boundary for River Rch & Prof#=Prairie Branch T,Reach-1,3
Up Type=0
Dn Type=3
Dn Slope=0.005
Boundary for River Rch & Prof#=Prairie Branch T,Reach-1,4
Up Type=0
Dn Type=3
Dn Slope=0.005
Boundary for River Rch & Prof#=Prairie Branch T,Reach-1,5
Up Type=0
Dn Type=3
Dn Slope=0.005
Boundary for River Rch & Prof#=Prairie Branch T,Reach-1,6
Up Type=0
Dn Type=3
Dn Slope=0.005
Boundary for River Rch & Prof#=Prairie Branch T,Reach-1,7
Up Type=0
Dn Type=3
Dn Slope=0.005

--- Prairie Branch Trib 1.g01 (geometry) ---

Geom Title=Existing Conditions

River Reach=Prairie Branch T,Reach-1
Reach XY= 30
      2645626.00      6899361.00      2645676.20      6898985.92
      2645626.52      6898895.78      2645624.78      6898471.50
      2645576.52      6898395.78      2645575.48      6897976.22
      2645375.61      6897290.87      2645424.78      6897200.50
      2645429.75      6896962.55      2645676.50      6896485.96
      2645477.08      6896200.45      2645479.47      6896112.50
      2645576.36      6895981.21      2645522.81      6895819.35
      2645428.00      6895755.31      2645476.81      6895505.97
      2645426.42      6895326.64      2645628.32      6895255.18
      2645718.52      6895167.07      2645679.14      6895012.64
      2645920.53      6894663.44      2645927.93      6894522.95
      2645995.63      6894440.58      2646323.47      6894352.83
      2646285.16      6894254.29      2646420.17      6894113.30
      2646531.85      6893808.71      2646622.45      6893709.53
      2646631.47      6893558.55      2646826.00      6893311.00

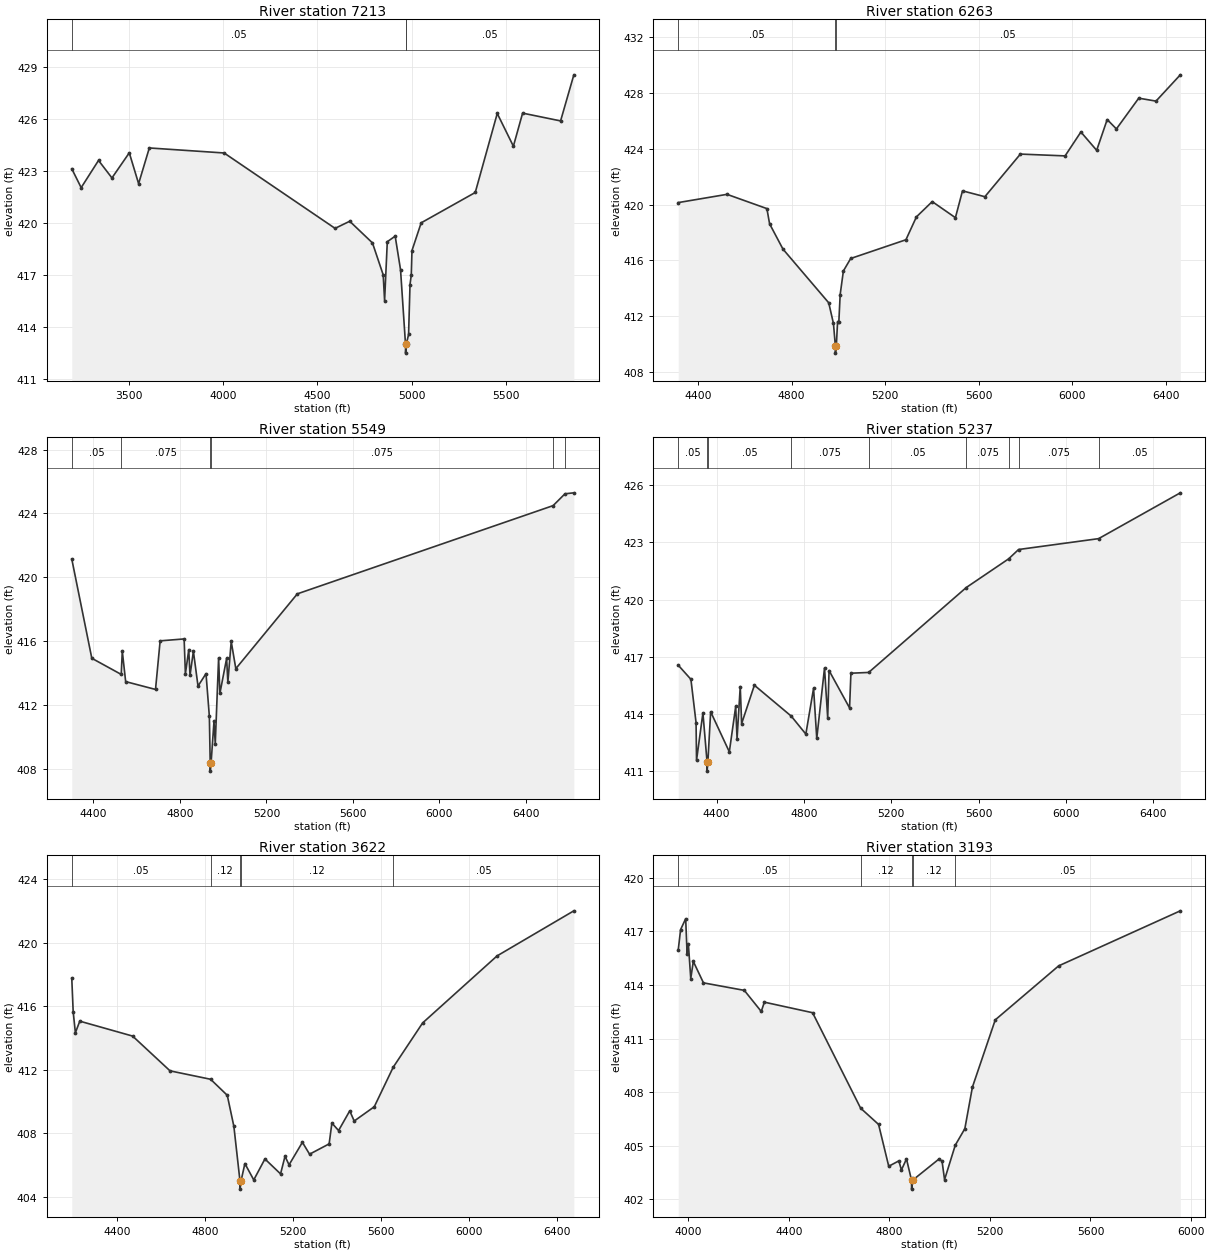
Type RM Length L Ch R = 1,7213,950,950,950
BEGIN DESCRIPTION:
Prairie Branch Trib 1 10.0
END DESCRIPTION:
XS GIS Cut Line= 3
      2646976.03      6900461.02      2645626.00      6899261.00
      2644825.97      6899561.01
#Sta/Elev= 30
  3198.0  423.12  3247.8  422.03  3339.8  423.60  3410.9  422.59  3502.8  424.04
  3552.2  422.26  3609.0  424.32  4005.4  424.03  4593.3  419.68  4671.0  420.09
  4791.5  418.84  4848.3  417.00  4855.8  415.51  4870.1  418.91  4911.9  419.23
  4940.3  417.29  4966.7  412.98  4967.0  412.48  4970.7  412.98  4982.9  413.56
  4990.5  416.44  4997.2  416.99  5000.9  418.40  5049.7  420.00  5336.2  421.75
  5452.8  426.31  5538.3  424.42  5587.2  426.33  5788.4  425.88  5858.7  428.54
#Mann=3,-1,0
  3198.0    0.05       0  4966.7    0.03       0  4970.7    0.05       0
Bank Sta=4966.7,4970.7
Exp/Cntr=0.3,0.1

Type RM Length L Ch R = 1,6263,714,714,714
BEGIN DESCRIPTION:
Prairie Branch Trib 1 9.0
END DESCRIPTION:
XS GIS Cut Line= 3
      2646252.21      6898463.12      2645576.00      6898361.00
      2644262.68      6899004.78
#Sta/Elev= 30
  4315.7  420.14  4524.2  420.73  4694.7  419.71  4706.3  418.62  4763.5  416.81
  4959.1  412.97  4979.3  411.49  4987.5  409.87  4987.7  409.37  4991.5  409.87
  4997.0  411.63  5002.4  411.63  5008.0  413.56  5021.8  415.25  5053.0  416.14
  5289.1  417.48  5334.1  419.12  5401.6  420.21  5500.7  419.06  5531.0  420.98
  5626.6  420.56  5778.5  423.61  5969.6  423.48  6037.1  425.19  6104.6  423.88
  6149.6  426.08  6189.0  425.41  6284.5  427.61  6358.3  427.40  6462.2  429.28
#Mann=3,-1,0
  4315.7    0.05       0  4987.5    0.03       0  4991.5    0.05       0
Bank Sta=4987.5,4991.5
Exp/Cntr=0.3,0.1

Type RM Length L Ch R = 1,5549,312,312,312
BEGIN DESCRIPTION:
Mapping XS 13c13e8c
END DESCRIPTION:
XS GIS Cut Line= 4
      2646110.17      6897396.39      2645983.06      6897382.50
      2645481.41      6897681.87      2644106.39      6898520.42
#Sta/Elev= 30
  4299.6  421.15  4392.3  414.94  4528.4  413.93  4533.3  415.38  4548.9  413.48
  4687.0  412.99  4708.4  416.03  4819.4  416.15  4825.2  413.96  4840.8  415.48
  4846.6  413.87  4862.2  415.38  4883.6  413.20  4920.6  413.98  4936.1  411.30
  4940.0  408.38  4940.2  407.88  4944.0  408.38  4957.5  410.99  4963.4  409.59
  4978.9  414.97  4984.8  412.74  5015.9  414.93  5021.7  413.44  5037.2  415.99
  5058.5  414.29  5343.1  418.97  6526.3  424.49  6581.3  425.23  6622.2  425.29
#Mann=6,-1,0
  4299.6    0.05       0  4528.4   0.075       0  4940.0    0.07       0
  4944.0   0.075       0  6526.3     0.1       0  6581.3   0.075       0
Bank Sta=4940,4944
Exp/Cntr=0.3,0.1

Type RM Length L Ch R = 1,5237,1615,1615,1615
BEGIN DESCRIPTION:
Mapping XS 7f59aa5f
END DESCRIPTION:
XS GIS Cut Line= 4
      2645956.53      6896906.83      2645933.17      6896985.03
      2645319.95      6897442.29      2644095.98      6898223.54
#Sta/Elev= 30
  4224.7  416.56  4282.7  415.82  4306.3  413.55  4308.5  411.58  4337.7  414.06
  4356.5  411.51  4356.8  411.01  4360.5  411.51  4373.1  414.12  4458.6  412.02
  4487.8  414.40  4494.0  412.71  4508.6  415.44  4514.9  413.50  4573.3  415.51
  4742.2  413.89  4808.9  412.95  4844.3  415.35  4858.9  412.72  4894.4  416.41
  4909.0  413.80  4915.2  416.28  5009.1  414.32  5015.3  416.14  5096.5  416.18
  5543.5  420.63  5737.2  422.13  5782.8  422.62  6149.3  423.19  6523.3  425.59
#Mann=9,-1,0
  4224.7    0.05       0  4356.5    0.07       0  4360.5    0.05       0
  4742.2   0.075       0  5096.5    0.05       0  5543.5   0.075       0
  5737.2    0.05       0  5782.8   0.075       0  6149.3    0.05       0
Bank Sta=4356.5,4360.5
Exp/Cntr=0.3,0.1

Type RM Length L Ch R = 1,3622,429,429,429
BEGIN DESCRIPTION:
Prairie Branch Trib 1 7.0
END DESCRIPTION:
XS GIS Cut Line= 3
      2646382.42      6895989.16      2645576.04      6895995.66
      2644121.99      6896239.17
#Sta/Elev= 30
  4193.6  417.76  4200.0  415.65  4210.0  414.32  4230.0  415.05  4470.0  414.11
  4640.0  411.92  4824.3  411.39  4900.0  410.38  4930.0  408.42  4957.8  404.97
  4958.2  404.47  4962.2  404.97  4980.0  406.08  5020.3  405.05  5071.0  406.37
  5142.0  405.43  5162.3  406.54  5180.6  406.00  5241.3  407.42  5273.8  406.67
  5362.7  407.32  5375.2  408.63  5405.6  408.16  5456.3  409.40  5476.6  408.76
  5567.8  409.66  5653.8  412.15  5787.5  414.94  6125.5  419.16  6474.3  422.00
#Mann=5,-1,0
  4193.6    0.05       0  4824.3    0.12       0  4957.8    0.07       0
  4962.2    0.12       0  5653.8    0.05       0
Bank Sta=4957.8,4962.2
Exp/Cntr=0.3,0.1

Type RM Length L Ch R = 1,3193,328,328,328
BEGIN DESCRIPTION:
Prairie Branch Trib 1 6.0
END DESCRIPTION:
XS GIS Cut Line= 3
      2646455.34      6895780.83      2645425.61      6895640.87
      2644475.98      6895761.00
#Sta/Elev= 30
  3960.8  415.96  3970.2  417.10  3990.4  417.71  3996.0  415.76  4001.1  416.29
  4010.6  414.36  4020.7  415.32  4061.1  414.12  4223.5  413.70  4290.9  412.52
  4303.3  413.04  4495.0  412.45  4686.0  407.11  4757.4  406.20  4797.8  403.86
  4838.1  404.16  4848.2  403.65  4868.4  404.27  4888.4  403.08  4888.8  402.58
  4892.9  403.08  4997.3  404.26  5009.7  404.15  5019.8  403.11  5062.4  405.04
  5100.4  405.96  5130.6  408.29  5221.4  412.05  5473.4  415.07  5957.2  418.15
#Mann=5,-1,0
  3960.8    0.05       0  4686.0    0.12       0  4888.4    0.07       0
  4892.9    0.12       0  5062.4    0.05       0
Bank Sta=4888.4,4892.9
Exp/Cntr=0.3,0.1

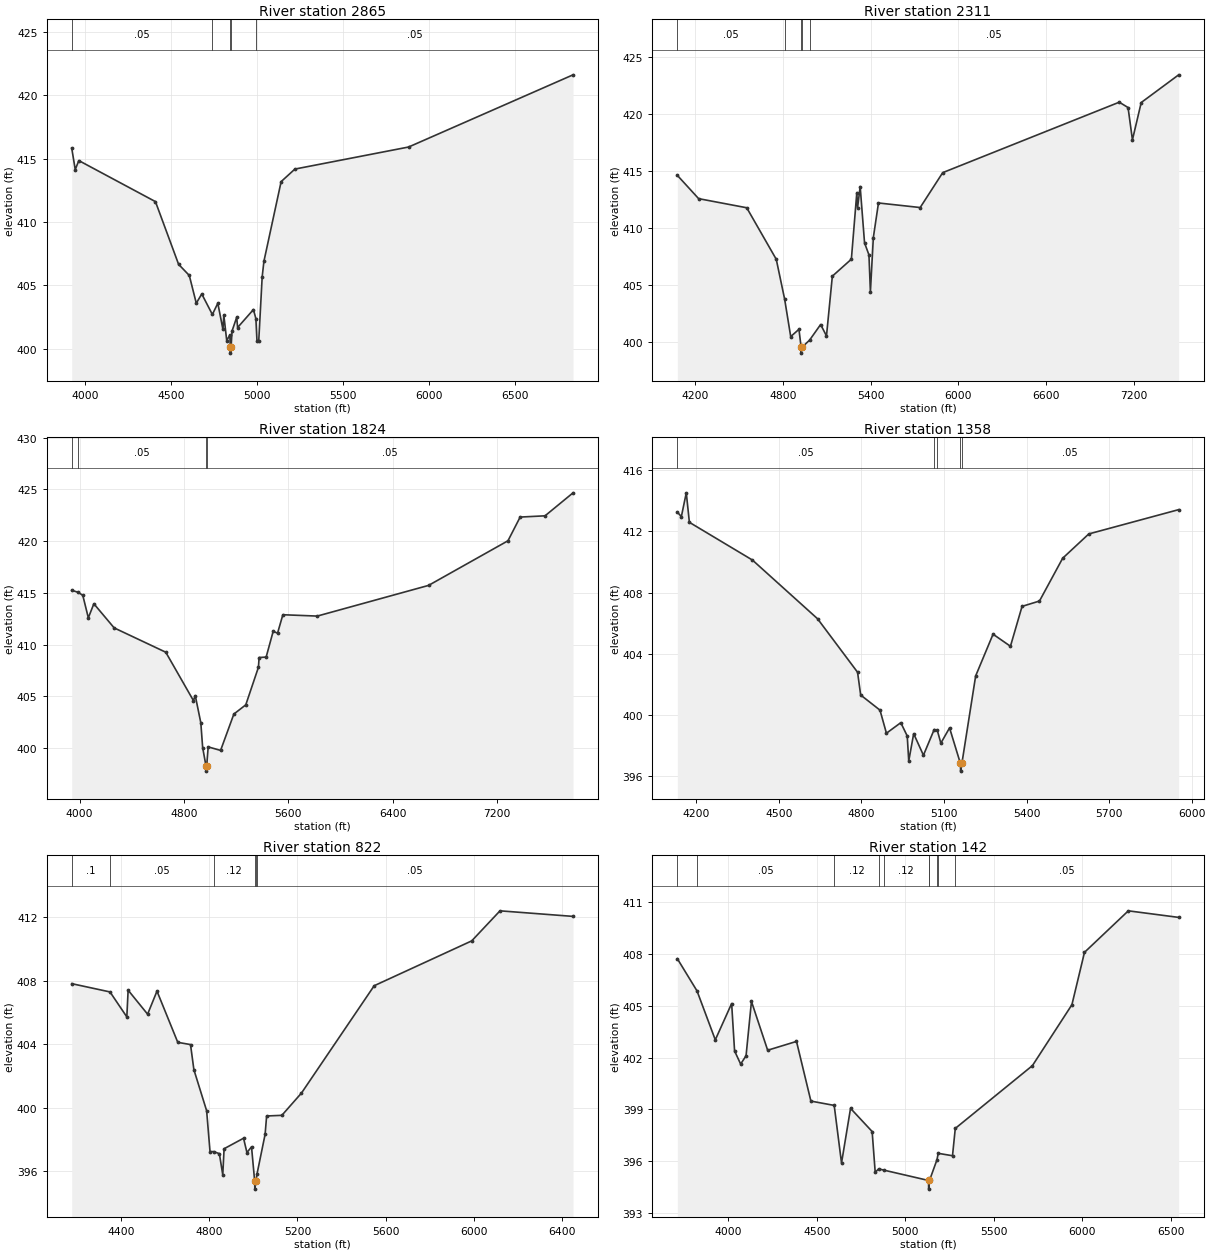
Type RM Length L Ch R = 1,2865,554,554,554
BEGIN DESCRIPTION:
Prairie Branch Trib 1 5.0
END DESCRIPTION:
XS GIS Cut Line= 3
      2646465.75      6895624.57      2645425.03      6895345.44
      2643590.89      6895286.04
#Sta/Elev= 30
  3922.5  415.83  3942.9  414.14  3963.7  414.85  4408.9  411.61  4543.4  406.66
  4605.6  405.78  4646.1  403.59  4678.0  404.32  4739.6  402.70  4771.3  403.59
  4801.0  401.52  4806.1  402.65  4823.0  400.64  4841.0  401.08  4843.8  400.15
  4844.3  399.65  4848.4  400.15  4854.0  401.40  4881.0  402.48  4886.2  401.67
  4978.3  403.09  4992.4  402.37  4998.9  400.58  5009.0  400.61  5029.0  405.67
  5039.1  406.90  5139.1  413.19  5219.1  414.18  5879.5  415.92  6835.1  421.62
#Mann=5,-1,0
  3922.5    0.05       0  4739.6    0.12       0  4843.8    0.03       0
  4848.4    0.12       0  4992.4    0.05       0
Bank Sta=4843.8,4848.4
Exp/Cntr=0.3,0.1

Type RM Length L Ch R = 1,2311,487,487,487
BEGIN DESCRIPTION:
Prairie Branch Trib 1 4.0
END DESCRIPTION:
XS GIS Cut Line= 3
      2646517.84      6895400.61      2645683.50      6895004.95
      2643180.18      6895176.60
#Sta/Elev= 30
  4076.6  414.62  4222.2  412.58  4551.6  411.78  4753.8  407.26  4811.2  403.76
  4852.7  400.48  4909.2  401.12  4924.1  399.53  4924.6  399.03  4928.7  399.53
  4982.0  400.17  5057.6  401.54  5097.7  400.54  5137.8  405.78  5268.1  407.27
  5305.4  413.11  5310.5  411.79  5328.3  413.64  5358.3  408.70  5388.4  407.65
  5398.4  404.41  5418.5  409.17  5453.7  412.20  5739.2  411.80  5893.5  414.86
  7102.4  421.04  7162.6  420.57  7192.6  417.74  7252.8  421.01  7509.2  423.44
#Mann=5,-1,0
  4076.6    0.05       0  4811.2    0.12       0  4924.1    0.03       0
  4928.7    0.12       0  4982.0    0.05       0
Bank Sta=4924.1,4928.7
Exp/Cntr=0.3,0.1

Type RM Length L Ch R = 1,1824,466,466,466
BEGIN DESCRIPTION:
Prairie Branch Trib 1 3.0
END DESCRIPTION:
XS GIS Cut Line= 3
      2646676.00      6895361.00      2645926.00      6894611.00
      2643184.58      6894124.59
#Sta/Elev= 30
  3939.8  415.25  3990.3  415.05  4024.7  414.76  4067.1  412.59  4109.5  413.95
  4265.1  411.62  4661.1  409.27  4873.2  404.60  4887.3  405.08  4929.8  402.46
  4943.9  400.07  4969.5  398.29  4970.3  397.79  4974.8  398.29  4986.3  400.13
  5081.5  399.79  5183.3  403.30  5274.7  404.19  5371.8  407.82  5376.9  408.76
  5430.9  408.80  5484.9  411.29  5518.4  411.11  5559.1  412.89  5823.1  412.76
  6676.2  415.72  7285.6  420.03  7379.0  422.32  7570.0  422.44  7784.7  424.66
#Mann=4,-1,0
  3939.8   0.075       0  3990.3    0.05       0  4969.5    0.03       0
  4974.8    0.05       0
Bank Sta=4969.5,4974.8
Exp/Cntr=0.3,0.1

Type RM Length L Ch R = 1,1358,536,536,536
BEGIN DESCRIPTION:
Prairie Branch Trib 1 2.0
END DESCRIPTION:
XS GIS Cut Line= 3
      2646576.01      6895161.02      2646226.00      6894361.00
      2645326.02      6894061.01
#Sta/Elev= 30
  4131.0  413.27  4145.5  412.97  4163.4  414.53  4174.7  412.60  4403.9  410.13
  4640.5  406.29  4785.9  402.79  4797.2  401.30  4867.4  400.31  4890.8  398.80
  4943.0  399.49  4966.4  398.62  4971.9  396.98  4989.8  398.77  5025.3  397.36
  5064.3  399.04  5075.5  399.00  5088.6  398.15  5120.2  399.15  5159.7  396.82
  5160.5  396.32  5165.0  396.82  5215.1  402.55  5278.3  405.28  5341.5  404.49
  5383.7  407.10  5447.0  407.45  5531.3  410.25  5626.2  411.84  5952.9  413.43
#Mann=5,-1,0
  4131.0    0.05       0  5064.3    0.12       0  5075.5    0.05       0
  5159.7    0.03       0  5165.0    0.05       0
Bank Sta=5159.7,5165
Exp/Cntr=0.3,0.1

Type RM Length L Ch R = 1,822,680,680,680
BEGIN DESCRIPTION:
Mapping XS a00624f7
END DESCRIPTION:
XS GIS Cut Line= 4
      2646913.70      6894697.49      2646481.41      6894004.79
      2645741.83      6893666.25      2645112.52      6893525.82
#Sta/Elev= 30
  4175.8  407.81  4349.4  407.29  4425.8  405.72  4431.7  407.40  4520.1  405.89
  4562.6  407.34  4657.0  404.12  4714.8  403.98  4730.1  402.40  4787.9  399.82
  4803.3  397.25  4819.6  397.25  4845.7  397.12  4861.1  395.79  4867.1  397.43
  4955.4  398.09  4970.8  397.19  4991.6  397.55  5005.9  395.39  5006.7  394.89
  5011.3  395.39  5016.5  395.84  5053.3  398.34  5060.1  399.49  5129.2  399.53
  5218.2  400.93  5548.2  407.68  5990.7  410.50  6119.1  412.39  6450.5  412.04
#Mann=6,-1,0
  4175.8     0.1       0  4349.4    0.05       0  4819.6    0.12       0
  5005.9    0.07       0  5011.3    0.12       0  5016.5    0.05       0
Bank Sta=5005.9,5011.3
Exp/Cntr=0.3,0.1

Type RM Length L Ch R = 1,142,0,0,0
BEGIN DESCRIPTION:
Prairie Branch Trib 1 1.0
END DESCRIPTION:
XS GIS Cut Line= 3
      2647002.24      6894692.29      2646759.40      6893427.69
      2645289.85      6892947.87
#Sta/Elev= 30
  3712.3  407.71  3823.4  405.85  3926.7  403.02  4019.1  405.12  4035.7  402.38
  4070.0  401.62  4100.6  402.10  4131.1  405.24  4222.7  402.42  4385.7  402.93
  4467.1  399.48  4598.8  399.23  4640.2  395.90  4691.2  399.06  4813.3  397.72
  4830.5  395.37  4850.4  395.56  4878.9  395.49  5132.0  394.89  5132.8  394.39
  5137.4  394.89  5179.8  396.09  5186.7  396.46  5267.5  396.32  5283.2  397.90
  5719.2  401.53  5942.4  405.05  6013.5  408.08  6261.3  410.48  6545.9  410.10
#Mann=10,-1,0
  3712.3     0.1       0  3823.4    0.05       0  4598.8    0.12       0
  4850.4    0.05       0  4878.9    0.12       0  5132.0    0.07       0
  5137.4    0.12       0  5179.8    0.05       0  5186.7    0.12       0
  5283.2    0.05       0
Bank Sta=5132,5137.4
Exp/Cntr=0.3,0.1

Chan Stop Cuts=-1