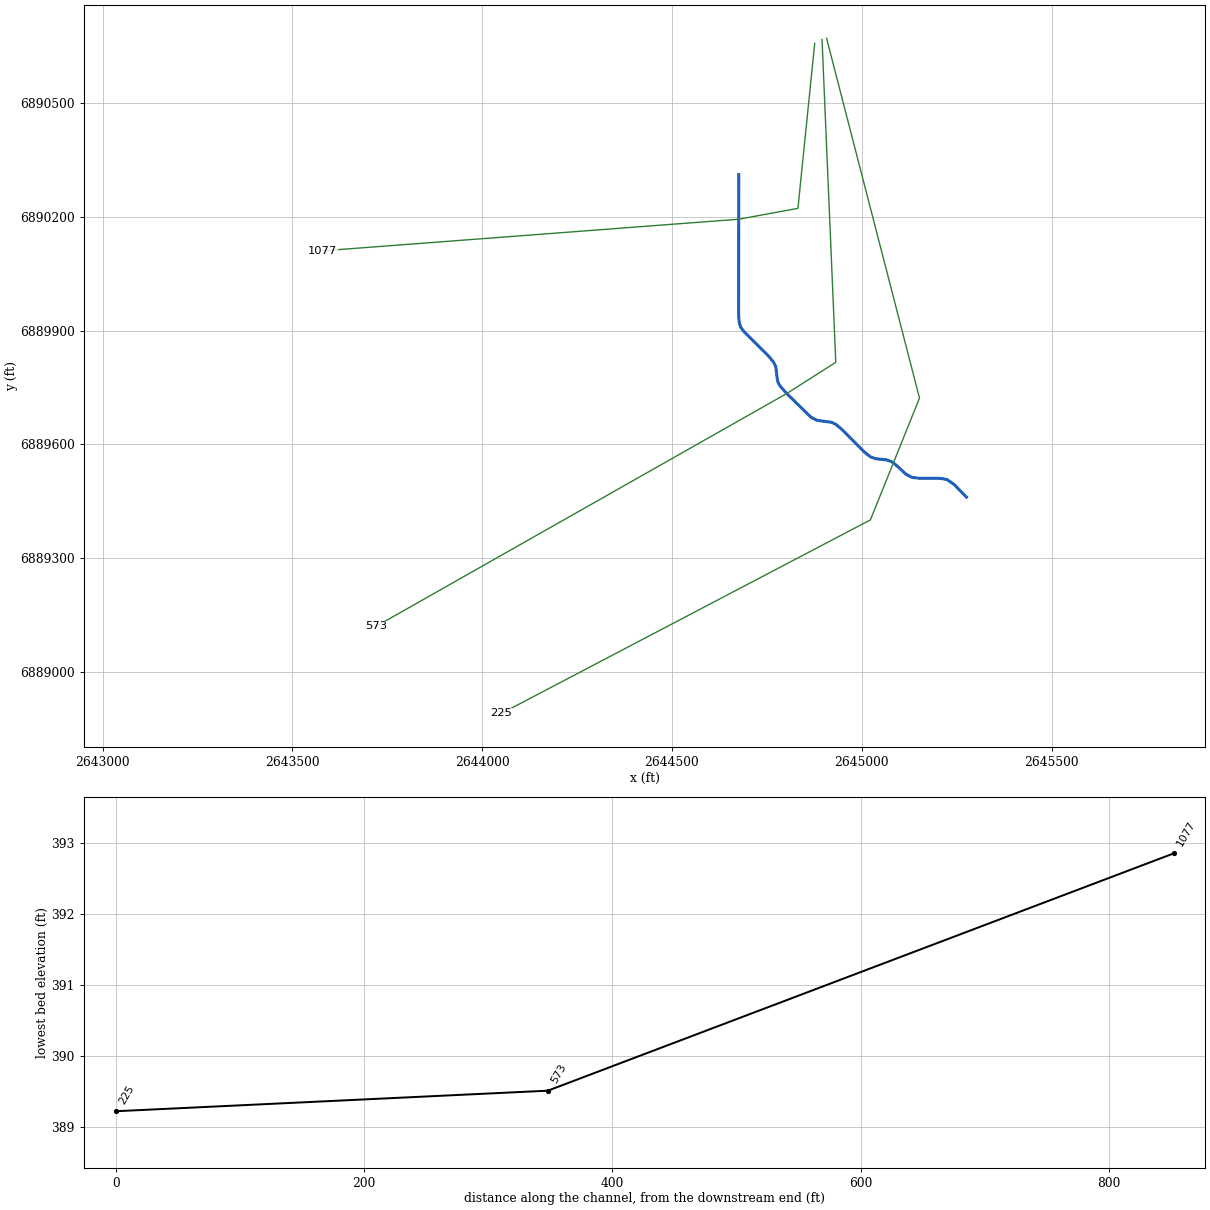
--- Prairie Branch Trib 2.prj (project) ---

Proj Title=Prairie Branch Trib 2 Base Level Engineering
Current Plan=p01
Default Exp/Contr=0.3,0.1
English Units
Geom File=g01
Flow File=f01
Plan File=p01
BEGIN DESCRIPTION:
Prairie Branch Trib 2
END DESCRIPTION:

--- Prairie Branch Trib 2.p01 (plan) ---

Plan Title=Multiple Run
Short Identifier=Multiple
Geom File=g01
Flow File=f01
Subcritical Flow
K Sum by GR= 0
Std Step Tol= 0.01
Critical Tol= 0.01
Num of Std Step Trials= 20
Max Error Tol= 0.3
Flow Tol Ratio= 0.001
Split Flow NTrial= 30
Split Flow Tol= 0.02
Split Flow Ratio= 0.02
Log Output Level= 0
Friction Slope Method= 1
Unsteady Friction Slope Method= 2
Unsteady Bridges Friction Slope Method= 1
Parabolic Critical Depth
Global Vel Dist=  1 , 1 , 1
Global Log Level= 0
CheckData=True
Encroach Param= -1, 0, 0, 0
BEGIN DESCRIPTION:
Multiple Run
END DESCRIPTION:

--- Prairie Branch Trib 2.f01 (steady flow) ---

Flow Title=Multiple
Number of Profiles=7
Profile Names=10-year,25-year,50-year,1pct_min,100-year,1pct_plu,500-year
River Rch & RM= Prairie Branch T,Reach-1,1077
     492     658     792     473     944    1884    1342
River Rch & RM= Prairie Branch T,Reach-1,225
    1753    2480    3097    1910    3810    7603    5778
Boundary for River Rch & Prof#=Prairie Branch T,Reach-1,1
Up Type=0
Dn Type=3
Dn Slope=0.005
Boundary for River Rch & Prof#=Prairie Branch T,Reach-1,2
Up Type=0
Dn Type=3
Dn Slope=0.005
Boundary for River Rch & Prof#=Prairie Branch T,Reach-1,3
Up Type=0
Dn Type=3
Dn Slope=0.005
Boundary for River Rch & Prof#=Prairie Branch T,Reach-1,4
Up Type=0
Dn Type=3
Dn Slope=0.005
Boundary for River Rch & Prof#=Prairie Branch T,Reach-1,5
Up Type=0
Dn Type=3
Dn Slope=0.005
Boundary for River Rch & Prof#=Prairie Branch T,Reach-1,6
Up Type=0
Dn Type=3
Dn Slope=0.005
Boundary for River Rch & Prof#=Prairie Branch T,Reach-1,7
Up Type=0
Dn Type=3
Dn Slope=0.005

--- Prairie Branch Trib 2.g01 (geometry) ---

Geom Title=Existing Conditions

River Reach=Prairie Branch T,Reach-1
Reach XY= 30
      2644676.00      6890311.00      2644675.51      6889945.80
      2644677.05      6889921.44      2644681.47      6889908.55
      2644689.40      6889897.69      2644752.93      6889834.44
      2644767.82      6889817.04      2644773.46      6889804.94
      2644777.54      6889771.63      2644779.97      6889762.64
      2644784.15      6889754.93      2644802.27      6889734.12
      2644866.30      6889671.77      2644882.04      6889663.53
      2644919.95      6889658.46      2644932.04      6889652.82
      2644949.44      6889637.94      2645005.93      6889580.82
      2645023.71      6889566.84      2645036.62      6889562.51
      2645065.29      6889559.28      2645078.17      6889554.86
      2645089.04      6889546.95      2645116.34      6889521.83
      2645131.95      6889513.30      2645150.97      6889510.93
      2645205.92      6889510.81      2645224.60      6889507.61
      2645243.05      6889494.88      2645276.00      6889461.00

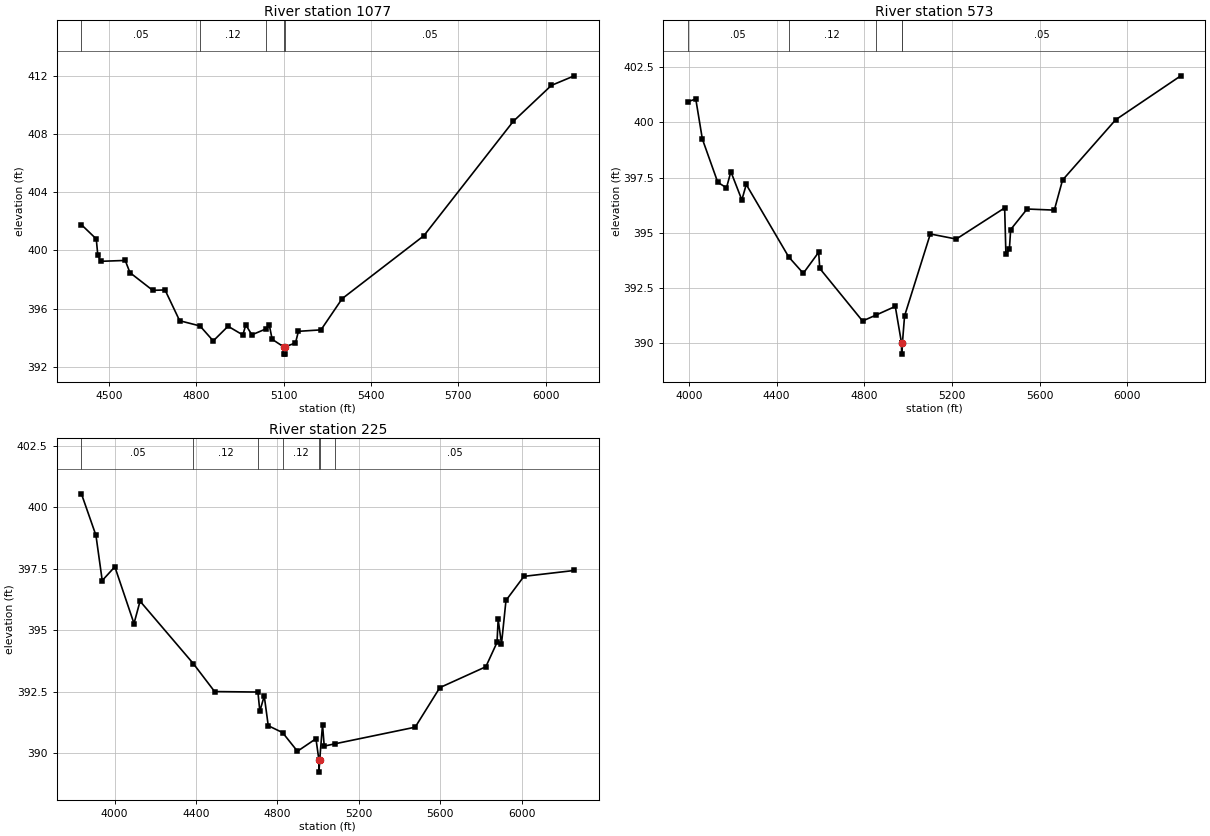
Type RM Length L Ch R = 1,1077,504,504,504
BEGIN DESCRIPTION:
Prairie Branch Trib 2 2.0
END DESCRIPTION:
XS GIS Cut Line= 4
      2644876.13      6890656.96      2644831.87      6890222.10
      2644675.99      6890193.45      2643580.15      6890110.19
#Sta/Elev= 30
  4404.4  401.77  4455.4  400.79  4460.6  399.69  4470.7  399.25  4555.0  399.31
  4571.2  398.47  4649.6  397.25  4691.8  397.28  4742.1  395.16  4812.0  394.80
  4857.6  393.77  4908.5  394.78  4959.3  394.18  4969.5  394.87  4990.4  394.19
  5040.4  394.61  5050.1  394.88  5060.2  393.88  5099.8  393.36  5100.1  392.86
  5103.6  392.86  5103.8  393.36  5140.4  393.63  5150.4  394.43  5228.0  394.53
  5300.9  396.68  5581.7  401.01  5888.9  408.88  6020.1  411.36  6099.0  412.02
#Mann=5,-1,0
  4404.4    0.05       0  4812.0    0.12       0  5040.4    0.05       0
  5099.8    0.07       0  5103.8    0.05       0
Bank Sta=5099.8,5103.8
Exp/Cntr=0.3,0.1

Type RM Length L Ch R = 1,573,348,348,348
BEGIN DESCRIPTION:
Prairie Branch Trib 2 1.0
END DESCRIPTION:
XS GIS Cut Line= 4
      2644895.41      6890666.83      2644931.62      6889816.41
      2644802.27      6889734.12      2643720.41      6889120.83
#Sta/Elev= 30
  3995.5  400.94  4031.4  401.06  4061.4  399.25  4131.7  397.29  4171.5  397.04
  4191.5  397.77  4241.6  396.49  4261.6  397.19  4455.3  393.91  4521.8  393.17
  4591.9  394.12  4597.0  393.39  4792.1  391.01  4851.7  391.27  4941.4  391.67
  4969.9  390.01  4970.1  389.51  4973.9  390.01  4983.8  391.24  5101.2  394.95
  5219.6  394.72  5440.3  396.13  5446.0  394.03  5461.9  394.27  5467.7  395.15
  5542.7  396.08  5666.8  396.03  5704.3  397.39  5946.6  400.12  6243.6  402.11
#Mann=5,-1,0
  3995.5    0.05       0  4455.3    0.12       0  4851.7    0.05       0
  4969.9    0.03       0  4973.9    0.05       0
Bank Sta=4969.9,4973.9
Exp/Cntr=0.3,0.1

Type RM Length L Ch R = 1,225,0,0,0
BEGIN DESCRIPTION:
Prairie Branch Trib 2 3.0
END DESCRIPTION:
XS GIS Cut Line= 4
      2644907.39      6890669.99      2645152.18      6889722.10
      2645022.80      6889401.20      2644050.83      6888891.48
#Sta/Elev= 30
  3837.0  400.55  3908.3  398.86  3939.2  397.02  4001.2  397.58  4095.4  395.27
  4125.1  396.18  4386.7  393.64  4491.6  392.50  4704.5  392.48  4713.8  391.70
  4735.5  392.32  4755.2  391.11  4825.5  390.83  4898.7  390.07  4989.7  390.58
  5004.1  389.72  5004.4  389.22  5008.1  389.72  5022.0  391.15  5030.3  390.28
  5081.2  390.37  5477.4  391.05  5598.5  392.66  5824.7  393.51  5879.6  394.50
  5885.2  395.44  5901.6  394.44  5923.7  396.21  6011.9  397.19  6259.5  397.43
#Mann=7,-1,0
  3837.0    0.05       0  4386.7    0.12       0  4704.5    0.05       0
  4825.5    0.12       0  5004.1    0.07       0  5008.1    0.12       0
  5081.2    0.05       0
Bank Sta=5004.1,5008.1
Exp/Cntr=0.3,0.1

Chan Stop Cuts=-1