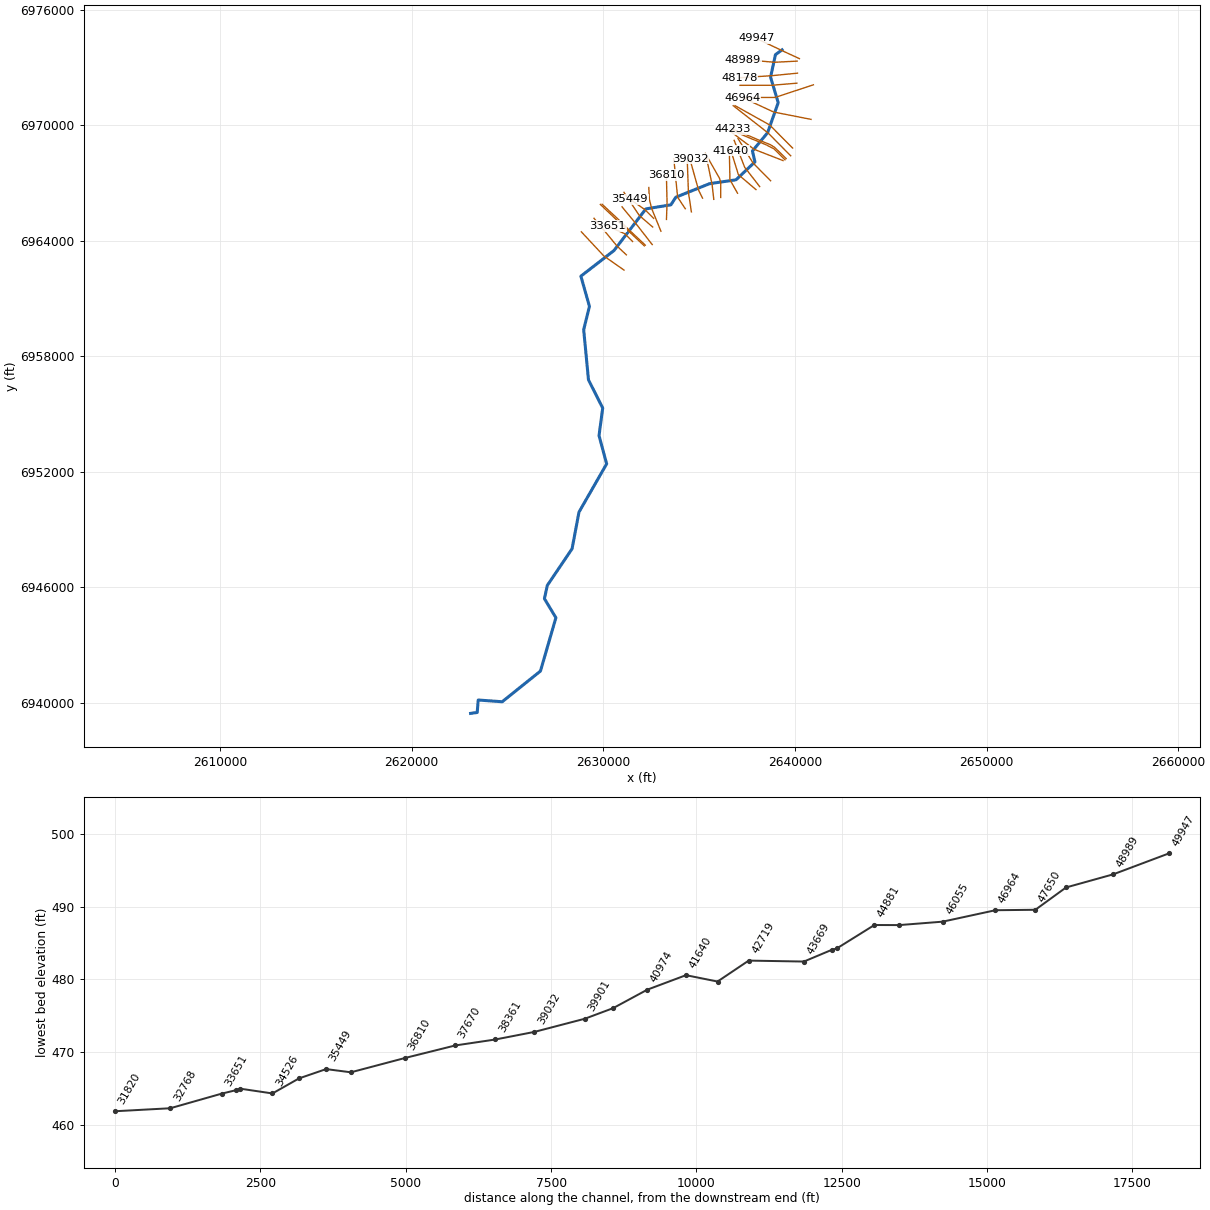
--- Terry Creek.prj (project) ---

Proj Title=Terry Creek Base Level Engineering
Current Plan=p01
Default Exp/Contr=0.3,0.1
English Units
Geom File=g01
Flow File=f01
Plan File=p01
Y Axis Title=Elevation
X Axis Title(PF)=Main Channel Distance
X Axis Title(XS)=Station
BEGIN DESCRIPTION:
Terry Creek
END DESCRIPTION:
DSS Export Rating Curves= 0
DSS Export Rating Curve Sorted= 0
DSS Export Volume Flow Curves= 0
DXF OffsetX= 0
DXF OffsetY= 0
DXF ScaleX= 1
DXF ScaleY= 10

--- Terry Creek.p01 (plan) ---

Plan Title=Multiple Run
Short Identifier=Multiple
Geom File=g01
Flow File=f01
Subcritical Flow
K Sum by GR= 0
Std Step Tol= 0.01
Critical Tol= 0.01
Num of Std Step Trials= 20
Max Error Tol= 0.3
Flow Tol Ratio= 0.001
Split Flow NTrial= 30
Split Flow Tol= 0.02
Split Flow Ratio= 0.02
Log Output Level= 0
Friction Slope Method= 1
Unsteady Friction Slope Method= 2
Unsteady Bridges Friction Slope Method= 1
Parabolic Critical Depth
Global Vel Dist=  1 , 1 , 1
Global Log Level= 0
CheckData=True
Encroach Param= -1, 0, 0, 0
BEGIN DESCRIPTION:
Multiple Run
END DESCRIPTION:

--- Terry Creek.f01 (steady flow) ---

Flow Title=Multiple
Program Version=4.10
Number of Profiles= 7
Profile Names=10-year,25-year,50-year,1pct_min,100-year,1pct_plu,500-year
River Rch & RM=Terry Creek,Reach-1         ,49947
     409     533     631     371     739    1475    1014
River Rch & RM=Terry Creek,Reach-1         ,48989
     654     877    1057     632    1260    2514    1790
River Rch & RM=Terry Creek,Reach-1         ,46055
     915    1243    1509     907    1810    3612    2605
River Rch & RM=Terry Creek,Reach-1         ,40387
    1067    1456    1776    1070    2136    4261    3091
River Rch & RM=Terry Creek,Reach-1         ,35876
    1089    1488    1815    1094    2183    4356    3162
River Rch & RM=Terry Creek,Reach-1         ,35449
    1273    1752    2148    1301    2596    5179    3795
River Rch & RM=Terry Creek,Reach-1         ,34526
    1314    1811    2221    1346    2685    5358    3929
River Rch & RM=Terry Creek,Reach-1         ,33651
    1424    1967    2416    1466    2925    5836    4291
River Rch & RM=Terry Creek,Reach-1         ,30036
    1603    2223    2739    1666    3323    6631    4897
River Rch & RM=Terry Creek,Reach-1         ,23217
    2408    3400    4237    2604    5195   10365    7818
River Rch & RM=Terry Creek,Reach-1         ,14457
    2519    3562    4443    2732    5451   10876    8215
River Rch & RM=Terry Creek,Reach-1         ,11367
    2546    3598    4486    2757    5501   10975    8281
River Rch & RM=Terry Creek,Reach-1         ,9310
    2655    3754    4682    2878    5743   11459    8649
River Rch & RM=Terry Creek,Reach-1         ,4485
    2796    3960    4945    3043    6072   12115    9163
Boundary for River Rch & Prof#=Terry Creek,Reach-1         , 1
Up Type= 0
Dn Type= 3
Dn Slope=0.00103
Boundary for River Rch & Prof#=Terry Creek,Reach-1         , 2
Up Type= 0
Dn Type= 3
Dn Slope=0.00103
Boundary for River Rch & Prof#=Terry Creek,Reach-1         , 3
Up Type= 0
Dn Type= 3
Dn Slope=0.00103
Boundary for River Rch & Prof#=Terry Creek,Reach-1         , 4
Up Type= 0
Dn Type= 3
Dn Slope=0.00103
Boundary for River Rch & Prof#=Terry Creek,Reach-1         , 5
Up Type= 0
Dn Type= 3
Dn Slope=0.00103
Boundary for River Rch & Prof#=Terry Creek,Reach-1         , 6
Up Type= 0
Dn Type= 3
Dn Slope=0.00103
Boundary for River Rch & Prof#=Terry Creek,Reach-1         , 7
Up Type= 0
Dn Type= 3
Dn Slope=0.00103
DSS Import GetInterval= 0
DSS Import GetPeak= 0
DSS Import FillOption= 0

--- Terry Creek.g01 (geometry) ---

Geom Title=Existing Conditions

River Reach=Terry Creek,Reach-1
Reach XY= 30
      2639326.00      6973911.00      2638979.13      6973659.39
      2638726.04      6972490.97      2639123.84      6971166.98
      2638570.17      6969608.70      2637779.43      6968659.42
      2637909.52      6968093.94      2636924.75      6967164.51
      2635531.89      6966959.03      2633784.01      6966257.97
      2633524.44      6965864.42      2632219.94      6965653.50
      2630556.53      6963490.46      2628829.46      6962159.50
      2629276.29      6960590.83      2628975.57      6959381.18
      2629226.03      6956776.71      2629967.92      6955314.30
      2629775.90      6953881.10      2630173.75      6952416.94
      2628729.54      6949909.53      2628370.53      6948008.55
      2627077.58      6946104.95      2626927.59      6945417.05
      2627526.14      6944426.42      2626720.58      6941658.33
      2624724.52      6940064.61      2623473.26      6940155.66
      2623420.66      6939508.26      2623076.00      6939461.00

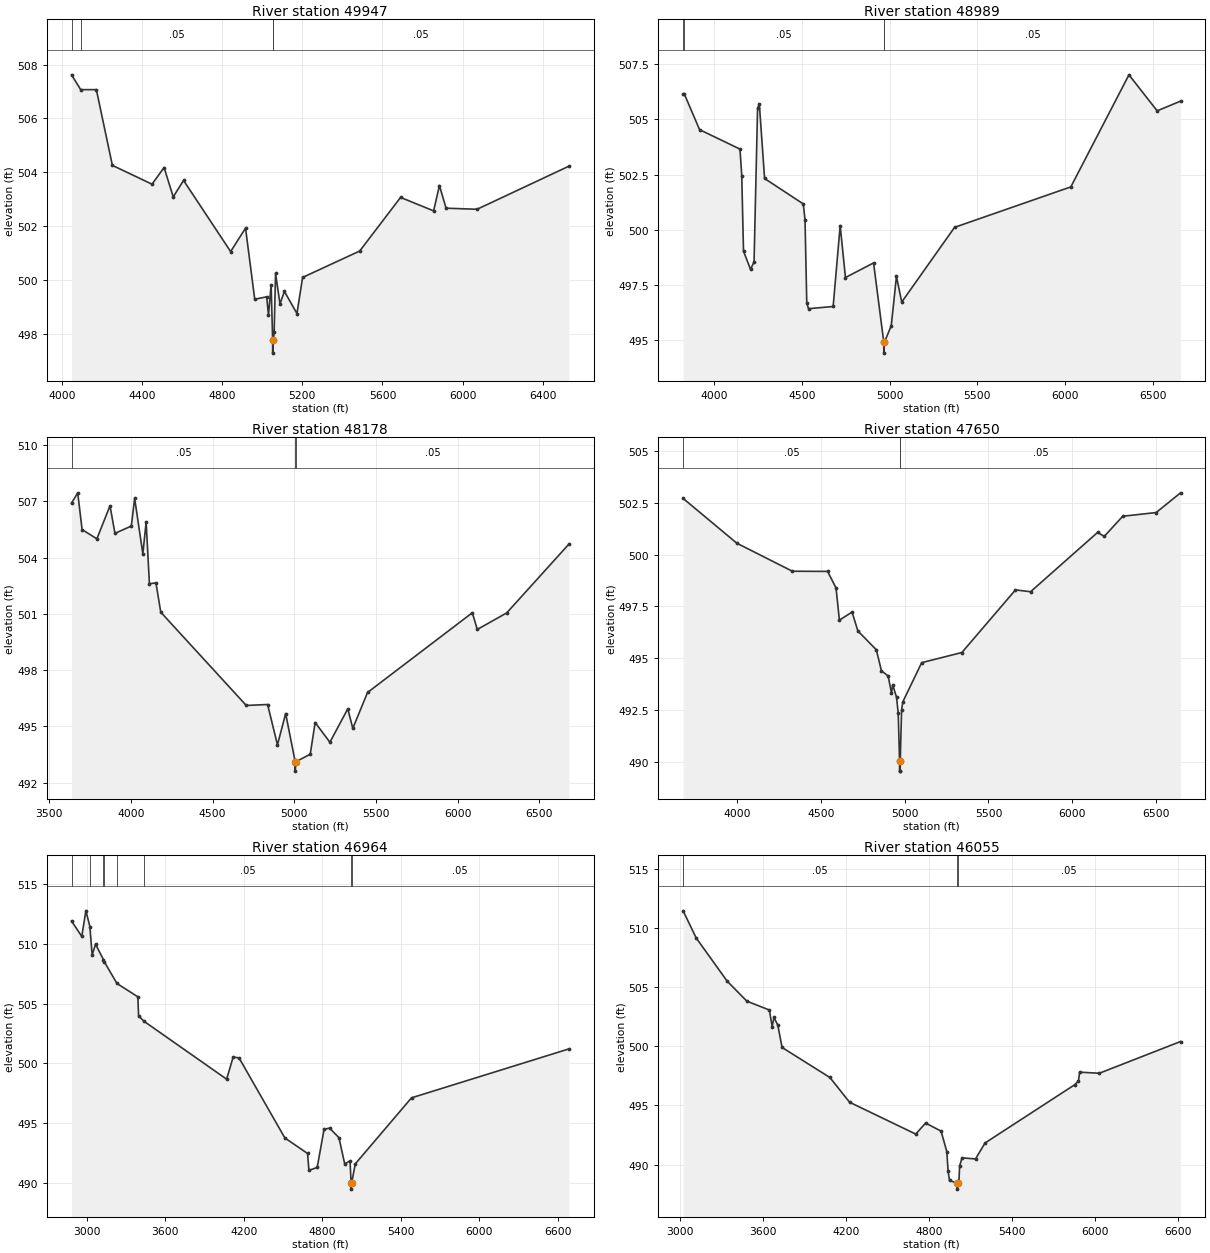
Type RM Length L Ch R = 1,49947,958,958,958
BEGIN DESCRIPTION:
Terry Creek 87.0
END DESCRIPTION:
XS GIS Cut Line= 3
      2640231.11      6973452.96      2639365.85      6973851.41
      2637981.07      6974505.06
#Sta/Elev= 30
  4047.4  507.62  4093.2  507.07  4171.4  507.07  4251.3  504.26  4449.4  503.56
  4509.4  504.18  4555.3  503.09  4606.8  503.70  4841.9  501.06  4916.3  501.93
  4962.2  499.29  5022.0  499.38  5030.8  498.69  5044.1  499.83  5051.6  497.79
  5051.8  497.29  5055.6  497.79  5059.1  498.06  5066.2  500.25  5088.3  499.12
  5110.4  499.58  5173.0  498.76  5201.3  500.10  5486.4  501.08  5690.5  503.07
  5855.5  502.57  5884.5  503.51  5917.7  502.67  6072.5  502.63  6531.3  504.23
#Mann=4,-1,0
  4047.4   0.075       0  4093.2    0.05       0  5051.6    0.03       0
  5055.6    0.05       0
Bank Sta=5051.6,5055.6
Exp/Cntr=0.3,0.1

Type RM Length L Ch R = 1,48989,811,811,811
BEGIN DESCRIPTION:
Mapping XS 9ac187eb
END DESCRIPTION:
XS GIS Cut Line= 3
      2640109.53      6973324.50      2638935.94      6973265.48
      2637283.14      6973404.37
#Sta/Elev= 30
  3823.6  506.14  3830.1  506.15  3917.2  504.53  4147.5  503.65  4157.6  502.45
  4167.6  499.03  4207.6  498.21  4227.6  498.55  4247.7  505.49  4257.7  505.69
  4287.7  502.32  4508.0  501.17  4518.0  500.46  4528.0  496.68  4538.0  496.43
  4678.2  496.53  4718.3  500.19  4748.3  497.84  4908.5  498.50  4966.6  494.92
  4966.8  494.42  4970.6  494.92  5009.3  495.66  5038.8  497.89  5068.9  496.73
  5369.9  500.11  6032.2  501.94  6363.4  507.01  6524.0  505.38  6657.3  505.82
#Mann=4,-1,0
  3823.6   0.075       0  3830.1    0.05       0  4966.6    0.03       0
  4970.6    0.05       0
Bank Sta=4966.6,4970.6
Exp/Cntr=0.3,0.1

Type RM Length L Ch R = 1,48178,528,528,528
BEGIN DESCRIPTION:
Mapping XS 9f08dd80
END DESCRIPTION:
XS GIS Cut Line= 3
      2640130.39      6972699.50      2638779.69      6972567.56
      2637095.66      6972459.92
#Sta/Elev= 30
  3636.4  506.90  3674.2  507.45  3701.1  505.49  3791.5  505.00  3871.9  506.76
  3902.1  505.29  4002.5  505.68  4022.6  507.16  4072.9  504.20  4093.0  505.90
  4113.1  502.61  4153.2  502.65  4182.5  501.09  4705.9  496.12  4836.5  496.17
  4896.8  494.02  4947.0  495.69  5005.3  493.12  5005.5  492.62  5009.3  493.12
  5097.4  493.52  5127.5  495.21  5217.7  494.16  5327.2  495.94  5358.0  494.90
  5448.1  496.81  6089.5  501.06  6119.9  500.17  6299.9  501.05  6681.0  504.72
#Mann=3,-1,0
  3636.4    0.05       0  5005.3    0.03       0  5009.3    0.05       0
Bank Sta=5005.3,5009.3
Exp/Cntr=0.3,0.1

Type RM Length L Ch R = 1,47650,686,686,686
BEGIN DESCRIPTION:
Mapping XS 002264bd
END DESCRIPTION:
XS GIS Cut Line= 3
      2640095.71      6972178.67      2638786.64      6972071.03
      2637130.74      6972067.56
#Sta/Elev= 30
  3677.2  502.71  3998.0  500.55  4329.1  499.20  4539.8  499.19  4590.0  498.39
  4610.1  496.84  4685.7  497.23  4720.4  496.32  4830.8  495.41  4860.9  494.40
  4901.0  494.15  4921.1  493.32  4928.1  493.73  4951.2  493.12  4961.2  492.35
  4969.3  490.06  4969.5  489.56  4973.0  489.56  4973.3  490.06  4981.3  492.50
  4988.5  492.90  5101.3  494.79  5341.3  495.28  5661.3  498.30  5751.3  498.21
  6151.3  501.07  6191.3  500.88  6301.3  501.85  6501.3  502.03  6646.6  502.98
#Mann=3,-1,0
  3677.2    0.05       0  4969.3    0.03       0  4973.3    0.05       0
Bank Sta=4969.3,4973.3
Exp/Cntr=0.3,0.1

Type RM Length L Ch R = 1,46964,909,909,909
BEGIN DESCRIPTION:
Mapping XS 62603502
END DESCRIPTION:
XS GIS Cut Line= 3
      2640960.23      6972095.33      2638963.72      6971439.09
      2637262.33      6971432.14
#Sta/Elev= 30
  2882.3  511.91  2960.4  510.62  2992.0  512.76  3022.5  511.45  3039.8  509.06
  3065.7  509.97  3126.0  508.69  3132.9  508.50  3229.4  506.69  3389.6  505.57
  3394.9  503.98  3436.2  503.53  4068.0  498.69  4118.3  500.55  4163.4  500.46
  4513.2  493.78  4686.8  492.48  4697.3  491.07  4760.4  491.31  4813.1  494.50
  4855.2  494.60  4926.7  493.80  4971.0  491.60  5011.6  491.87  5019.6  490.00
  5019.9  489.50  5023.6  490.00  5051.6  491.61  5481.6  497.13  6685.3  501.22
#Mann=8,-1,0
  2882.3   0.075       0  3022.5    0.05       0  3126.0   0.075       0
  3132.9    0.05       0  3229.4   0.075       0  3436.2    0.05       0
  5019.6    0.03       0  5023.6    0.05       0
Bank Sta=5019.6,5023.6
Exp/Cntr=0.3,0.1

Type RM Length L Ch R = 1,46055,748,748,748
BEGIN DESCRIPTION:
Mapping XS 7bba2ad4
END DESCRIPTION:
XS GIS Cut Line= 3
      2640838.72      6970300.20      2638887.33      6970682.14
      2637422.06      6971355.75
#Sta/Elev= 30
  3020.3  511.44  3114.8  509.15  3339.0  505.50  3481.6  503.81  3644.6  503.06
  3665.0  501.66  3677.8  502.43  3705.8  501.79  3736.4  499.90  4082.8  497.36
  4225.5  495.27  4704.4  492.58  4775.7  493.51  4887.8  492.83  4929.2  491.10
  4938.7  489.43  4948.9  488.66  5004.6  488.43  5005.0  487.93  5009.1  488.43
  5016.8  488.56  5022.3  489.91  5039.8  490.57  5137.2  490.48  5206.1  491.83
  5854.0  496.74  5882.5  497.06  5890.7  497.81  6033.7  497.72  6621.4  500.40
#Mann=3,-1,0
  3020.3    0.05       0  5004.6    0.03       0  5009.1    0.05       0
Bank Sta=5004.6,5009.1
Exp/Cntr=0.3,0.1

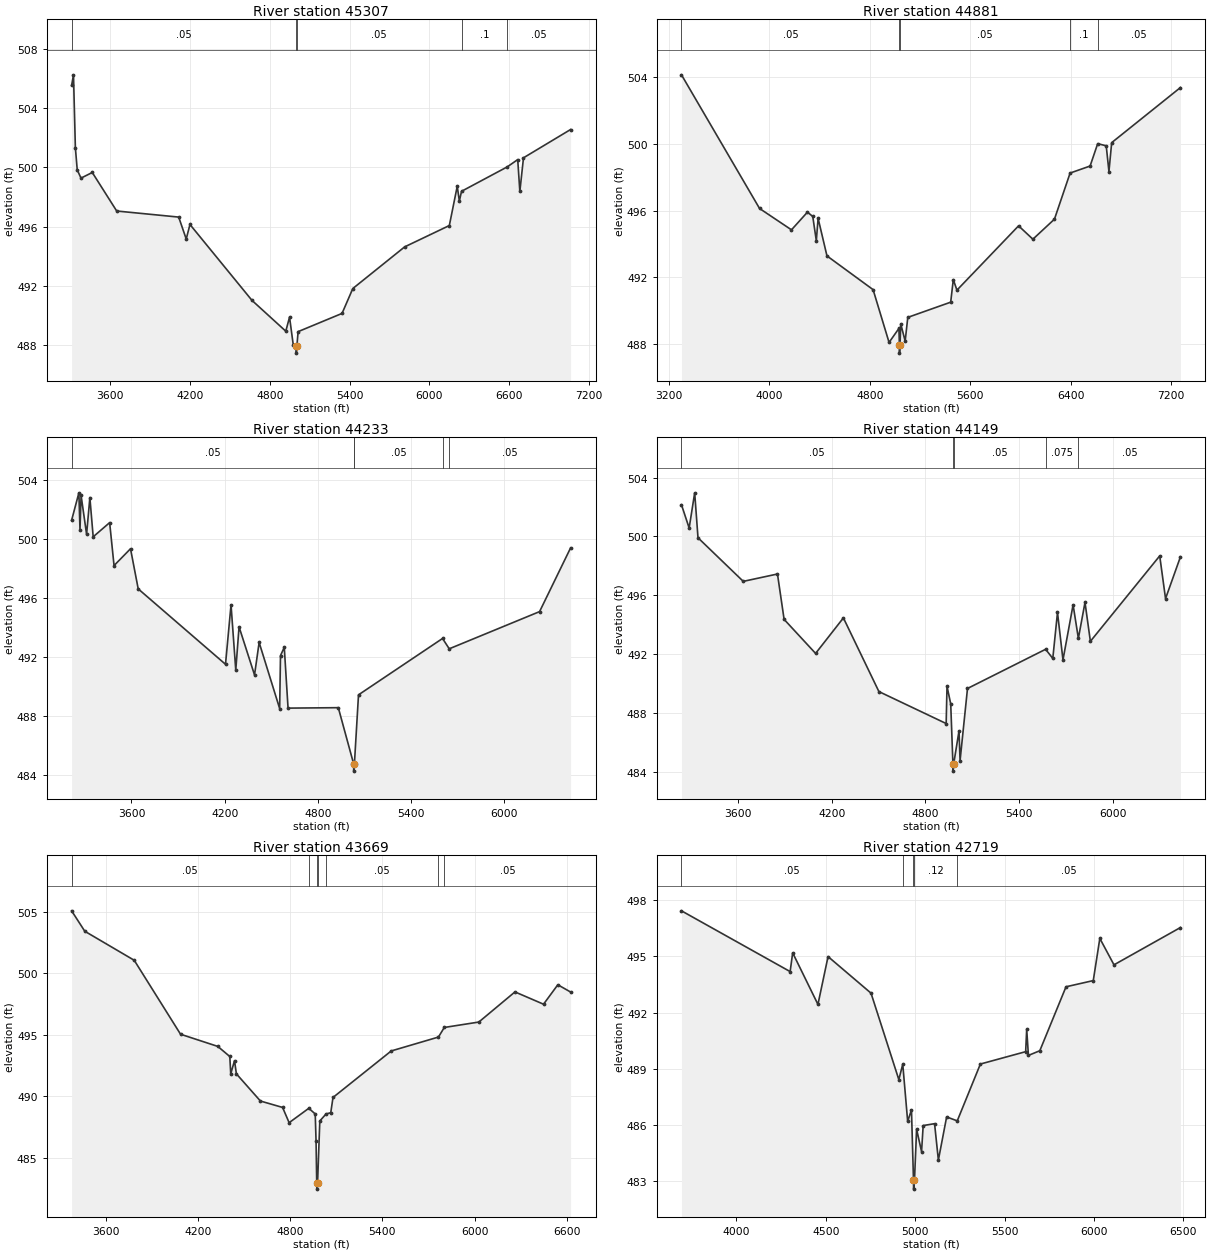
Type RM Length L Ch R = 1,45307,426,426,426
BEGIN DESCRIPTION:
Terry Creek 80.0
END DESCRIPTION:
XS GIS Cut Line= 3
      2639875.99      6968811.01      2638676.00      6970011.00
      2636875.97      6971011.02
#Sta/Elev= 30
  3308.0  505.52  3322.1  506.24  3336.3  501.32  3350.4  499.82  3378.7  499.27
  3463.5  499.65  3647.4  497.05  4114.1  496.64  4170.7  495.16  4198.9  496.14
  4665.6  491.02  4920.2  488.94  4948.5  489.89  4976.8  487.99  4999.1  487.96
  4999.7  487.46  5004.0  487.96  5013.0  488.91  5343.7  490.14  5424.9  491.82
  5815.0  494.63  6151.3  496.07  6210.8  498.72  6226.8  497.72  6243.1  498.38
  6587.6  500.03  6666.1  500.52  6682.1  498.37  6709.5  500.64  7064.2  502.55
#Mann=5,-1,0
  3308.0    0.05       0  4999.1    0.03       0  5004.0    0.05       0
  6243.1     0.1       0  6587.6    0.05       0
Bank Sta=4999.1,5004
Exp/Cntr=0.3,0.1

Type RM Length L Ch R = 1,44881,648,648,648
BEGIN DESCRIPTION:
Terry Creek 79.0
END DESCRIPTION:
XS GIS Cut Line= 3
      2639776.02      6968410.98      2638576.00      6969611.00
      2636776.02      6971010.98
#Sta/Elev= 30
  3298.4  504.13  3920.7  496.13  4175.2  494.85  4302.5  495.91  4344.9  495.65
  4373.2  494.20  4387.4  495.54  4458.1  493.29  4825.8  491.27  4953.1  488.11
  5031.7  488.95  5035.5  487.97  5036.2  487.47  5040.5  487.97  5046.2  489.22
  5081.4  488.19  5102.3  489.61  5444.3  490.52  5465.1  491.87  5494.1  491.24
  5985.4  495.09  6099.5  494.29  6271.4  495.49  6396.1  498.25  6555.5  498.67
  6616.0  500.01  6684.0  499.88  6705.7  498.34  6727.5  500.07  7275.8  503.37
#Mann=5,-1,0
  3298.4    0.05       0  5035.5    0.03       0  5040.5    0.05       0
  6396.1     0.1       0  6616.0    0.05       0
Bank Sta=5035.5,5040.5
Exp/Cntr=0.3,0.1

Type RM Length L Ch R = 1,44233,84,84,84
BEGIN DESCRIPTION:
Mapping XS 44981738
END DESCRIPTION:
XS GIS Cut Line= 6
      2639536.64      6968265.47      2638939.42      6968845.34
      2638720.67      6968984.23      2638076.27      6969240.97
      2637673.47      6969417.06      2636755.38      6969779.37
#Sta/Elev= 30
  3214.8  501.25  3261.6  503.11  3268.7  500.61  3275.7  502.94  3311.2  500.30
  3332.3  502.79  3353.6  500.13  3459.6  501.09  3487.9  498.18  3593.9  499.32
  3643.5  496.60  4205.3  491.49  4240.9  495.52  4271.4  491.09  4292.5  494.03
  4392.1  490.77  4421.8  492.97  4553.9  488.49  4559.3  492.08  4583.6  492.64
  4607.9  488.52  4931.4  488.55  5029.9  484.75  5030.6  484.25  5035.1  484.75
  5061.4  489.42  5602.3  493.24  5645.4  492.54  6226.9  495.06  6426.6  499.38
#Mann=5,-1,0
  3214.8    0.05       0  5029.9    0.03       0  5035.1    0.05       0
  5602.3   0.075       0  5645.4    0.05       0
Bank Sta=5029.9,5035.1
Exp/Cntr=0.3,0.1

Type RM Length L Ch R = 1,44149,480,480,480
BEGIN DESCRIPTION:
Mapping XS a1f4bbe0
END DESCRIPTION:
XS GIS Cut Line= 6
      2639477.60      6968202.99      2638908.17      6968765.48
      2638508.98      6968972.18      2638036.83      6969170.66
      2637710.37      6969298.79      2636713.72      6969723.81
#Sta/Elev= 30
  3237.9  502.15  3287.1  500.57  3322.5  502.96  3343.7  499.91  3633.7  496.95
  3852.8  497.45  3895.3  494.37  4097.0  492.06  4275.1  494.47  4502.5  489.47
  4933.4  487.30  4938.8  489.83  4962.6  488.63  4976.6  484.57  4977.3  484.07
  4981.8  484.57  5015.8  486.81  5022.4  484.78  5070.0  489.68  5570.3  492.34
  5616.4  491.72  5646.5  494.84  5681.6  491.62  5746.4  495.36  5780.2  493.08
  5822.7  495.52  5857.2  492.88  6301.3  498.68  6338.6  495.78  6434.2  498.62
#Mann=5,-1,0
  3237.9    0.05       0  4976.6    0.03       0  4981.8    0.05       0
  5570.3   0.075       0  5780.2    0.05       0
Bank Sta=4976.6,4981.8
Exp/Cntr=0.3,0.1

Type RM Length L Ch R = 1,43669,950,950,950
BEGIN DESCRIPTION:
Terry Creek 77.0
END DESCRIPTION:
XS GIS Cut Line= 3
      2639375.99      6968161.00      2637863.19      6968748.03
      2636565.28      6969726.63
#Sta/Elev= 30
  3377.3  505.08  3463.1  503.42  3784.9  501.06  4086.4  495.05  4328.8  494.06
  4407.0  493.24  4413.1  491.83  4437.7  492.90  4449.9  491.83  4606.4  489.62
  4750.6  489.10  4793.2  487.86  4921.3  489.03  4963.1  488.57  4968.5  486.35
  4972.8  482.96  4973.6  482.46  4978.3  482.96  4993.0  488.00  5033.6  488.57
  5064.2  488.67  5078.8  489.91  5457.7  493.69  5765.2  494.82  5803.3  495.60
  6028.1  496.04  6263.3  498.49  6449.3  497.49  6542.3  499.07  6625.5  498.48
#Mann=7,-1,0
  3377.3    0.05       0  4921.3    0.12       0  4972.8    0.07       0
  4978.3    0.12       0  5033.6    0.05       0  5765.2   0.075       0
  5803.3    0.05       0
Bank Sta=4972.8,4978.3
Exp/Cntr=0.3,0.1

Type RM Length L Ch R = 1,42719,536,536,536
BEGIN DESCRIPTION:
Terry Creek 76.0
END DESCRIPTION:
XS GIS Cut Line= 3
      2638727.60      6967112.71      2637806.12      6968040.72
      2637026.24      6969303.63
#Sta/Elev= 30
  3692.2  497.43  4300.2  494.19  4314.4  495.19  4455.8  492.44  4512.4  494.99
  4752.8  493.04  4908.4  488.43  4930.4  489.25  4957.9  486.20  4979.1  486.82
  4990.4  483.09  4991.3  482.59  4996.0  483.09  5008.0  485.78  5035.6  484.59
  5044.6  485.98  5108.4  486.08  5129.7  484.14  5175.9  486.44  5235.3  486.23
  5364.7  489.26  5618.1  489.92  5623.9  491.11  5633.5  489.72  5697.3  489.97
  5843.9  493.38  5996.4  493.71  6033.1  495.96  6112.3  494.55  6484.3  496.54
#Mann=5,-1,0
  3692.2    0.05       0  4930.4    0.12       0  4990.4    0.07       0
  4996.0    0.12       0  5235.3    0.05       0
Bank Sta=4990.4,4996
Exp/Cntr=0.3,0.1

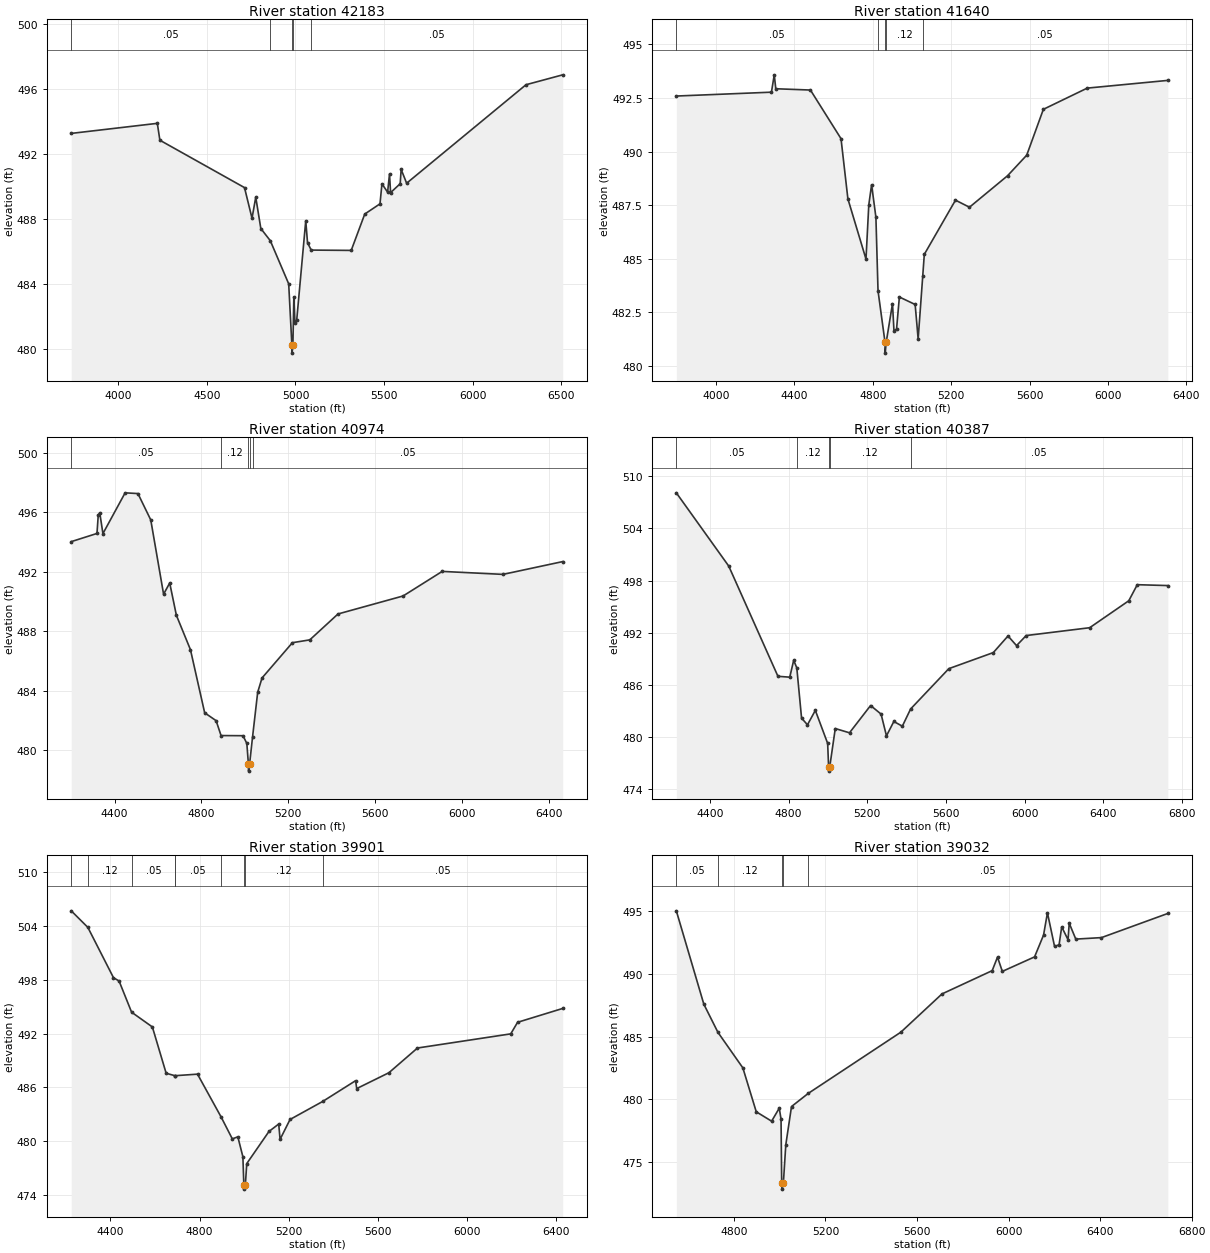
Type RM Length L Ch R = 1,42183,543,543,543
BEGIN DESCRIPTION:
Terry Creek 75.0
END DESCRIPTION:
XS GIS Cut Line= 3
      2638158.16      6966810.62      2637376.00      6967811.00
      2636826.01      6969210.98
#Sta/Elev= 30
  3734.3  493.26  4220.1  493.88  4234.6  492.84  4712.2  489.92  4754.6  488.03
  4775.7  489.33  4804.3  487.40  4857.7  486.65  4961.6  483.99  4979.6  480.22
  4980.5  479.72  4985.3  480.22  4990.6  483.19  4996.9  481.55  5006.8  481.75
  5057.9  487.88  5067.9  486.52  5088.8  486.07  5314.5  486.05  5390.9  488.29
  5476.9  488.92  5487.9  490.15  5519.9  489.64  5530.6  490.76  5536.7  489.61
  5590.9  490.16  5596.3  491.04  5627.3  490.19  6301.0  496.26  6508.3  496.87
#Mann=5,-1,0
  3734.3    0.05       0  4857.7    0.12       0  4979.6    0.07       0
  4985.3    0.12       0  5088.8    0.05       0
Bank Sta=4979.6,4985.3
Exp/Cntr=0.3,0.1

Type RM Length L Ch R = 1,41640,666,666,666
BEGIN DESCRIPTION:
Terry Creek 74.0
END DESCRIPTION:
XS GIS Cut Line= 3
      2637963.71      6966654.38      2637045.92      6967431.03
      2636658.58      6968677.33
#Sta/Elev= 30
  3797.7  492.59  4283.0  492.77  4297.3  493.58  4305.1  492.93  4481.9  492.87
  4637.9  490.60  4673.0  487.79  4765.3  484.98  4779.6  487.51  4793.9  488.45
  4815.9  486.93  4826.7  483.50  4862.5  481.09  4863.4  480.59  4868.3  481.09
  4900.5  482.90  4908.2  481.61  4921.3  481.72  4935.6  483.21  5016.1  482.86
  5031.4  481.25  5055.0  484.21  5062.8  485.20  5221.9  487.73  5293.2  487.40
  5487.6  488.87  5585.3  489.83  5670.2  491.97  5894.0  492.96  6305.1  493.32
#Mann=5,-1,0
  3797.7    0.05       0  4826.7    0.12       0  4862.5    0.07       0
  4868.3    0.12       0  5055.0    0.05       0
Bank Sta=4862.5,4868.3
Exp/Cntr=0.3,0.1

Type RM Length L Ch R = 1,40974,587,587,587
BEGIN DESCRIPTION:
Terry Creek 73.0
END DESCRIPTION:
XS GIS Cut Line= 3
      2637001.94      6966466.83      2636605.95      6967161.60
      2636574.84      6968626.27
#Sta/Elev= 30
  4200.3  494.02  4318.9  494.57  4324.7  495.79  4331.7  495.96  4346.3  494.56
  4448.6  497.30  4507.6  497.25  4566.7  495.48  4625.8  490.49  4654.0  491.24
  4684.8  489.07  4749.6  486.76  4815.1  482.52  4867.8  481.99  4890.6  480.99
  4991.7  480.98  5009.4  480.46  5016.5  479.10  5017.4  478.60  5022.3  479.10
  5035.7  480.89  5059.4  483.90  5079.4  484.86  5219.4  487.23  5299.5  487.42
  5429.5  489.16  5729.6  490.37  5909.6  492.02  6189.7  491.82  6465.0  492.68
#Mann=5,-1,0
  4200.3    0.05       0  4890.6    0.12       0  5016.5    0.07       0
  5022.3    0.12       0  5035.7    0.05       0
Bank Sta=5016.5,5022.3
Exp/Cntr=0.3,0.1

Type RM Length L Ch R = 1,40387,486,486,486
BEGIN DESCRIPTION:
Terry Creek 71.0
END DESCRIPTION:
XS GIS Cut Line= 4
      2636123.44      6966244.60      2636126.00      6967011.00
      2636071.51      6967222.17      2635321.44      6968536.17
#Sta/Elev= 30
  4229.4  508.09  4495.8  499.66  4745.8  486.98  4805.8  486.88  4825.8  488.82
  4841.6  487.95  4865.8  482.17  4895.8  481.40  4935.8  483.06  4998.4  479.26
  5003.2  476.57  5004.1  476.07  5009.0  476.57  5037.1  480.97  5109.4  480.48
  5216.6  483.62  5269.9  482.63  5297.2  480.13  5334.7  481.78  5377.9  481.24
  5419.9  483.22  5614.1  487.86  5840.2  489.71  5914.9  491.62  5958.2  490.51
  6007.2  491.67  6329.8  492.57  6528.5  495.67  6571.7  497.52  6726.9  497.42
#Mann=5,-1,0
  4229.4    0.05       0  4841.6    0.12       0  5003.2    0.07       0
  5009.0    0.12       0  5419.9    0.05       0
Bank Sta=5003.2,5009
Exp/Cntr=0.3,0.1

Type RM Length L Ch R = 1,39901,869,869,869
BEGIN DESCRIPTION:
Terry Creek 70.0
END DESCRIPTION:
XS GIS Cut Line= 3
      2635762.33      6966147.45      2635676.00      6966911.00
      2635380.70      6968319.56
#Sta/Elev= 30
  4223.8  505.70  4298.4  503.85  4413.6  498.23  4438.7  497.86  4494.9  494.38
  4588.2  492.73  4650.1  487.56  4690.6  487.28  4691.3  487.29  4790.9  487.46
  4896.7  482.69  4947.3  480.23  4972.1  480.46  4994.8  478.23  4999.0  475.12
  5000.1  474.62  5005.9  475.12  5012.1  477.47  5111.9  481.06  5155.7  481.89
  5161.8  480.18  5206.6  482.40  5353.1  484.41  5501.0  486.73  5506.1  485.85
  5650.7  487.62  5779.0  490.38  6197.9  491.96  6228.5  493.25  6431.4  494.80
#Mann=9,-1,0
  4223.8    0.05       0  4298.4    0.12       0  4494.9    0.05       0
  4690.6    0.12       0  4691.3    0.05       0  4896.7    0.12       0
  4999.0    0.07       0  5005.9    0.12       0  5353.1    0.05       0
Bank Sta=4999,5005.9
Exp/Cntr=0.3,0.1

Type RM Length L Ch R = 1,39032,671,671,671
BEGIN DESCRIPTION:
Terry Creek 69.0
END DESCRIPTION:
XS GIS Cut Line= 3
      2635175.98      6966211.03      2634976.00      6966611.00
      2634512.63      6968247.07
#Sta/Elev= 30
  4548.2  495.05  4668.4  487.59  4730.0  485.34  4838.9  482.50  4897.5  478.99
  4964.6  478.24  4998.0  479.28  5005.8  478.40  5008.6  473.31  5009.8  472.81
  5016.0  473.31  5026.6  476.36  5051.5  479.41  5124.6  480.46  5529.1  485.35
  5709.1  488.41  5928.4  490.27  5951.6  491.35  5972.7  490.21  6113.6  491.37
  6152.8  493.11  6169.8  494.89  6201.0  492.20  6220.7  492.34  6232.2  493.77
  6259.8  492.74  6265.0  494.06  6293.7  492.79  6405.9  492.91  6695.8  494.84
#Mann=5,-1,0
  4548.2    0.05       0  4730.0    0.12       0  5008.6    0.07       0
  5016.0    0.12       0  5124.6    0.05       0
Bank Sta=5008.6,5016
Exp/Cntr=0.3,0.1

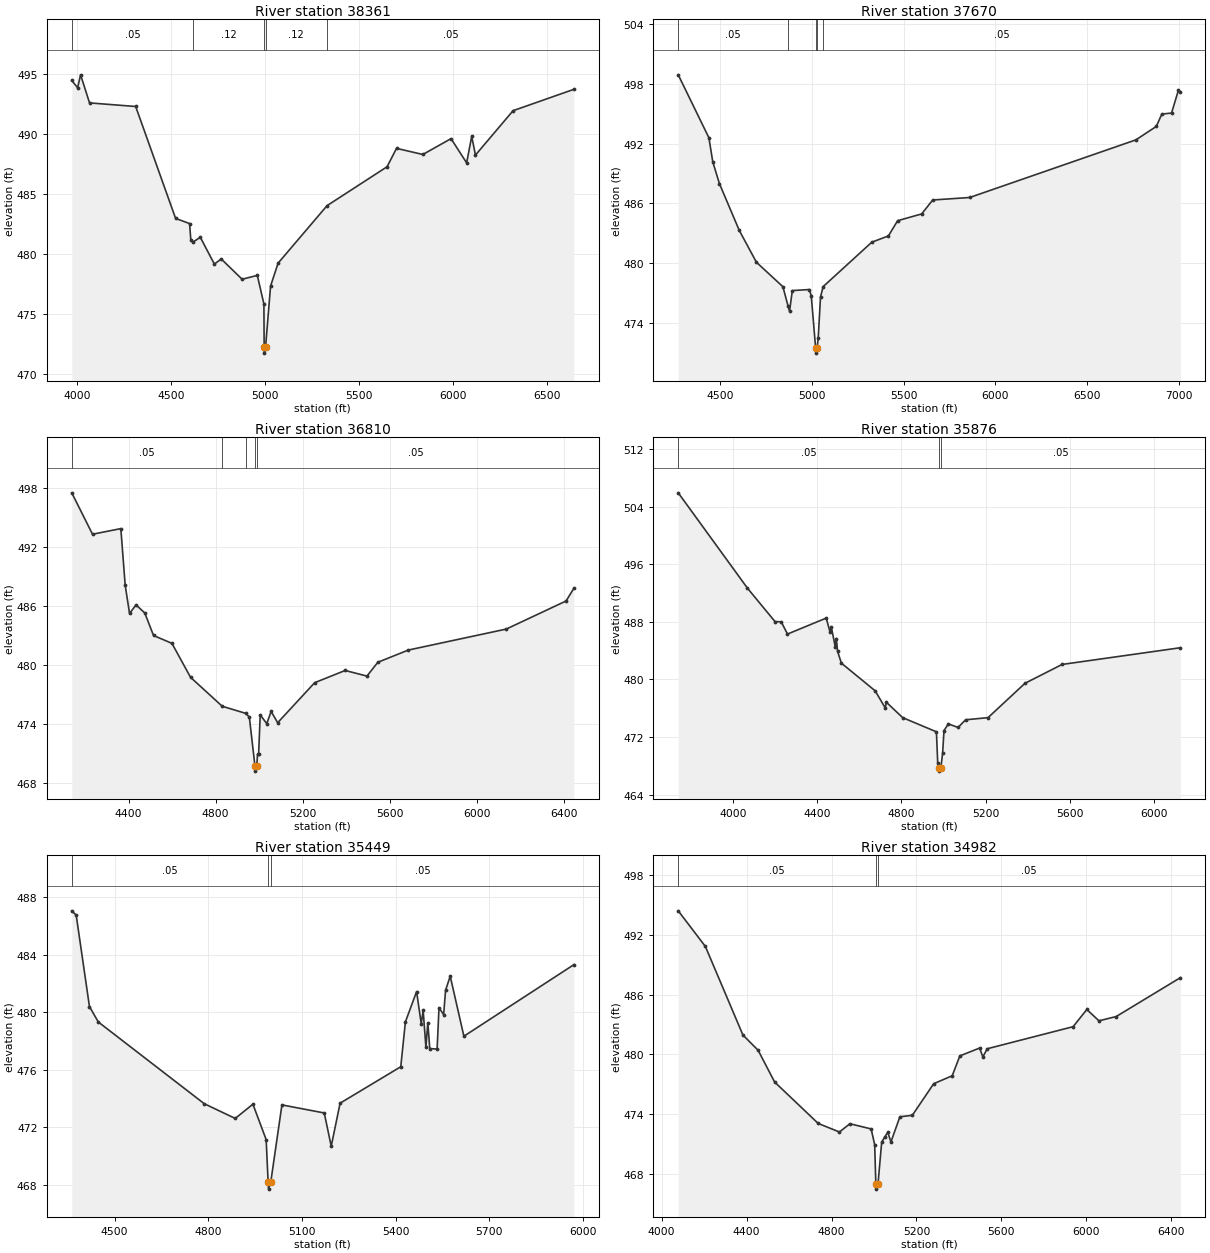
Type RM Length L Ch R = 1,38361,691,691,691
BEGIN DESCRIPTION:
Mapping XS 7c89a99c
END DESCRIPTION:
XS GIS Cut Line= 3
      2634595.66      6965494.67      2634439.42      6966515.48
      2634380.39      6968154.32
#Sta/Elev= 30
  3971.5  494.50  4002.7  493.89  4018.4  494.97  4066.1  492.63  4311.7  492.33
  4524.2  483.00  4598.6  482.57  4605.1  481.23  4616.5  481.02  4655.7  481.43
  4730.5  479.19  4767.0  479.62  4878.3  477.93  4959.2  478.25  4994.2  475.87
  4995.6  472.27  4996.8  471.77  5003.1  472.27  5029.7  477.36  5069.8  479.27
  5330.1  484.06  5650.1  487.31  5700.2  488.84  5840.3  488.33  5990.4  489.65
  6073.4  487.63  6100.4  489.84  6120.4  488.28  6320.6  491.98  6644.1  493.76
#Mann=5,-1,0
  3971.5    0.05       0  4616.5    0.12       0  4995.6    0.07       0
  5003.1    0.12       0  5330.1    0.05       0
Bank Sta=4995.6,5003.1
Exp/Cntr=0.3,0.1

Type RM Length L Ch R = 1,37670,860,860,860
BEGIN DESCRIPTION:
Terry Creek 66.0
END DESCRIPTION:
XS GIS Cut Line= 3
      2634276.02      6965660.97      2633876.00      6966261.00
      2633676.00      6968260.97
#Sta/Elev= 30
  4274.3  498.90  4441.1  492.58  4462.1  490.17  4498.2  487.98  4606.4  483.27
  4699.5  480.08  4843.7  477.62  4872.1  475.65  4879.8  475.16  4894.8  477.23
  4987.9  477.34  4998.0  476.68  5021.7  471.45  5022.9  470.95  5029.5  471.45
  5035.7  472.44  5048.2  476.59  5062.6  477.63  5327.1  482.09  5417.5  482.72
  5467.8  484.25  5598.4  484.93  5658.7  486.33  5859.7  486.58  6764.2  492.37
  6874.8  493.72  6904.9  494.96  6957.7  495.06  6995.4  497.37  7005.4  497.19
#Mann=5,-1,0
  4274.3    0.05       0  4872.1    0.12       0  5021.7    0.07       0
  5029.5    0.12       0  5062.6    0.05       0
Bank Sta=5021.7,5029.5
Exp/Cntr=0.3,0.1

Type RM Length L Ch R = 1,36810,934,934,934
BEGIN DESCRIPTION:
Terry Creek 64.0
END DESCRIPTION:
XS GIS Cut Line= 3
      2633293.58      6965105.78      2633326.00      6965961.00
      2633290.11      6967411.32
#Sta/Elev= 30
  4139.0  497.47  4234.3  493.27  4364.4  493.84  4384.4  488.10  4404.4  485.24
  4434.4  486.10  4474.5  485.28  4514.5  483.00  4599.2  482.20  4684.6  478.76
  4830.2  475.82  4939.6  475.09  4954.8  474.71  4980.7  469.74  4981.9  469.24
  4989.0  469.74  4992.3  470.93  4997.3  470.93  5004.8  474.94  5034.8  474.06
  5054.9  475.29  5084.9  474.15  5254.9  478.21  5395.0  479.45  5495.0  478.88
  5545.0  480.28  5685.0  481.52  6135.2  483.65  6409.9  486.50  6445.6  487.78
#Mann=5,-1,0
  4139.0    0.05       0  4830.2    0.12       0  4939.6    0.05       0
  4980.7    0.03       0  4989.0    0.05       0
Bank Sta=4980.7,4989
Exp/Cntr=0.3,0.1

Type RM Length L Ch R = 1,35876,427,427,427
BEGIN DESCRIPTION:
Terry Creek 62.0
END DESCRIPTION:
XS GIS Cut Line= 4
      2633005.39      6964491.16      2632526.00      6965661.00
      2632403.94      6966142.54      2632372.69      6966764.03
#Sta/Elev= 30
  3740.3  505.93  4069.0  492.68  4199.8  488.04  4229.2  488.01  4258.9  486.31
  4442.8  488.53  4461.4  486.53  4466.8  487.32  4485.4  484.56  4490.8  485.69
  4496.6  483.91  4514.8  482.27  4674.9  478.43  4722.9  476.06  4728.3  476.84
  4805.7  474.70  4965.9  472.73  4972.1  468.36  4978.7  467.77  4979.9  467.27
  4987.2  467.77  4995.3  469.77  5001.9  472.90  5022.5  473.83  5068.6  473.34
  5104.4  474.40  5210.9  474.70  5386.2  479.47  5562.4  482.09  6123.6  484.41
#Mann=3,-1,0
  3740.3    0.05       0  4978.7    0.03       0  4987.2    0.05       0
Bank Sta=4978.7,4987.2
Exp/Cntr=0.3,0.1

Type RM Length L Ch R = 1,35449,467,467,467
BEGIN DESCRIPTION:
Terry Creek 61.0
END DESCRIPTION:
XS GIS Cut Line= 3
      2632626.02      6965160.98      2632176.00      6965611.00
      2631375.96      6966161.03
#Sta/Elev= 30
  4363.1  487.04  4377.3  486.74  4419.7  480.39  4448.0  479.32  4787.4  473.64
  4886.4  472.62  4943.0  473.61  4985.4  471.15  4991.7  468.21  4993.0  467.71
  5000.2  468.21  5035.9  473.56  5171.4  473.00  5193.7  470.69  5222.1  473.68
  5416.3  476.21  5431.2  479.33  5467.0  481.43  5481.9  479.19  5488.0  480.12
  5496.8  477.57  5502.9  479.27  5509.2  477.47  5532.7  477.44  5538.7  480.31
  5553.6  479.83  5559.7  481.52  5574.6  482.50  5618.4  478.33  5970.4  483.30
#Mann=3,-1,0
  4363.1    0.05       0  4991.7    0.03       0  5000.2    0.05       0
Bank Sta=4991.7,5000.2
Exp/Cntr=0.3,0.1

Type RM Length L Ch R = 1,34982,456,456,456
BEGIN DESCRIPTION:
Terry Creek 60.0
END DESCRIPTION:
XS GIS Cut Line= 3
      2632576.03      6964710.98      2631876.00      6965311.00
      2631076.01      6966510.99
#Sta/Elev= 30
  4078.2  494.44  4206.1  490.85  4382.8  481.94  4454.2  480.41  4532.1  477.21
  4737.3  473.04  4837.2  472.18  4886.6  473.01  4986.5  472.49  5003.2  470.91
  5008.7  466.93  5010.1  466.43  5018.8  466.93  5036.2  471.16  5049.8  471.65
  5064.8  472.15  5079.8  471.18  5121.9  473.71  5180.5  473.86  5281.1  477.04
  5368.3  477.84  5404.3  479.84  5497.5  480.63  5512.5  479.74  5533.5  480.56
  5937.6  482.78  6002.2  484.51  6059.3  483.37  6140.4  483.80  6442.4  487.71
#Mann=3,-1,0
  4078.2    0.05       0  5008.7    0.03       0  5018.8    0.05       0
Bank Sta=5008.7,5018.8
Exp/Cntr=0.3,0.1

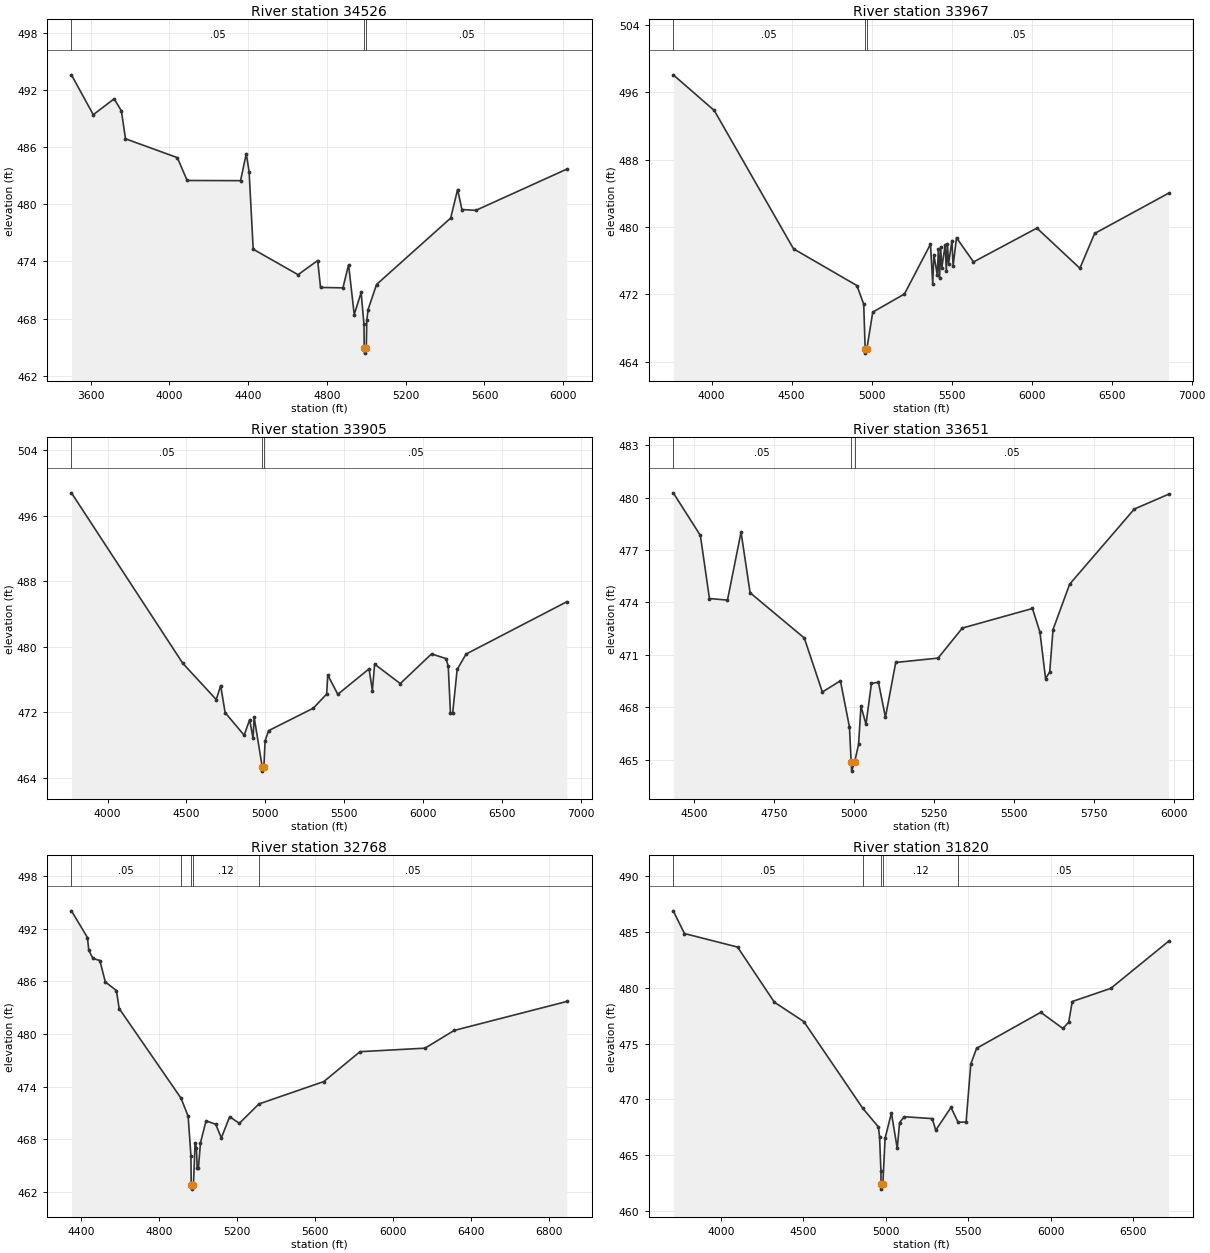
Type RM Length L Ch R = 1,34526,559,559,559
BEGIN DESCRIPTION:
Terry Creek 59.0
END DESCRIPTION:
XS GIS Cut Line= 3
      2632550.50      6963800.23      2631722.75      6964858.97
      2630976.02      6965760.97
#Sta/Elev= 30
  3502.9  493.61  3613.8  489.42  3719.7  491.09  3756.6  489.82  3777.4  486.89
  4040.6  484.91  4090.4  482.51  4361.6  482.49  4390.6  485.32  4405.0  483.44
  4425.8  475.29  4653.7  472.61  4753.2  474.10  4767.7  471.27  4881.4  471.23
  4910.1  473.66  4938.7  468.42  4973.9  470.74  4988.2  467.40  4989.6  464.87
  4991.0  464.37  4999.9  464.87  5002.6  467.80  5009.0  468.94  5052.0  471.58
  5428.5  478.56  5463.6  481.56  5485.6  479.46  5556.1  479.37  6017.8  483.70
#Mann=3,-1,0
  3502.9    0.05       0  4989.6    0.04       0  4999.9    0.05       0
Bank Sta=4989.6,4999.9
Exp/Cntr=0.3,0.1

Type RM Length L Ch R = 1,33967,62,62,62
BEGIN DESCRIPTION:
Mapping XS bfc05538
END DESCRIPTION:
XS GIS Cut Line= 4
      2632189.41      6963772.43      2631283.52      6964618.28
      2630765.80      6965126.59      2629935.95      6965893.94
#Sta/Elev= 30
  3760.6  498.06  4016.7  493.83  4512.0  477.41  4908.2  473.05  4950.7  470.84
  4959.7  465.53  4961.1  465.03  4970.1  465.53  5007.3  469.90  5205.3  472.05
  5367.9  477.96  5382.0  473.24  5389.0  476.70  5410.3  474.34  5417.3  477.36
  5424.5  473.90  5431.5  477.61  5438.6  475.16  5459.7  477.89  5466.9  474.79
  5473.9  477.96  5481.0  475.66  5502.2  478.39  5509.3  475.37  5530.5  478.73
  5636.6  475.85  6032.9  479.87  6301.6  475.10  6393.5  479.23  6855.8  484.01
#Mann=3,-1,0
  3760.6    0.05       0  4959.7    0.03       0  4970.1    0.05       0
Bank Sta=4959.7,4970.1
Exp/Cntr=0.3,0.1

Type RM Length L Ch R = 1,33905,254,254,254
BEGIN DESCRIPTION:
Mapping XS 54bc64e6
END DESCRIPTION:
XS GIS Cut Line= 4
      2632137.35      6963734.21      2631239.66      6964574.20
      2630654.69      6965116.17      2629845.67      6965883.52
#Sta/Elev= 30
  3770.6  498.78  4476.7  477.99  4689.2  473.56  4717.4  475.26  4745.4  471.97
  4866.1  469.21  4901.2  471.11  4922.7  468.83  4929.6  471.41  4981.0  465.33
  4982.5  464.83  4991.4  465.33  4999.1  468.54  5021.4  469.77  5304.9  472.51
  5389.4  474.23  5396.7  476.56  5460.2  474.20  5658.6  477.31  5679.6  474.66
  5693.8  477.88  5856.5  475.51  6054.7  479.13  6146.5  478.56  6160.7  477.65
  6174.8  471.92  6189.0  471.93  6217.3  477.23  6273.9  479.11  6912.5  485.49
#Mann=3,-1,0
  3770.6    0.05       0  4981.0    0.03       0  4991.4    0.05       0
Bank Sta=4981,4991.4
Exp/Cntr=0.3,0.1

Type RM Length L Ch R = 1,33651,883,883,883
BEGIN DESCRIPTION:
Terry Creek 57.0
END DESCRIPTION:
XS GIS Cut Line= 3
      2631526.03      6963960.97      2631126.00      6964361.00
      2630226.01      6964761.00
#Sta/Elev= 30
  4433.9  480.27  4518.8  477.83  4547.1  474.22  4603.6  474.13  4646.1  478.02
  4674.4  474.55  4844.1  471.96  4900.6  468.87  4957.2  469.51  4985.5  466.86
  4990.8  464.84  4992.3  464.34  5001.3  464.84  5014.0  465.87  5021.5  468.06
  5037.2  467.02  5054.3  469.36  5076.2  469.43  5098.1  467.42  5130.3  470.56
  5262.9  470.81  5338.9  472.53  5558.4  473.65  5581.7  472.30  5599.4  469.64
  5612.4  470.02  5622.7  472.44  5674.7  475.04  5877.1  479.34  5984.5  480.19
#Mann=3,-1,0
  4433.9    0.05       0  4990.8    0.03       0  5001.3    0.05       0
Bank Sta=4990.8,5001.3
Exp/Cntr=0.3,0.1

Type RM Length L Ch R = 1,32768,948,948,948
BEGIN DESCRIPTION:
Terry Creek 55.0
END DESCRIPTION:
XS GIS Cut Line= 3
      2631199.85      6963268.94      2630726.00      6963711.00
      2629515.81      6965164.77
#Sta/Elev= 30
  4352.2  494.05  4434.3  491.01  4441.1  489.55  4462.6  488.62  4497.8  488.39
  4526.1  485.94  4582.8  484.97  4596.9  482.92  4914.2  472.70  4950.6  470.64
  4964.8  466.17  4966.5  462.84  4968.0  462.34  4977.7  462.84  4986.3  467.64
  4993.2  467.01  4996.8  464.80  5003.5  464.80  5013.9  467.63  5042.5  470.12
  5092.0  469.73  5120.7  468.17  5163.6  470.59  5213.1  469.84  5313.3  472.04
  5646.6  474.60  5831.5  478.00  6164.7  478.40  6314.4  480.42  6891.8  483.72
#Mann=5,-1,0
  4352.2    0.05       0  4914.2    0.12       0  4966.5    0.07       0
  4977.7    0.12       0  5313.3    0.05       0
Bank Sta=4966.5,4977.7
Exp/Cntr=0.3,0.1

Type RM Length L Ch R = 1,31820,457,457,457
BEGIN DESCRIPTION:
Terry Creek 53.0
END DESCRIPTION:
XS GIS Cut Line= 3
      2631081.82      6962473.78      2630026.00      6963211.00
      2628852.62      6964463.38
#Sta/Elev= 30
  3711.8  486.91  3779.7  484.87  4101.5  483.66  4324.8  478.71  4503.6  476.97
  4860.4  469.20  4955.9  467.51  4962.9  466.62  4971.2  463.54  4971.6  462.43
  4973.2  461.93  4982.9  462.43  4996.5  466.50  5034.9  468.77  5070.1  465.58
  5084.3  467.91  5112.6  468.43  5282.6  468.26  5303.6  467.22  5395.9  469.26
  5439.3  467.93  5487.7  467.96  5516.1  473.16  5551.3  474.57  5940.6  477.80
  6074.9  476.35  6110.1  476.92  6131.5  478.77  6365.0  479.95  6715.7  484.18
#Mann=5,-1,0
  3711.8    0.05       0  4860.4    0.12       0  4971.6    0.07       0
  4982.9    0.12       0  5439.3    0.05       0
Bank Sta=4971.6,4982.9
Exp/Cntr=0.3,0.1