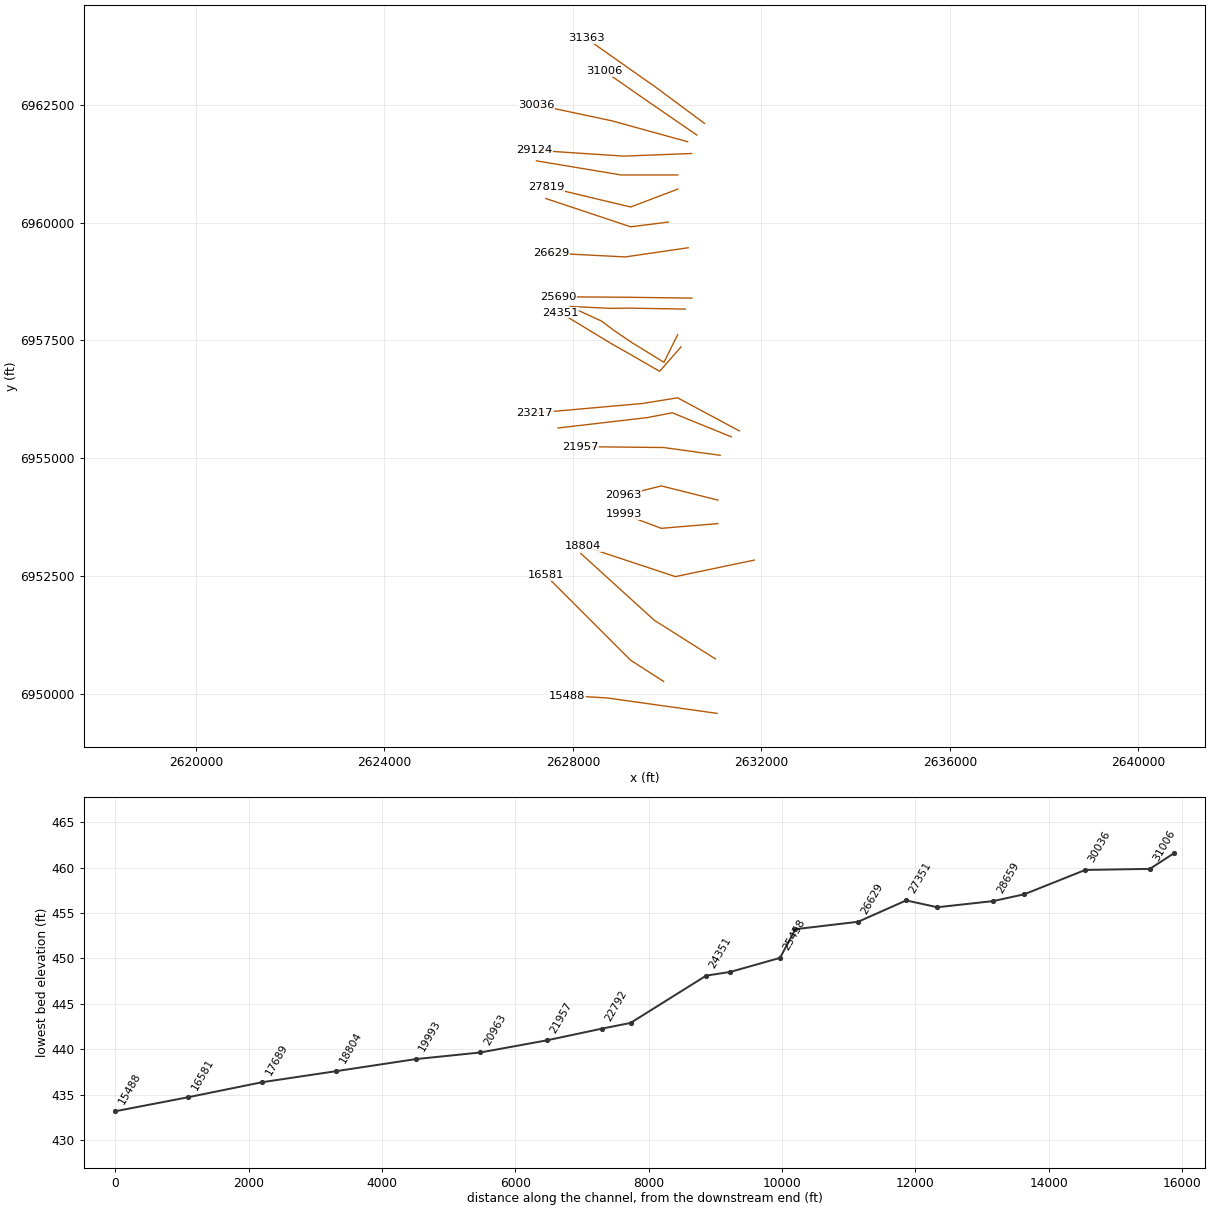
HEC-RAS study Terry Creek.prj: Terry Creek Base Level Engineering

--- Terry Creek.g01 (geometry) --- (continued)

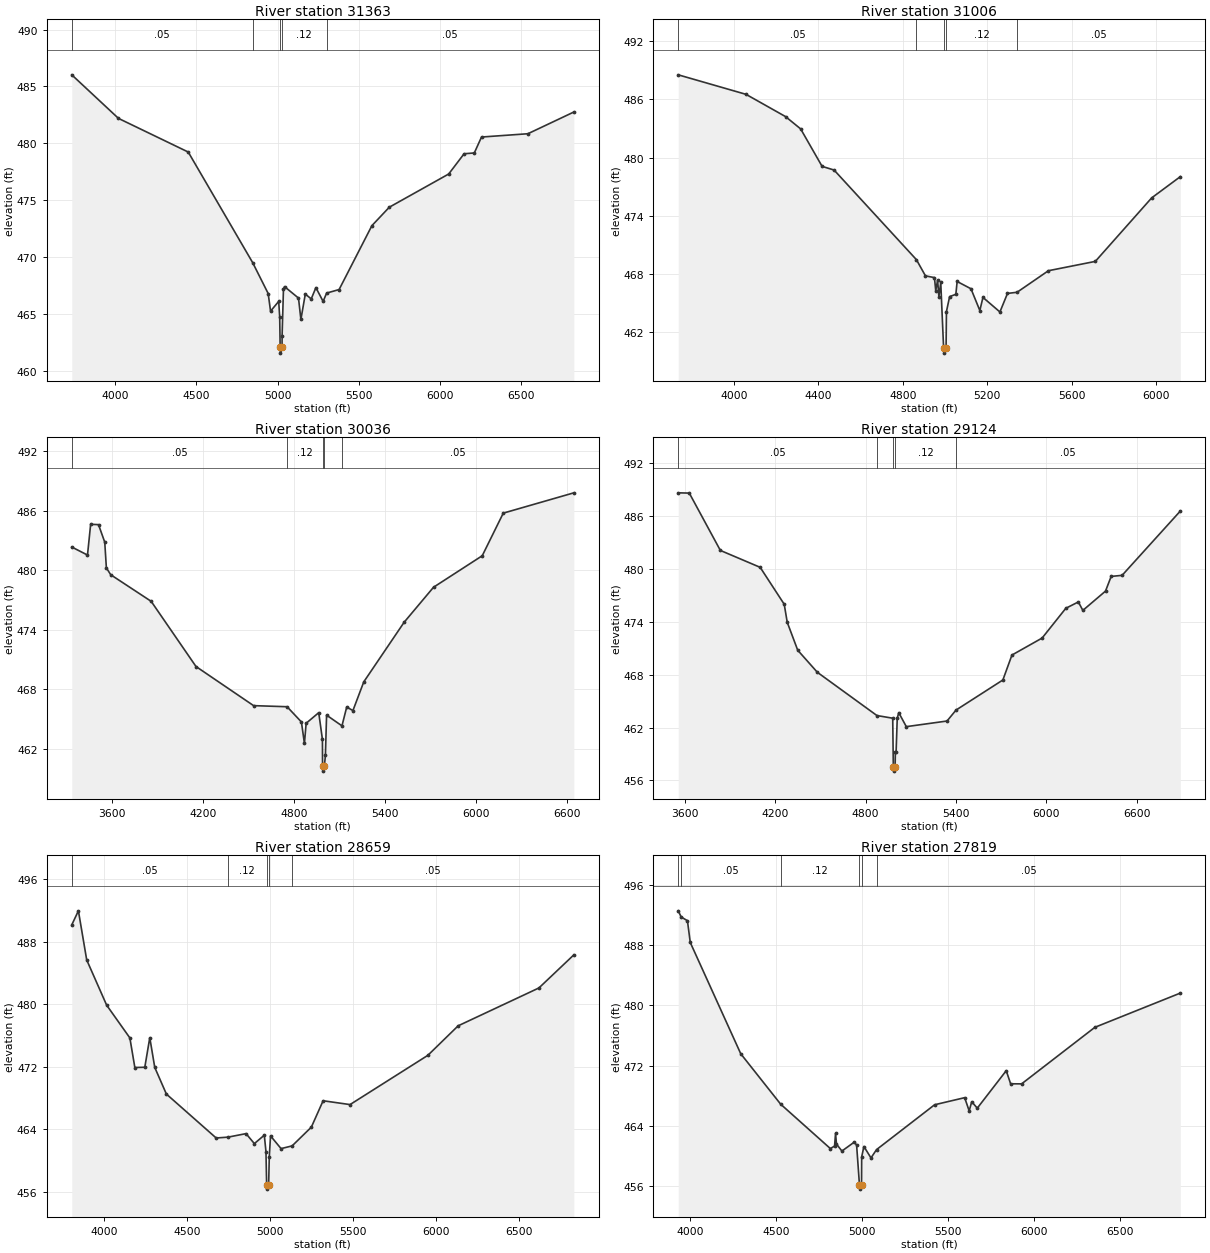
Type RM Length L Ch R = 1,31363,357,357,357
BEGIN DESCRIPTION:
Terry Creek 52.0
END DESCRIPTION:
XS GIS Cut Line= 3
      2630793.54      6962105.78      2629776.00      6962861.00
      2628283.15      6963911.32
#Sta/Elev= 30
  3732.8  486.02  4020.4  482.19  4450.2  479.23  4846.9  469.51  4942.6  466.79
  4957.2  465.24  5007.4  466.10  5013.5  464.71  5016.4  462.05  5018.0  461.55
  5028.0  462.05  5028.3  463.07  5036.7  467.17  5043.1  467.40  5129.3  466.39
  5144.1  464.51  5171.2  466.74  5207.8  466.32  5236.5  467.31  5280.9  466.10
  5302.7  466.83  5379.4  467.14  5581.5  472.76  5688.6  474.38  6054.5  477.30
  6149.3  479.08  6212.2  479.15  6256.6  480.55  6542.3  480.84  6825.3  482.75
#Mann=5,-1,0
  3732.8    0.05       0  4846.9    0.12       0  5016.4    0.07       0
  5028.0    0.12       0  5302.7    0.05       0
Bank Sta=5016.4,5028
Exp/Cntr=0.3,0.1

Type RM Length L Ch R = 1,31006,970,970,970
BEGIN DESCRIPTION:
Terry Creek 51.0
END DESCRIPTION:
XS GIS Cut Line= 3
      2630630.41      6961859.21      2629589.67      6962574.23
      2628675.98      6963211.02
#Sta/Elev= 30
  3737.3  488.52  4058.1  486.51  4245.0  484.22  4316.7  482.95  4418.2  479.09
  4475.0  478.71  4864.6  469.48  4907.4  467.81  4950.0  467.63  4956.1  466.29
  4964.9  467.38  4971.0  465.66  4979.8  467.13  4993.4  460.35  4995.0  459.85
  5005.0  460.35  5006.8  464.13  5021.7  465.67  5051.3  465.91  5057.4  467.23
  5122.9  466.48  5164.8  464.24  5179.6  465.59  5259.9  464.09  5295.7  466.00
  5341.1  466.12  5489.4  468.34  5711.4  469.30  5978.0  475.84  6113.7  478.03
#Mann=5,-1,0
  3737.3    0.05       0  4864.6    0.12       0  4993.4    0.07       0
  5005.0    0.12       0  5341.1    0.05       0
Bank Sta=4993.4,5005
Exp/Cntr=0.3,0.1

Type RM Length L Ch R = 1,30036,912,912,912
BEGIN DESCRIPTION:
Terry Creek 49.0
END DESCRIPTION:
XS GIS Cut Line= 3
      2630435.99      6961716.85      2628826.00      6962161.00
      2627220.86      6962501.55
#Sta/Elev= 30
  3333.7  482.35  3437.4  481.54  3458.2  484.64  3510.0  484.61  3551.2  482.84
  3561.9  480.24  3590.8  479.55  3857.2  476.87  4152.9  470.29  4532.8  466.34
  4753.6  466.23  4848.2  464.69  4868.0  462.52  4879.3  464.56  4962.3  465.63
  4986.7  462.93  4987.6  460.23  4989.2  459.73  4999.4  460.23  5006.4  461.33
  5014.1  465.38  5115.5  464.30  5146.9  466.20  5187.8  465.84  5259.4  468.74
  5525.2  474.75  5719.4  478.29  6040.6  481.47  6179.3  485.77  6644.7  487.82
#Mann=5,-1,0
  3333.7    0.05       0  4753.6    0.12       0  4987.6    0.07       0
  4999.4    0.12       0  5115.5    0.05       0
Bank Sta=4987.6,4999.4
Exp/Cntr=0.3,0.1

Type RM Length L Ch R = 1,29124,465,465,465
BEGIN DESCRIPTION:
Terry Creek 48.0
END DESCRIPTION:
XS GIS Cut Line= 3
      2630519.32      6961466.87      2629076.00      6961411.00
      2627190.26      6961536.25
#Sta/Elev= 30
  3555.2  488.66  3628.6  488.63  3834.9  482.12  4099.3  480.20  4259.0  476.01
  4279.1  473.96  4348.7  470.79  4479.2  468.28  4874.8  463.37  4979.6  463.07
  4983.6  457.56  4985.3  457.06  4995.5  457.56  4997.1  459.25  5002.1  459.25
  5009.6  463.05  5019.6  463.70  5069.8  462.11  5340.4  462.75  5399.8  463.99
  5711.2  467.41  5771.3  470.24  5971.7  472.17  6129.2  475.55  6212.3  476.27
  6242.3  475.31  6392.7  477.50  6430.4  479.17  6502.9  479.29  6889.5  486.59
#Mann=5,-1,0
  3555.2    0.05       0  4874.8    0.12       0  4983.6    0.07       0
  4995.5    0.12       0  5399.8    0.05       0
Bank Sta=4983.6,4995.5
Exp/Cntr=0.3,0.1

Type RM Length L Ch R = 1,28659,840,840,840
BEGIN DESCRIPTION:
Terry Creek 47.0
END DESCRIPTION:
XS GIS Cut Line= 3
      2630226.04      6961011.00      2629026.00      6961011.00
      2627225.97      6961311.00
#Sta/Elev= 30
  3804.2  490.16  3844.2  491.96  3894.2  485.67  4014.2  479.88  4154.2  475.68
  4184.2  471.89  4244.2  471.92  4274.2  475.71  4304.2  471.90  4374.2  468.49
  4674.2  462.86  4745.5  462.97  4854.2  463.42  4904.2  462.14  4964.2  463.22
  4974.2  461.11  4978.3  456.81  4979.9  456.31  4990.2  456.81  4994.2  460.46
  5001.7  463.13  5065.1  461.50  5131.8  461.85  5247.6  464.25  5318.5  467.63
  5480.7  467.14  5949.6  473.45  6132.1  477.23  6618.7  482.08  6829.1  486.32
#Mann=5,-1,0
  3804.2    0.05       0  4745.5    0.12       0  4978.3    0.07       0
  4990.2    0.12       0  5131.8    0.05       0
Bank Sta=4978.3,4990.2
Exp/Cntr=0.3,0.1

Type RM Length L Ch R = 1,27819,468,468,468
BEGIN DESCRIPTION:
Terry Creek 45.0
END DESCRIPTION:
XS GIS Cut Line= 3
      2630226.01      6960711.00      2629226.29      6960331.30
      2627425.97      6960761.01
#Sta/Elev= 30
  3930.6  492.54  3947.9  491.72  3984.1  491.23  4000.6  488.34  4294.3  473.58
  4526.6  466.89  4815.4  461.01  4839.9  461.34  4845.6  463.02  4850.9  461.61
  4882.6  460.68  4955.4  461.88  4968.2  461.45  4984.9  456.13  4986.6  455.63
  4996.8  456.13  4997.5  459.90  5010.6  461.28  5051.7  459.77  5084.0  460.87
  5421.8  466.82  5596.6  467.76  5622.8  466.01  5637.7  467.22  5670.0  466.37
  5838.4  471.34  5863.9  469.60  5927.8  469.59  6353.9  477.09  6850.9  481.63
#Mann=6,-1,0
  3930.6   0.075       0  3947.9    0.05       0  4526.6    0.12       0
  4984.9    0.07       0  4996.8    0.12       0  5084.0    0.05       0
Bank Sta=4984.9,4996.8
Exp/Cntr=0.3,0.1

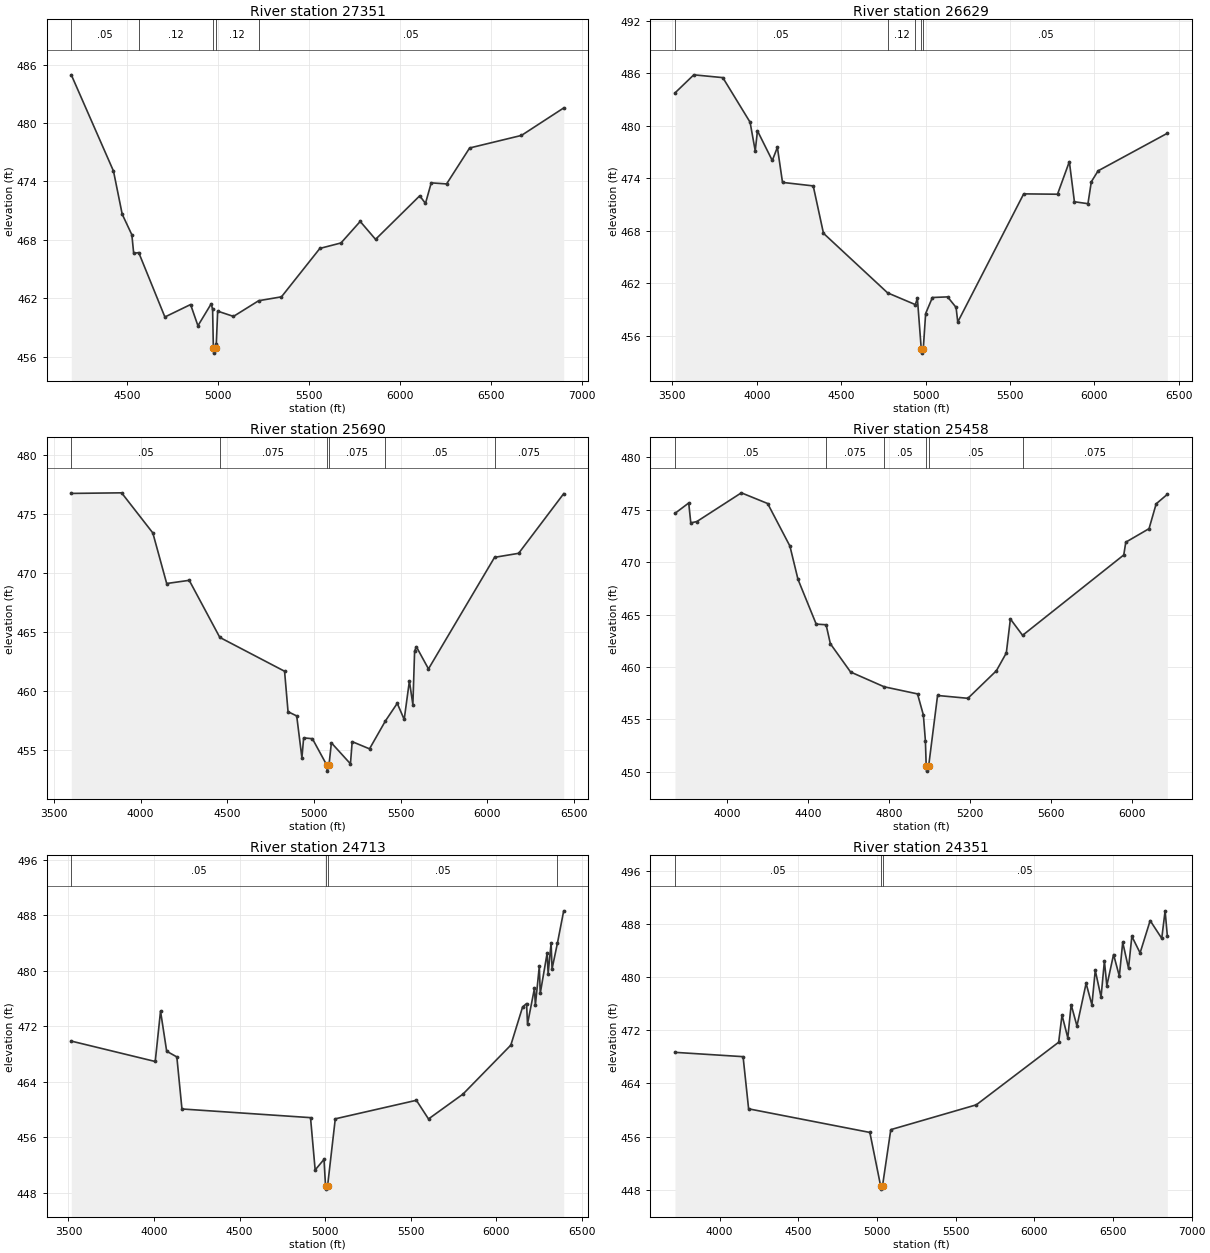
Type RM Length L Ch R = 1,27351,722,722,722
BEGIN DESCRIPTION:
Terry Creek 44.0
END DESCRIPTION:
XS GIS Cut Line= 3
      2630025.95      6960010.99      2629226.00      6959911.00
      2627426.04      6960510.99
#Sta/Elev= 30
  4193.9  484.95  4425.6  475.07  4473.5  470.64  4526.4  468.53  4536.5  466.63
  4564.2  466.70  4707.8  460.09  4848.9  461.37  4889.2  459.19  4962.3  461.45
  4969.8  460.87  4974.0  456.88  4975.6  456.38  4985.9  456.88  4990.0  457.30
  4997.6  460.69  5084.4  460.15  5222.6  461.76  5347.9  462.16  5558.7  467.13
  5674.7  467.69  5780.1  469.90  5864.4  468.06  6106.9  472.53  6138.5  471.75
  6170.1  473.86  6254.4  473.75  6380.9  477.44  6665.5  478.73  6897.4  481.55
#Mann=5,-1,0
  4193.9    0.05       0  4564.2    0.12       0  4974.0    0.07       0
  4985.9    0.12       0  5222.6    0.05       0
Bank Sta=4974,4985.9
Exp/Cntr=0.3,0.1

Type RM Length L Ch R = 1,26629,939,939,939
BEGIN DESCRIPTION:
Mapping XS 32d76205
END DESCRIPTION:
XS GIS Cut Line= 3
      2630446.39      6959466.18      2629112.21      6959271.74
      2627546.22      6959351.60
#Sta/Elev= 30
  3515.3  483.73  3626.9  485.80  3798.8  485.48  3960.3  480.39  3990.7  477.12
  4003.9  479.41  4091.7  476.02  4122.0  477.52  4152.3  473.52  4334.2  473.12
  4394.9  467.71  4774.7  460.91  4938.8  459.57  4951.1  460.29  4973.9  454.53
  4975.6  454.03  4986.0  454.53  5000.0  458.55  5040.0  460.38  5130.1  460.45
  5180.2  459.25  5190.2  457.58  5580.7  472.21  5781.0  472.17  5851.1  475.89
  5881.1  471.31  5961.2  471.09  5981.2  473.59  6021.3  474.84  6431.6  479.13
#Mann=5,-1,0
  3515.3    0.05       0  4774.7    0.12       0  4938.8    0.05       0
  4973.9    0.03       0  4986.0    0.05       0
Bank Sta=4973.9,4986
Exp/Cntr=0.3,0.1

Type RM Length L Ch R = 1,25690,232,232,232
BEGIN DESCRIPTION:
Mapping XS 29f7da70
END DESCRIPTION:
XS GIS Cut Line= 3
      2630526.21      6958397.42      2629126.44      6958416.18
      2627685.97      6958425.20
#Sta/Elev= 30
  3600.1  476.77  3890.3  476.82  4070.4  473.42  4150.4  469.13  4280.4  469.40
  4456.8  464.56  4830.4  461.69  4850.4  458.26  4900.4  457.90  4930.4  454.35
  4940.4  456.04  4990.9  455.97  5074.3  453.72  5076.0  453.22  5086.5  453.72
  5100.4  455.62  5210.4  453.84  5220.4  455.72  5320.4  455.11  5412.2  457.48
  5480.4  458.97  5520.4  457.60  5550.4  460.86  5570.5  458.85  5580.5  463.40
  5590.5  463.77  5660.5  461.89  6041.7  471.35  6180.5  471.69  6440.5  476.75
#Mann=6,-1,0
  3600.1    0.05       0  4456.8   0.075       0  5074.3    0.07       0
  5086.5   0.075       0  5412.2    0.05       0  6041.7   0.075       0
Bank Sta=5074.3,5086.5
Exp/Cntr=0.3,0.1

Type RM Length L Ch R = 1,25458,745,745,745
BEGIN DESCRIPTION:
Mapping XS 4ccd49e3
END DESCRIPTION:
XS GIS Cut Line= 4
      2630384.28      6958164.78      2629189.19      6958184.79
      2628799.16      6958179.87      2627950.64      6958220.32
#Sta/Elev= 30
  3741.5  474.66  3809.6  475.65  3819.8  473.75  3849.8  473.88  4069.8  476.62
  4199.8  475.60  4309.9  471.54  4349.9  468.36  4439.9  464.09  4488.9  464.03
  4509.9  462.22  4609.9  459.52  4775.9  458.11  4940.9  457.43  4969.9  455.41
  4979.9  452.94  4983.8  450.56  4985.5  450.06  4996.0  450.56  5040.0  457.28
  5190.0  457.01  5330.9  459.64  5380.0  461.34  5400.1  464.58  5460.4  463.02
  5960.7  470.69  5970.7  471.91  6085.7  473.20  6120.9  475.57  6176.3  476.48
#Mann=6,-1,0
  3741.5    0.05       0  4488.9   0.075       0  4775.9    0.05       0
  4983.8    0.03       0  4996.0    0.05       0  5460.4   0.075       0
Bank Sta=4983.8,4996
Exp/Cntr=0.3,0.1

Type RM Length L Ch R = 1,24713,362,362,362
BEGIN DESCRIPTION:
Mapping XS 23197842
END DESCRIPTION:
XS GIS Cut Line= 6
      2630223.34      6957620.98      2629933.98      6957035.05
      2629252.55      6957453.45      2628890.57      6957698.24
      2628601.51      6957913.52      2628030.56      6958175.00
#Sta/Elev= 30
  3516.6  469.85  4007.3  466.91  4038.3  474.17  4074.2  468.39  4133.6  467.57
  4163.5  460.07  4915.1  458.82  4942.2  451.28  4993.9  452.81  5002.8  449.02
  5004.5  448.52  5015.0  449.02  5059.8  458.65  5533.9  461.32  5604.8  458.63
  5806.2  462.21  6086.0  469.27  6155.0  474.78  6178.0  475.26  6183.5  472.31
  6224.0  477.43  6229.5  475.04  6252.5  480.63  6258.0  476.71  6298.5  482.56
  6304.0  479.57  6321.5  483.98  6327.0  480.25  6358.7  484.00  6395.1  488.62
#Mann=4,-1,0
  3516.6    0.05       0  5002.8    0.05       0  5015.0    0.05       0
  6358.7   0.075       0
Bank Sta=5002.8,5015
Exp/Cntr=0.3,0.1

Type RM Length L Ch R = 1,24351,1134,1134,1134
BEGIN DESCRIPTION:
Mapping XS a85e19c0
END DESCRIPTION:
XS GIS Cut Line= 6
      2630295.93      6957362.28      2629840.23      6956844.07
      2629325.95      6957140.96      2629260.37      6957180.01
      2628828.94      6957423.07      2627739.76      6958084.13
#Sta/Elev= 30
  3716.1  468.67  4149.1  468.02  4184.2  460.18  4954.8  456.63  5023.1  448.61
  5024.8  448.11  5035.3  448.61  5087.8  457.05  5631.3  460.78  6154.7  470.19
  6176.0  474.27  6212.8  470.85  6234.2  475.83  6271.0  472.63  6329.1  479.04
  6366.0  475.80  6387.3  480.99  6424.1  476.96  6445.4  482.40  6460.9  478.69
  6503.6  483.37  6540.4  480.12  6561.8  485.21  6598.6  481.31  6619.9  486.11
  6672.2  483.61  6736.2  488.47  6809.9  485.80  6831.2  489.94  6845.6  486.11
#Mann=3,-1,0
  3716.1    0.05       0  5023.1    0.05       0  5035.3    0.05       0
Bank Sta=5023.1,5035.3
Exp/Cntr=0.3,0.1

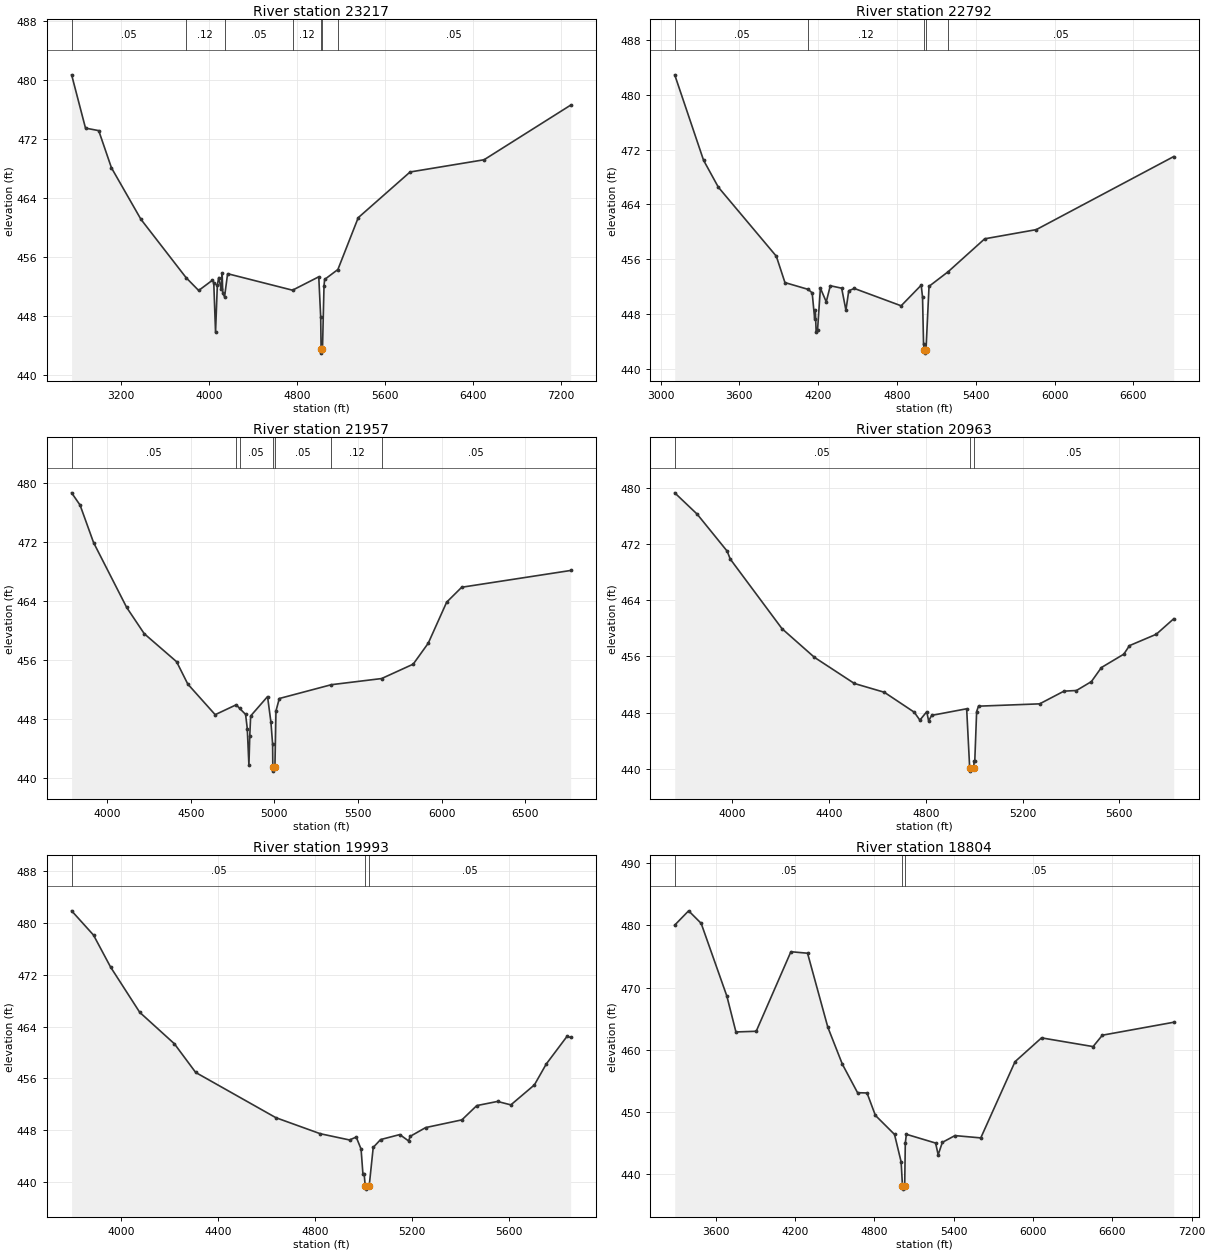
Type RM Length L Ch R = 1,23217,425,425,425
BEGIN DESCRIPTION:
Terry Creek 35.0
END DESCRIPTION:
XS GIS Cut Line= 4
      2631535.30      6955577.99      2630222.84      6956281.10
      2629476.00      6956161.00      2627191.55      6955958.18
#Sta/Elev= 30
  2751.0  480.72  2877.3  473.48  2997.5  473.14  3113.2  468.09  3381.0  461.10
  3792.3  453.16  3906.6  451.42  4032.1  452.82  4043.9  452.48  4060.1  445.73
  4076.4  452.16  4088.9  453.18  4111.6  451.56  4120.2  453.77  4125.9  451.04
  4142.0  450.56  4169.8  453.70  4760.1  451.46  4998.9  453.28  5016.4  447.84
  5020.3  443.41  5022.0  442.91  5032.7  443.41  5046.6  452.04  5052.2  452.92
  5172.9  454.27  5357.8  461.31  5829.6  467.52  6502.3  469.18  7289.8  476.60
#Mann=7,-1,0
  2751.0    0.05       0  3792.3    0.12       0  4142.0    0.05       0
  4760.1    0.12       0  5020.3    0.07       0  5032.7    0.12       0
  5172.9    0.05       0
Bank Sta=5020.3,5032.7
Exp/Cntr=0.3,0.1

Type RM Length L Ch R = 1,22792,835,835,835
BEGIN DESCRIPTION:
Terry Creek 34.0
END DESCRIPTION:
XS GIS Cut Line= 4
      2631363.47      6955452.97      2630108.25      6955963.39
      2629576.00      6955861.00      2627686.37      6955640.47
#Sta/Elev= 30
  3107.6  482.92  3327.1  470.45  3439.6  466.52  3881.1  456.44  3946.9  452.59
  4123.0  451.60  4154.2  451.09  4172.9  447.34  4178.3  448.52  4184.4  445.39
  4195.2  445.72  4216.8  451.77  4261.3  449.78  4292.3  452.13  4378.7  451.77
  4411.1  448.56  4432.7  451.40  4475.1  451.73  4831.5  449.20  4984.3  452.21
  4994.5  450.45  5002.1  443.62  5008.5  442.79  5010.3  442.29  5020.9  442.79
  5043.8  452.04  5189.7  454.18  5467.8  458.98  5860.4  460.32  6907.1  470.99
#Mann=5,-1,0
  3107.6    0.05       0  4123.0    0.12       0  5008.5    0.07       0
  5020.9    0.12       0  5189.7    0.05       0
Bank Sta=5008.5,5020.9
Exp/Cntr=0.3,0.1

Type RM Length L Ch R = 1,21957,994,994,994
BEGIN DESCRIPTION:
Terry Creek 33.0
END DESCRIPTION:
XS GIS Cut Line= 3
      2631126.04      6955060.99      2629925.34      6955226.12
      2628155.14      6955244.64
#Sta/Elev= 30
  3788.0  478.66  3838.5  477.00  3919.3  471.92  4117.2  463.14  4222.1  459.59
  4415.4  455.80  4482.4  452.77  4646.0  448.63  4771.8  449.97  4792.6  449.47
  4827.7  448.67  4837.8  446.74  4847.6  441.78  4852.7  445.74  4858.0  448.46
  4959.0  451.08  4979.1  447.63  4989.2  444.63  4990.5  441.49  4992.2  440.99
  5003.0  441.49  5009.3  449.14  5029.3  450.82  5340.5  452.69  5640.5  453.52
  5829.4  455.47  5919.4  458.31  6029.4  463.86  6119.4  465.88  6770.3  468.15
#Mann=7,-1,0
  3788.0    0.05       0  4771.8    0.12       0  4792.6    0.05       0
  4990.5    0.03       0  5003.0    0.05       0  5340.5    0.12       0
  5640.5    0.05       0
Bank Sta=4990.5,5003
Exp/Cntr=0.3,0.1

Type RM Length L Ch R = 1,20963,970,970,970
BEGIN DESCRIPTION:
Terry Creek 31.0
END DESCRIPTION:
XS GIS Cut Line= 3
      2631076.04      6954110.99      2629876.00      6954411.00
      2629076.00      6954211.00
#Sta/Elev= 30
  3763.0  479.29  3855.8  476.25  3979.5  470.99  3992.4  469.86  4206.3  459.94
  4340.3  455.86  4505.2  452.14  4628.9  450.89  4752.6  448.05  4775.8  446.92
  4804.1  448.12  4811.9  446.82  4824.7  447.60  4969.1  448.54  4981.5  440.16
  4983.5  439.66  4997.8  440.16  5000.0  441.06  5002.6  441.06  5010.3  448.14
  5018.0  448.91  5270.6  449.24  5371.1  451.05  5422.6  451.14  5484.4  452.41
  5525.7  454.41  5618.4  456.32  5641.6  457.53  5752.4  459.15  5824.6  461.36
#Mann=3,-1,0
  3763.0    0.05       0  4981.5    0.03       0  4997.8    0.05       0
Bank Sta=4981.5,4997.8
Exp/Cntr=0.3,0.1

Type RM Length L Ch R = 1,19993,1189,1189,1189
BEGIN DESCRIPTION:
Terry Creek 29.0
END DESCRIPTION:
XS GIS Cut Line= 3
      2631076.02      6953611.00      2629876.00      6953511.00
      2629075.98      6953811.01
#Sta/Elev= 30
  3795.4  481.84  3885.7  478.10  3956.0  473.18  4076.4  466.19  4219.4  461.34
  4307.2  456.92  4638.3  449.94  4821.5  447.47  4941.9  446.51  4969.5  446.96
  4989.5  445.10  4997.1  441.29  5002.2  441.29  5006.5  439.43  5008.5  438.93
  5023.0  439.43  5039.6  445.36  5069.9  446.57  5149.1  447.34  5185.6  446.36
  5191.8  447.06  5255.9  448.42  5405.4  449.61  5466.8  451.81  5552.3  452.45
  5607.4  451.92  5704.5  455.00  5753.4  458.22  5838.8  462.47  5854.0  462.32
#Mann=3,-1,0
  3795.4    0.05       0  5006.5    0.03       0  5023.0    0.05       0
Bank Sta=5006.5,5023
Exp/Cntr=0.3,0.1

Type RM Length L Ch R = 1,18804,1115,1115,1115
BEGIN DESCRIPTION:
Terry Creek 27.0
END DESCRIPTION:
XS GIS Cut Line= 3
      2631848.98      6952836.52      2630176.42      6952486.01
      2628217.04      6953135.14
#Sta/Elev= 30
  3291.1  480.03  3396.3  482.32  3491.0  480.31  3685.6  468.60  3753.9  462.86
  3907.2  462.97  4169.5  475.75  4295.4  475.51  4448.7  463.62  4558.6  457.68
  4673.5  453.10  4745.0  453.06  4808.2  449.46  4952.9  446.40  5002.9  441.99
  5013.2  438.11  5015.2  437.61  5029.8  438.11  5034.5  445.01  5042.6  446.42
  5263.8  445.01  5282.9  443.12  5314.6  445.12  5409.7  446.21  5605.1  445.84
  5864.3  458.09  6064.4  461.91  6454.2  460.51  6524.5  462.34  7064.1  464.42
#Mann=3,-1,0
  3291.1    0.05       0  5013.2    0.03       0  5029.8    0.05       0
Bank Sta=5013.2,5029.8
Exp/Cntr=0.3,0.1

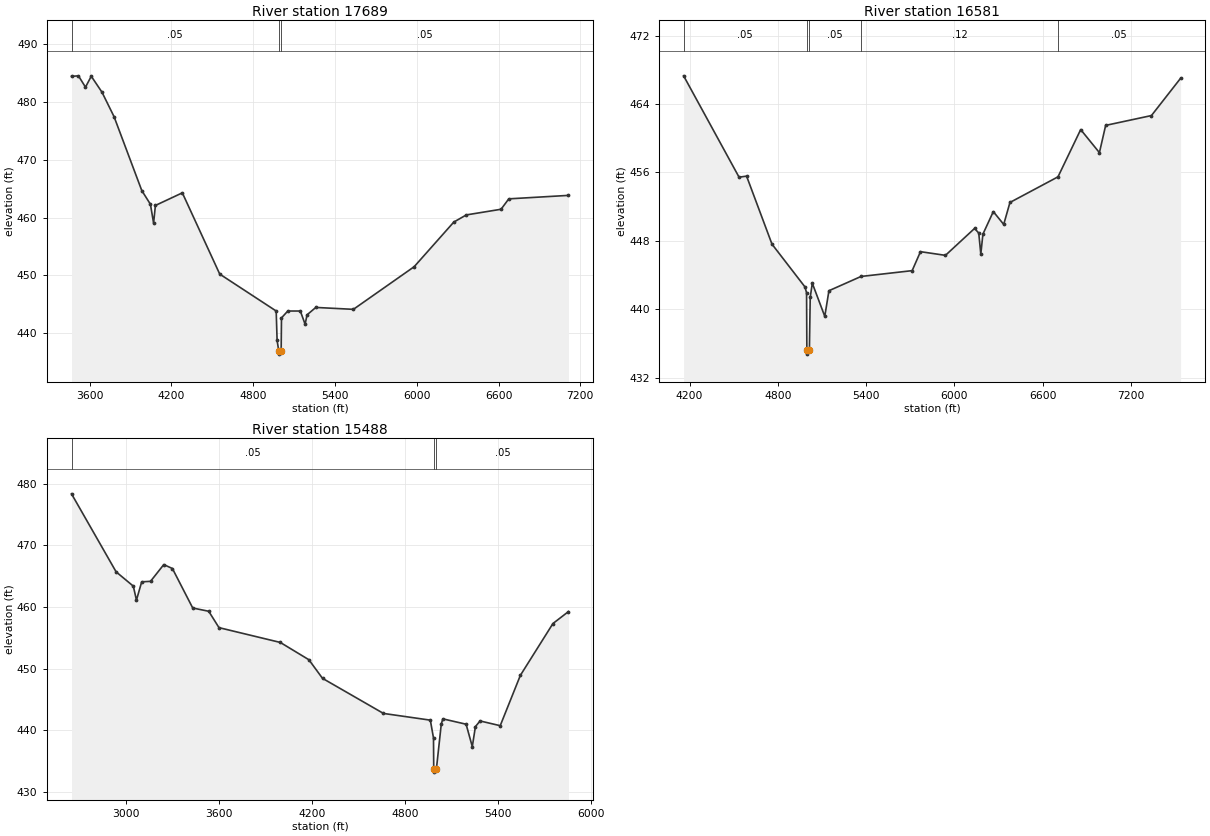
Type RM Length L Ch R = 1,17689,1108,1108,1108
BEGIN DESCRIPTION:
Terry Creek 25.0
END DESCRIPTION:
XS GIS Cut Line= 3
      2631024.88      6950739.46      2629726.00      6951561.00
      2628165.54      6952979.02
#Sta/Elev= 30
  3467.8  484.46  3518.6  484.55  3570.3  482.59  3612.7  484.48  3691.5  481.71
  3779.7  477.49  3983.2  464.70  4046.7  462.32  4069.9  459.06  4083.2  462.12
  4280.7  464.30  4555.1  450.24  4969.2  443.85  4975.9  438.75  4988.6  436.89
  4990.6  436.39  5005.6  436.89  5008.1  442.66  5054.4  443.85  5146.3  443.85
  5181.4  441.56  5195.6  443.19  5259.8  444.47  5535.5  444.14  5981.5  451.52
  6272.0  459.24  6363.9  460.48  6618.7  461.46  6675.5  463.26  7113.2  463.86
#Mann=3,-1,0
  3467.8    0.05       0  4988.6   0.035       0  5005.6    0.05       0
Bank Sta=4988.6,5005.6
Exp/Cntr=0.3,0.1

Type RM Length L Ch R = 1,16581,1093,1093,1093
BEGIN DESCRIPTION:
Terry Creek 23.0
END DESCRIPTION:
XS GIS Cut Line= 3
      2629926.00      6950261.00      2629226.00      6950711.00
      2627425.97      6952511.03
#Sta/Elev= 30
  4159.8  467.31  4536.6  455.45  4587.8  455.57  4760.5  447.61  4984.4  442.61
  4995.5  441.92  4997.5  435.24  4999.5  434.74  5014.7  435.24  5020.3  441.37
  5034.4  443.04  5119.3  439.16  5147.5  442.16  5365.8  443.83  5713.2  444.51
  5769.8  446.73  5939.5  446.30  6137.5  449.45  6165.8  448.91  6179.9  446.45
  6194.1  448.78  6264.8  451.42  6335.5  449.92  6377.9  452.49  6704.5  455.49
  6858.7  461.02  6986.0  458.32  7028.4  461.51  7339.6  462.66  7537.6  467.02
#Mann=5,-1,0
  4159.8    0.05       0  4997.5    0.03       0  5014.7    0.05       0
  5365.8    0.12       0  6704.5    0.05       0
Bank Sta=4997.5,5014.7
Exp/Cntr=0.3,0.1

Type RM Length L Ch R = 1,15488,1031,1031,1031
BEGIN DESCRIPTION:
Terry Creek 21.0
END DESCRIPTION:
XS GIS Cut Line= 3
      2631061.33      6949583.19      2628726.00      6949911.00
      2627876.00      6949961.00
#Sta/Elev= 30
  2645.8  478.39  2933.9  465.72  3045.0  463.40  3065.2  461.13  3099.1  464.10
  3156.1  464.18  3241.7  466.90  3297.5  466.26  3428.7  459.85  3532.0  459.32
  3598.3  456.66  3994.2  454.26  4178.9  451.45  4266.9  448.43  4660.7  442.73
  4963.3  441.64  4983.8  438.74  4985.3  433.70  4987.3  433.20  5002.5  433.70
  5034.1  441.02  5044.1  441.85  5194.4  440.98  5234.4  437.34  5254.5  440.59
  5284.5  441.51  5414.7  440.74  5545.0  448.92  5755.3  457.33  5855.5  459.27
#Mann=3,-1,0
  2645.8    0.05       0  4985.3   0.035       0  5002.5    0.05       0
Bank Sta=4985.3,5002.5
Exp/Cntr=0.3,0.1