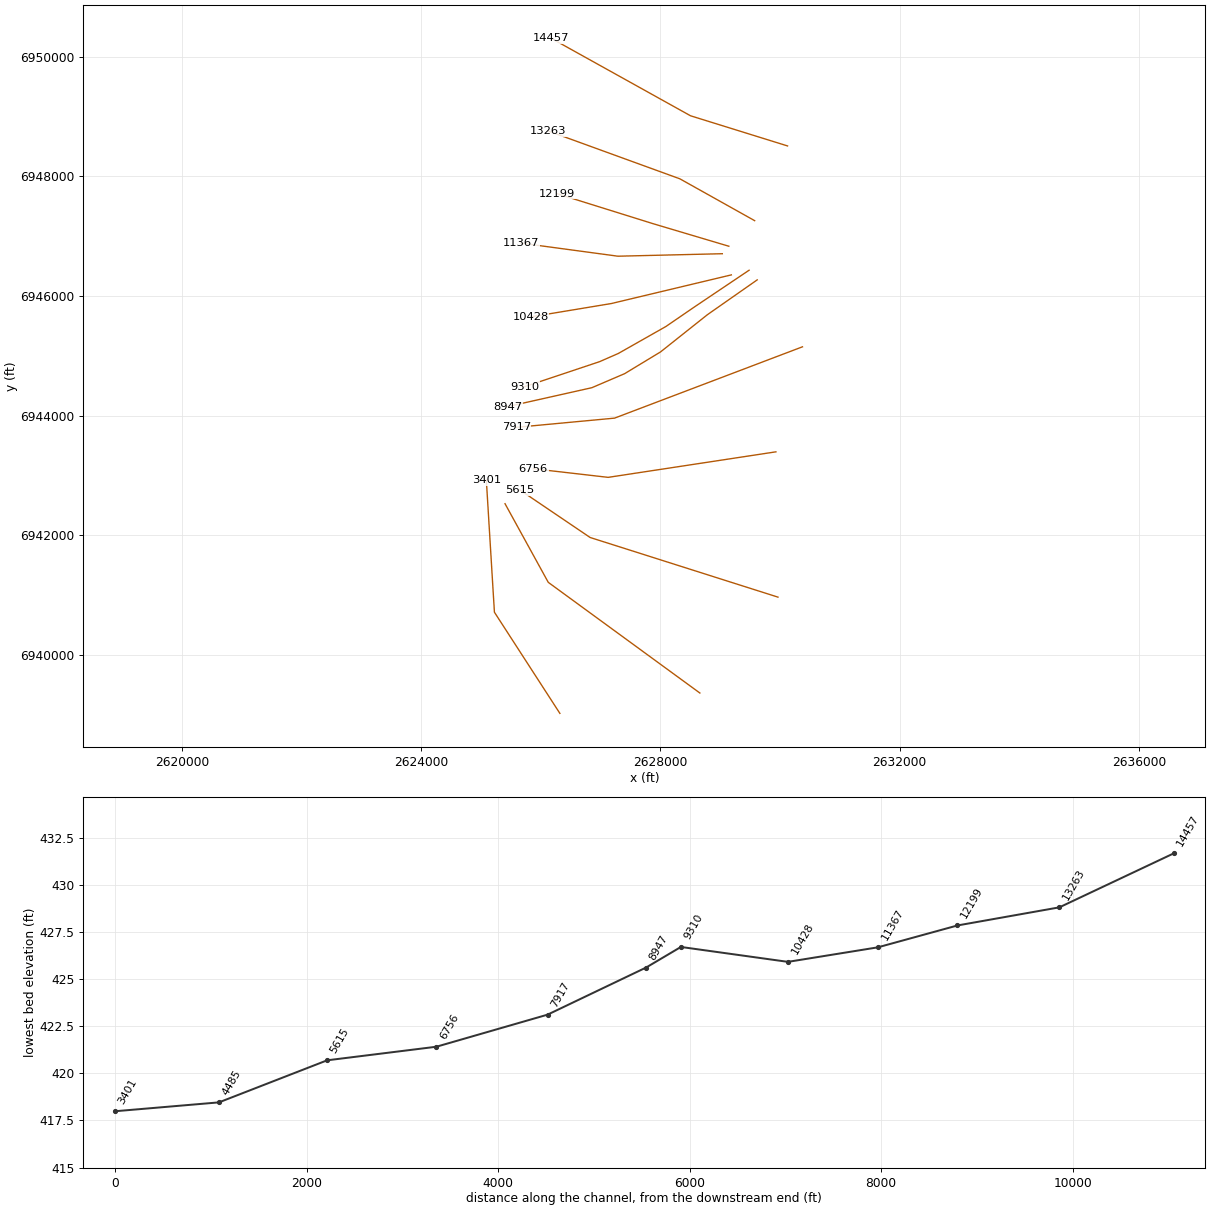
HEC-RAS study Terry Creek.prj: Terry Creek Base Level Engineering

--- Terry Creek.g01 (geometry) --- (continued)

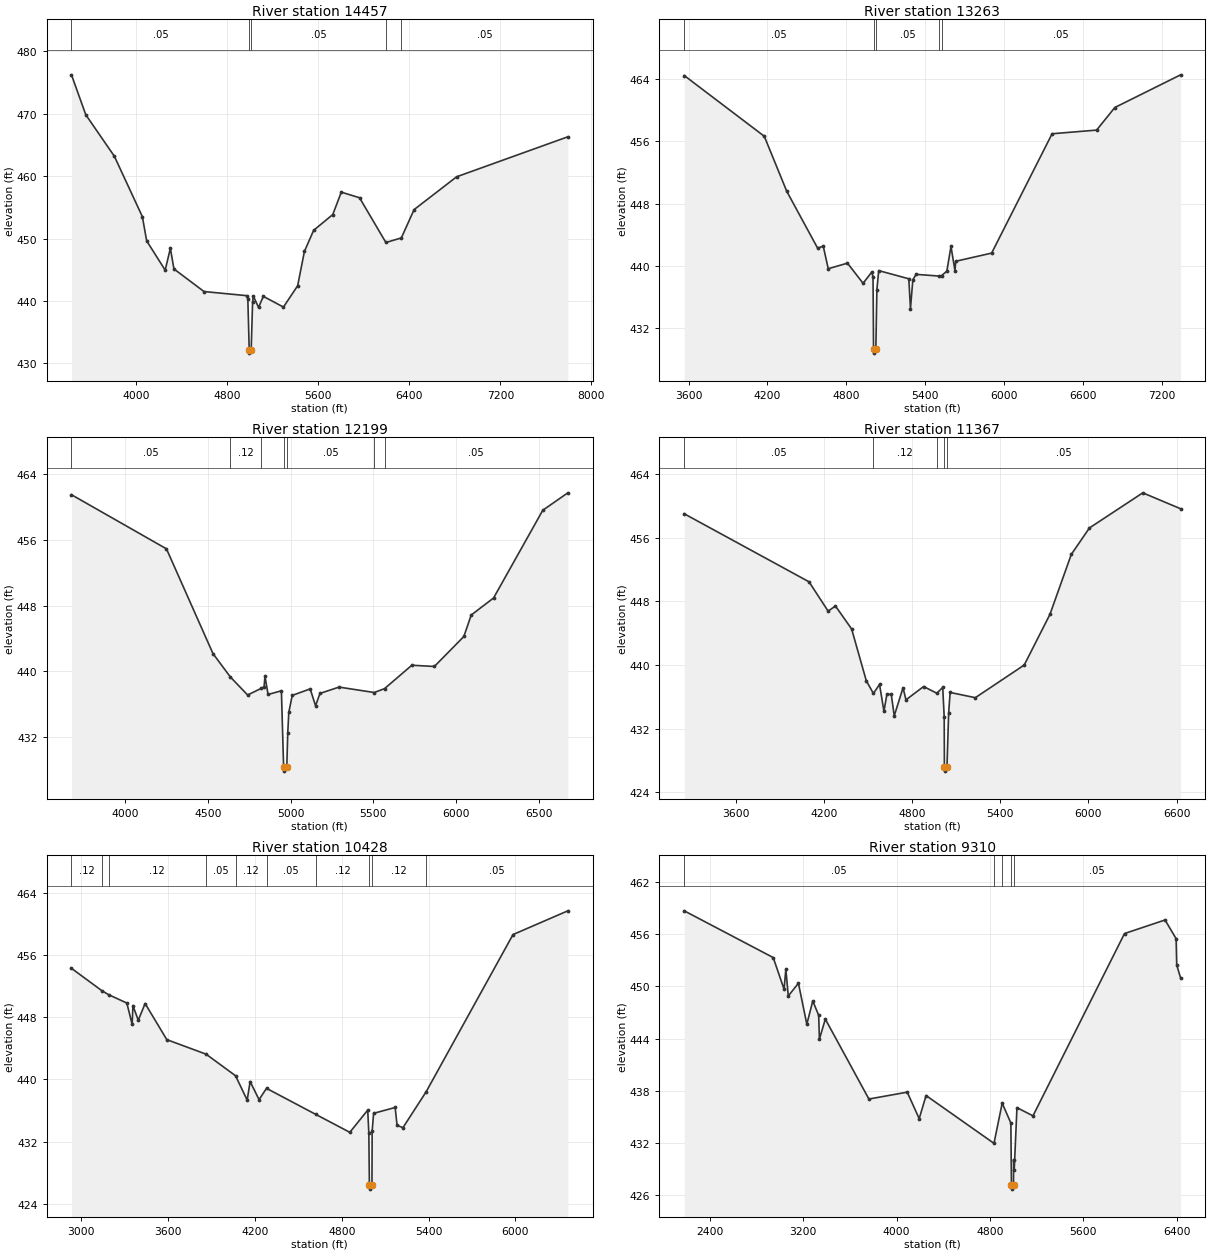
Type RM Length L Ch R = 1,14457,1194,1194,1194
BEGIN DESCRIPTION:
Terry Creek 19.0
END DESCRIPTION:
XS GIS Cut Line= 3
      2630126.01      6948511.00      2628504.09      6949015.48
      2626176.04      6950310.98
#Sta/Elev= 30
  3429.5  476.26  3555.2  469.86  3806.5  463.21  4052.5  453.53  4090.3  449.65
  4253.0  444.96  4298.7  448.45  4330.1  445.15  4594.2  441.53  4969.0  440.87
  4979.4  440.40  4991.8  432.16  4993.8  431.66  5009.0  432.16  5021.3  439.78
  5027.7  440.82  5073.7  438.98  5115.6  440.76  5292.7  439.04  5417.4  442.46
  5476.8  447.96  5558.0  451.34  5726.1  453.87  5801.1  457.46  5961.3  456.56
  6192.9  449.39  6328.7  450.12  6440.8  454.66  6814.7  459.92  7792.3  466.33
#Mann=5,-1,0
  3429.5    0.05       0  4991.8    0.03       0  5009.0    0.05       0
  6192.9    0.12       0  6328.7    0.05       0
Bank Sta=4991.8,5009
Exp/Cntr=0.3,0.1

Type RM Length L Ch R = 1,13263,1064,1064,1064
BEGIN DESCRIPTION:
Terry Creek 17.0
END DESCRIPTION:
XS GIS Cut Line= 3
      2629576.01      6947260.99      2628326.00      6947961.00
      2626126.01      6948761.00
#Sta/Elev= 30
  3567.4  464.46  4175.9  456.66  4346.8  449.59  4581.1  442.30  4624.5  442.53
  4662.2  439.64  4808.3  440.36  4927.0  437.77  4992.1  439.19  5002.7  438.64
  5006.6  429.30  5008.6  428.80  5024.1  429.30  5032.0  436.95  5046.0  439.40
  5274.7  438.35  5287.4  434.53  5305.3  438.21  5329.9  438.92  5504.1  438.70
  5524.3  438.76  5564.0  439.33  5595.3  442.52  5625.9  439.37  5631.2  440.60
  5904.5  441.65  6364.1  456.98  6702.6  457.45  6840.9  460.35  7341.0  464.55
#Mann=5,-1,0
  3567.4    0.05       0  5006.6    0.03       0  5024.1    0.05       0
  5504.1    0.12       0  5524.3    0.05       0
Bank Sta=5006.6,5024.1
Exp/Cntr=0.3,0.1

Type RM Length L Ch R = 1,12199,832,832,832
BEGIN DESCRIPTION:
Terry Creek 15.0
END DESCRIPTION:
XS GIS Cut Line= 3
      2629144.75      6946833.17      2627876.00      6947211.00
      2626276.01      6947711.00
#Sta/Elev= 30
  3676.2  461.49  4250.3  454.90  4531.4  442.15  4636.5  439.30  4740.8  437.11
  4822.6  437.91  4840.3  438.06  4845.5  439.42  4864.4  437.17  4945.0  437.62
  4958.3  428.38  4959.9  428.34  4961.9  427.84  4977.5  428.34  4983.4  432.50
  4989.6  434.98  5010.5  437.06  5118.9  437.85  5151.4  435.80  5178.1  437.30
  5293.4  438.07  5506.0  437.41  5568.2  437.88  5733.4  440.73  5869.6  440.58
  6047.7  444.23  6092.2  446.84  6227.4  448.92  6524.9  459.60  6676.3  461.72
#Mann=7,-1,0
  3676.2    0.05       0  4636.5    0.12       0  4822.6    0.05       0
  4959.9    0.03       0  4977.5    0.05       0  5506.0    0.12       0
  5568.2    0.05       0
Bank Sta=4959.9,4977.5
Exp/Cntr=0.3,0.1

Type RM Length L Ch R = 1,11367,939,939,939
BEGIN DESCRIPTION:
Mapping XS 484c74dc
END DESCRIPTION:
XS GIS Cut Line= 3
      2629035.38      6946708.18      2627290.54      6946666.52
      2625670.88      6946885.25
#Sta/Elev= 30
  3247.8  458.99  4097.4  450.45  4227.5  446.77  4277.5  447.41  4387.5  444.53
  4487.5  438.02  4535.9  436.43  4577.6  437.57  4607.6  434.19  4627.6  436.31
  4657.6  436.32  4677.6  433.62  4737.6  437.14  4757.6  435.63  4877.6  437.30
  4967.8  436.46  5007.8  437.19  5017.9  433.50  5019.2  427.18  5021.2  426.68
  5036.8  427.18  5048.2  433.98  5058.3  436.56  5229.8  435.90  5562.8  440.00
  5737.9  446.36  5883.3  453.89  6006.8  457.21  6370.1  461.62  6627.5  459.62
#Mann=5,-1,0
  3247.8    0.05       0  4535.9    0.12       0  4967.8    0.05       0
  5019.2    0.03       0  5036.8    0.05       0
Bank Sta=5019.2,5036.8
Exp/Cntr=0.3,0.1

Type RM Length L Ch R = 1,10428,1118,1118,1118
BEGIN DESCRIPTION:
Mapping XS 38009a63
END DESCRIPTION:
XS GIS Cut Line= 3
      2629186.42      6946354.03      2627181.17      6945874.85
      2625832.24      6945650.90
#Sta/Elev= 30
  2933.2  454.28  3142.3  451.42  3189.2  450.90  3315.6  449.82  3352.5  447.07
  3357.6  449.49  3394.6  447.61  3441.8  449.76  3591.7  445.12  3863.2  443.25
  4066.5  440.48  4146.9  437.35  4167.4  439.73  4229.1  437.41  4280.5  438.86
  4621.2  435.51  4856.0  433.21  4979.7  436.06  4987.4  433.12  4991.3  426.41
  4993.3  425.91  5009.0  426.41  5010.3  433.38  5020.4  435.65  5169.2  436.40
  5182.6  434.10  5223.2  433.81  5383.7  438.43  5983.4  458.62  6362.3  461.67
#Mann=10,-1,0
  2933.2    0.12       0  3142.3    0.05       0  3189.2    0.12       0
  3863.2    0.05       0  4066.5    0.12       0  4280.5    0.05       0
  4621.2    0.12       0  4991.3    0.07       0  5009.0    0.12       0
  5383.7    0.05       0
Bank Sta=4991.3,5009
Exp/Cntr=0.3,0.1

Type RM Length L Ch R = 1,9310,363,363,363
BEGIN DESCRIPTION:
Mapping XS 41cf0a86
END DESCRIPTION:
XS GIS Cut Line= 6
      2629483.24      6946432.14      2628561.38      6945812.35
      2628092.06      6945490.34      2627297.78      6945039.82
      2626982.68      6944901.80      2625733.27      6944484.23
#Sta/Elev= 30
  2179.4  458.67  2942.2  453.30  3035.2  449.66  3050.2  451.97  3071.2  448.89
  3158.2  450.35  3230.2  445.64  3281.2  448.32  3331.9  446.66  3338.0  443.93
  3388.8  446.23  3762.3  437.05  4090.9  437.84  4193.3  434.80  4252.4  437.45
  4834.3  431.96  4904.7  436.57  4979.0  434.30  4984.0  427.20  4986.0  426.70
  5001.8  427.20  5002.4  430.10  5007.8  428.87  5031.2  436.06  5168.7  435.12
  5953.2  456.06  6300.7  457.62  6395.4  455.47  6400.7  452.44  6433.9  450.96
#Mann=5,-1,0
  2179.4    0.05       0  4834.3    0.12       0  4904.7    0.05       0
  4984.0    0.03       0  5001.8    0.05       0
Bank Sta=4984,5001.8
Exp/Cntr=0.3,0.1

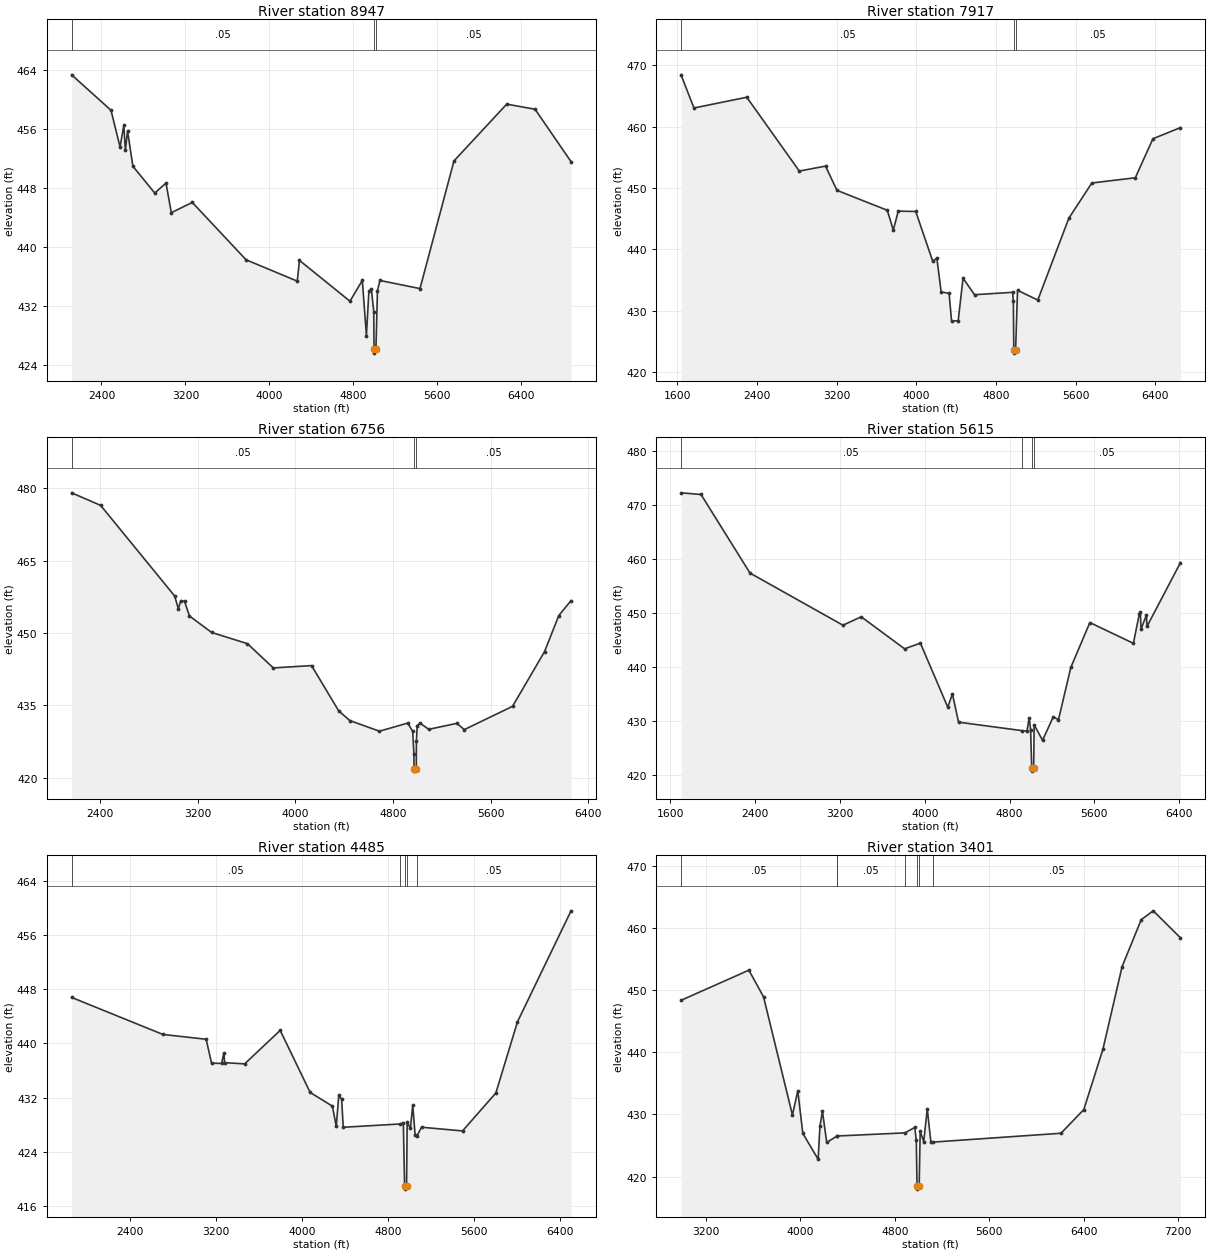
Type RM Length L Ch R = 1,8947,1030,1030,1030
BEGIN DESCRIPTION:
Mapping XS d697fe3b
END DESCRIPTION:
XS GIS Cut Line= 6
      2629618.71      6946270.71      2628785.34      6945687.35
      2628003.51      6945065.86      2627401.95      6944701.28
      2626855.08      6944466.90      2625446.81      6944150.89
#Sta/Elev= 30
  2115.9  463.30  2490.9  458.50  2577.2  453.52  2613.0  456.47  2627.8  453.09
  2648.7  455.69  2699.3  450.92  2907.7  447.29  3014.9  448.64  3065.5  444.63
  3265.2  446.02  3777.8  438.25  4265.1  435.36  4286.4  438.17  4767.3  432.64
  4885.3  435.46  4924.1  427.99  4947.7  434.00  4971.3  434.29  4994.1  431.24
  4996.8  426.11  4998.8  425.61  5014.6  426.11  5029.3  434.06  5052.9  435.45
  5434.5  434.35  5758.3  451.64  6260.6  459.33  6530.8  458.64  6873.6  451.54
#Mann=3,-1,0
  2115.9    0.05       0  4996.8    0.03       0  5014.6    0.05       0
Bank Sta=4996.8,5014.6
Exp/Cntr=0.3,0.1

Type RM Length L Ch R = 1,7917,1161,1161,1161
BEGIN DESCRIPTION:
Terry Creek 9.0
END DESCRIPTION:
XS GIS Cut Line= 3
      2630375.60      6945150.89      2627234.06      6943957.71
      2625590.96      6943803.68
#Sta/Elev= 30
  1639.5  468.42  1769.4  463.02  2299.0  464.77  2826.4  452.75  3089.1  453.56
  3204.2  449.61  3709.1  446.37  3769.4  443.13  3818.9  446.23  3994.3  446.17
  4164.4  438.09  4206.3  438.56  4249.4  433.07  4329.1  432.84  4353.9  428.34
  4420.3  428.37  4469.1  435.31  4584.2  432.62  4965.8  433.01  4973.9  431.66
  4978.2  423.61  4980.2  423.11  4996.3  423.61  5015.7  433.34  5219.0  431.75
  5530.4  445.07  5761.4  450.81  6197.6  451.66  6374.1  458.01  6650.3  459.83
#Mann=3,-1,0
  1639.5    0.05       0  4978.2    0.03       0  4996.3    0.05       0
Bank Sta=4978.2,4996.3
Exp/Cntr=0.3,0.1

Type RM Length L Ch R = 1,6756,1141,1141,1141
BEGIN DESCRIPTION:
Terry Creek 7.0
END DESCRIPTION:
XS GIS Cut Line= 3
      2629931.22      6943393.95      2627127.82      6942967.12
      2625875.97      6943111.00
#Sta/Elev= 30
  2164.3  479.01  2402.2  476.41  3009.1  457.66  3039.5  455.02  3059.7  456.70
  3090.1  456.56  3130.5  453.52  3312.6  450.11  3605.9  447.79  3818.4  442.77
  4131.9  443.25  4354.5  433.88  4445.5  431.88  4688.3  429.67  4920.9  431.36
  4961.4  429.62  4971.5  425.00  4972.6  421.91  4974.6  421.41  4990.7  421.91
  4991.7  427.56  4998.4  430.83  5022.0  431.36  5092.4  430.06  5323.9  431.30
  5384.3  430.00  5780.2  434.82  6042.4  446.13  6159.4  453.60  6260.1  456.70
#Mann=3,-1,0
  2164.3    0.05       0  4972.6    0.03       0  4990.7    0.05       0
Bank Sta=4972.6,4990.7
Exp/Cntr=0.3,0.1

Type RM Length L Ch R = 1,5615,1130,1130,1130
BEGIN DESCRIPTION:
Terry Creek 5.0
END DESCRIPTION:
XS GIS Cut Line= 3
      2629965.89      6940963.39      2626826.00      6941961.00
      2625653.42      6942755.04
#Sta/Elev= 30
  1701.2  472.30  1890.0  471.99  2351.6  457.42  3228.4  447.75  3400.9  449.31
  3810.1  443.37  3958.9  444.43  4216.9  432.56  4261.3  434.99  4318.9  429.77
  4912.9  428.21  4964.3  428.10  4985.3  430.61  4998.8  428.31  5009.0  421.19
  5011.0  420.69  5027.3  421.19  5032.0  429.29  5111.1  426.40  5212.9  430.78
  5261.5  430.22  5377.7  439.91  5557.5  448.24  5967.9  444.39  6024.8  449.90
  6033.7  450.18  6039.8  447.00  6090.7  449.60  6096.7  447.54  6411.9  459.35
#Mann=4,-1,0
  1701.2    0.05       0  4912.9    0.12       0  5009.0    0.07       0
  5027.3    0.05       0
Bank Sta=5009,5027.3
Exp/Cntr=0.3,0.1

Type RM Length L Ch R = 1,4485,1084,1084,1084
BEGIN DESCRIPTION:
Terry Creek 3.0
END DESCRIPTION:
XS GIS Cut Line= 3
      2628660.31      6939359.25      2626126.00      6941211.00
      2625403.40      6942525.88
#Sta/Elev= 30
  1861.0  446.79  2708.9  441.32  3110.4  440.61  3160.6  437.08  3253.5  437.03
  3275.7  438.60  3281.9  437.15  3468.0  436.97  3798.4  441.92  4076.5  432.75
  4283.5  430.72  4319.0  427.73  4342.2  432.30  4369.2  431.76  4383.9  427.60
  4913.0  428.09  4942.2  428.23  4953.9  418.96  4955.9  418.46  4972.2  418.96
  4977.7  428.33  5007.8  427.45  5029.6  430.87  5051.4  426.49  5065.8  426.24
  5111.0  427.61  5491.9  427.06  5801.7  432.67  6002.5  443.19  6500.1  459.59
#Mann=5,-1,0
  1861.0    0.05       0  4913.0    0.12       0  4953.9    0.07       0
  4972.2    0.12       0  5065.8    0.05       0
Bank Sta=4953.9,4972.2
Exp/Cntr=0.3,0.1

Type RM Length L Ch R = 1,3401,0,0,0
BEGIN DESCRIPTION:
Terry Creek 1.0
END DESCRIPTION:
XS GIS Cut Line= 3
      2626320.08      6939018.91      2625226.00      6940711.00
      2625090.95      6942920.78
#Sta/Elev= 30
  2989.4  448.37  3564.0  453.22  3688.0  448.93  3932.8  429.91  3978.3  433.81
  4020.5  426.96  4150.5  422.80  4165.6  428.09  4186.8  430.53  4223.0  425.50
  4311.1  426.54  4311.6  426.54  4884.5  427.04  4968.7  427.91  4981.6  425.82
  4987.7  418.49  4989.7  417.99  5006.0  418.49  5014.4  427.27  5044.5  425.65
  5074.5  430.89  5104.6  425.65  5124.9  425.56  6206.6  426.98  6399.9  430.79
  6562.0  440.51  6724.1  453.79  6886.2  461.35  6988.1  462.77  7218.3  458.43
#Mann=7,-1,0
  2989.4    0.05       0  4311.1    0.12       0  4311.6    0.05       0
  4884.5    0.12       0  4987.7    0.07       0  5006.0    0.12       0
  5124.9    0.05       0
Bank Sta=4987.7,5006
Exp/Cntr=0.3,0.1

Chan Stop Cuts=-1