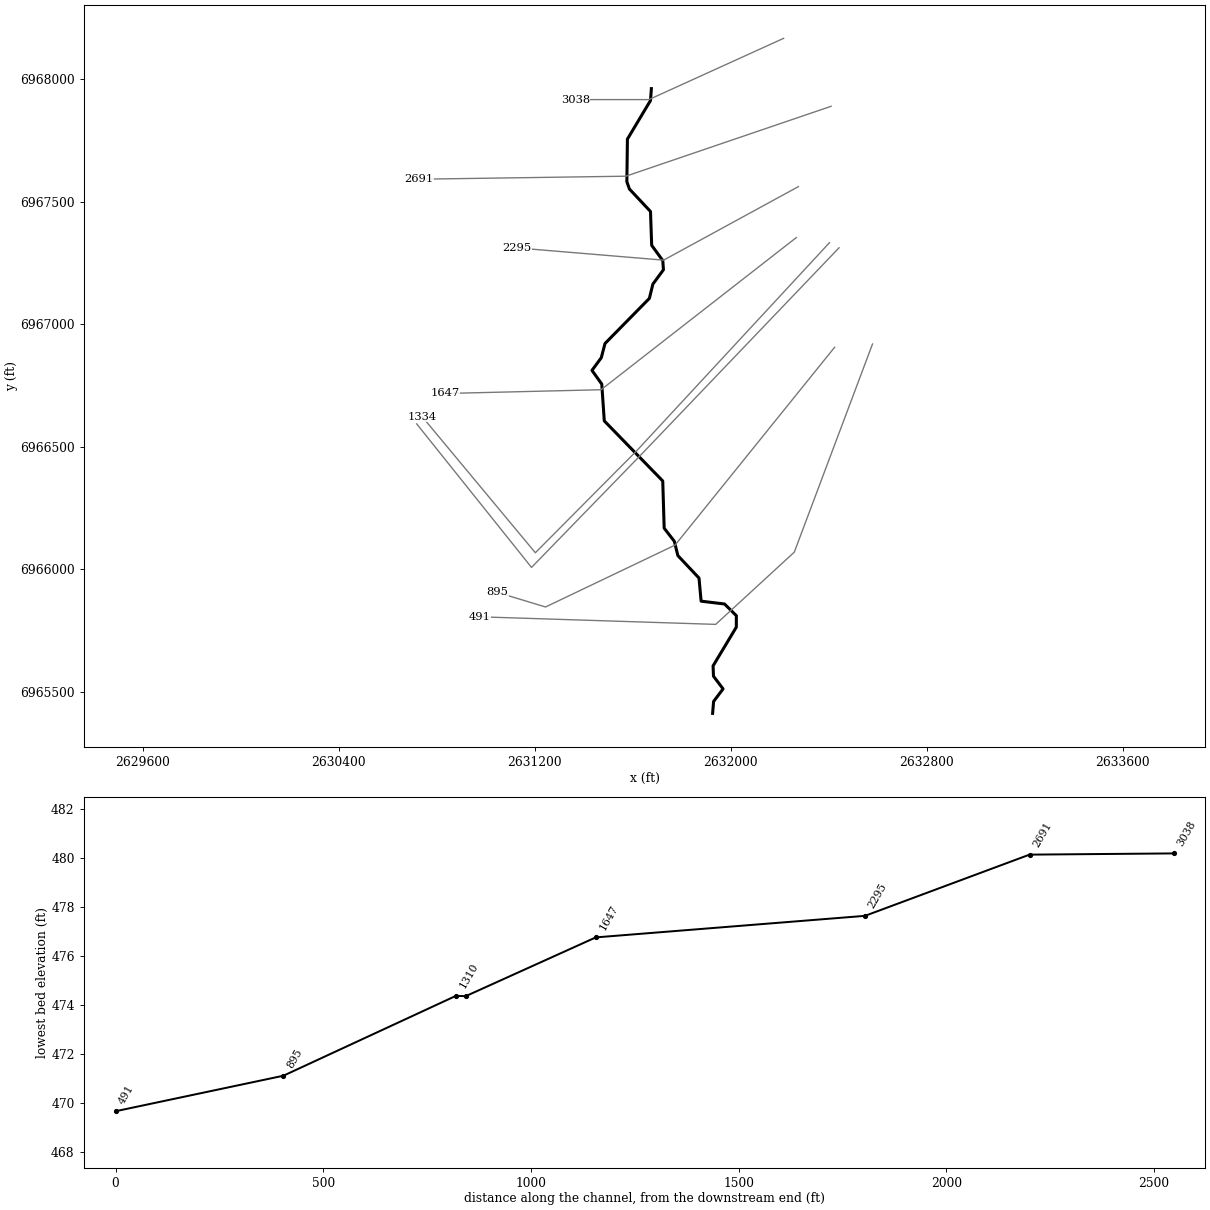
--- Terry Creek Trib 1.prj (project) ---

Proj Title=Terry Creek Trib 1 Base Level Engineering
Current Plan=p01
Default Exp/Contr=0.3,0.1
English Units
Geom File=g01
Flow File=f01
Plan File=p01
BEGIN DESCRIPTION:
Terry Creek Trib 1
END DESCRIPTION:

--- Terry Creek Trib 1.p01 (plan) ---

Plan Title=Multiple Run
Short Identifier=Multiple
Geom File=g01
Flow File=f01
Subcritical Flow
K Sum by GR= 0
Std Step Tol= 0.01
Critical Tol= 0.01
Num of Std Step Trials= 20
Max Error Tol= 0.3
Flow Tol Ratio= 0.001
Split Flow NTrial= 30
Split Flow Tol= 0.02
Split Flow Ratio= 0.02
Log Output Level= 0
Friction Slope Method= 1
Unsteady Friction Slope Method= 2
Unsteady Bridges Friction Slope Method= 1
Parabolic Critical Depth
Global Vel Dist=  1 , 1 , 1
Global Log Level= 0
CheckData=True
Encroach Param= -1, 0, 0, 0
BEGIN DESCRIPTION:
Multiple Run
END DESCRIPTION:

--- Terry Creek Trib 1.f01 (steady flow) ---

Flow Title=Multiple
Number of Profiles=7
Profile Names=10-year,25-year,50-year,1pct_min,100-year,1pct_plu,500-year
River Rch & RM= Terry Creek Trib,Reach-1,3038
     428     560     662     390     777    1551    1068
Boundary for River Rch & Prof#=Terry Creek Trib,Reach-1,1
Up Type=0
Dn Type=3
Dn Slope=0.005
Boundary for River Rch & Prof#=Terry Creek Trib,Reach-1,2
Up Type=0
Dn Type=3
Dn Slope=0.005
Boundary for River Rch & Prof#=Terry Creek Trib,Reach-1,3
Up Type=0
Dn Type=3
Dn Slope=0.005
Boundary for River Rch & Prof#=Terry Creek Trib,Reach-1,4
Up Type=0
Dn Type=3
Dn Slope=0.005
Boundary for River Rch & Prof#=Terry Creek Trib,Reach-1,5
Up Type=0
Dn Type=3
Dn Slope=0.005
Boundary for River Rch & Prof#=Terry Creek Trib,Reach-1,6
Up Type=0
Dn Type=3
Dn Slope=0.005
Boundary for River Rch & Prof#=Terry Creek Trib,Reach-1,7
Up Type=0
Dn Type=3
Dn Slope=0.005

--- Terry Creek Trib 1.g01 (geometry) ---

Geom Title=Existing Conditions

River Reach=Terry Creek Trib,Reach-1
Reach XY= 30
      2631676.00      6967961.00      2631672.40      6967912.49
      2631578.24      6967755.07      2631575.96      6967580.99
      2631586.50      6967551.21      2631672.44      6967459.53
      2631677.25      6967321.50      2631722.63      6967259.26
      2631725.25      6967221.68      2631682.18      6967163.19
      2631667.86      6967104.94      2631486.75      6966920.68
      2631471.55      6966862.65      2631433.53      6966811.01
      2631473.53      6966755.14      2631483.82      6966604.81
      2631722.46      6966359.54      2631728.24      6966166.93
      2631769.86      6966113.17      2631784.16      6966054.95
      2631870.44      6965963.36      2631879.03      6965869.01
      2631974.70      6965857.44      2632022.97      6965809.61
      2632022.70      6965762.77      2631927.83      6965604.88
      2631929.58      6965562.64      2631968.65      6965510.97
      2631930.00      6965459.64      2631926.00      6965411.00

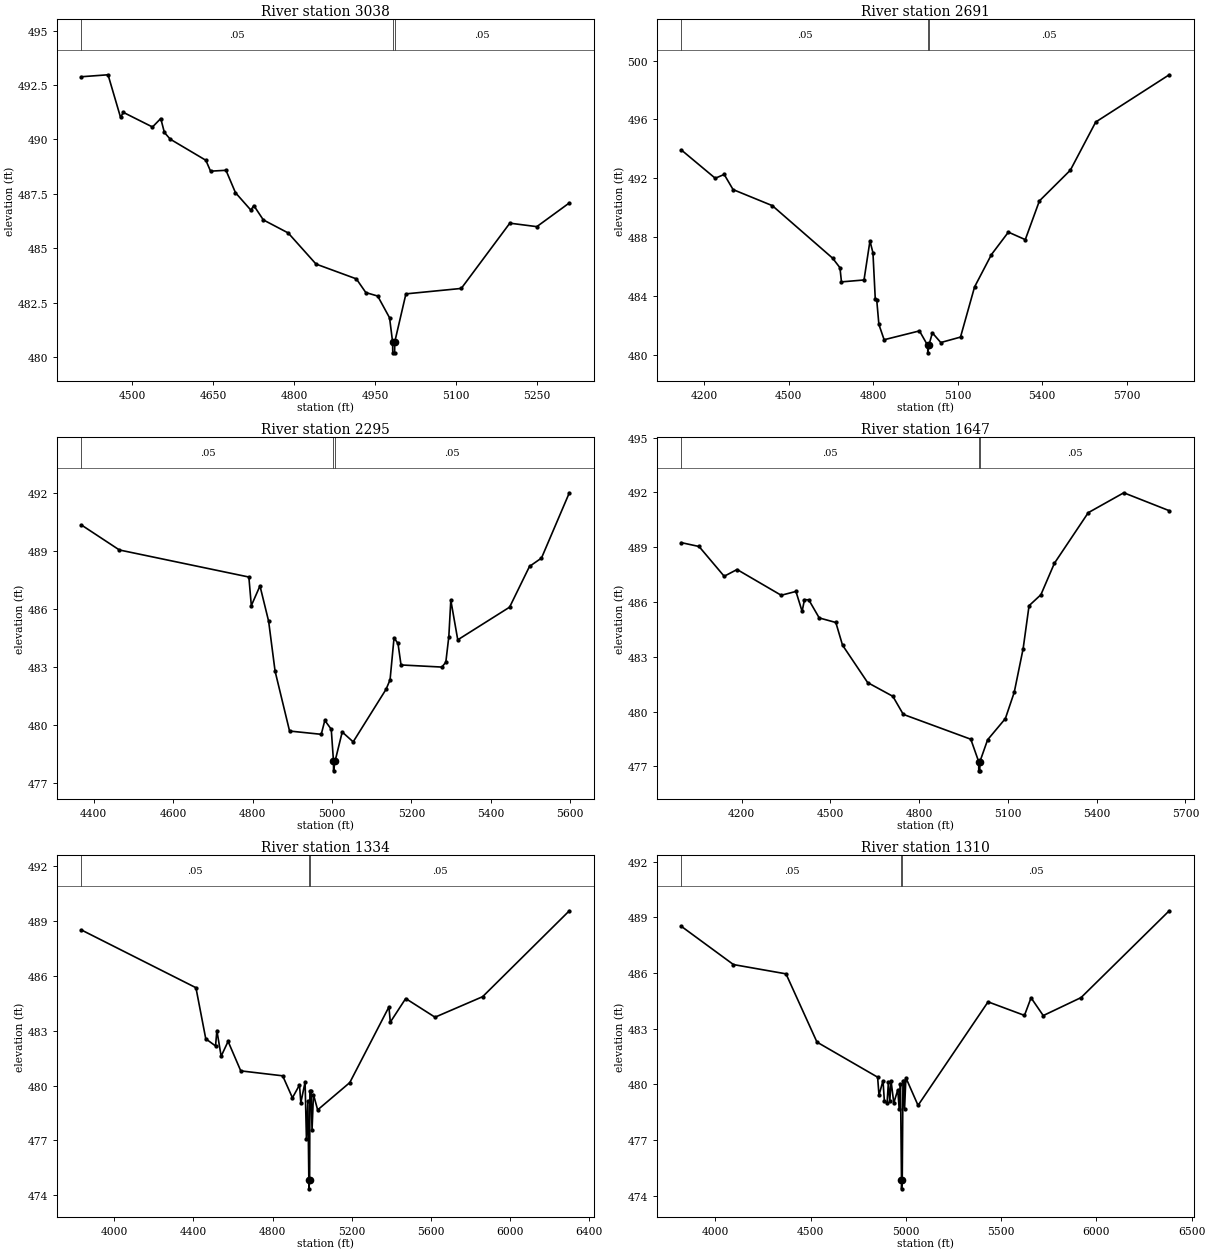
Type RM Length L Ch R = 1,3038,347,347,347
BEGIN DESCRIPTION:
Terry Creek Trib 1 4.0
END DESCRIPTION:
XS GIS Cut Line= 3
      2632215.79      6968166.34      2631665.78      6967916.34
      2631365.75      6967916.34
#Sta/Elev= 30
  4405.6  492.88  4454.8  492.97  4477.9  491.02  4483.3  491.24  4537.2  490.57
  4552.5  490.96  4559.2  490.32  4570.1  490.01  4636.1  489.04  4644.8  488.54
  4673.4  488.58  4691.0  487.55  4719.5  486.75  4725.0  486.96  4742.6  486.30
  4788.7  485.70  4840.3  484.27  4915.0  483.59  4932.6  482.96  4954.6  482.80
  4976.6  481.80  4982.2  480.69  4982.5  480.19  4986.0  480.19  4986.2  480.69
  5006.9  482.90  5109.5  483.15  5199.5  486.15  5249.5  485.99  5309.8  487.08
#Mann=3,-1,0
  4405.6    0.05       0  4982.2    0.03       0  4986.2    0.05       0
Bank Sta=4982.2,4986.2
Exp/Cntr=0.3,0.1

Type RM Length L Ch R = 1,2691,396,396,396
BEGIN DESCRIPTION:
Mapping XS 19e50f7f
END DESCRIPTION:
XS GIS Cut Line= 3
      2632409.83      6967889.03      2631571.99      6967603.61
      2630725.00      6967591.33
#Sta/Elev= 30
  4118.6  493.92  4238.9  492.00  4270.6  492.26  4302.2  491.23  4441.5  490.14
  4655.7  486.57  4681.7  485.92  4687.0  484.96  4767.1  485.09  4788.2  487.74
  4798.8  486.94  4807.1  483.79  4812.4  483.70  4819.9  482.07  4838.5  481.03
  4963.9  481.63  4993.3  480.64  4993.5  480.14  4997.3  480.64  5009.7  481.50
  5039.7  480.84  5109.7  481.21  5159.7  484.62  5219.7  486.82  5279.7  488.34
  5339.7  487.83  5389.8  490.46  5499.8  492.55  5589.8  495.82  5850.8  499.03
#Mann=3,-1,0
  4118.6    0.05       0  4993.3    0.03       0  4997.3    0.05       0
Bank Sta=4993.3,4997.3
Exp/Cntr=0.3,0.1

Type RM Length L Ch R = 1,2295,648,648,648
BEGIN DESCRIPTION:
Terry Creek Trib 1 3.0
END DESCRIPTION:
XS GIS Cut Line= 3
      2632276.03      6967561.02      2631726.00      6967261.00
      2631126.02      6967311.00
#Sta/Elev= 30
  4369.0  490.36  4464.4  489.07  4790.5  487.67  4796.7  486.19  4818.5  487.21
  4840.3  485.38  4856.5  482.80  4893.0  479.70  4972.8  479.53  4981.8  480.25
  4998.0  479.79  5003.6  478.14  5003.8  477.64  5007.6  478.14  5025.6  479.65
  5053.2  479.14  5136.0  481.86  5146.1  482.35  5156.1  484.52  5166.1  484.23
  5173.7  483.12  5276.5  483.01  5286.5  483.26  5294.1  484.59  5299.1  486.47
  5316.6  484.42  5447.1  486.11  5497.3  488.22  5527.4  488.65  5597.6  492.03
#Mann=3,-1,0
  4369.0    0.05       0  5003.6    0.03       0  5007.6    0.05       0
Bank Sta=5003.6,5007.6
Exp/Cntr=0.3,0.1

Type RM Length L Ch R = 1,1647,313,313,313
BEGIN DESCRIPTION:
Mapping XS 76a487e1
END DESCRIPTION:
XS GIS Cut Line= 3
      2632267.58      6967353.10      2631470.71      6966732.03
      2630832.40      6966716.69
#Sta/Elev= 30
  3996.5  489.25  4056.2  489.04  4141.2  487.41  4184.7  487.78  4333.9  486.37
  4383.7  486.58  4404.5  485.49  4412.6  486.13  4427.1  486.12  4462.4  485.13
  4518.5  484.88  4541.1  483.64  4626.1  481.59  4711.2  480.84  4746.5  479.85
  4974.7  478.49  5001.4  477.26  5001.6  476.76  5005.1  476.76  5005.4  477.26
  5031.5  478.46  5091.5  479.62  5121.5  481.06  5151.6  483.45  5171.6  485.80
  5211.6  486.40  5257.2  488.12  5371.6  490.89  5491.7  491.98  5645.3  491.00
#Mann=3,-1,0
  3996.5    0.05       0  5001.4   0.035       0  5005.4    0.05       0
Bank Sta=5001.4,5005.4
Exp/Cntr=0.3,0.1

Type RM Length L Ch R = 1,1334,24,24,24
BEGIN DESCRIPTION:
Mapping XS 432fa11c
END DESCRIPTION:
XS GIS Cut Line= 4
      2632402.97      6967332.24      2631616.51      6966483.28
      2631202.44      6966066.61      2630739.96      6966622.63
#Sta/Elev= 30
  3833.7  488.49  4412.6  485.34  4462.4  482.55  4511.8  482.16  4518.6  483.00
  4540.2  481.60  4575.3  482.41  4639.4  480.80  4851.4  480.53  4900.8  479.33
  4936.5  480.03  4943.3  479.06  4964.8  480.19  4971.6  477.09  4979.0  479.15
  4983.8  474.86  4984.1  474.36  4987.8  474.86  4989.1  479.70  4994.9  479.70
  5000.0  477.56  5007.1  479.51  5028.3  478.67  5190.9  480.16  5388.9  484.29
  5396.0  483.46  5473.7  484.75  5622.1  483.73  5862.9  484.85  6301.6  489.54
#Mann=3,-1,0
  3833.7    0.05       0  4983.8   0.035       0  4987.8    0.05       0
Bank Sta=4983.8,4987.8
Exp/Cntr=0.3,0.1

Type RM Length L Ch R = 1,1310,415,415,415
BEGIN DESCRIPTION:
Mapping XS 3f98512f
END DESCRIPTION:
XS GIS Cut Line= 4
      2632442.02      6967311.40      2631634.73      6966467.65
      2631186.82      6966006.72      2630718.09      6966592.63
#Sta/Elev= 30
  3821.4  488.52  4094.8  486.46  4370.6  485.96  4533.2  482.28  4851.5  480.39
  4858.7  479.42  4879.8  480.20  4887.0  479.09  4901.2  479.00  4908.1  480.12
  4915.3  479.08  4922.2  480.18  4936.4  479.00  4957.5  479.71  4964.7  478.67
  4971.6  480.02  4976.8  474.87  4977.1  474.37  4980.8  474.87  4984.6  480.17
  4989.1  480.17  4993.0  478.69  4999.9  480.36  5063.7  478.87  5431.3  484.45
  5622.4  483.72  5656.9  484.67  5720.9  483.71  5919.4  484.68  6382.2  489.36
#Mann=3,-1,0
  3821.4    0.05       0  4976.8   0.035       0  4980.8    0.05       0
Bank Sta=4976.8,4980.8
Exp/Cntr=0.3,0.1

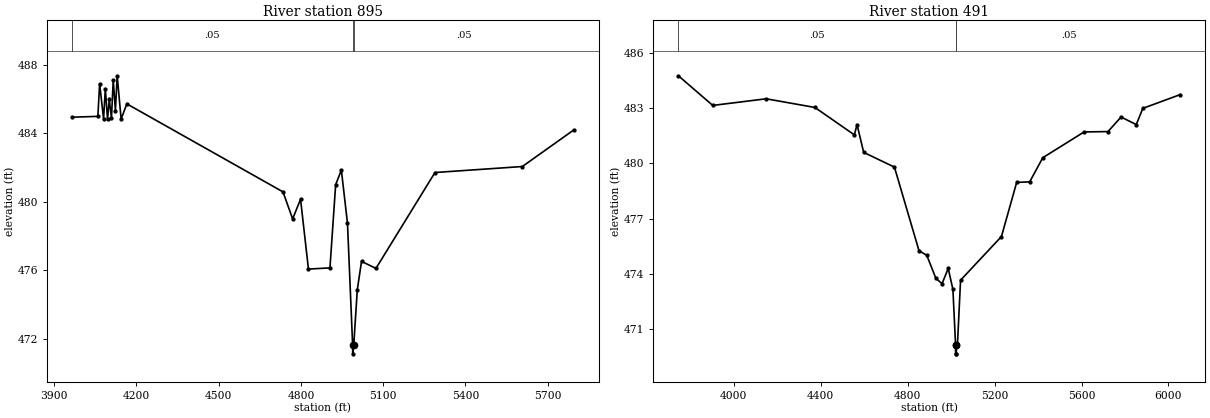
Type RM Length L Ch R = 1,895,404,404,404
BEGIN DESCRIPTION:
Mapping XS 2da995a5
END DESCRIPTION:
XS GIS Cut Line= 4
      2632423.82      6966905.19      2631772.76      6966097.86
      2631244.11      6965845.26      2631046.21      6965905.15
#Sta/Elev= 30
  3965.4  484.93  4059.9  484.98  4066.3  486.89  4080.7  484.83  4087.1  486.59
  4095.1  484.81  4101.5  485.97  4109.5  484.88  4115.9  487.11  4123.9  485.32
  4130.3  487.35  4144.7  484.82  4165.5  485.71  4734.8  480.57  4770.0  478.99
  4798.8  480.14  4827.6  476.06  4906.0  476.13  4926.8  480.99  4947.6  481.84
  4969.9  478.74  4988.7  471.61  4989.0  471.11  4992.7  471.61  5005.7  474.85
  5021.1  476.51  5073.7  476.10  5288.9  481.70  5607.4  482.05  5795.2  484.19
#Mann=3,-1,0
  3965.4    0.05       0  4988.7    0.04       0  4992.7    0.05       0
Bank Sta=4988.7,4992.7
Exp/Cntr=0.3,0.1

Type RM Length L Ch R = 1,491,0,0,0
BEGIN DESCRIPTION:
Terry Creek Trib 1 2.0
END DESCRIPTION:
XS GIS Cut Line= 4
      2632578.68      6966918.80      2632259.43      6966069.15
      2631938.54      6965774.26      2630973.50      6965805.22
#Sta/Elev= 30
  3745.4  484.76  3903.3  483.15  4149.0  483.51  4373.3  483.04  4554.9  481.55
  4567.1  482.11  4597.7  480.60  4739.2  479.80  4852.2  475.26  4888.0  475.01
  4929.9  473.76  4958.3  473.47  4986.6  474.30  5008.2  473.16  5020.4  470.16
  5020.6  469.66  5024.1  469.66  5024.4  470.16  5029.2  470.18  5043.4  473.66
  5231.5  476.03  5301.5  478.97  5361.5  479.00  5421.6  480.31  5611.7  481.71
  5721.7  481.73  5781.8  482.52  5851.8  482.11  5881.8  482.99  6054.4  483.74
#Mann=3,-1,0
  3745.4    0.05       0  5020.4    0.03       0  5024.4    0.05       0
Bank Sta=5020.4,5024.4
Exp/Cntr=0.3,0.1

Chan Stop Cuts=-1