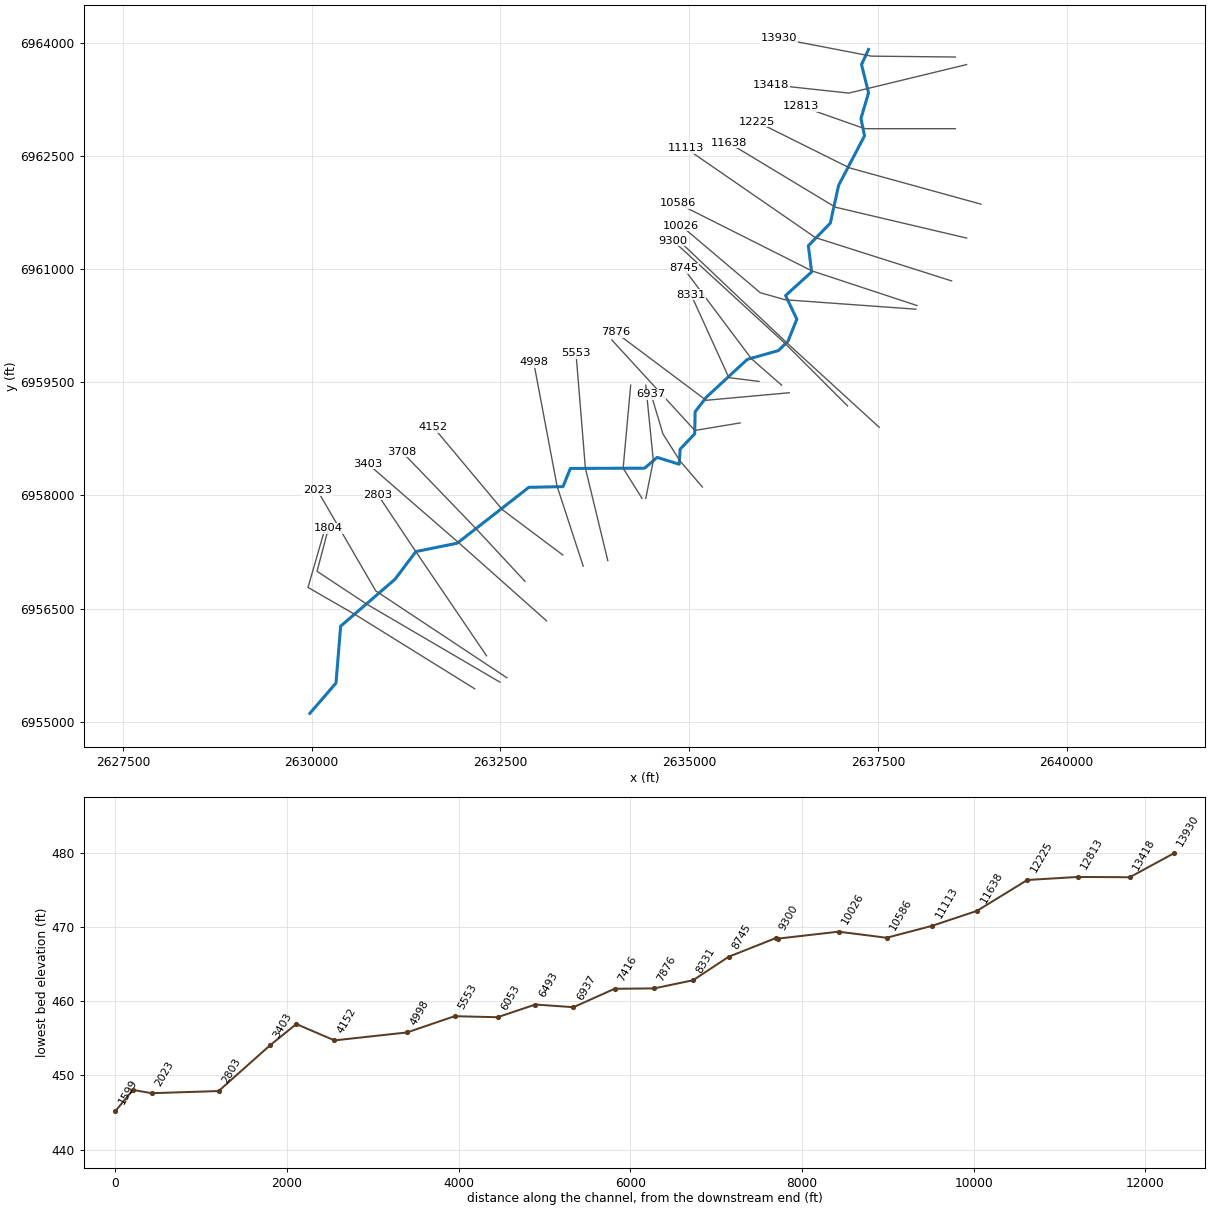
--- Terry Creek Trib 2.prj (project) ---

Proj Title=Terry Creek Trib 2 Base Level Engineering
Current Plan=p01
Default Exp/Contr=0.3,0.1
English Units
Geom File=g01
Flow File=f01
Plan File=p01
BEGIN DESCRIPTION:
Terry Creek Trib 2
END DESCRIPTION:

--- Terry Creek Trib 2.p01 (plan) ---

Plan Title=Multiple Run
Short Identifier=Multiple
Geom File=g01
Flow File=f01
Subcritical Flow
K Sum by GR= 0
Std Step Tol= 0.01
Critical Tol= 0.01
Num of Std Step Trials= 20
Max Error Tol= 0.3
Flow Tol Ratio= 0.001
Split Flow NTrial= 30
Split Flow Tol= 0.02
Split Flow Ratio= 0.02
Log Output Level= 0
Friction Slope Method= 1
Unsteady Friction Slope Method= 2
Unsteady Bridges Friction Slope Method= 1
Parabolic Critical Depth
Global Vel Dist=  1 , 1 , 1
Global Log Level= 0
CheckData=True
Encroach Param= -1, 0, 0, 0
BEGIN DESCRIPTION:
Multiple Run
END DESCRIPTION:

--- Terry Creek Trib 2.f01 (steady flow) ---

Flow Title=Multiple
Number of Profiles=7
Profile Names=10-year,25-year,50-year,1pct_min,100-year,1pct_plu,500-year
River Rch & RM= Terry Creek Trib,Reach-1,13930
     549     732     880     524    1046    2088    1480
River Rch & RM= Terry Creek Trib,Reach-1,12813
     752    1020    1239     746    1489    2972    2150
River Rch & RM= Terry Creek Trib,Reach-1,11638
     997    1368    1675    1015    2025    4041    2961
River Rch & RM= Terry Creek Trib,Reach-1,6937
    1254    1738    2140    1304    2602    5191    3846
River Rch & RM= Terry Creek Trib,Reach-1,4152
    1277    1771    2183    1331    2656    5299    3931
River Rch & RM= Terry Creek Trib,Reach-1,2803
    1372    1907    2354    1437    2867    5720    4253
Boundary for River Rch & Prof#=Terry Creek Trib,Reach-1,1
Up Type=0
Dn Type=3
Dn Slope=0.005
Boundary for River Rch & Prof#=Terry Creek Trib,Reach-1,2
Up Type=0
Dn Type=3
Dn Slope=0.005
Boundary for River Rch & Prof#=Terry Creek Trib,Reach-1,3
Up Type=0
Dn Type=3
Dn Slope=0.005
Boundary for River Rch & Prof#=Terry Creek Trib,Reach-1,4
Up Type=0
Dn Type=3
Dn Slope=0.005
Boundary for River Rch & Prof#=Terry Creek Trib,Reach-1,5
Up Type=0
Dn Type=3
Dn Slope=0.005
Boundary for River Rch & Prof#=Terry Creek Trib,Reach-1,6
Up Type=0
Dn Type=3
Dn Slope=0.005
Boundary for River Rch & Prof#=Terry Creek Trib,Reach-1,7
Up Type=0
Dn Type=3
Dn Slope=0.005

--- Terry Creek Trib 2.g01 (geometry) ---

Geom Title=Existing Conditions

River Reach=Terry Creek Trib,Reach-1
Reach XY= 30
      2637376.00      6963911.00      2637283.56      6963711.00
      2637376.30      6963336.05      2637276.09      6962995.61
      2637323.77      6962766.93      2636979.75      6962109.45
      2636870.18      6961608.69      2636579.14      6961309.36
      2636622.87      6960962.62      2636277.61      6960649.17
      2636426.51      6960336.04      2636309.61      6960044.33
      2636182.74      6959920.13      2635769.96      6959802.82
      2635231.62      6959305.38      2635079.54      6959109.54
      2635073.94      6958816.85      2634881.43      6958613.46
      2634868.30      6958413.70      2634576.00      6958503.92
      2634410.84      6958361.38      2633427.22      6958357.57
      2633328.74      6958116.34      2632877.47      6958107.45
      2631928.30      6957366.83      2631381.41      6957255.83
      2631102.82      6956887.29      2630384.14      6956267.06
      2630322.45      6955512.47      2629976.00      6955111.00

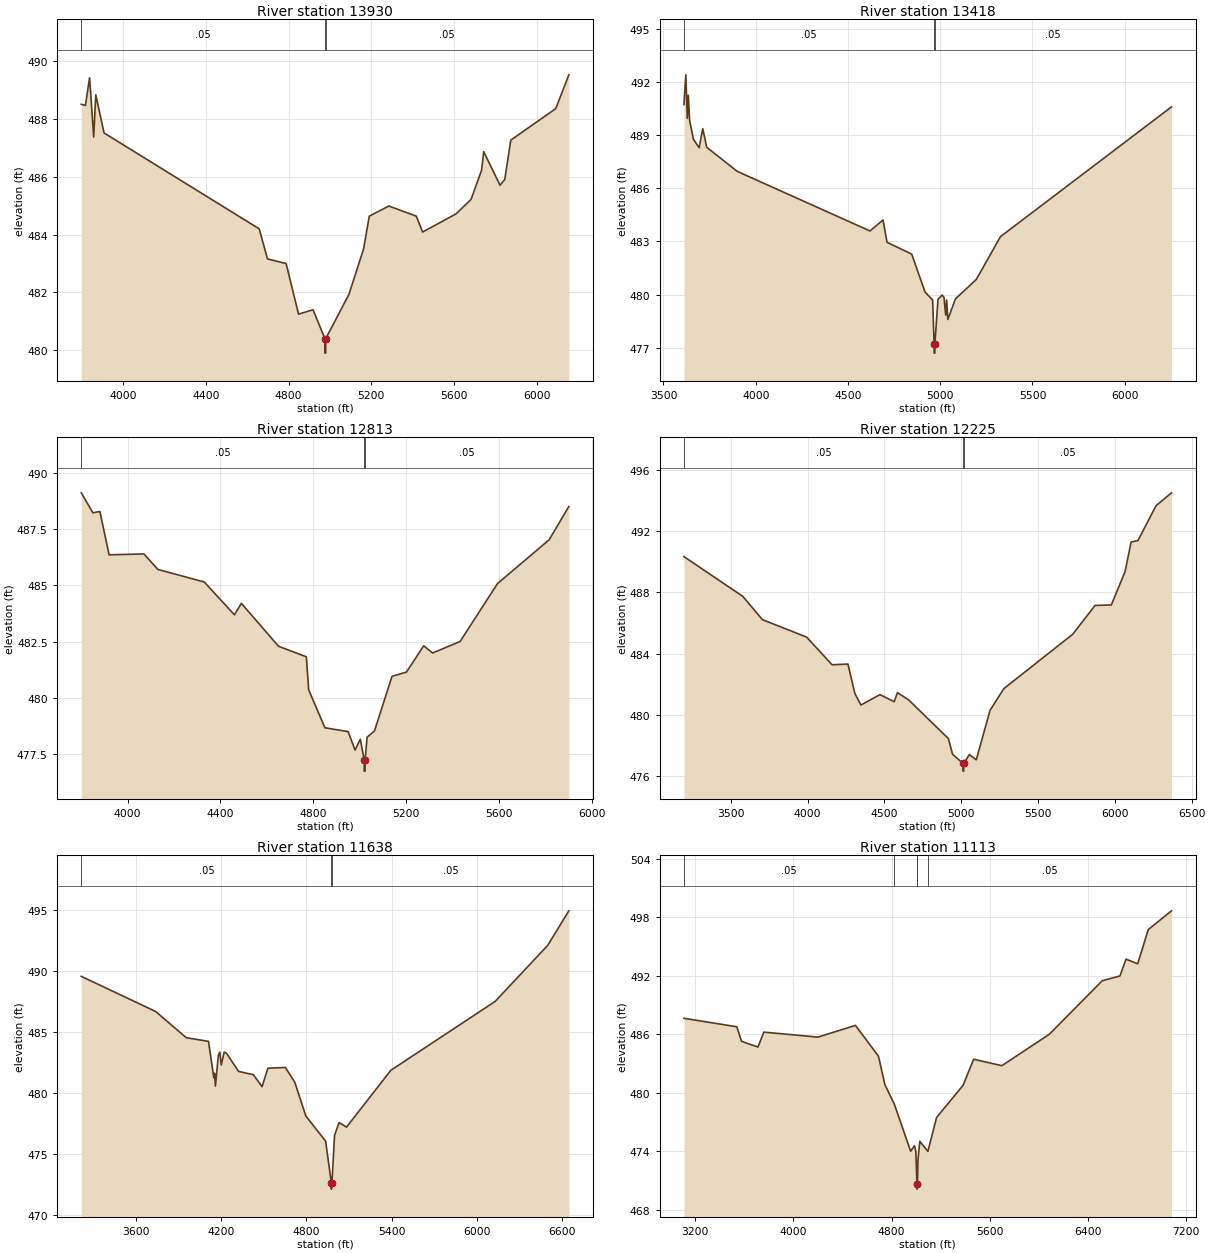
Type RM Length L Ch R = 1,13930,512,512,512
BEGIN DESCRIPTION:
Terry Creek Trib 2 27.0
END DESCRIPTION:
XS GIS Cut Line= 3
      2638526.04      6963811.00      2637414.11      6963822.51
      2636191.89      6964058.62
#Sta/Elev= 30
  3798.4  488.51  3818.4  488.47  3838.4  489.43  3858.4  487.38  3868.4  488.84
  3908.4  487.52  4658.5  484.20  4698.5  483.16  4788.5  483.00  4848.5  481.25
  4918.6  481.40  4976.1  480.40  4976.3  479.90  4979.8  479.90  4980.1  480.40
  5091.9  481.93  5163.1  483.51  5190.5  484.64  5285.3  484.99  5417.7  484.64
  5448.3  484.09  5610.2  484.72  5682.5  485.22  5733.4  486.23  5743.6  486.87
  5822.5  485.71  5845.5  485.91  5874.4  487.27  6091.8  488.36  6155.2  489.53
#Mann=3,-1,0
  3798.4    0.05       0  4976.1    0.03       0  4980.1    0.05       0
Bank Sta=4976.1,4980.1
Exp/Cntr=0.3,0.1

Type RM Length L Ch R = 1,13418,605,605,605
BEGIN DESCRIPTION:
Terry Creek Trib 2 26.0
END DESCRIPTION:
XS GIS Cut Line= 3
      2638675.95      6963710.99      2637115.50      6963332.92
      2636084.27      6963444.03
#Sta/Elev= 30
  3610.9  490.73  3621.1  492.41  3629.2  489.95  3634.3  491.26  3641.7  489.83
  3662.3  488.77  3693.2  488.29  3712.8  489.37  3734.3  488.32  3899.0  486.96
  4619.2  483.59  4689.9  484.21  4711.8  482.95  4845.6  482.28  4917.6  480.14
  4958.8  479.69  4967.0  477.19  4967.3  476.69  4970.8  476.69  4971.0  477.19
  4987.8  479.73  5010.2  479.97  5020.5  479.84  5029.6  478.84  5034.7  479.69
  5041.1  478.59  5082.2  479.75  5195.4  480.85  5326.6  483.27  6253.7  490.60
#Mann=3,-1,0
  3610.9    0.05       0  4967.0    0.03       0  4971.0    0.05       0
Bank Sta=4967,4971
Exp/Cntr=0.3,0.1

Type RM Length L Ch R = 1,12813,588,588,588
BEGIN DESCRIPTION:
Terry Creek Trib 2 25.0
END DESCRIPTION:
XS GIS Cut Line= 3
      2638526.04      6962861.00      2637326.00      6962861.00
      2636476.03      6963160.99
#Sta/Elev= 30
  3800.4  489.12  3850.4  488.23  3880.4  488.29  3920.4  486.36  4070.4  486.40
  4130.4  485.71  4330.4  485.15  4460.4  483.69  4490.4  484.20  4650.4  482.29
  4770.4  481.82  4780.4  480.35  4850.4  478.66  4950.4  478.49  4980.4  477.67
  5003.1  478.15  5019.6  477.23  5019.9  476.73  5023.4  476.73  5023.6  477.23
  5032.3  478.24  5064.1  478.52  5139.6  480.95  5201.9  481.14  5276.2  482.31
  5314.6  481.99  5433.0  482.50  5594.3  485.08  5817.0  487.03  5901.8  488.51
#Mann=3,-1,0
  3800.4    0.05       0  5019.6    0.03       0  5023.6    0.05       0
Bank Sta=5019.6,5023.6
Exp/Cntr=0.3,0.1

Type RM Length L Ch R = 1,12225,587,587,587
BEGIN DESCRIPTION:
Terry Creek Trib 2 23.0
END DESCRIPTION:
XS GIS Cut Line= 3
      2638865.50      6961860.70      2637126.18      6962340.93
      2635900.63      6962950.78
#Sta/Elev= 30
  3195.6  490.34  3578.9  487.74  3706.3  486.22  3993.9  485.08  4160.0  483.27
  4263.0  483.32  4307.7  481.40  4347.3  480.64  4471.1  481.32  4563.7  480.86
  4585.2  481.45  4657.8  480.98  4917.2  478.44  4943.5  477.43  5012.2  476.82
  5012.4  476.32  5015.9  476.32  5016.2  476.82  5053.4  477.40  5098.2  477.06
  5187.7  480.29  5277.3  481.71  5725.2  485.26  5871.4  487.15  5977.1  487.18
  6066.6  489.36  6105.8  491.29  6150.6  491.39  6268.2  493.67  6368.9  494.51
#Mann=3,-1,0
  3195.6    0.05       0  5012.2    0.03       0  5016.2    0.05       0
Bank Sta=5012.2,5016.2
Exp/Cntr=0.3,0.1

Type RM Length L Ch R = 1,11638,525,525,525
BEGIN DESCRIPTION:
Terry Creek Trib 2 22.0
END DESCRIPTION:
XS GIS Cut Line= 3
      2638676.00      6961411.00      2636936.89      6961820.63
      2635525.18      6962673.23
#Sta/Elev= 30
  3213.3  489.60  3737.3  486.72  3953.0  484.57  4109.9  484.27  4147.1  481.29
  4152.2  481.66  4158.5  480.60  4179.0  483.12  4189.3  483.39  4199.7  482.34
  4220.1  483.39  4236.9  483.29  4321.6  481.81  4425.6  481.54  4487.2  480.56
  4528.3  482.07  4651.6  482.13  4718.2  480.91  4795.4  478.16  4935.2  476.09
  4975.4  472.66  4975.7  472.16  4979.7  472.66  4997.9  476.56  5030.0  477.62
  5082.4  477.24  5394.8  481.90  6130.3  487.55  6501.0  492.15  6649.2  494.97
#Mann=3,-1,0
  3213.3    0.05       0  4975.4    0.03       0  4979.7    0.05       0
Bank Sta=4975.4,4979.7
Exp/Cntr=0.3,0.1

Type RM Length L Ch R = 1,11113,527,527,527
BEGIN DESCRIPTION:
Terry Creek Trib 2 21.0
END DESCRIPTION:
XS GIS Cut Line= 3
      2638476.66      6960843.33      2636673.44      6961417.09
      2634960.14      6962599.67
#Sta/Elev= 30
  3107.7  487.66  3538.6  486.79  3576.8  485.30  3711.0  484.71  3759.0  486.24
  4199.7  485.73  4505.5  486.93  4693.0  483.78  4745.5  480.86  4823.3  478.83
  4955.3  474.03  4986.8  474.59  4998.2  473.97  5006.8  470.64  5007.2  470.14
  5011.2  470.64  5015.4  473.18  5030.3  475.04  5095.8  474.01  5167.0  477.49
  5382.5  480.78  5469.0  483.46  5698.9  482.80  6087.0  486.03  6516.9  491.51
  6661.6  492.00  6710.9  493.72  6806.3  493.25  6892.4  496.76  7081.8  498.68
#Mann=5,-1,0
  3107.7    0.05       0  4823.3    0.12       0  5006.8    0.07       0
  5011.2    0.12       0  5095.8    0.05       0
Bank Sta=5006.8,5011.2
Exp/Cntr=0.3,0.1

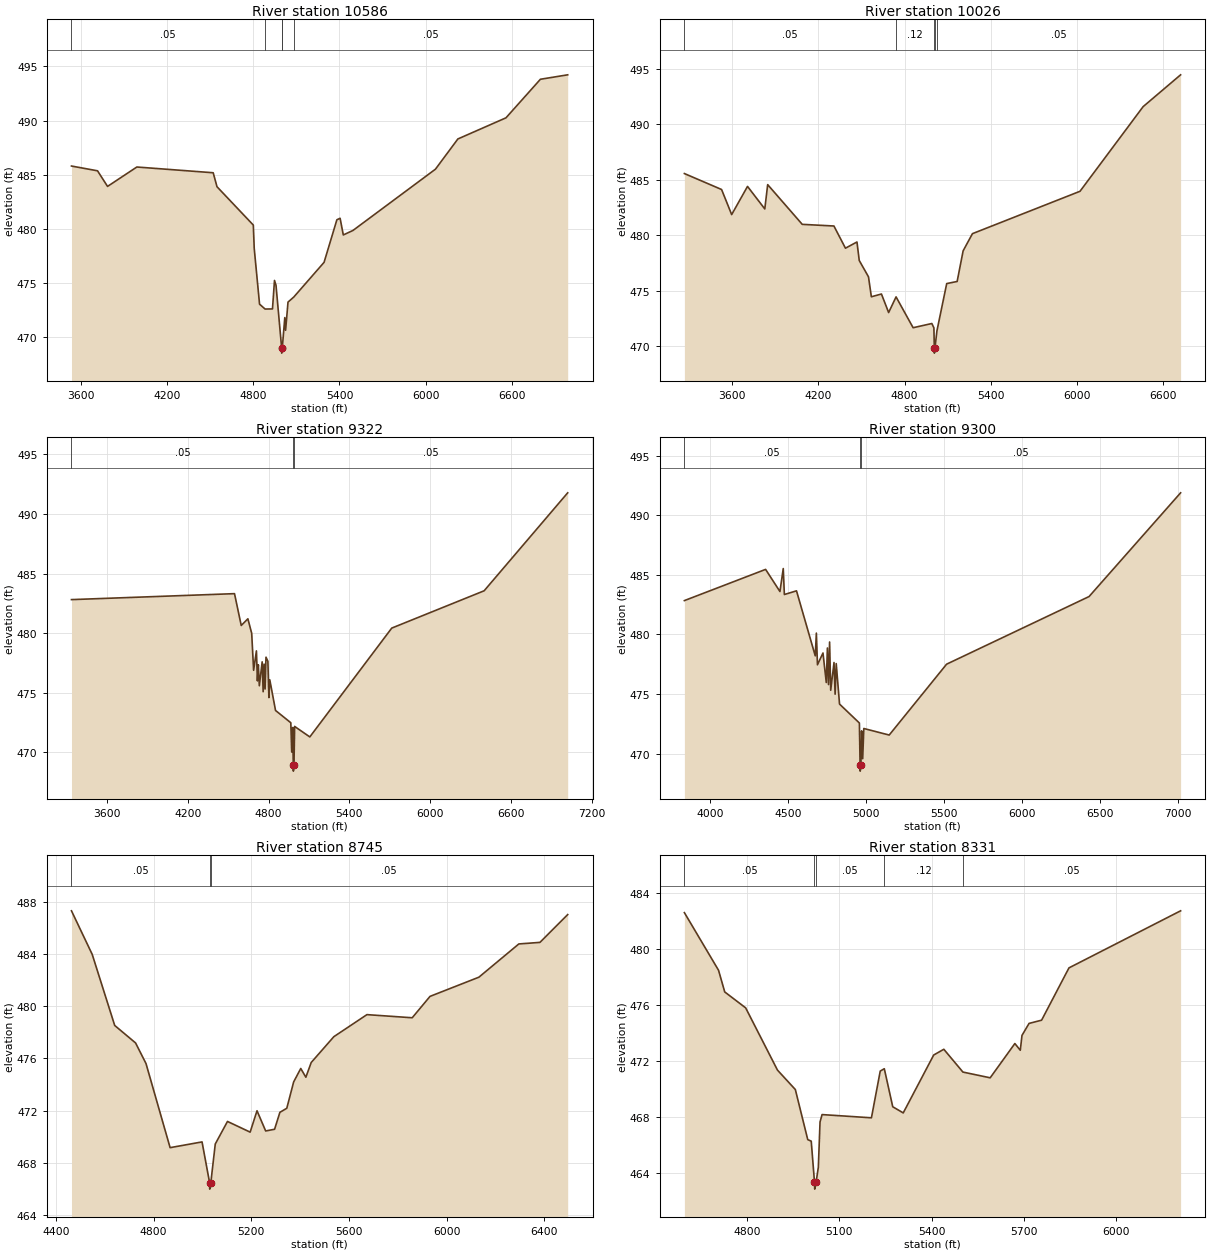
Type RM Length L Ch R = 1,10586,560,560,560
BEGIN DESCRIPTION:
Terry Creek Trib 2 20.0
END DESCRIPTION:
XS GIS Cut Line= 3
      2638018.31      6960516.94      2636626.04      6960976.33
      2634849.54      6961870.41
#Sta/Elev= 30
  3533.9  485.81  3715.3  485.37  3785.0  483.93  3989.1  485.72  4520.6  485.19
  4547.1  483.90  4800.0  480.36  4806.3  478.21  4843.4  473.06  4881.9  472.61
  4933.4  472.62  4947.4  475.25  4957.9  474.81  4997.1  469.04  4997.6  468.54
  5001.8  469.04  5019.2  471.82  5024.8  470.65  5041.5  473.25  5081.9  473.72
  5292.6  476.92  5381.8  480.85  5404.2  480.99  5426.5  479.45  5493.4  479.86
  6068.1  485.52  6224.3  488.31  6559.1  490.26  6798.9  493.82  6988.8  494.23
#Mann=5,-1,0
  3533.9    0.05       0  4881.9    0.12       0  4997.1    0.07       0
  5001.8    0.12       0  5081.9    0.05       0
Bank Sta=4997.1,5001.8
Exp/Cntr=0.3,0.1

Type RM Length L Ch R = 1,10026,704,704,704
BEGIN DESCRIPTION:
Mapping XS 3615c40e
END DESCRIPTION:
XS GIS Cut Line= 4
      2638004.36      6960468.34      2636271.75      6960593.34
      2635941.89      6960687.09      2634893.28      6961575.97
#Sta/Elev= 30
  3266.6  485.55  3525.6  484.11  3595.8  481.85  3706.1  484.39  3826.4  482.36
  3846.5  484.55  4087.1  480.97  4307.7  480.82  4387.9  478.82  4468.1  479.38
  4484.0  477.71  4548.3  476.24  4568.3  474.44  4638.5  474.69  4688.6  473.02
  4740.3  474.43  4859.1  471.65  4989.4  472.03  5003.7  471.64  5006.6  469.86
  5007.1  469.36  5011.3  469.86  5024.9  471.37  5092.9  475.63  5165.6  475.82
  5207.2  478.58  5272.1  480.13  6020.9  483.95  6460.3  491.58  6721.3  494.45
#Mann=5,-1,0
  3266.6    0.05       0  4740.3    0.12       0  5006.6    0.07       0
  5011.3    0.12       0  5024.9    0.05       0
Bank Sta=5006.6,5011.3
Exp/Cntr=0.3,0.1

Type RM Length L Ch R = 1,9322,22,22,22
BEGIN DESCRIPTION:
Mapping XS 2368de48
END DESCRIPTION:
XS GIS Cut Line= 4
      2637518.29      6958902.35      2636285.64      6960030.84
      2635528.69      6960746.12      2634823.99      6961416.11
#Sta/Elev= 30
  3336.6  482.82  4547.3  483.32  4597.3  480.65  4646.6  481.21  4675.0  479.99
  4689.2  476.89  4710.1  478.52  4717.5  476.00  4724.3  477.35  4731.7  475.59
  4752.7  477.60  4760.1  475.09  4766.9  477.41  4774.3  475.32  4781.1  477.99
  4795.2  477.65  4802.6  474.60  4809.4  476.09  4852.0  473.52  4965.4  472.49
  4972.2  470.03  4979.6  472.09  4983.8  468.93  4984.5  468.43  4988.9  468.93
  4993.8  472.18  5106.6  471.30  5715.0  480.43  6401.1  483.56  7021.6  491.78
#Mann=3,-1,0
  3336.6    0.05       0  4983.8    0.03       0  4988.9    0.05       0
Bank Sta=4983.8,4988.9
Exp/Cntr=0.3,0.1

Type RM Length L Ch R = 1,9300,555,555,555
BEGIN DESCRIPTION:
Mapping XS c1fae4d4
END DESCRIPTION:
XS GIS Cut Line= 3
      2637098.16      6959187.07      2636264.81      6960020.42
      2634790.06      6961373.71
#Sta/Elev= 30
  3836.4  482.84  4356.9  485.46  4448.8  483.60  4470.0  485.53  4477.1  483.35
  4554.9  483.66  4675.1  478.20  4682.2  480.11  4689.2  477.45  4724.6  478.44
  4745.8  475.96  4752.9  478.86  4759.9  475.79  4767.0  479.36  4774.1  475.31
  4795.3  477.64  4802.4  474.98  4809.4  477.55  4830.7  474.15  4957.9  472.56
  4962.5  469.02  4963.1  468.52  4967.6  469.02  4972.1  471.90  4979.1  469.56
  4986.2  472.10  5149.0  471.55  5516.8  477.50  6429.9  483.18  7016.5  491.89
#Mann=3,-1,0
  3836.4    0.05       0  4962.5    0.03       0  4967.6    0.05       0
Bank Sta=4962.5,4967.6
Exp/Cntr=0.3,0.1

Type RM Length L Ch R = 1,8745,414,414,414
BEGIN DESCRIPTION:
Terry Creek Trib 2 17.0
END DESCRIPTION:
XS GIS Cut Line= 3
      2636225.96      6959461.03      2635826.00      6959811.00
      2634925.97      6961011.03
#Sta/Elev= 30
  4464.0  487.32  4548.9  483.98  4641.0  478.53  4726.4  477.19  4769.1  475.61
  4867.8  469.16  4998.6  469.60  5029.4  466.48  5030.0  465.98  5034.5  466.48
  5052.7  469.44  5102.7  471.17  5195.5  470.35  5223.6  471.99  5259.0  470.44
  5295.5  470.57  5317.3  471.87  5345.5  472.18  5373.6  474.20  5402.7  475.23
  5423.6  474.56  5445.5  475.69  5538.2  477.67  5673.6  479.36  5859.0  479.12
  5931.9  480.76  6131.9  482.23  6295.5  484.78  6381.9  484.90  6495.5  487.03
#Mann=3,-1,0
  4464.0    0.05       0  5029.4    0.04       0  5034.5    0.05       0
Bank Sta=5029.4,5034.5
Exp/Cntr=0.3,0.1

Type RM Length L Ch R = 1,8331,455,455,455
BEGIN DESCRIPTION:
Terry Creek Trib 2 16.0
END DESCRIPTION:
XS GIS Cut Line= 3
      2635926.01      6959511.00      2635526.00      6959561.00
      2635026.01      6960660.97
#Sta/Elev= 30
  4596.9  482.59  4707.8  478.47  4727.9  476.92  4795.9  475.78  4899.2  471.33
  4957.2  469.94  4997.5  466.36  5008.8  466.25  5019.4  463.32  5020.1  462.82
  5024.6  463.32  5031.9  464.39  5037.4  467.62  5044.0  468.15  5204.3  467.92
  5232.9  471.26  5246.1  471.43  5273.5  468.71  5307.6  468.27  5406.5  472.41
  5439.4  472.82  5501.4  471.19  5589.9  470.78  5670.1  473.23  5687.7  472.75
  5693.2  473.81  5716.2  474.67  5756.9  474.90  5845.8  478.64  6208.3  482.72
#Mann=5,-1,0
  4596.9    0.05       0  5019.4    0.04       0  5024.6    0.05       0
  5246.1    0.12       0  5501.4    0.05       0
Bank Sta=5019.4,5024.6
Exp/Cntr=0.3,0.1

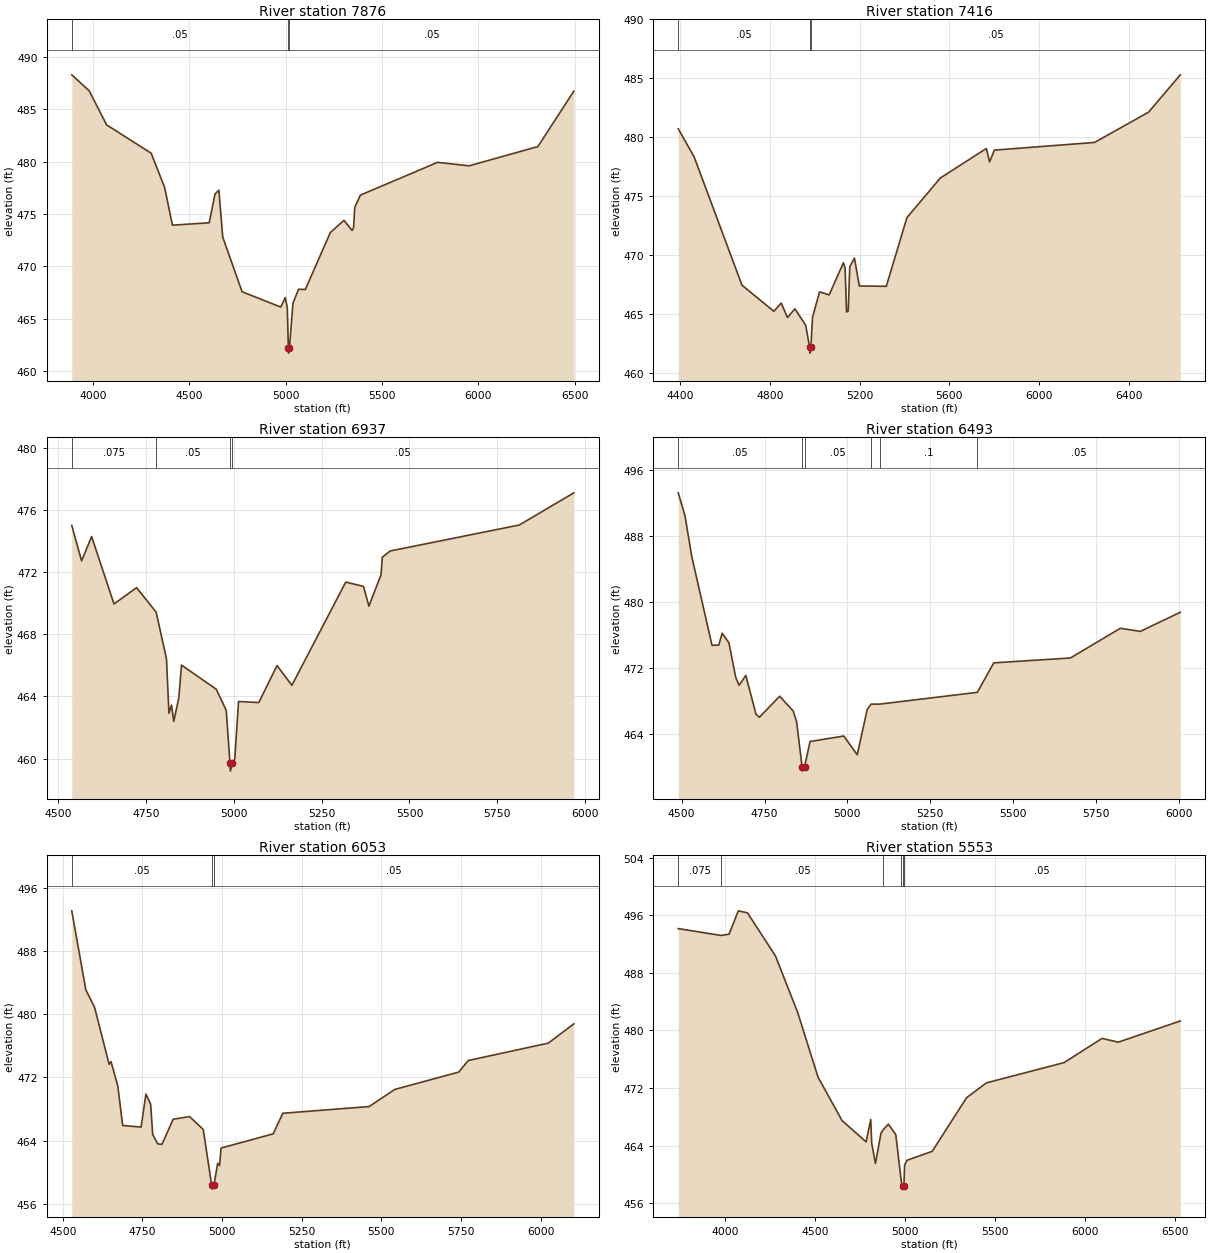
Type RM Length L Ch R = 1,7876,460,460,460
BEGIN DESCRIPTION:
Terry Creek Trib 2 15.0
END DESCRIPTION:
XS GIS Cut Line= 3
      2636325.96      6959361.00      2635226.00      6959261.00
      2634026.00      6960161.00
#Sta/Elev= 30
  3890.7  488.30  3981.0  486.78  4071.4  483.52  4302.4  480.82  4372.6  477.54
  4412.8  473.94  4603.6  474.17  4633.7  476.92  4653.8  477.28  4673.9  472.80
  4774.3  467.58  4975.1  466.12  4998.3  467.03  5008.7  466.09  5014.3  462.22
  5015.1  461.72  5019.9  462.22  5037.9  466.47  5067.1  467.82  5102.5  467.80
  5231.7  473.23  5302.5  474.40  5345.2  473.44  5352.5  473.69  5358.7  475.64
  5387.9  476.81  5787.9  479.94  5952.5  479.61  6308.7  481.45  6495.2  486.74
#Mann=3,-1,0
  3890.7    0.05       0  5014.3    0.04       0  5019.9    0.05       0
Bank Sta=5014.3,5019.9
Exp/Cntr=0.3,0.1

Type RM Length L Ch R = 1,7416,479,479,479
BEGIN DESCRIPTION:
Terry Creek Trib 2 14.0
END DESCRIPTION:
XS GIS Cut Line= 3
      2635675.97      6958960.99      2635076.00      6958861.00
      2633976.02      6960060.98
#Sta/Elev= 30
  4392.2  480.71  4463.1  478.32  4676.0  467.44  4818.0  465.22  4850.9  465.92
  4878.8  464.69  4911.7  465.43  4959.9  464.04  4977.3  462.17  4978.2  461.67
  4983.0  462.17  4990.3  464.70  5021.7  466.87  5064.3  466.61  5127.8  469.34
  5135.2  468.90  5142.0  465.16  5149.4  465.24  5156.1  469.00  5177.1  469.73
  5198.7  467.37  5318.9  467.34  5410.8  473.17  5559.4  476.53  5764.7  479.04
  5778.9  477.90  5800.5  478.90  6246.3  479.55  6486.8  482.12  6628.3  485.29
#Mann=3,-1,0
  4392.2    0.05       0  4977.3    0.03       0  4983.0    0.05       0
Bank Sta=4977.3,4983
Exp/Cntr=0.3,0.1

Type RM Length L Ch R = 1,6937,444,444,444
BEGIN DESCRIPTION:
Terry Creek Trib 2 13.0
END DESCRIPTION:
XS GIS Cut Line= 4
      2635176.01      6958110.98      2634876.00      6958461.00
      2634653.07      6958815.96      2634495.50      6959341.59
#Sta/Elev= 30
  4539.0  474.99  4567.0  472.71  4595.5  474.28  4659.2  469.94  4723.4  470.99
  4779.1  469.42  4808.5  466.42  4815.6  462.91  4822.7  463.44  4829.3  462.39
  4843.6  463.90  4851.3  466.01  4950.1  464.46  4978.6  463.10  4989.3  459.69
  4990.4  459.19  4996.4  459.69  5003.0  459.98  5013.6  463.67  5071.3  463.60
  5123.1  465.98  5165.5  464.71  5318.8  471.35  5369.3  471.07  5384.6  469.80
  5419.2  471.82  5422.8  472.95  5445.3  473.35  5812.7  475.02  5967.9  477.09
#Mann=4,-1,0
  4539.0   0.075       0  4779.1    0.05       0  4989.3    0.03       0
  4996.4    0.05       0
Bank Sta=4989.3,4996.4
Exp/Cntr=0.3,0.1

Type RM Length L Ch R = 1,6493,440,440,440
BEGIN DESCRIPTION:
Terry Creek Trib 2 12.0
END DESCRIPTION:
XS GIS Cut Line= 3
      2634425.99      6957960.96      2634526.00      6958461.00
      2634426.00      6959460.97
#Sta/Elev= 30
  4489.6  493.25  4510.0  490.47  4530.4  485.53  4591.6  474.78  4612.0  474.82
  4622.2  476.25  4642.6  475.08  4663.0  470.91  4673.2  469.94  4693.6  471.14
  4724.2  466.44  4734.4  466.07  4795.6  468.62  4836.4  466.83  4846.6  465.56
  4863.4  460.05  4864.5  459.55  4870.6  460.05  4887.4  463.14  4989.3  463.80
  5029.7  461.53  5059.8  467.02  5071.7  467.66  5098.6  467.67  5392.0  469.09
  5441.7  472.66  5672.9  473.25  5823.6  476.85  5883.9  476.47  6004.5  478.79
#Mann=6,-1,0
  4489.6    0.05       0  4863.4    0.03       0  4870.6    0.05       0
  5071.7   0.075       0  5098.6     0.1       0  5392.0    0.05       0
Bank Sta=4863.4,4870.6
Exp/Cntr=0.3,0.1

Type RM Length L Ch R = 1,6053,500,500,500
BEGIN DESCRIPTION:
Terry Creek Trib 2 11.0
END DESCRIPTION:
XS GIS Cut Line= 3
      2634376.00      6957960.99      2634126.00      6958361.00
      2634226.00      6959460.96
#Sta/Elev= 30
  4528.3  493.13  4572.5  483.10  4599.7  480.92  4645.6  473.67  4651.5  474.01
  4672.8  470.93  4688.1  465.91  4745.9  465.71  4761.2  469.90  4775.9  468.61
  4782.4  464.78  4797.8  463.59  4811.3  463.51  4846.7  466.70  4898.0  467.04
  4941.0  465.41  4967.5  458.34  4968.6  457.84  4974.8  458.34  4986.4  461.13
  4992.3  460.83  4997.1  463.05  5160.7  464.85  5190.8  467.46  5461.9  468.31
  5542.2  470.48  5743.1  472.68  5773.2  474.15  6024.2  476.35  6104.5  478.80
#Mann=3,-1,0
  4528.3    0.05       0  4967.5    0.03       0  4974.8    0.05       0
Bank Sta=4967.5,4974.8
Exp/Cntr=0.3,0.1

Type RM Length L Ch R = 1,5553,555,555,555
BEGIN DESCRIPTION:
Terry Creek Trib 2 10.0
END DESCRIPTION:
XS GIS Cut Line= 3
      2633922.58      6957136.73      2633626.00      6958361.00
      2633501.57      6959884.15
#Sta/Elev= 30
  3740.3  494.14  3978.9  493.19  4022.5  493.37  4073.9  496.61  4124.8  496.33
  4279.7  490.37  4403.2  482.53  4516.5  473.53  4650.1  467.49  4783.9  464.54
  4809.2  467.66  4814.8  464.33  4835.3  461.54  4866.2  465.76  4879.9  466.26
  4907.4  467.00  4948.5  465.53  4980.0  458.82  4986.0  458.48  4987.2  457.98
  4993.3  458.48  4997.4  461.31  5010.0  461.98  5150.5  463.22  5341.1  470.66
  5451.5  472.73  5882.9  475.54  6093.6  478.90  6183.9  478.38  6528.2  481.32
#Mann=6,-1,0
  3740.3   0.075       0  3978.9    0.05       0  4879.9   0.075       0
  4980.0    0.05       0  4986.0    0.05       0  4993.3    0.05       0
Bank Sta=4986,4993.3
Exp/Cntr=0.3,0.1

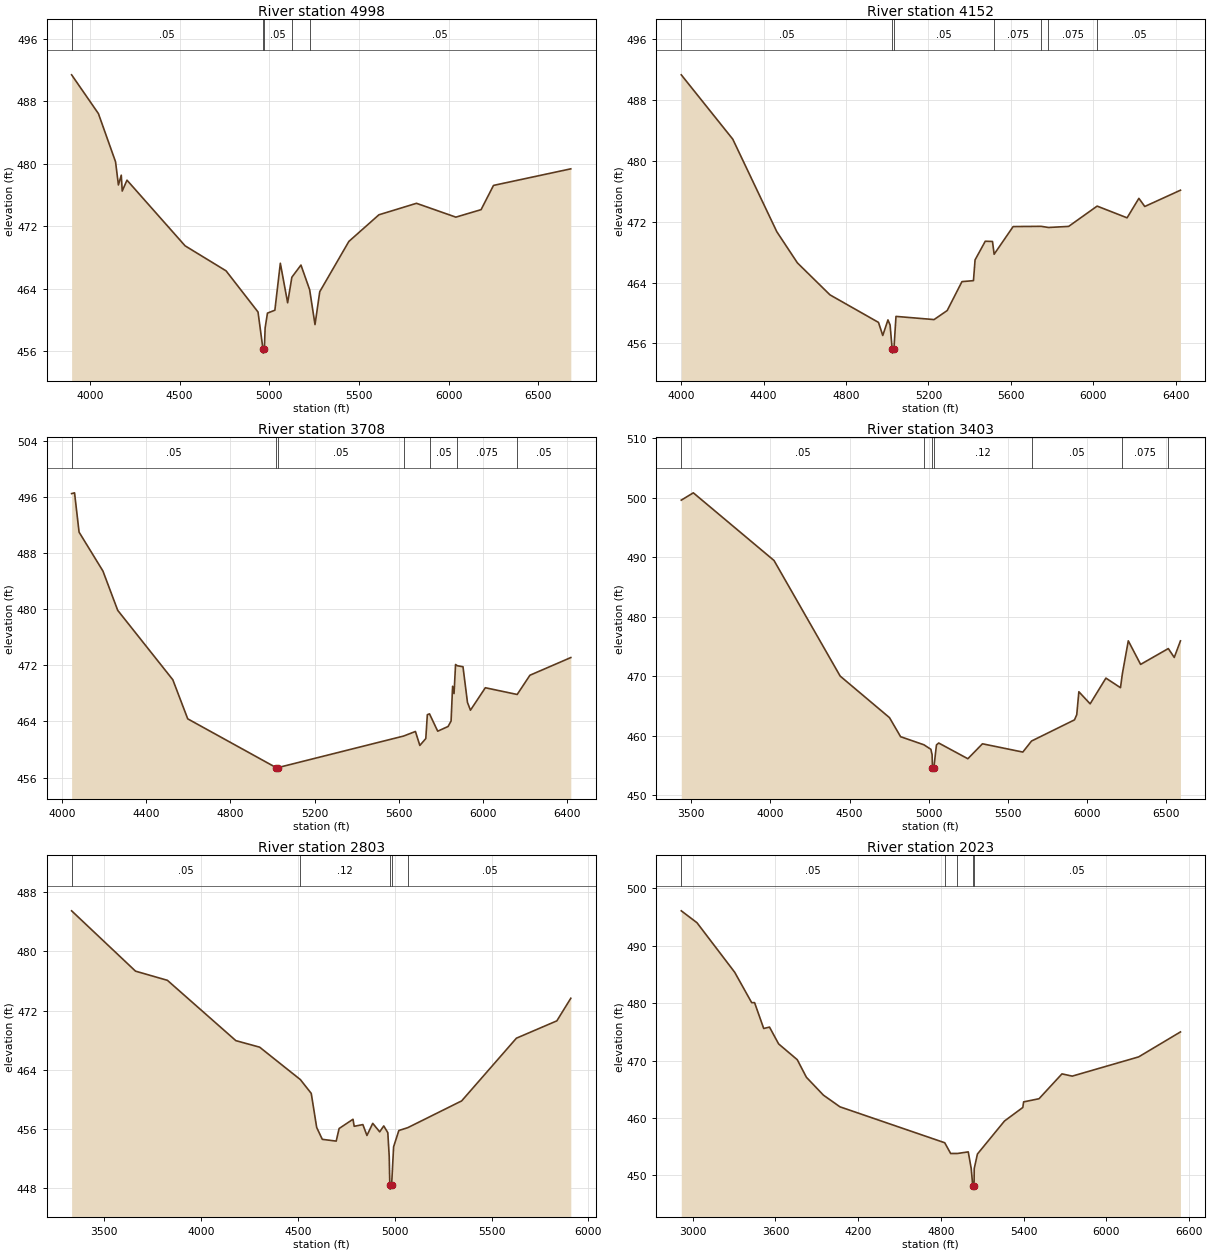
Type RM Length L Ch R = 1,4998,846,846,846
BEGIN DESCRIPTION:
Terry Creek Trib 2 9.0
END DESCRIPTION:
XS GIS Cut Line= 3
      2633597.05      6957062.96      2633251.34      6958120.98
      2632941.66      6959762.65
#Sta/Elev= 30
  3897.7  491.40  4047.1  486.44  4142.7  480.27  4158.6  477.31  4174.6  478.56
  4179.9  476.53  4206.5  477.92  4530.5  469.52  4758.9  466.32  4937.2  461.05
  4964.9  456.29  4966.1  455.79  4972.5  456.29  4976.8  459.01  4989.8  460.91
  5031.1  461.28  5061.6  467.29  5102.4  462.23  5125.8  465.50  5176.6  467.06
  5225.0  463.91  5255.0  459.44  5281.4  463.65  5443.7  470.08  5611.2  473.49
  5820.8  474.96  6040.6  473.19  6181.1  474.15  6250.3  477.25  6681.4  479.37
#Mann=5,-1,0
  3897.7    0.05       0  4964.9    0.03       0  4972.5    0.05       0
  5125.8   0.075       0  5225.0    0.05       0
Bank Sta=4964.9,4972.5
Exp/Cntr=0.3,0.1

Type RM Length L Ch R = 1,4152,444,444,444
BEGIN DESCRIPTION:
Terry Creek Trib 2 7.0
END DESCRIPTION:
XS GIS Cut Line= 3
      2633326.02      6957210.99      2632526.00      6957811.00
      2631613.57      6958903.20
#Sta/Elev= 30
  4000.2  491.31  4250.2  482.85  4463.8  470.69  4563.8  466.59  4722.1  462.38
  4957.5  458.76  4978.3  457.04  5003.5  459.09  5013.9  458.41  5024.1  455.22
  5025.3  454.72  5032.4  455.22  5042.5  459.55  5227.3  459.13  5291.1  460.32
  5362.7  464.12  5418.6  464.25  5426.4  466.98  5475.9  469.43  5511.0  469.40
  5518.9  467.72  5611.2  471.36  5747.7  471.39  5782.6  471.24  5880.6  471.38
  6018.9  474.05  6164.3  472.51  6221.6  475.07  6250.2  474.00  6423.4  476.14
#Mann=7,-1,0
  4000.2    0.05       0  5024.1    0.03       0  5032.4    0.05       0
  5518.9   0.075       0  5747.7     0.1       0  5782.6   0.075       0
  6018.9    0.05       0
Bank Sta=5024.1,5032.4
Exp/Cntr=0.3,0.1

Type RM Length L Ch R = 1,3708,305,305,305
BEGIN DESCRIPTION:
Terry Creek Trib 2 6.0
END DESCRIPTION:
XS GIS Cut Line= 3
      2632825.97      6956861.03      2632176.00      6957561.00
      2631192.51      6958582.08
#Sta/Elev= 30
  4045.0  496.46  4058.9  496.57  4080.4  490.97  4193.8  485.43  4264.1  479.83
  4526.0  469.94  4596.9  464.37  5017.2  457.42  5018.5  456.92  5025.6  457.42
  5623.4  461.92  5679.3  462.57  5700.3  460.58  5728.6  461.56  5735.9  464.96
  5746.2  465.08  5785.2  462.61  5834.6  463.28  5848.8  464.06  5856.0  469.01
  5862.9  467.97  5870.1  472.11  5879.0  471.93  5905.4  471.79  5926.7  466.71
  5940.9  465.60  6011.6  468.80  6163.0  467.84  6223.6  470.58  6417.9  473.10
#Mann=7,-1,0
  4045.0    0.05       0  5017.2    0.03       0  5025.6    0.05       0
  5623.4    0.12       0  5746.2    0.05       0  5879.0   0.075       0
  6163.0    0.05       0
Bank Sta=5017.2,5025.6
Exp/Cntr=0.3,0.1

Type RM Length L Ch R = 1,3403,600,600,600
BEGIN DESCRIPTION:
Terry Creek Trib 2 5.0
END DESCRIPTION:
XS GIS Cut Line= 3
      2633110.95      6956338.12      2631942.68      6957377.64
      2630741.16      6958421.46
#Sta/Elev= 30
  3436.2  499.57  3512.3  500.80  4022.4  489.44  4440.5  470.03  4752.4  463.05
  4822.6  459.85  4970.3  458.49  5014.1  457.73  5021.7  456.82  5024.2  454.57
  5025.4  454.07  5032.6  454.57  5049.2  458.47  5063.5  458.79  5247.7  456.15
  5340.0  458.66  5595.2  457.27  5650.1  459.12  5921.9  462.68  5936.1  463.56
  5949.4  467.40  6020.7  465.37  6120.4  469.69  6212.5  468.08  6224.5  470.43
  6261.9  475.95  6339.7  471.99  6514.9  474.65  6552.4  473.16  6591.6  475.94
#Mann=7,-1,0
  3436.2    0.05       0  4970.3    0.12       0  5024.2    0.07       0
  5032.6    0.12       0  5650.1    0.05       0  6224.5   0.075       0
  6514.9    0.05       0
Bank Sta=5024.2,5032.6
Exp/Cntr=0.3,0.1

Type RM Length L Ch R = 1,2803,780,780,780
BEGIN DESCRIPTION:
Terry Creek Trib 2 4.0
END DESCRIPTION:
XS GIS Cut Line= 3
      2632316.66      6955873.74      2631376.00      6957261.00
      2630876.00      6958011.00
#Sta/Elev= 30
  3331.8  485.46  3661.7  477.32  3826.4  476.08  4179.8  467.94  4302.6  467.06
  4513.0  462.68  4569.1  460.82  4597.1  456.23  4626.1  454.62  4698.0  454.38
  4712.9  456.08  4784.8  457.33  4790.8  456.38  4835.7  456.61  4856.7  455.14
  4886.6  456.78  4922.5  455.63  4943.5  456.43  4964.5  455.52  4971.7  452.30
  4974.9  448.40  4976.2  447.90  4983.9  448.40  4994.4  453.62  5021.4  455.81
  5067.9  456.20  5345.9  459.81  5628.4  468.27  5837.2  470.61  5909.3  473.66
#Mann=5,-1,0
  3331.8    0.05       0  4513.0    0.12       0  4974.9    0.07       0
  4983.9    0.12       0  5067.9    0.05       0
Bank Sta=4974.9,4983.9
Exp/Cntr=0.3,0.1

Type RM Length L Ch R = 1,2023,219,219,219
BEGIN DESCRIPTION:
Terry Creek Trib 2 3.0
END DESCRIPTION:
XS GIS Cut Line= 3
      2632585.77      6955582.93      2630849.25      6956734.41
      2630077.09      6958065.56
#Sta/Elev= 30
  2916.4  496.10  3030.3  494.03  3304.0  485.40  3427.3  480.10  3448.4  480.10
  3514.6  475.60  3556.7  475.84  3622.9  472.91  3758.2  470.16  3824.4  467.10
  3947.7  463.99  4068.0  461.95  4828.3  455.69  4871.1  453.82  4920.6  453.82
  4999.0  454.10  5020.7  451.16  5031.8  448.11  5033.2  447.61  5041.0  448.11
  5042.3  451.18  5065.4  453.72  5262.0  459.48  5395.0  461.84  5400.8  462.81
  5512.6  463.36  5679.0  467.69  5753.6  467.30  6235.5  470.65  6538.9  475.00
#Mann=5,-1,0
  2916.4    0.05       0  4828.3    0.12       0  4920.6    0.05       0
  5031.8    0.03       0  5041.0    0.05       0
Bank Sta=5031.8,5041
Exp/Cntr=0.3,0.1

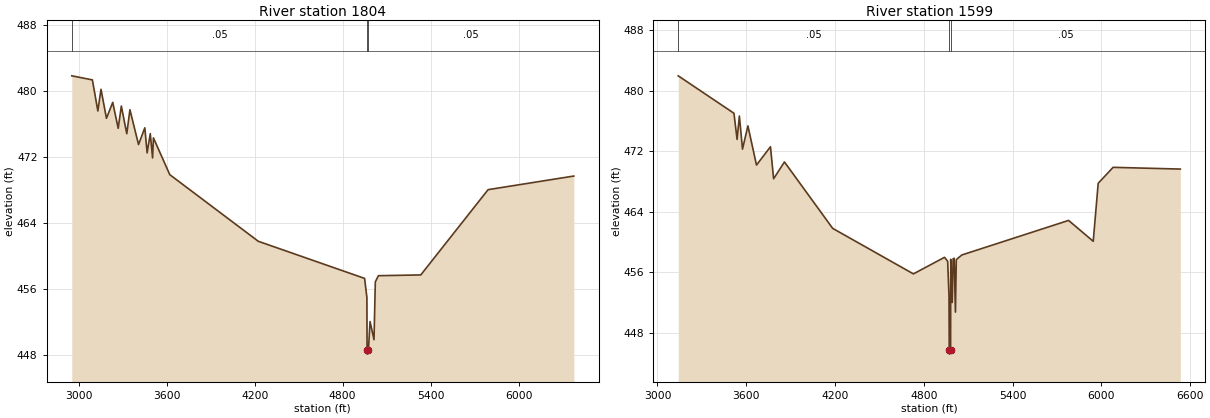
Type RM Length L Ch R = 1,1804,205,205,205
BEGIN DESCRIPTION:
Mapping XS d60735a0
END DESCRIPTION:
XS GIS Cut Line= 4
      2632493.52      6955525.49      2630733.08      6956556.75
      2630071.62      6956994.25      2630222.51      6957566.59
#Sta/Elev= 30
  2951.8  481.79  3092.5  481.30  3129.7  477.53  3151.2  480.16  3188.4  476.64
  3231.3  478.57  3268.5  475.43  3290.0  478.13  3327.1  474.77  3348.6  477.68
  3407.3  473.46  3450.2  475.49  3465.9  472.45  3487.4  474.78  3503.1  471.84
  3508.9  474.27  3620.4  469.81  4224.3  461.73  4949.6  457.23  4965.2  454.92
  4966.4  448.55  4967.7  448.05  4975.6  448.55  4986.7  452.00  5013.7  449.80
  5022.7  456.81  5043.8  457.56  5332.7  457.65  5792.1  467.99  6377.0  469.64
#Mann=3,-1,0
  2951.8    0.05       0  4966.4    0.05       0  4975.6    0.05       0
Bank Sta=4966.4,4975.6
Exp/Cntr=0.3,0.1

Type RM Length L Ch R = 1,1599,0,0,0
BEGIN DESCRIPTION:
Mapping XS 5fbb3b7c
END DESCRIPTION:
XS GIS Cut Line= 4
      2632160.16      6955436.96      2630592.45      6956410.92
      2629951.83      6956780.71      2630175.67      6957556.35
#Sta/Elev= 30
  3140.2  481.98  3516.7  477.03  3537.9  473.57  3553.3  476.67  3574.5  472.29
  3611.1  475.36  3669.0  470.18  3763.4  472.60  3784.7  468.37  3857.9  470.59
  4183.8  461.81  4729.3  455.79  4939.5  457.98  4960.8  457.46  4969.9  452.80
  4971.5  445.68  4972.8  445.18  4980.8  445.68  4981.2  457.72  4991.7  452.01
  4997.5  457.78  5004.8  457.86  5013.3  450.74  5019.1  457.68  5056.4  458.29
  5777.9  462.86  5944.4  460.10  5977.9  467.77  6078.8  469.88  6532.8  469.65
#Mann=3,-1,0
  3140.2    0.05       0  4971.5    0.05       0  4980.8    0.05       0
Bank Sta=4971.5,4980.8
Exp/Cntr=0.3,0.1

Chan Stop Cuts=-1