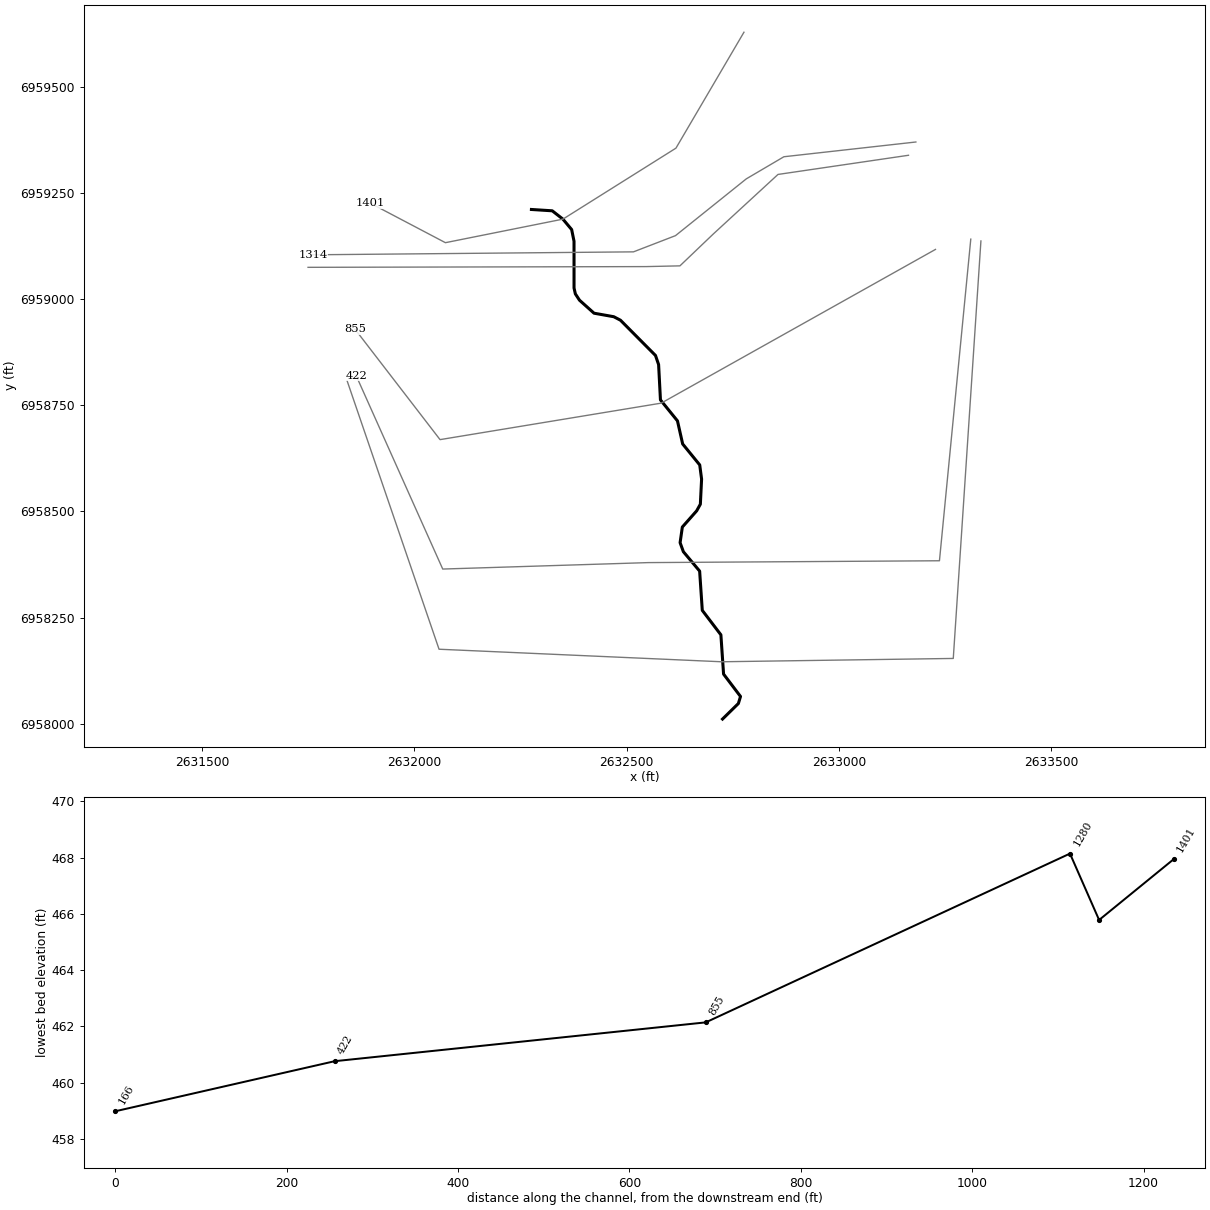
--- Terry Creek Trib 2_1.prj (project) ---

Proj Title=Terry Creek Trib 2_1 Base Level Engineering
Current Plan=p01
Default Exp/Contr=0.3,0.1
English Units
Geom File=g01
Flow File=f01
Plan File=p01
BEGIN DESCRIPTION:
Terry Creek Trib 2_1
END DESCRIPTION:

--- Terry Creek Trib 2_1.p01 (plan) ---

Plan Title=Multiple Run
Short Identifier=Multiple
Geom File=g01
Flow File=f01
Subcritical Flow
K Sum by GR= 0
Std Step Tol= 0.01
Critical Tol= 0.01
Num of Std Step Trials= 20
Max Error Tol= 0.3
Flow Tol Ratio= 0.001
Split Flow NTrial= 30
Split Flow Tol= 0.02
Split Flow Ratio= 0.02
Log Output Level= 0
Friction Slope Method= 1
Unsteady Friction Slope Method= 2
Unsteady Bridges Friction Slope Method= 1
Parabolic Critical Depth
Global Vel Dist=  1 , 1 , 1
Global Log Level= 0
CheckData=True
Encroach Param= -1, 0, 0, 0
BEGIN DESCRIPTION:
Multiple Run
END DESCRIPTION:

--- Terry Creek Trib 2_1.f01 (steady flow) ---

Flow Title=Multiple
Number of Profiles=7
Profile Names=10-year,25-year,50-year,1pct_min,100-year,1pct_plu,500-year
River Rch & RM= Terry Creek Trib,Reach-1,1401
     228     286     330     190     379     756     497
Boundary for River Rch & Prof#=Terry Creek Trib,Reach-1,1
Up Type=0
Dn Type=3
Dn Slope=0.005
Boundary for River Rch & Prof#=Terry Creek Trib,Reach-1,2
Up Type=0
Dn Type=3
Dn Slope=0.005
Boundary for River Rch & Prof#=Terry Creek Trib,Reach-1,3
Up Type=0
Dn Type=3
Dn Slope=0.005
Boundary for River Rch & Prof#=Terry Creek Trib,Reach-1,4
Up Type=0
Dn Type=3
Dn Slope=0.005
Boundary for River Rch & Prof#=Terry Creek Trib,Reach-1,5
Up Type=0
Dn Type=3
Dn Slope=0.005
Boundary for River Rch & Prof#=Terry Creek Trib,Reach-1,6
Up Type=0
Dn Type=3
Dn Slope=0.005
Boundary for River Rch & Prof#=Terry Creek Trib,Reach-1,7
Up Type=0
Dn Type=3
Dn Slope=0.005

--- Terry Creek Trib 2_1.g01 (geometry) ---

Geom Title=Existing Conditions

River Reach=Terry Creek Trib,Reach-1
Reach XY= 30
      2632276.00      6959211.00      2632325.02      6959207.88
      2632350.15      6959188.24      2632370.73      6959163.69
      2632376.30      6959136.18      2632376.34      6959026.04
      2632379.45      6959012.25      2632389.23      6958997.33
      2632423.43      6958966.74      2632469.92      6958958.45
      2632485.68      6958950.22      2632568.15      6958867.19
      2632575.48      6958845.79      2632579.83      6958762.59
      2632619.89      6958713.18      2632632.12      6958658.82
      2632672.33      6958609.42      2632676.71      6958576.06
      2632673.81      6958516.97      2632665.13      6958501.35
      2632631.38      6958463.18      2632626.09      6958426.39
      2632633.81      6958405.08      2632672.11      6958359.42
      2632678.35      6958266.97      2632722.15      6958209.40
      2632728.46      6958116.88      2632768.37      6958064.18
      2632763.32      6958047.59      2632726.00      6958011.00

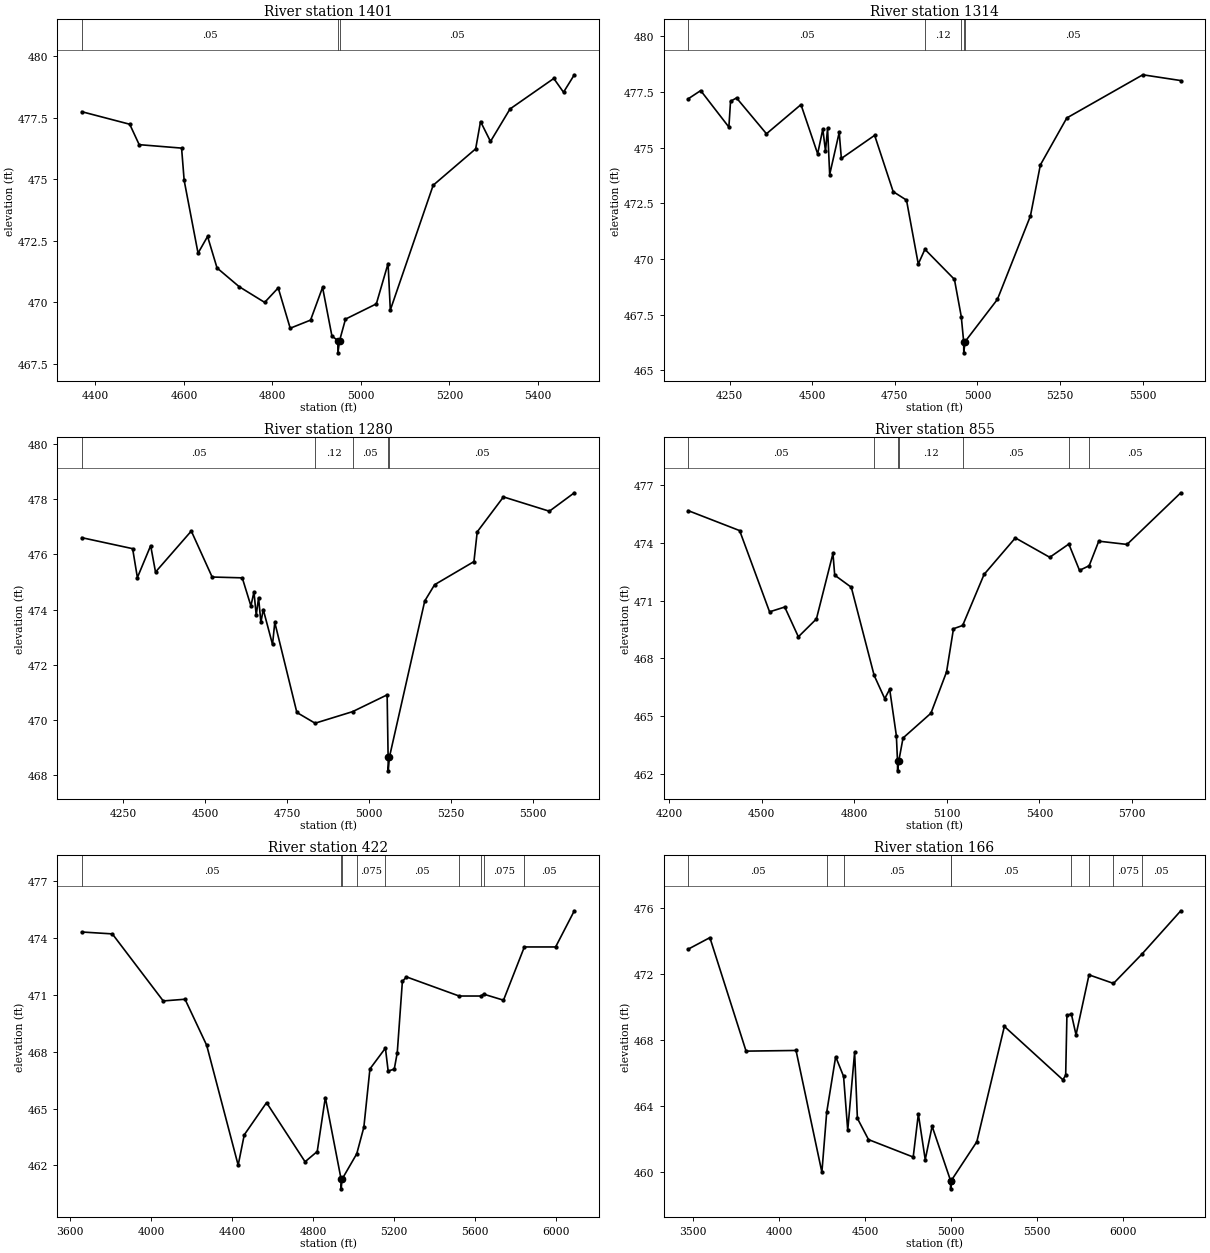
Type RM Length L Ch R = 1,1401,87,87,87
BEGIN DESCRIPTION:
Mapping XS 6a71e795
END DESCRIPTION:
XS GIS Cut Line= 5
      2632776.45      6959628.40      2632616.33      6959355.44
      2632350.15      6959188.24      2632073.46      6959132.80
      2631896.52      6959225.84
#Sta/Elev= 30
  4369.2  477.74  4477.6  477.23  4499.0  476.40  4594.8  476.26  4600.6  474.95
  4632.0  471.99  4653.5  472.67  4674.9  471.39  4724.8  470.63  4782.5  469.99
  4813.1  470.58  4840.2  468.94  4886.2  469.27  4913.3  470.60  4934.5  468.62
  4947.8  468.44  4948.0  467.94  4951.8  468.44  4965.1  469.31  5034.8  469.93
  5061.3  471.57  5066.4  469.68  5163.2  474.75  5259.2  476.23  5270.2  477.34
  5292.7  476.53  5336.8  477.85  5435.7  479.09  5457.7  478.53  5482.1  479.24
#Mann=3,-1,0
  4369.2    0.05       0  4947.8    0.03       0  4951.8    0.05       0
Bank Sta=4947.8,4951.8
Exp/Cntr=0.3,0.1

Type RM Length L Ch R = 1,1314,34,34,34
BEGIN DESCRIPTION:
Mapping XS b514daa7
END DESCRIPTION:
XS GIS Cut Line= 6
      2633181.30      6959369.90      2632870.51      6959335.17
      2632781.97      6959283.09      2632615.30      6959149.41
      2632516.34      6959111.21      2631761.15      6959104.27
#Sta/Elev= 30
  4124.8  477.19  4162.6  477.56  4247.9  475.92  4252.9  477.08  4271.0  477.23
  4361.6  475.62  4466.0  476.93  4516.5  474.72  4532.1  475.83  4540.2  474.84
  4546.5  475.86  4552.9  473.79  4581.7  475.68  4588.2  474.51  4688.9  475.55
  4745.0  473.02  4785.3  472.64  4820.9  469.77  4841.0  470.43  4930.3  469.08
  4951.0  467.41  4958.3  466.28  4958.6  465.78  4962.3  466.28  5060.3  468.18
  5160.3  471.93  5190.3  474.22  5270.3  476.33  5500.3  478.27  5615.2  478.01
#Mann=5,-1,0
  4124.8    0.05       0  4841.0    0.12       0  4951.0    0.05       0
  4958.3    0.03       0  4962.3    0.05       0
Bank Sta=4958.3,4962.3
Exp/Cntr=0.3,0.1

Type RM Length L Ch R = 1,1280,425,425,425
BEGIN DESCRIPTION:
Mapping XS c3d587a3
END DESCRIPTION:
XS GIS Cut Line= 6
      2633163.93      6959338.65      2632856.62      6959293.50
      2632703.84      6959152.88      2632625.72      6959078.23
      2632545.85      6959076.49      2631749.94      6959074.76
#Sta/Elev= 30
  4123.8  476.61  4279.0  476.21  4293.5  475.16  4334.0  476.32  4348.8  475.36
  4457.9  476.85  4521.5  475.18  4613.3  475.15  4639.7  474.13  4649.0  474.64
  4655.9  473.79  4663.1  474.43  4670.1  473.53  4677.3  474.00  4705.6  472.73
  4712.5  473.53  4779.8  470.26  4835.4  469.87  4949.7  470.29  5055.1  470.90
  5058.1  468.64  5058.4  468.14  5062.1  468.64  5169.8  474.31  5199.8  474.90
  5319.8  475.74  5329.8  476.82  5409.8  478.09  5549.8  477.57  5625.9  478.24
#Mann=5,-1,0
  4123.8    0.05       0  4835.4    0.12       0  4949.7    0.05       0
  5058.1    0.03       0  5062.1    0.05       0
Bank Sta=5058.1,5062.1
Exp/Cntr=0.3,0.1

Type RM Length L Ch R = 1,855,433,433,433
BEGIN DESCRIPTION:
Mapping XS 3ab88650
END DESCRIPTION:
XS GIS Cut Line= 4
      2633227.43      6959116.93      2632581.62      6958754.96
      2632060.79      6958669.03      2631860.62      6958928.99
#Sta/Elev= 30
  4261.8  475.69  4428.5  474.65  4525.5  470.42  4574.6  470.67  4618.8  469.12
  4677.3  470.05  4730.9  473.46  4736.6  472.33  4790.3  471.70  4864.4  467.11
  4898.7  465.90  4914.7  466.39  4936.4  463.97  4940.1  462.64  4940.3  462.14
  4944.1  462.64  4958.0  463.85  5048.4  465.14  5099.0  467.29  5121.5  469.54
  5151.2  469.71  5220.7  472.37  5322.0  474.27  5433.5  473.26  5495.3  473.95
  5529.9  472.58  5561.2  472.82  5592.3  474.10  5683.9  473.93  5858.1  476.62
#Mann=7,-1,0
  4261.8    0.05       0  4864.4    0.12       0  4940.1    0.07       0
  4944.1    0.12       0  5151.2    0.05       0  5495.3   0.075       0
  5561.2    0.05       0
Bank Sta=4940.1,4944.1
Exp/Cntr=0.3,0.1

Type RM Length L Ch R = 1,422,256,256,256
BEGIN DESCRIPTION:
Mapping XS 509ad666
END DESCRIPTION:
XS GIS Cut Line= 5
      2633310.61      6959141.17      2633236.83      6958383.78
      2632551.06      6958379.44      2632067.12      6958364.25
      2631863.14      6958819.95
#Sta/Elev= 30
  3658.8  474.32  3809.7  474.22  4060.9  470.68  4168.4  470.77  4275.2  468.34
  4430.6  462.01  4460.6  463.61  4570.6  465.31  4760.6  462.19  4820.6  462.73
  4860.6  465.58  4938.6  461.26  4938.9  460.76  4942.6  461.26  5015.6  462.61
  5050.6  464.01  5080.6  467.09  5157.0  468.19  5170.6  466.98  5200.7  467.08
  5215.5  467.95  5240.7  471.71  5260.7  471.95  5520.6  470.94  5628.1  470.94
  5641.2  471.04  5739.6  470.72  5842.5  473.53  5996.7  473.53  6089.0  475.44
#Mann=9,-1,0
  3658.8    0.05       0  4938.6    0.05       0  4942.6    0.05       0
  5015.6   0.075       0  5157.0    0.05       0  5520.6   0.075       0
  5628.1    0.05       0  5641.2   0.075       0  5842.5    0.05       0
Bank Sta=4938.6,4942.6
Exp/Cntr=0.3,0.1

Type RM Length L Ch R = 1,166,0,0,0
BEGIN DESCRIPTION:
Terry Creek Trib 2_1 1.0
END DESCRIPTION:
XS GIS Cut Line= 5
      2633334.49      6959136.86      2633269.38      6958153.75
      2632723.73      6958145.91      2632058.44      6958175.45
      2631841.95      6958807.59
#Sta/Elev= 30
  3471.2  473.53  3597.3  474.23  3807.8  467.34  4098.4  467.38  4248.8  459.99
  4276.7  463.62  4328.9  467.00  4374.9  465.81  4399.1  462.54  4439.2  467.27
  4455.3  463.26  4519.9  461.97  4779.9  460.91  4809.9  463.52  4849.9  460.75
  4889.9  462.78  4997.2  459.48  4997.5  458.98  5001.2  459.48  5150.0  461.84
  5310.2  468.84  5650.5  465.60  5666.8  465.88  5674.0  469.52  5699.9  469.59
  5727.0  468.33  5802.5  471.97  5944.9  471.45  6110.3  473.23  6336.3  475.86
#Mann=9,-1,0
  3471.2    0.05       0  4276.7   0.075       0  4374.9    0.05       0
  4997.2    0.05       0  5001.2    0.05       0  5699.9   0.075       0
  5802.5     0.1       0  5944.9   0.075       0  6110.3    0.05       0
Bank Sta=4997.2,5001.2
Exp/Cntr=0.3,0.1

Chan Stop Cuts=-1