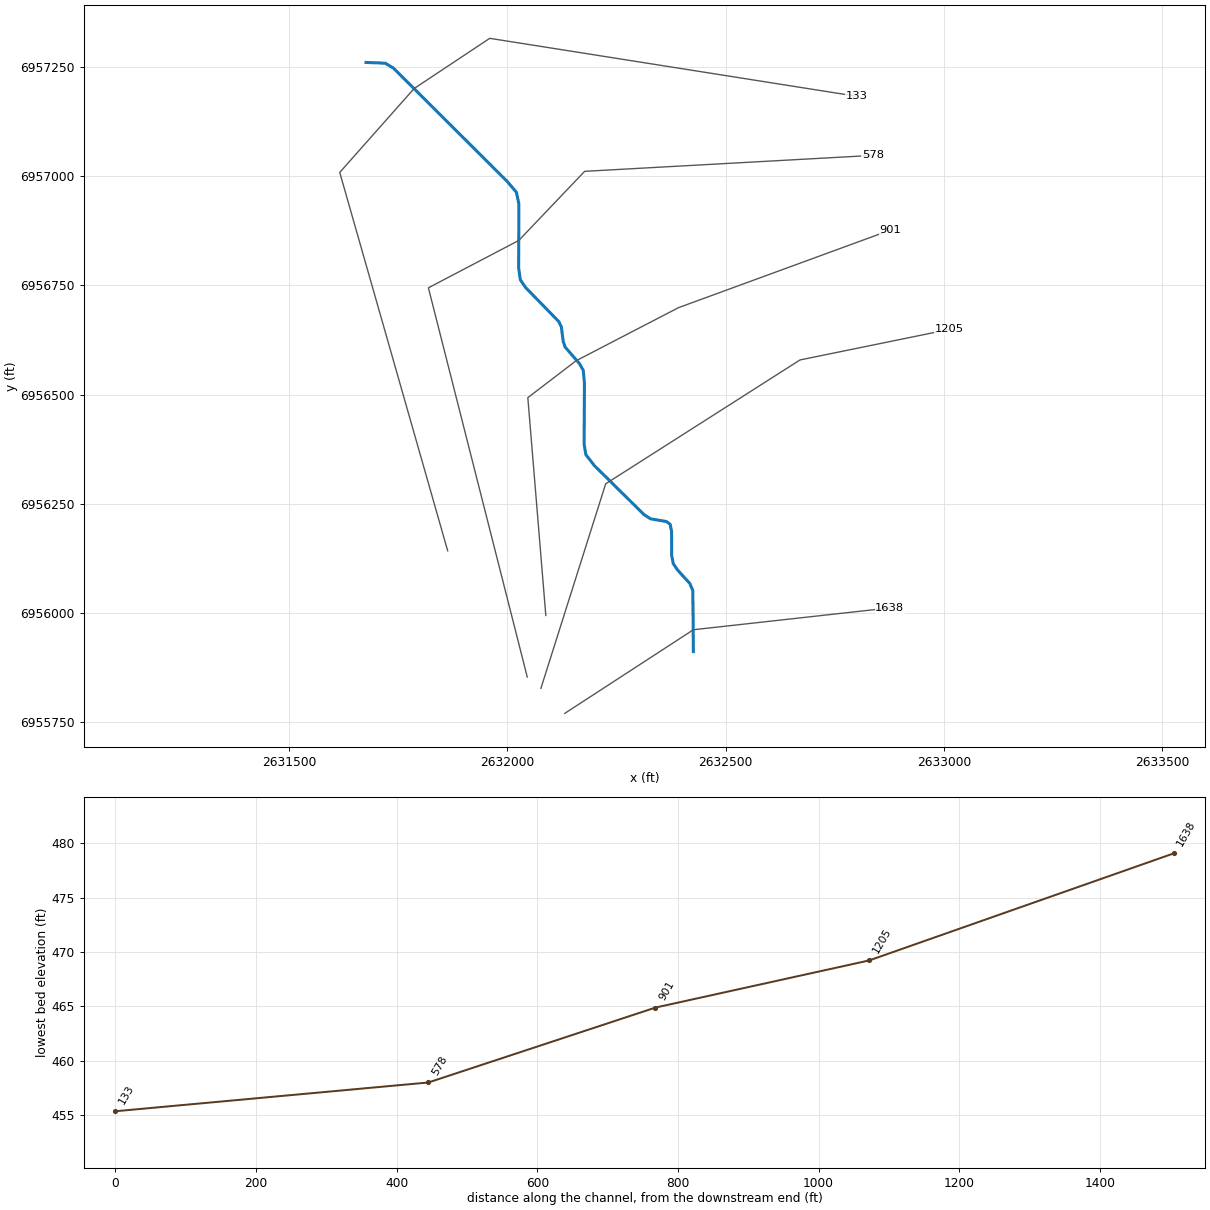
--- Terry Creek Trib 2_2.prj (project) ---

Proj Title=Terry Creek Trib 2_2 Base Level Engineering
Current Plan=p01
Default Exp/Contr=0.3,0.1
English Units
Geom File=g01
Flow File=f01
Plan File=p01
BEGIN DESCRIPTION:
Terry Creek Trib 2_2
END DESCRIPTION:

--- Terry Creek Trib 2_2.p01 (plan) ---

Plan Title=Multiple Run
Short Identifier=Multiple
Geom File=g01
Flow File=f01
Subcritical Flow
K Sum by GR= 0
Std Step Tol= 0.01
Critical Tol= 0.01
Num of Std Step Trials= 20
Max Error Tol= 0.3
Flow Tol Ratio= 0.001
Split Flow NTrial= 30
Split Flow Tol= 0.02
Split Flow Ratio= 0.02
Log Output Level= 0
Friction Slope Method= 1
Unsteady Friction Slope Method= 2
Unsteady Bridges Friction Slope Method= 1
Parabolic Critical Depth
Global Vel Dist=  1 , 1 , 1
Global Log Level= 0
CheckData=True
Encroach Param= -1, 0, 0, 0
BEGIN DESCRIPTION:
Multiple Run
END DESCRIPTION:

--- Terry Creek Trib 2_2.f01 (steady flow) ---

Flow Title=Multiple
Number of Profiles=7
Profile Names=10-year,25-year,50-year,1pct_min,100-year,1pct_plu,500-year
River Rch & RM= Terry Creek Trib,Reach-1,1638
      94     111     123      68     136     271     165
Boundary for River Rch & Prof#=Terry Creek Trib,Reach-1,1
Up Type=0
Dn Type=3
Dn Slope=0.005
Boundary for River Rch & Prof#=Terry Creek Trib,Reach-1,2
Up Type=0
Dn Type=3
Dn Slope=0.005
Boundary for River Rch & Prof#=Terry Creek Trib,Reach-1,3
Up Type=0
Dn Type=3
Dn Slope=0.005
Boundary for River Rch & Prof#=Terry Creek Trib,Reach-1,4
Up Type=0
Dn Type=3
Dn Slope=0.005
Boundary for River Rch & Prof#=Terry Creek Trib,Reach-1,5
Up Type=0
Dn Type=3
Dn Slope=0.005
Boundary for River Rch & Prof#=Terry Creek Trib,Reach-1,6
Up Type=0
Dn Type=3
Dn Slope=0.005
Boundary for River Rch & Prof#=Terry Creek Trib,Reach-1,7
Up Type=0
Dn Type=3
Dn Slope=0.005

--- Terry Creek Trib 2_2.g01 (geometry) ---

Geom Title=Existing Conditions

River Reach=Terry Creek Trib,Reach-1
Reach XY= 30
      2632426.00      6955911.00      2632424.83      6956050.52
      2632417.88      6956067.07      2632389.83      6956097.90
      2632379.89      6956112.67      2632376.31      6956131.26
      2632376.13      6956186.12      2632372.84      6956202.66
      2632364.26      6956209.00      2632328.08      6956215.15
      2632313.05      6956224.74      2632198.86      6956337.47
      2632179.54      6956362.46      2632175.71      6956385.88
      2632176.43      6956526.18      2632173.76      6956555.07
      2632165.21      6956570.67      2632132.14      6956608.83
      2632127.72      6956621.71      2632123.50      6956654.96
      2632117.84      6956667.05      2632042.46      6956744.25
      2632029.55      6956762.47      2632025.57      6956790.82
      2632026.29      6956936.12      2632020.54      6956963.45
      2631999.83      6956987.87      2631739.27      6957247.53
      2631719.86      6957259.32      2631676.00      6957261.00

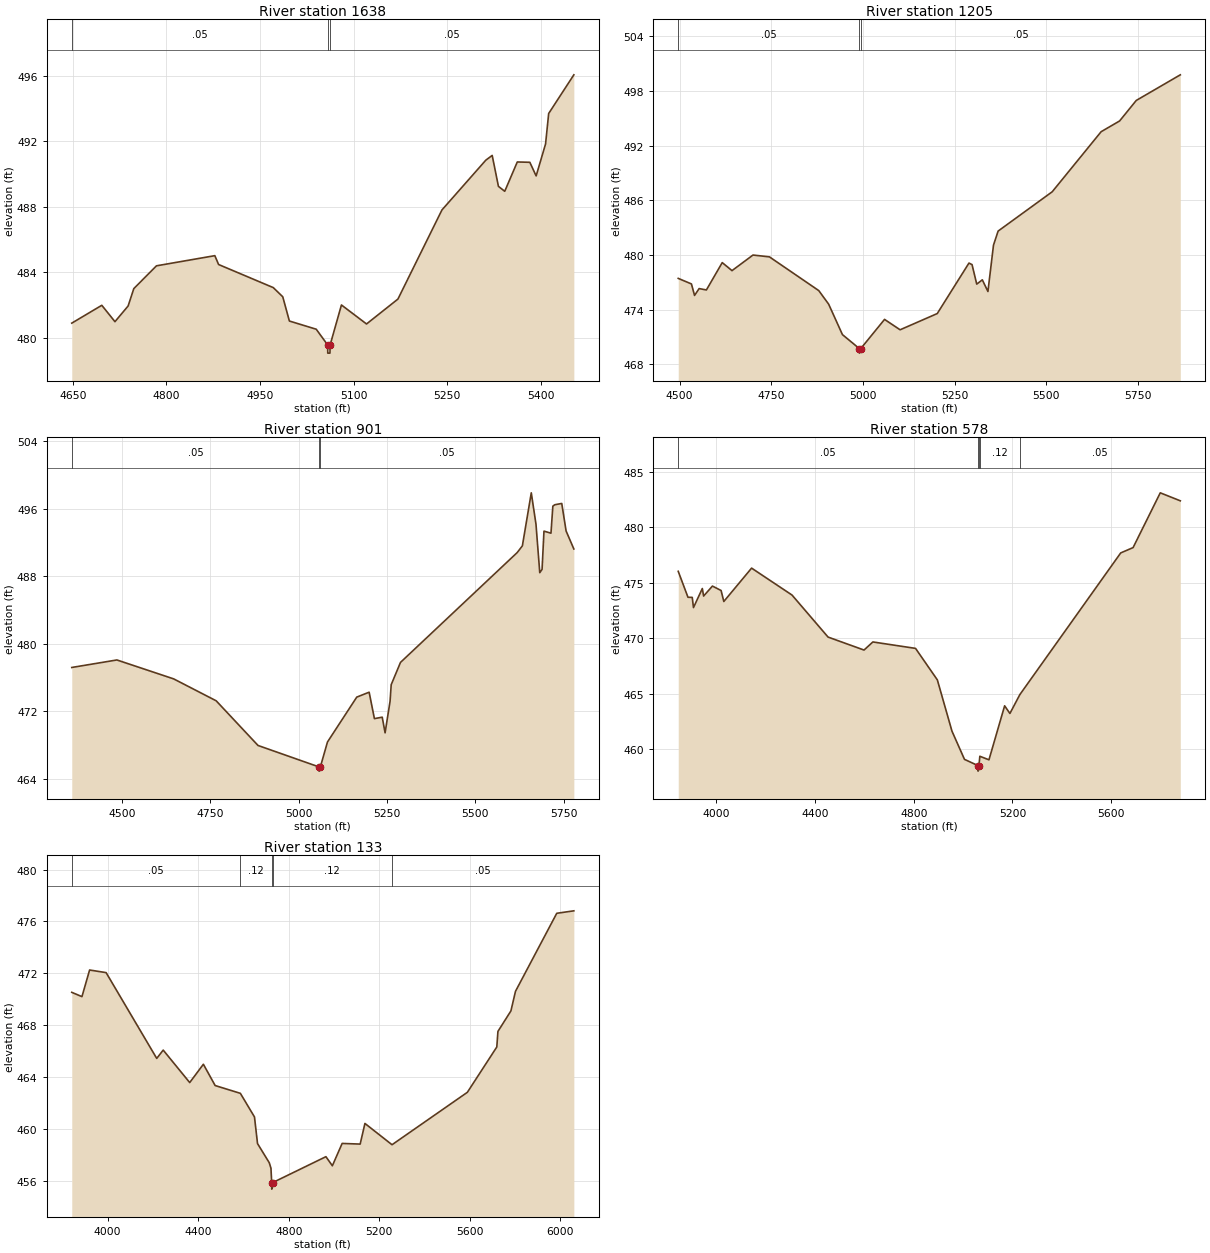
Type RM Length L Ch R = 1,1638,433,433,433
BEGIN DESCRIPTION:
Terry Creek Trib 2_2 2.0
END DESCRIPTION:
XS GIS Cut Line= 3
      2632131.34      6955769.39      2632426.11      6955961.05
      2632876.05      6956011.01
#Sta/Elev= 30
  4648.4  480.89  4696.5  481.98  4717.6  480.98  4738.7  481.94  4747.8  483.00
  4784.1  484.39  4877.6  485.01  4883.6  484.47  4971.2  483.06  4986.4  482.50
  4997.0  481.02  5040.0  480.52  5058.3  479.56  5058.5  479.06  5062.0  479.06
  5062.3  479.56  5080.4  482.00  5120.6  480.84  5170.9  482.36  5241.4  487.80
  5311.7  490.84  5321.9  491.13  5331.9  489.24  5342.0  488.94  5362.1  490.73
  5382.2  490.71  5392.3  489.88  5407.4  491.83  5412.4  493.69  5452.7  496.05
#Mann=3,-1,0
  4648.4    0.05       0  5058.3    0.03       0  5062.3    0.05       0
Bank Sta=5058.3,5062.3
Exp/Cntr=0.3,0.1

Type RM Length L Ch R = 1,1205,304,304,304
BEGIN DESCRIPTION:
Mapping XS 09085c07
END DESCRIPTION:
XS GIS Cut Line= 4
      2632076.61      6955826.65      2632225.06      6956295.41
      2632670.37      6956579.27      2633012.58      6956649.27
#Sta/Elev= 30
  4496.5  477.43  4532.5  476.82  4541.0  475.56  4553.5  476.31  4573.3  476.16
  4616.5  479.16  4643.1  478.28  4700.4  479.99  4745.2  479.79  4879.7  476.09
  4906.7  474.60  4944.3  471.26  4990.3  469.73  4990.5  469.23  4994.3  469.73
  5059.1  472.93  5101.5  471.79  5202.8  473.57  5289.3  479.11  5297.7  478.94
  5310.5  476.80  5325.7  477.27  5341.0  475.99  5356.2  481.08  5368.8  482.62
  5516.3  486.93  5649.7  493.52  5700.1  494.70  5745.5  496.95  5865.6  499.76
#Mann=3,-1,0
  4496.5    0.05       0  4990.3    0.03       0  4994.3    0.05       0
Bank Sta=4990.3,4994.3
Exp/Cntr=0.3,0.1

Type RM Length L Ch R = 1,901,323,323,323
BEGIN DESCRIPTION:
Mapping XS c8300454
END DESCRIPTION:
XS GIS Cut Line= 5
      2632087.92      6955993.74      2632046.69      6956492.84
      2632157.37      6956577.47      2632391.74      6956699.00
      2632876.55      6956876.47
#Sta/Elev= 30
  4358.4  477.18  4486.1  478.07  4646.6  475.83  4767.0  473.23  4885.3  467.94
  5057.7  465.40  5058.0  464.90  5061.7  465.40  5081.8  468.35  5164.7  473.67
  5199.7  474.25  5214.6  471.12  5236.7  471.29  5244.8  469.44  5258.9  473.18
  5262.1  475.14  5288.4  477.78  5618.5  490.79  5633.2  491.59  5658.4  497.87
  5671.7  494.15  5682.4  488.41  5688.9  488.80  5694.3  493.33  5714.1  493.09
  5719.4  496.29  5725.0  496.46  5744.6  496.61  5756.9  493.35  5778.8  491.22
#Mann=3,-1,0
  4358.4    0.05       0  5057.7    0.03       0  5061.7    0.05       0
Bank Sta=5057.7,5061.7
Exp/Cntr=0.3,0.1

Type RM Length L Ch R = 1,578,445,445,445
BEGIN DESCRIPTION:
Mapping XS e8aa9d15
END DESCRIPTION:
XS GIS Cut Line= 5
      2632045.37      6955852.70      2631818.83      6956744.57
      2632025.93      6956853.07      2632176.90      6957011.50
      2632837.05      6957048.02
#Sta/Elev= 30
  3846.0  476.04  3885.5  473.70  3902.7  473.69  3907.8  472.77  3943.6  474.49
  3948.8  473.81  3984.6  474.71  4019.6  474.31  4030.7  473.32  4143.2  476.33
  4307.0  473.90  4453.0  470.11  4598.7  468.94  4634.5  469.67  4807.4  469.09
  4895.7  466.25  4954.9  461.63  5005.7  459.08  5060.3  458.52  5060.6  458.02
  5064.3  458.52  5067.9  459.36  5104.8  459.04  5168.3  463.91  5189.7  463.22
  5229.9  464.92  5638.6  477.70  5688.7  478.18  5798.8  483.12  5880.0  482.40
#Mann=5,-1,0
  3846.0    0.05       0  5060.3    0.03       0  5064.3    0.05       0
  5067.9    0.12       0  5229.9    0.05       0
Bank Sta=5060.3,5064.3
Exp/Cntr=0.3,0.1

Type RM Length L Ch R = 1,133,0,0,0
BEGIN DESCRIPTION:
Terry Creek Trib 2_2 1.0
END DESCRIPTION:
XS GIS Cut Line= 5
      2631863.07      6956141.79      2631615.68      6957008.96
      2631786.04      6957201.15      2631959.43      6957316.25
      2632800.60      6957183.43
#Sta/Elev= 30
  3841.4  470.54  3886.4  470.21  3920.2  472.26  3993.1  472.06  4216.8  465.45
  4245.4  466.09  4362.5  463.59  4422.9  465.00  4474.9  463.36  4586.3  462.76
  4648.7  460.94  4662.1  458.89  4714.1  457.41  4721.5  456.99  4724.7  455.88
  4725.0  455.38  4728.7  455.88  4964.3  457.88  4992.8  457.18  5036.0  458.90
  5115.6  458.85  5136.7  460.44  5256.4  458.80  5589.3  462.84  5719.3  466.33
  5724.3  467.53  5781.7  469.11  5801.9  470.62  5984.2  476.63  6059.7  476.82
#Mann=5,-1,0
  3841.4    0.05       0  4586.3    0.12       0  4724.7    0.07       0
  4728.7    0.12       0  5256.4    0.05       0
Bank Sta=4724.7,4728.7
Exp/Cntr=0.3,0.1

Chan Stop Cuts=-1