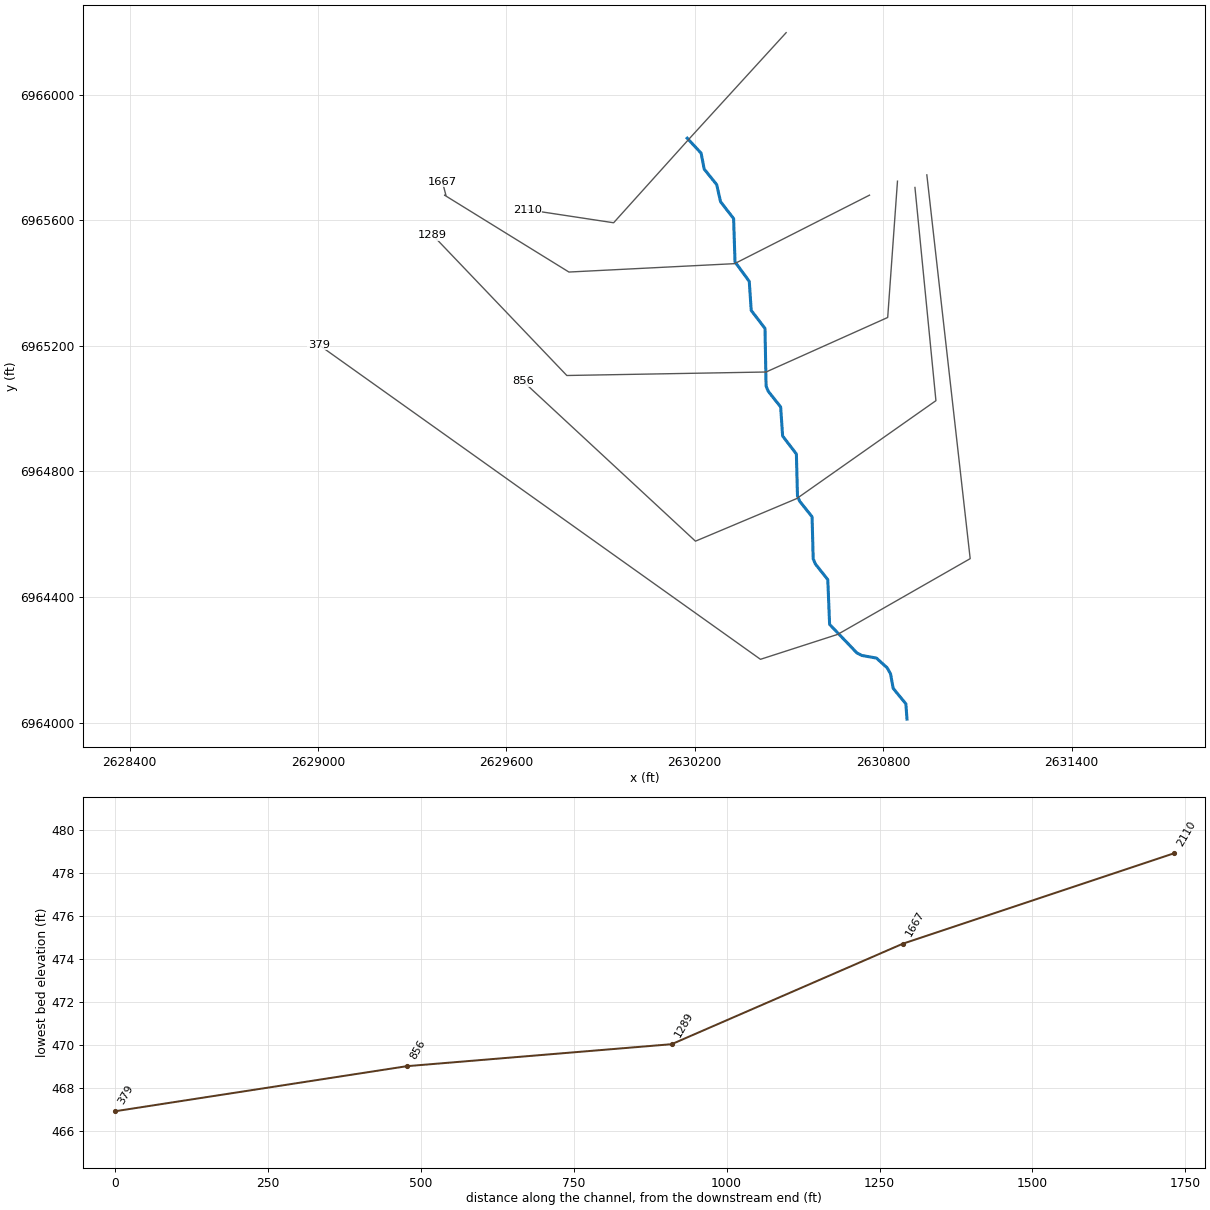
--- Terry Creek Trib 3.prj (project) ---

Proj Title=Terry Creek Trib 3 Base Level Engineering
Current Plan=p01
Default Exp/Contr=0.3,0.1
English Units
Geom File=g01
Flow File=f01
Plan File=p01
BEGIN DESCRIPTION:
Terry Creek Trib 3
END DESCRIPTION:

--- Terry Creek Trib 3.p01 (plan) ---

Plan Title=Multiple Run
Short Identifier=Multiple
Geom File=g01
Flow File=f01
Subcritical Flow
K Sum by GR= 0
Std Step Tol= 0.01
Critical Tol= 0.01
Num of Std Step Trials= 20
Max Error Tol= 0.3
Flow Tol Ratio= 0.001
Split Flow NTrial= 30
Split Flow Tol= 0.02
Split Flow Ratio= 0.02
Log Output Level= 0
Friction Slope Method= 1
Unsteady Friction Slope Method= 2
Unsteady Bridges Friction Slope Method= 1
Parabolic Critical Depth
Global Vel Dist=  1 , 1 , 1
Global Log Level= 0
CheckData=True
Encroach Param= -1, 0, 0, 0
BEGIN DESCRIPTION:
Multiple Run
END DESCRIPTION:

--- Terry Creek Trib 3.f01 (steady flow) ---

Flow Title=Multiple
Number of Profiles=7
Profile Names=10-year,25-year,50-year,1pct_min,100-year,1pct_plu,500-year
River Rch & RM= Terry Creek Trib,Reach-1,2110
     349     449     527     307     613    1223     828
Boundary for River Rch & Prof#=Terry Creek Trib,Reach-1,1
Up Type=0
Dn Type=3
Dn Slope=0.005
Boundary for River Rch & Prof#=Terry Creek Trib,Reach-1,2
Up Type=0
Dn Type=3
Dn Slope=0.005
Boundary for River Rch & Prof#=Terry Creek Trib,Reach-1,3
Up Type=0
Dn Type=3
Dn Slope=0.005
Boundary for River Rch & Prof#=Terry Creek Trib,Reach-1,4
Up Type=0
Dn Type=3
Dn Slope=0.005
Boundary for River Rch & Prof#=Terry Creek Trib,Reach-1,5
Up Type=0
Dn Type=3
Dn Slope=0.005
Boundary for River Rch & Prof#=Terry Creek Trib,Reach-1,6
Up Type=0
Dn Type=3
Dn Slope=0.005
Boundary for River Rch & Prof#=Terry Creek Trib,Reach-1,7
Up Type=0
Dn Type=3
Dn Slope=0.005

--- Terry Creek Trib 3.g01 (geometry) ---

Geom Title=Existing Conditions

River Reach=Terry Creek Trib,Reach-1
Reach XY= 30
      2630176.00      6965861.00      2630220.33      6965813.36
      2630230.04      6965762.67      2630269.93      6965713.20
      2630282.12      6965658.82      2630323.75      6965605.07
      2630328.27      6965466.94      2630373.64      6965405.02
      2630379.86      6965312.60      2630423.74      6965255.06
      2630427.22      6965071.50      2630434.14      6965054.94
      2630473.64      6965005.02      2630479.86      6964912.60
      2630523.73      6964855.06      2630527.23      6964721.51
      2630534.15      6964704.95      2630573.73      6964655.06
      2630577.23      6964521.51      2630584.15      6964504.95
      2630623.73      6964455.06      2630629.54      6964312.46
      2630716.31      6964221.78      2630732.08      6964213.55
      2630778.54      6964205.25      2630812.53      6964174.57
      2630823.60      6964155.16      2630831.99      6964108.79
      2630872.40      6964059.51      2630876.00      6964011.00

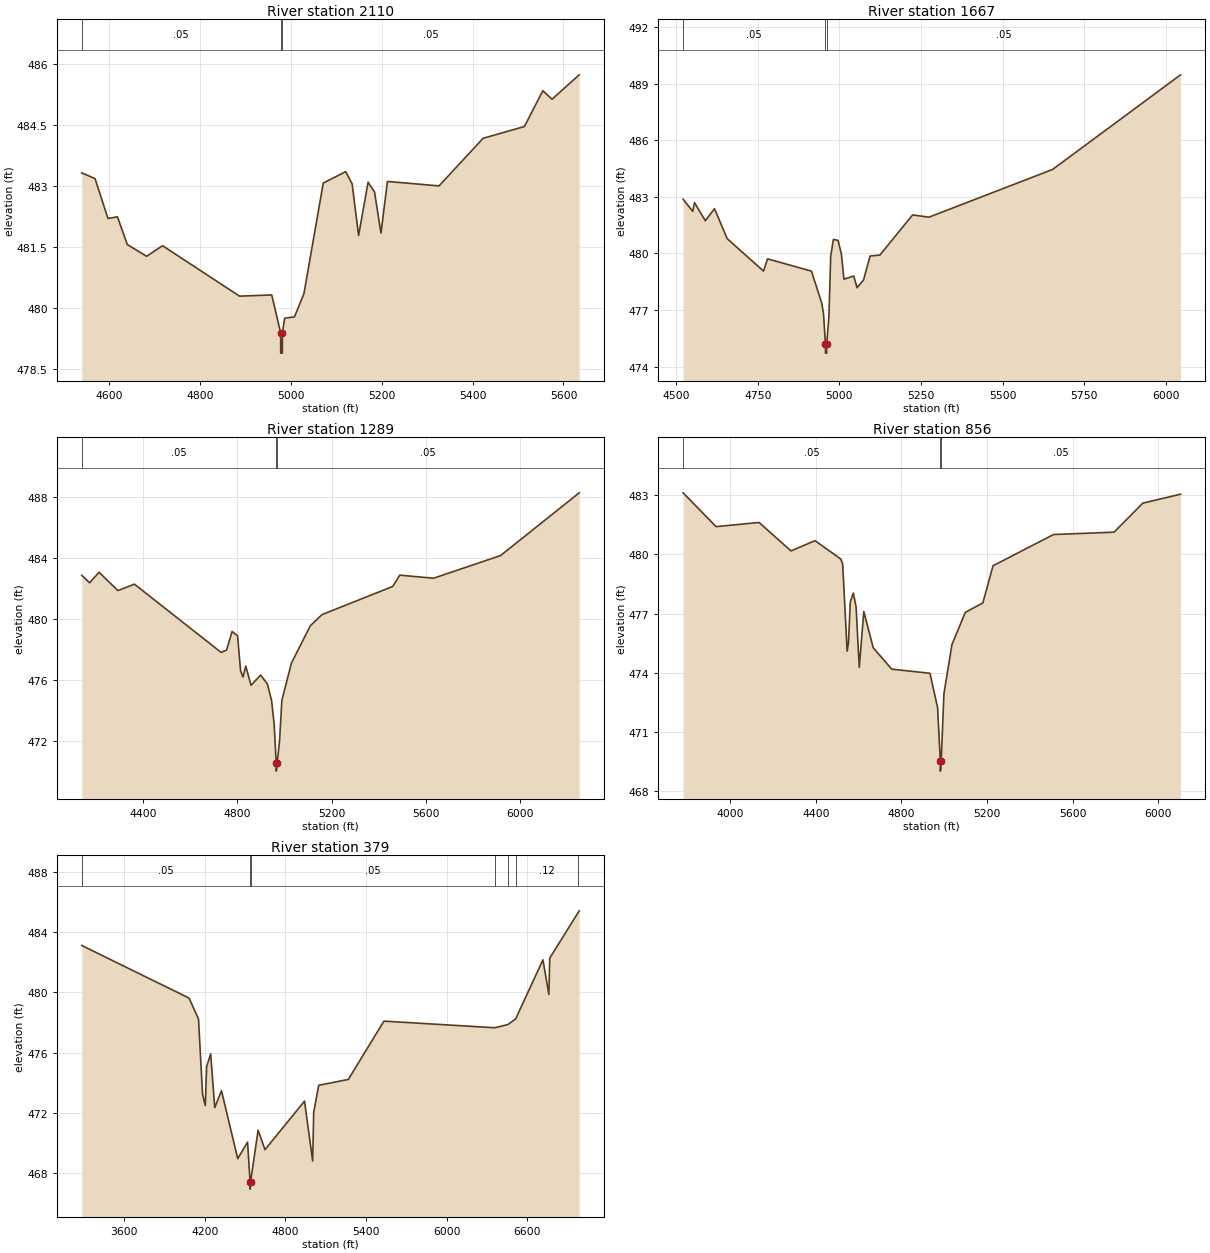
Type RM Length L Ch R = 1,2110,443,443,443
BEGIN DESCRIPTION:
Mapping XS d86f1c73
END DESCRIPTION:
XS GIS Cut Line= 4
      2630491.11      6966197.15      2630180.31      6965856.81
      2629941.61      6965591.66      2629666.82      6965633.33
#Sta/Elev= 30
  4539.1  483.33  4568.3  483.19  4596.7  482.21  4617.7  482.25  4639.3  481.57
  4681.8  481.28  4717.0  481.54  4886.6  480.30  4957.5  480.33  4977.1  479.40
  4977.3  478.90  4980.8  478.90  4981.1  479.40  4985.9  479.76  5007.5  479.79
  5028.4  480.36  5071.0  483.08  5120.4  483.36  5134.6  483.06  5148.8  481.79
  5169.7  483.10  5183.9  482.86  5198.1  481.85  5212.3  483.12  5325.9  483.01
  5423.1  484.18  5514.1  484.47  5554.6  485.35  5574.8  485.14  5634.7  485.74
#Mann=3,-1,0
  4539.1    0.05       0  4977.1    0.04       0  4981.1    0.05       0
Bank Sta=4977.1,4981.1
Exp/Cntr=0.3,0.1

Type RM Length L Ch R = 1,1667,378,378,378
BEGIN DESCRIPTION:
Mapping XS 310d7048
END DESCRIPTION:
XS GIS Cut Line= 6
      2630756.61      6965679.62      2630326.94      6965461.45
      2629799.26      6965434.73      2629402.95      6965679.64
      2629407.40      6965679.64      2629396.28      6965721.93
#Sta/Elev= 30
  4521.2  482.87  4550.6  482.23  4556.2  482.69  4589.2  481.73  4617.4  482.37
  4656.3  480.78  4767.6  479.06  4779.8  479.71  4914.4  479.06  4945.7  477.38
  4951.3  476.82  4957.3  475.21  4957.5  474.71  4961.0  474.71  4961.3  475.21
  4967.9  476.63  4973.5  479.86  4981.7  480.74  4995.8  480.69  5006.1  479.98
  5014.0  478.63  5044.1  478.80  5054.1  478.18  5074.1  478.59  5094.1  479.86
  5124.2  479.91  5224.3  482.04  5274.4  481.92  5653.3  484.45  6045.5  489.47
#Mann=3,-1,0
  4521.2    0.05       0  4957.3    0.04       0  4961.3    0.05       0
Bank Sta=4957.3,4961.3
Exp/Cntr=0.3,0.1

Type RM Length L Ch R = 1,1289,433,433,433
BEGIN DESCRIPTION:
Mapping XS d98d4d44
END DESCRIPTION:
XS GIS Cut Line= 5
      2630845.71      6965724.15      2630814.54      6965290.01
      2630427.13      6965116.34      2629792.58      6965105.21
      2629365.13      6965552.71
#Sta/Elev= 30
  4138.7  482.87  4171.9  482.38  4212.0  483.07  4292.2  481.87  4362.4  482.29
  4730.9  477.82  4754.0  477.98  4777.2  479.19  4800.4  478.92  4813.5  476.61
  4823.6  476.21  4835.4  476.93  4857.7  475.67  4898.6  476.34  4927.3  475.75
  4945.0  474.68  4955.9  473.13  4964.9  470.55  4965.1  470.05  4968.9  470.55
  4979.1  472.08  4988.8  474.69  5029.6  477.13  5109.7  479.57  5159.7  480.30
  5459.7  482.14  5489.7  482.88  5633.2  482.68  5917.7  484.16  6252.0  488.27
#Mann=3,-1,0
  4138.7    0.05       0  4964.9    0.04       0  4968.9    0.05       0
Bank Sta=4964.9,4968.9
Exp/Cntr=0.3,0.1

Type RM Length L Ch R = 1,856,477,477,477
BEGIN DESCRIPTION:
Mapping XS 8f5e9f7e
END DESCRIPTION:
XS GIS Cut Line= 5
      2630901.37      6965704.10      2630968.16      6965025.06
      2630525.10      6964713.35      2630202.26      6964577.54
      2629653.06      6965086.71
#Sta/Elev= 30
  3780.3  483.11  3934.1  481.40  4135.1  481.61  4284.0  480.17  4396.4  480.69
  4516.7  479.76  4525.4  479.51  4546.3  475.10  4552.4  475.50  4561.1  477.59
  4575.3  478.04  4588.1  477.34  4602.9  474.28  4624.2  477.10  4668.3  475.27
  4754.5  474.19  4933.1  473.98  4968.8  472.25  4981.6  469.53  4981.9  469.03
  4985.6  469.53  4998.4  472.95  5035.9  475.43  5098.1  477.06  5180.2  477.54
  5227.7  479.42  5510.2  481.00  5793.1  481.12  5927.5  482.59  6103.5  483.04
#Mann=3,-1,0
  3780.3    0.05       0  4981.6    0.04       0  4985.6    0.05       0
Bank Sta=4981.6,4985.6
Exp/Cntr=0.3,0.1

Type RM Length L Ch R = 1,379,0,0,0
BEGIN DESCRIPTION:
Terry Creek Trib 3 3.0
END DESCRIPTION:
XS GIS Cut Line= 5
      2630939.22      6965744.25      2631077.26      6964521.88
      2630655.48      6964280.72      2630409.32      6964201.26
      2629002.15      6965203.21
#Sta/Elev= 30
  3284.0  483.11  4082.3  479.62  4152.7  478.23  4182.9  473.24  4203.1  472.49
  4213.1  475.06  4243.3  475.92  4273.5  472.35  4323.8  473.47  4444.6  468.96
  4517.8  470.06  4536.6  467.44  4536.9  466.94  4540.6  467.44  4596.2  470.85
  4647.5  469.56  4941.8  472.78  5002.4  468.81  5010.0  472.03  5047.3  473.83
  5267.9  474.22  5532.8  478.09  6357.8  477.65  6454.7  477.86  6513.3  478.24
  6716.2  482.16  6760.4  479.86  6766.7  482.27  6976.3  485.27  6986.1  485.41
#Mann=7,-1,0
  3284.0    0.05       0  4536.6    0.04       0  4540.6    0.05       0
  6357.8    0.12       0  6454.7    0.05       0  6513.3    0.12       0
  6976.3    0.05       0
Bank Sta=4536.6,4540.6
Exp/Cntr=0.3,0.1

Chan Stop Cuts=-1