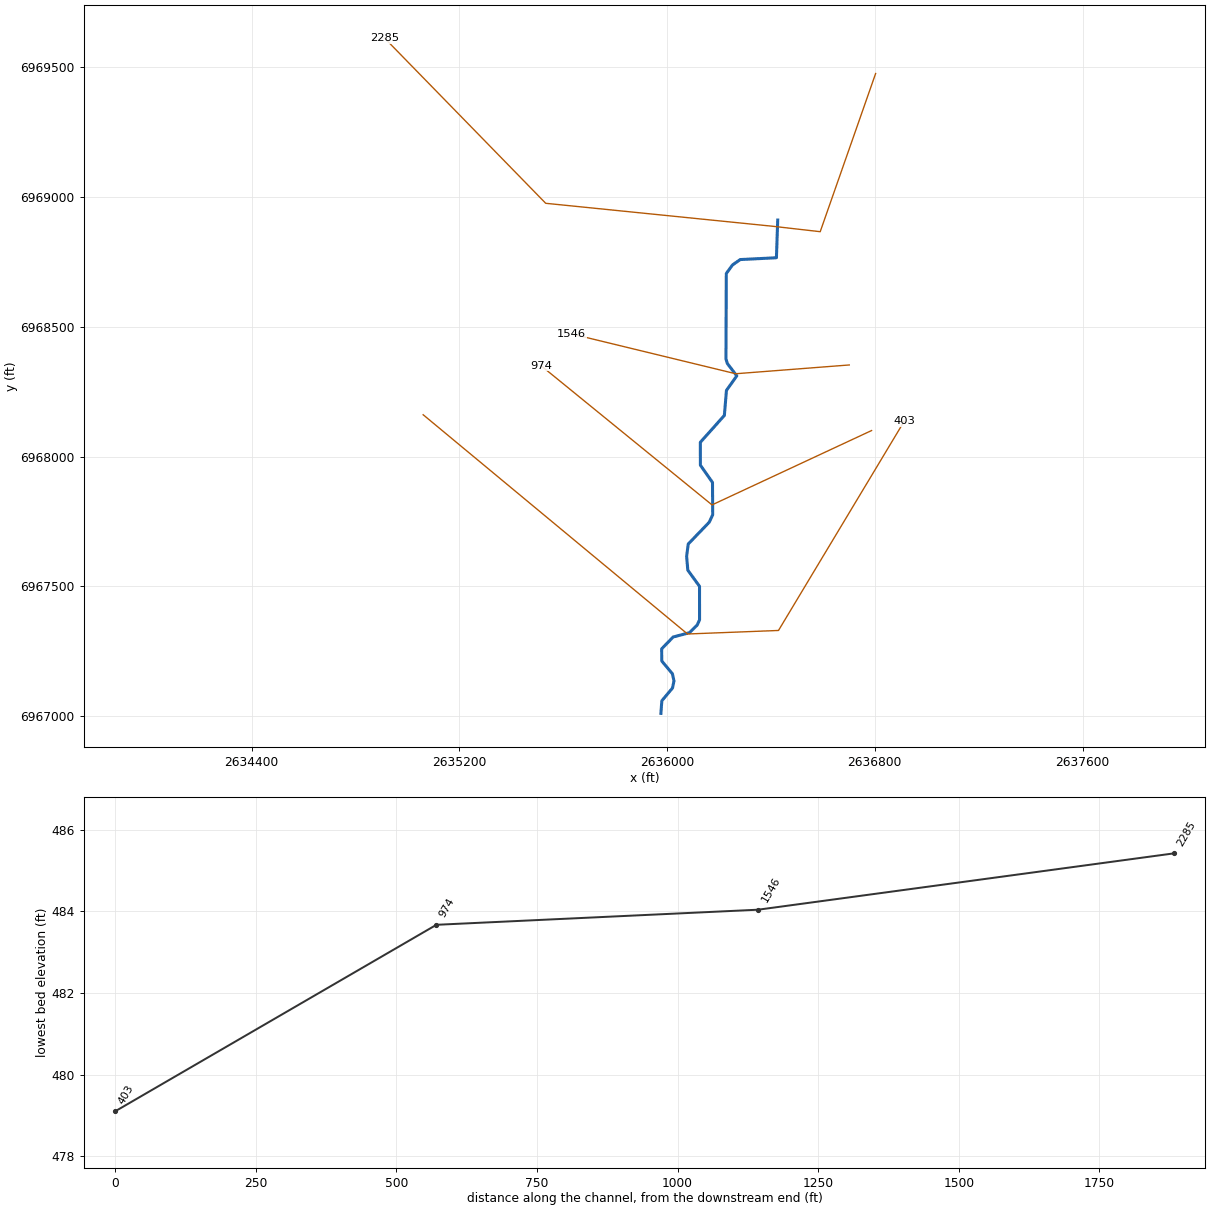
--- Terry Creek Trib 4.prj (project) ---

Proj Title=Terry Creek Trib 4 Base Level Engineering
Current Plan=p01
Default Exp/Contr=0.3,0.1
English Units
Geom File=g01
Flow File=f01
Plan File=p01
BEGIN DESCRIPTION:
Terry Creek Trib 4
END DESCRIPTION:

--- Terry Creek Trib 4.p01 (plan) ---

Plan Title=Multiple Run
Short Identifier=Multiple
Geom File=g01
Flow File=f01
Subcritical Flow
K Sum by GR= 0
Std Step Tol= 0.01
Critical Tol= 0.01
Num of Std Step Trials= 20
Max Error Tol= 0.3
Flow Tol Ratio= 0.001
Split Flow NTrial= 30
Split Flow Tol= 0.02
Split Flow Ratio= 0.02
Log Output Level= 0
Friction Slope Method= 1
Unsteady Friction Slope Method= 2
Unsteady Bridges Friction Slope Method= 1
Parabolic Critical Depth
Global Vel Dist=  1 , 1 , 1
Global Log Level= 0
CheckData=True
Encroach Param= -1, 0, 0, 0
BEGIN DESCRIPTION:
Multiple Run
END DESCRIPTION:

--- Terry Creek Trib 4.f01 (steady flow) ---

Flow Title=Multiple
Number of Profiles=7
Profile Names=10-year,25-year,50-year,1pct_min,100-year,1pct_plu,500-year
River Rch & RM= Terry Creek Trib,Reach-1,2285
     320     410     480     279     557    1111     748
Boundary for River Rch & Prof#=Terry Creek Trib,Reach-1,1
Up Type=0
Dn Type=3
Dn Slope=0.005
Boundary for River Rch & Prof#=Terry Creek Trib,Reach-1,2
Up Type=0
Dn Type=3
Dn Slope=0.005
Boundary for River Rch & Prof#=Terry Creek Trib,Reach-1,3
Up Type=0
Dn Type=3
Dn Slope=0.005
Boundary for River Rch & Prof#=Terry Creek Trib,Reach-1,4
Up Type=0
Dn Type=3
Dn Slope=0.005
Boundary for River Rch & Prof#=Terry Creek Trib,Reach-1,5
Up Type=0
Dn Type=3
Dn Slope=0.005
Boundary for River Rch & Prof#=Terry Creek Trib,Reach-1,6
Up Type=0
Dn Type=3
Dn Slope=0.005
Boundary for River Rch & Prof#=Terry Creek Trib,Reach-1,7
Up Type=0
Dn Type=3
Dn Slope=0.005

--- Terry Creek Trib 4.g01 (geometry) ---

Geom Title=Existing Conditions

River Reach=Terry Creek Trib,Reach-1
Reach XY= 30
      2636426.00      6968911.00      2636421.05      6968765.95
      2636281.66      6968759.01      2636251.97      6968738.35
      2636227.97      6968705.35      2636226.66      6968376.16
      2636232.02      6968358.55      2636268.44      6968311.00
      2636228.56      6968255.10      2636220.46      6968158.58
      2636127.97      6968055.11      2636128.16      6967966.98
      2636174.79      6967900.49      2636175.63      6967776.17
      2636162.60      6967747.70      2636081.41      6967663.42
      2636075.15      6967616.05      2636079.70      6967562.60
      2636124.79      6967500.49      2636125.03      6967371.29
      2636115.66      6967350.88      2636086.04      6967321.63
      2636023.41      6967305.24      2635979.04      6967259.58
      2635979.36      6967212.76      2636020.59      6967163.20
      2636026.46      6967136.01      2636020.88      6967108.75
      2635979.69      6967059.51      2635976.00      6967011.00

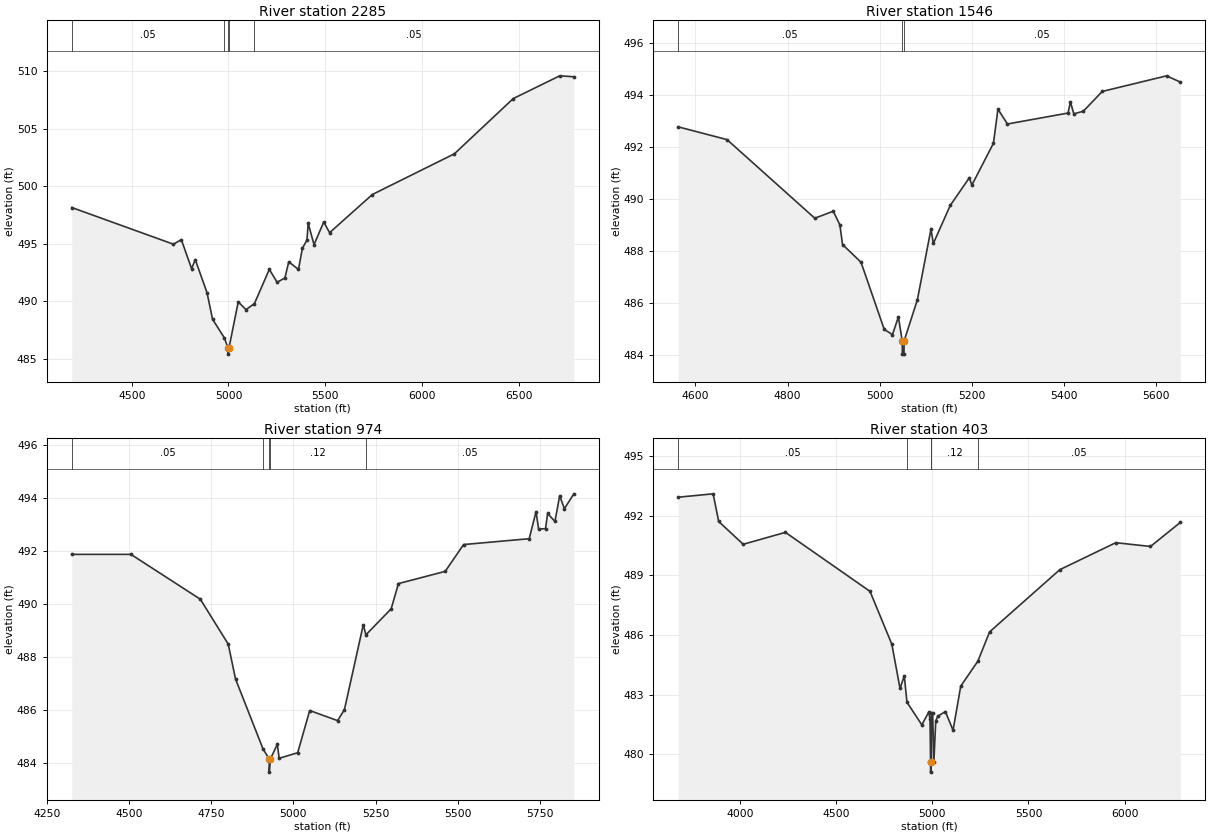
Type RM Length L Ch R = 1,2285,739,739,739
BEGIN DESCRIPTION:
Mapping XS 659906b1
END DESCRIPTION:
XS GIS Cut Line= 5
      2636803.24      6969475.76      2636589.68      6968866.34
      2636407.39      6968887.18      2635532.39      6968975.72
      2634912.62      6969611.11
#Sta/Elev= 30
  4189.6  498.17  4714.8  494.98  4756.2  495.37  4809.2  492.85  4828.2  493.64
  4889.4  490.74  4917.5  488.46  4978.7  486.83  4998.1  485.92  4998.3  485.42
  5002.1  485.92  5050.4  489.96  5090.6  489.29  5134.0  489.81  5211.2  492.79
  5251.4  491.67  5291.6  492.04  5311.7  493.45  5362.0  492.78  5382.1  494.62
  5405.8  495.34  5412.2  496.79  5442.4  494.94  5492.6  496.91  5522.8  495.98
  5743.9  499.30  6168.2  502.84  6472.3  507.64  6712.8  509.62  6785.9  509.54
#Mann=5,-1,0
  4189.6    0.05       0  4978.7    0.12       0  4998.1    0.07       0
  5002.1    0.12       0  5134.0    0.05       0
Bank Sta=4998.1,5002.1
Exp/Cntr=0.3,0.1

Type RM Length L Ch R = 1,1546,572,572,572
BEGIN DESCRIPTION:
Mapping XS 35c897a0
END DESCRIPTION:
XS GIS Cut Line= 3
      2636701.61      6968353.03      2636264.13      6968319.18
      2635631.30      6968472.83
#Sta/Elev= 30
  4562.6  492.77  4668.5  492.28  4859.1  489.26  4899.2  489.53  4913.6  489.00
  4919.3  488.25  4959.4  487.57  5009.8  484.99  5027.7  484.79  5040.6  485.47
  5048.9  484.54  5049.2  484.04  5052.7  484.04  5052.9  484.54  5081.8  486.13
  5111.3  488.84  5116.4  488.29  5153.1  489.75  5194.8  490.82  5200.0  490.53
  5246.9  492.14  5256.7  493.45  5277.3  492.88  5408.8  493.30  5414.0  493.73
  5421.4  493.27  5442.0  493.37  5483.1  494.13  5622.8  494.73  5652.6  494.49
#Mann=3,-1,0
  4562.6    0.05       0  5048.9    0.04       0  5052.9    0.05       0
Bank Sta=5048.9,5052.9
Exp/Cntr=0.3,0.1

Type RM Length L Ch R = 1,974,571,571,571
BEGIN DESCRIPTION:
Mapping XS c970afb5
END DESCRIPTION:
XS GIS Cut Line= 3
      2636787.55      6968100.42      2636172.98      6967813.97
      2635514.11      6968350.44
#Sta/Elev= 30
  4325.8  491.87  4505.8  491.87  4717.1  490.18  4801.9  488.49  4824.0  487.18
  4907.5  484.55  4926.4  484.17  4926.7  483.67  4930.4  484.17  4951.3  484.72
  4956.8  484.19  5013.2  484.40  5049.8  485.99  5134.6  485.61  5155.4  486.02
  5212.8  489.22  5220.8  488.84  5297.6  489.82  5319.9  490.77  5462.1  491.23
  5518.0  492.24  5717.7  492.46  5738.5  493.48  5746.4  492.82  5767.3  492.84
  5773.7  493.41  5796.0  493.11  5810.4  494.08  5824.7  493.59  5853.5  494.15
#Mann=5,-1,0
  4325.8    0.05       0  4907.5    0.12       0  4926.4    0.07       0
  4930.4    0.12       0  5220.8    0.05       0
Bank Sta=4926.4,4930.4
Exp/Cntr=0.3,0.1

Type RM Length L Ch R = 1,403,0,0,0
BEGIN DESCRIPTION:
Terry Creek Trib 4 2.0
END DESCRIPTION:
XS GIS Cut Line= 4
      2635060.33      6968161.32      2636078.55      6967316.75
      2636428.98      6967330.35      2636913.00      6968135.81
#Sta/Elev= 30
  3677.1  492.94  3858.8  493.11  3887.5  491.72  4015.1  490.57  4235.1  491.17
  4675.3  488.20  4788.8  485.54  4831.6  483.31  4853.7  483.95  4867.6  482.62
  4944.9  481.48  4981.4  482.13  4987.8  481.75  4990.5  479.60  4990.8  479.10
  4994.5  479.60  4995.1  482.09  5001.2  482.09  5007.5  479.60  5017.5  481.67
  5027.5  481.91  5067.5  482.15  5107.5  481.21  5147.6  483.43  5236.9  484.69
  5297.7  486.16  5662.9  489.29  5954.4  490.65  6135.1  490.46  6290.4  491.67
#Mann=5,-1,0
  3677.1    0.05       0  4867.6    0.12       0  4990.5    0.07       0
  4994.5    0.12       0  5236.9    0.05       0
Bank Sta=4990.5,4994.5
Exp/Cntr=0.3,0.1

Chan Stop Cuts=-1