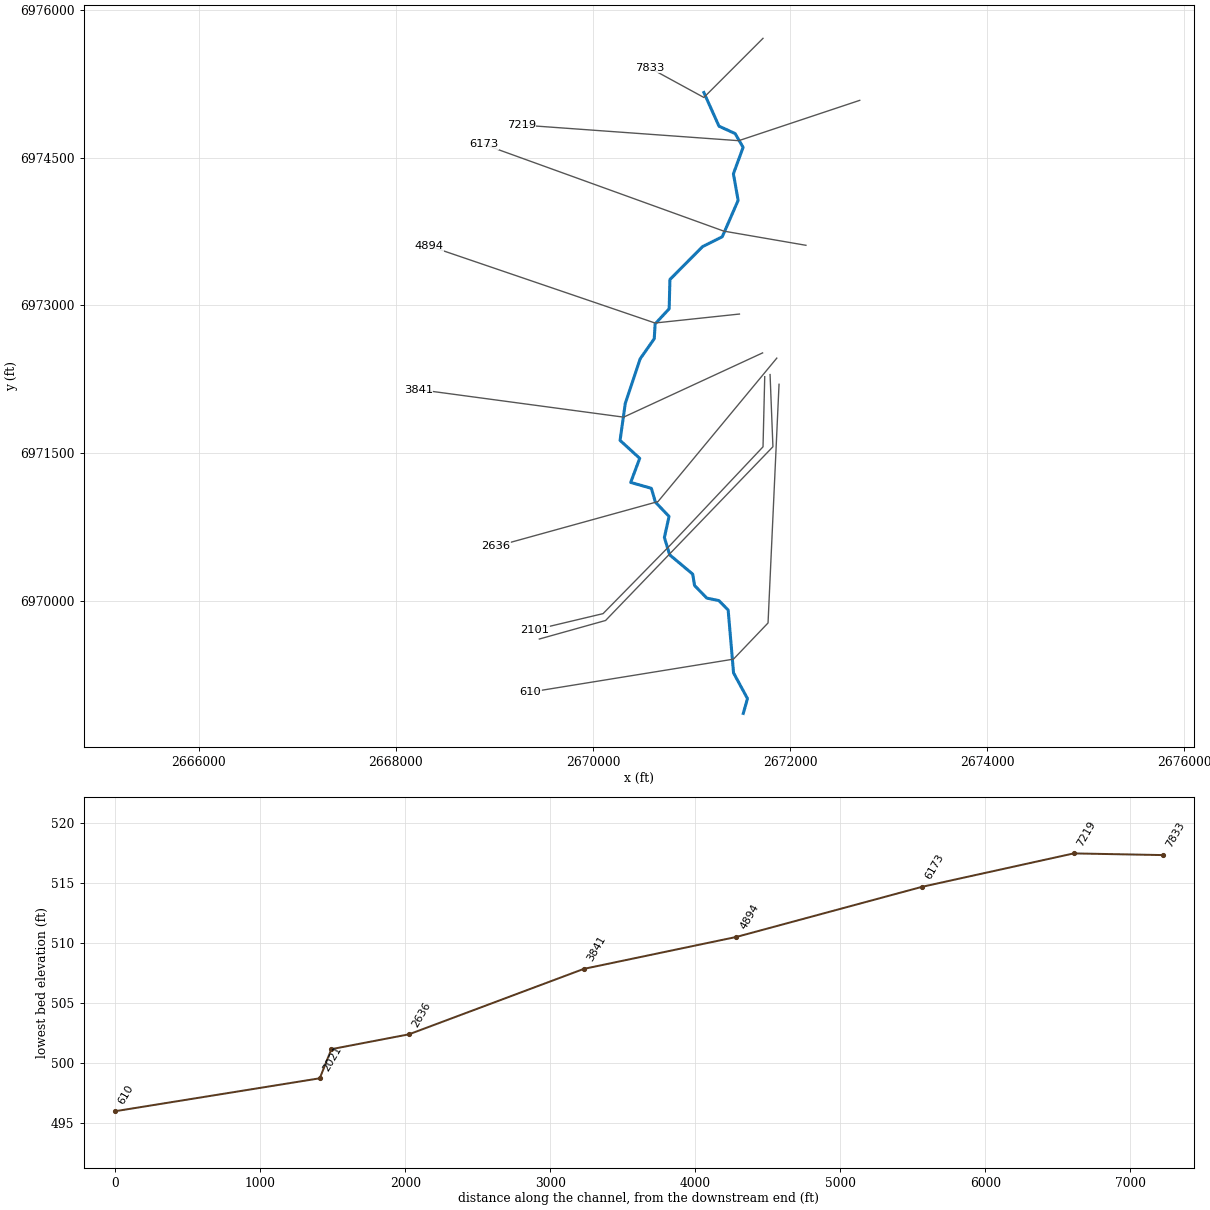
--- Walnut Creek Trib 1.prj (project) ---

Proj Title=Walnut Creek Trib 1 Base Level Engineering
Current Plan=p01
Default Exp/Contr=0.3,0.1
English Units
Geom File=g01
Flow File=f01
Plan File=p01
BEGIN DESCRIPTION:
Walnut Creek Trib 1
END DESCRIPTION:

--- Walnut Creek Trib 1.p01 (plan) ---

Plan Title=Multiple Run
Short Identifier=Multiple
Geom File=g01
Flow File=f01
Subcritical Flow
K Sum by GR= 0
Std Step Tol= 0.01
Critical Tol= 0.01
Num of Std Step Trials= 20
Max Error Tol= 0.3
Flow Tol Ratio= 0.001
Split Flow NTrial= 30
Split Flow Tol= 0.02
Split Flow Ratio= 0.02
Log Output Level= 0
Friction Slope Method= 1
Unsteady Friction Slope Method= 2
Unsteady Bridges Friction Slope Method= 1
Parabolic Critical Depth
Global Vel Dist=  1 , 1 , 1
Global Log Level= 0
CheckData=True
Encroach Param= -1, 0, 0, 0
BEGIN DESCRIPTION:
Multiple Run
END DESCRIPTION:

--- Walnut Creek Trib 1.f01 (steady flow) ---

Flow Title=Multiple
Number of Profiles=7
Profile Names=10-year,25-year,50-year,1pct_min,100-year,1pct_plu,500-year
River Rch & RM= Walnut Creek Tri,Reach-1,7833
     551     734     881     525    1047    2089    1478
River Rch & RM= Walnut Creek Tri,Reach-1,6173
     666     896    1082     649    1294    2582    1848
River Rch & RM= Walnut Creek Tri,Reach-1,4894
     910    1243    1517     916    1828    3647    2656
Boundary for River Rch & Prof#=Walnut Creek Tri,Reach-1,1
Up Type=0
Dn Type=3
Dn Slope=0.005
Boundary for River Rch & Prof#=Walnut Creek Tri,Reach-1,2
Up Type=0
Dn Type=3
Dn Slope=0.005
Boundary for River Rch & Prof#=Walnut Creek Tri,Reach-1,3
Up Type=0
Dn Type=3
Dn Slope=0.005
Boundary for River Rch & Prof#=Walnut Creek Tri,Reach-1,4
Up Type=0
Dn Type=3
Dn Slope=0.005
Boundary for River Rch & Prof#=Walnut Creek Tri,Reach-1,5
Up Type=0
Dn Type=3
Dn Slope=0.005
Boundary for River Rch & Prof#=Walnut Creek Tri,Reach-1,6
Up Type=0
Dn Type=3
Dn Slope=0.005
Boundary for River Rch & Prof#=Walnut Creek Tri,Reach-1,7
Up Type=0
Dn Type=3
Dn Slope=0.005

--- Walnut Creek Trib 1.g01 (geometry) ---

Geom Title=Existing Conditions

River Reach=Walnut Creek Tri,Reach-1
Reach XY= 30
      2671126.00      6975161.00      2671279.54      6974819.48
      2671443.05      6974744.51      2671524.20      6974604.89
      2671425.68      6974336.04      2671473.75      6974066.94
      2671312.53      6973697.43      2671112.78      6973597.38
      2670781.45      6973263.47      2670773.94      6972966.85
      2670631.47      6972813.45      2670622.45      6972662.47
      2670479.83      6972459.42      2670328.26      6972005.06
      2670275.60      6971631.13      2670474.83      6971448.99
      2670383.34      6971204.61      2670593.22      6971144.76
      2670633.86      6971004.83      2670772.54      6970859.50
      2670725.29      6970645.94      2670779.19      6970469.35
      2671012.60      6970274.33      2671031.52      6970158.57
      2671155.84      6970030.63      2671278.44      6970005.48
      2671372.47      6969909.55      2671427.20      6969271.50
      2671568.52      6969011.01      2671526.00      6968861.00

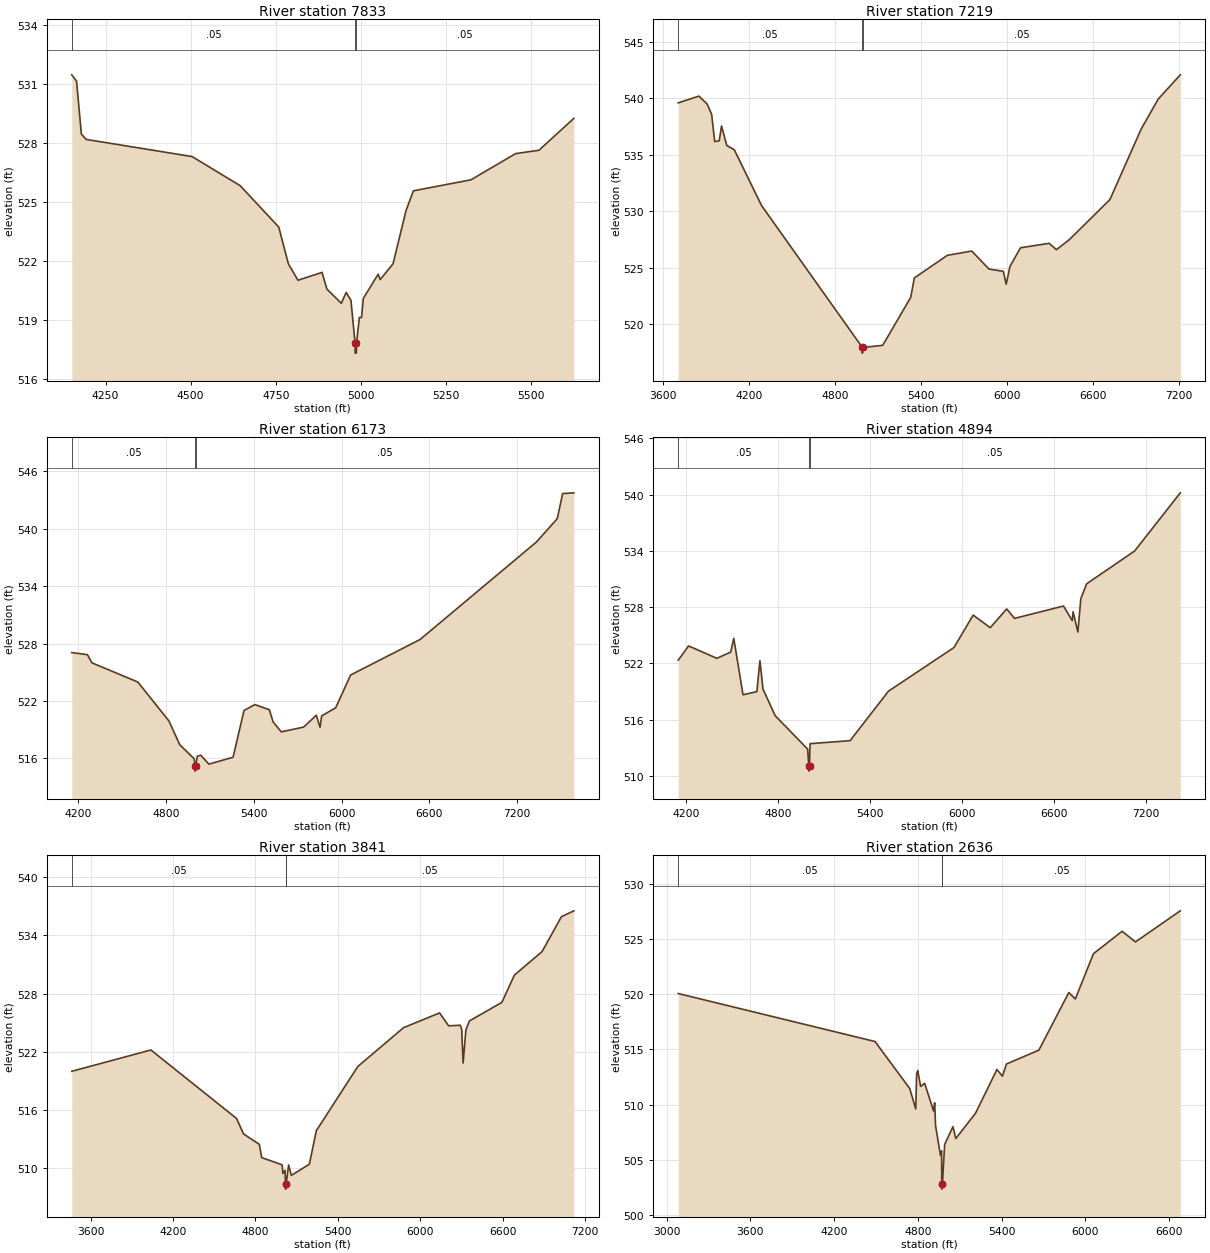
Type RM Length L Ch R = 1,7833,614,614,614
BEGIN DESCRIPTION:
Walnut Creek Trib 1 7.0
END DESCRIPTION:
XS GIS Cut Line= 3
      2671725.97      6975710.97      2671126.00      6975111.00
      2670575.99      6975411.01
#Sta/Elev= 30
  4150.8  531.46  4164.9  531.14  4179.0  528.45  4193.2  528.18  4504.3  527.31
  4645.7  525.83  4758.9  523.73  4787.2  521.86  4815.4  521.03  4886.1  521.43
  4900.3  520.58  4942.7  519.86  4956.9  520.41  4971.0  520.01  4983.1  517.83
  4983.4  517.33  4986.9  517.33  4987.1  517.83  4995.8  519.14  5002.1  519.14
  5007.4  520.11  5051.0  521.34  5056.7  521.06  5094.7  521.87  5132.7  524.56
  5154.5  525.57  5323.5  526.13  5454.9  527.46  5523.3  527.63  5625.8  529.25
#Mann=3,-1,0
  4150.8    0.05       0  4983.1    0.04       0  4987.1    0.05       0
Bank Sta=4983.1,4987.1
Exp/Cntr=0.3,0.1

Type RM Length L Ch R = 1,7219,1046,1046,1046
BEGIN DESCRIPTION:
Mapping XS 513df539
END DESCRIPTION:
XS GIS Cut Line= 3
      2672707.61      6975081.74      2671479.29      6974672.30
      2669272.89      6974831.53
#Sta/Elev= 30
  3703.6  539.58  3847.9  540.18  3905.6  539.48  3937.2  538.56  3958.3  536.16
  3989.9  536.23  4006.0  537.54  4042.9  535.81  4095.3  535.44  4285.0  530.52
  4989.6  517.97  4989.9  517.47  4993.6  517.97  5132.0  518.16  5327.6  522.40
  5352.6  524.11  5583.2  526.11  5753.6  526.49  5873.9  524.90  5974.2  524.70
  5994.2  523.56  6020.8  525.13  6094.5  526.78  6295.0  527.17  6345.1  526.61
  6434.7  527.49  6719.0  531.04  6936.7  537.26  7057.0  539.93  7210.5  542.06
#Mann=3,-1,0
  3703.6    0.05       0  4989.6    0.03       0  4993.6    0.05       0
Bank Sta=4989.6,4993.6
Exp/Cntr=0.3,0.1

Type RM Length L Ch R = 1,6173,1279,1279,1279
BEGIN DESCRIPTION:
Mapping XS 6e7b297f
END DESCRIPTION:
XS GIS Cut Line= 3
      2672161.66      6973610.82      2671327.65      6973754.87
      2668893.85      6974634.38
#Sta/Elev= 30
  4154.7  527.06  4261.9  526.84  4292.4  525.99  4607.0  523.98  4820.1  519.90
  4893.2  517.44  4992.6  515.96  4997.4  515.18  4997.6  514.68  5001.4  515.18
  5013.5  516.24  5036.9  516.34  5092.9  515.41  5258.0  516.13  5332.9  521.01
  5406.9  521.63  5506.2  521.09  5531.6  519.83  5587.6  518.78  5740.9  519.28
  5827.6  520.52  5852.9  519.25  5864.1  520.45  5959.8  521.29  6062.2  524.72
  6536.8  528.42  7332.8  538.60  7475.5  541.04  7512.2  543.66  7588.9  543.74
#Mann=3,-1,0
  4154.7    0.05       0  4997.4    0.03       0  5001.4    0.05       0
Bank Sta=4997.4,5001.4
Exp/Cntr=0.3,0.1

Type RM Length L Ch R = 1,4894,1053,1053,1053
BEGIN DESCRIPTION:
Mapping XS 63e266f9
END DESCRIPTION:
XS GIS Cut Line= 3
      2671486.86      6972913.26      2670630.10      6972822.28
      2668340.67      6973603.11
#Sta/Elev= 30
  4146.8  522.34  4214.3  523.86  4399.1  522.54  4489.6  523.20  4509.7  524.67
  4570.0  518.65  4660.5  518.98  4680.6  522.29  4700.8  519.25  4780.0  516.42
  4992.4  512.85  5000.3  511.00  5000.7  510.50  5004.5  511.00  5007.9  513.43
  5269.6  513.75  5520.3  519.03  5948.5  523.69  6073.9  527.15  6185.5  525.81
  6293.2  527.81  6344.0  526.80  6664.0  528.12  6721.4  526.56  6726.7  527.51
  6758.0  525.34  6777.2  528.90  6815.4  530.49  7128.8  533.99  7427.3  540.20
#Mann=3,-1,0
  4146.8    0.05       0  5000.3    0.03       0  5004.5    0.05       0
Bank Sta=5000.3,5004.5
Exp/Cntr=0.3,0.1

Type RM Length L Ch R = 1,3841,1205,1205,1205
BEGIN DESCRIPTION:
Mapping XS 423a6bd0
END DESCRIPTION:
XS GIS Cut Line= 3
      2671721.90      6972518.99      2670311.65      6971866.94
      2668226.63      6972147.47
#Sta/Elev= 30
  3462.1  519.98  4038.5  522.18  4662.3  515.12  4713.7  513.52  4828.3  512.45
  4845.7  511.08  4994.3  510.34  5000.0  509.44  5015.8  509.77  5019.2  508.33
  5019.7  507.83  5023.7  508.33  5041.7  510.32  5061.9  509.25  5193.0  510.40
  5243.5  513.85  5546.2  520.48  5879.2  524.48  6141.5  526.00  6207.9  524.67
  6292.8  524.73  6302.9  524.27  6313.0  520.83  6333.2  524.26  6358.5  525.17
  6595.5  527.09  6686.4  529.90  6888.4  532.33  7029.0  535.92  7119.6  536.53
#Mann=3,-1,0
  3462.1    0.05       0  5019.2    0.03       0  5023.7    0.05       0
Bank Sta=5019.2,5023.7
Exp/Cntr=0.3,0.1

Type RM Length L Ch R = 1,2636,535,535,535
BEGIN DESCRIPTION:
Mapping XS ba961c35
END DESCRIPTION:
XS GIS Cut Line= 3
      2671865.97      6972465.91      2670660.43      6971010.17
      2669016.52      6970555.63
#Sta/Elev= 30
  3083.6  520.06  4492.8  515.72  4741.5  511.47  4784.5  509.62  4791.0  512.83
  4798.9  513.09  4819.7  511.66  4848.3  511.94  4912.2  509.44  4920.0  510.18
  4926.5  508.10  4961.6  505.43  4969.5  505.83  4970.9  502.87  4971.4  502.37
  4975.7  502.87  4991.6  506.41  5050.9  508.02  5071.7  506.95  5213.1  509.24
  5366.0  513.19  5405.5  512.59  5434.6  513.69  5666.5  514.94  5880.9  520.15
  5927.5  519.57  6057.3  523.66  6262.4  525.69  6358.2  524.73  6679.3  527.54
#Mann=3,-1,0
  3083.6    0.05       0  4970.9    0.03       0  4975.7    0.05       0
Bank Sta=4970.9,4975.7
Exp/Cntr=0.3,0.1

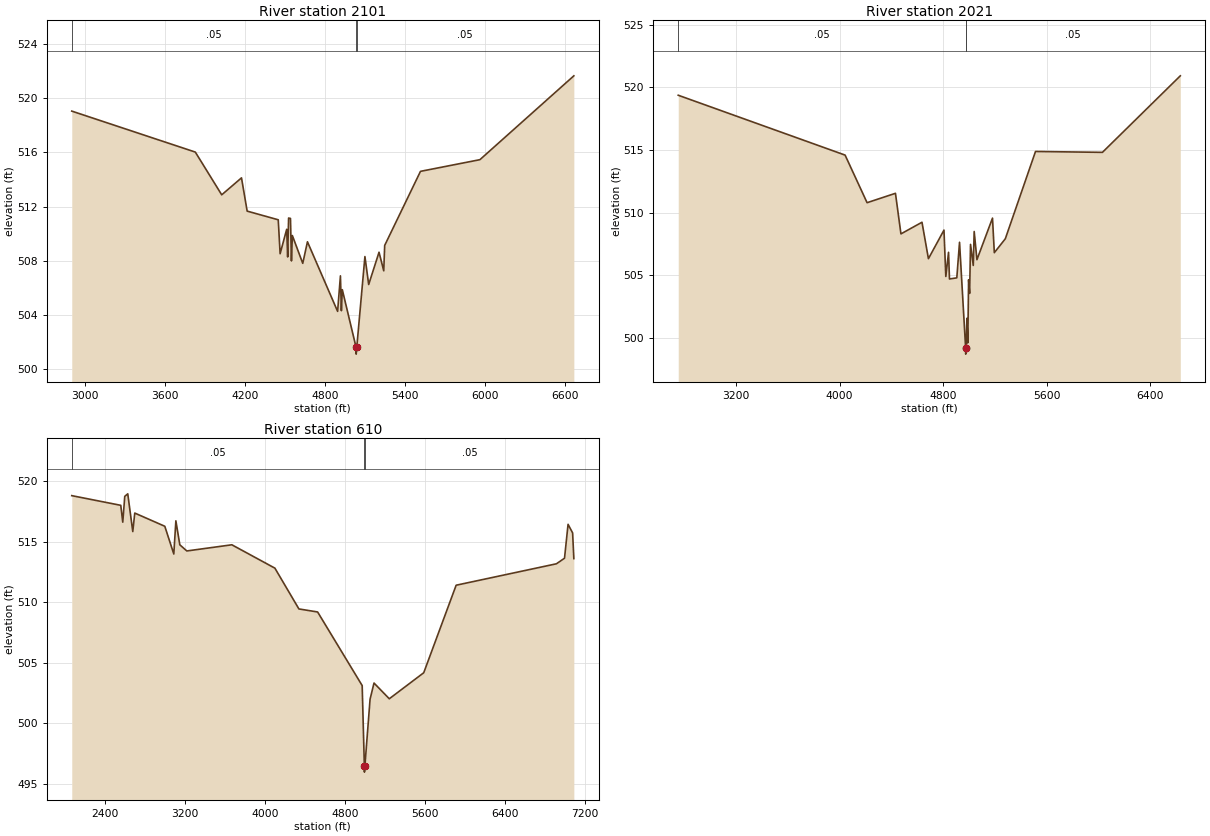
Type RM Length L Ch R = 1,2101,80,80,80
BEGIN DESCRIPTION:
Mapping XS e1eb660a
END DESCRIPTION:
XS GIS Cut Line= 5
      2671743.57      6972277.60      2671726.21      6971565.83
      2670784.37      6970567.57      2670102.95      6969873.12
      2669409.79      6969708.50
#Sta/Elev= 30
  2899.6  519.04  3827.3  516.02  4025.5  512.87  4174.0  514.12  4216.5  511.67
  4449.9  511.03  4464.0  508.53  4513.4  510.33  4520.7  508.29  4527.6  511.16
  4541.7  511.13  4549.0  508.00  4555.9  509.87  4634.0  507.82  4669.2  509.41
  4895.7  504.28  4916.8  506.90  4924.0  504.33  4930.9  505.88  5034.4  501.63
  5035.1  501.13  5039.5  501.63  5100.7  508.32  5129.0  506.26  5206.7  508.64
  5242.1  507.27  5249.1  509.14  5517.9  514.60  5964.1  515.46  6669.4  521.64
#Mann=3,-1,0
  2899.6    0.05       0  5034.4    0.03       0  5039.5    0.05       0
Bank Sta=5034.4,5039.5
Exp/Cntr=0.3,0.1

Type RM Length L Ch R = 1,2021,1411,1411,1411
BEGIN DESCRIPTION:
Mapping XS db49df91
END DESCRIPTION:
XS GIS Cut Line= 5
      2671797.74      6972299.08      2671826.69      6971566.70
      2670776.81      6970476.90      2670128.77      6969803.68
      2669456.55      6969615.54
#Sta/Elev= 30
  2753.8  519.37  4042.9  514.59  4212.7  510.79  4431.9  511.54  4474.3  508.30
  4636.9  509.23  4686.6  506.32  4806.7  508.60  4820.9  504.90  4842.0  506.83
  4849.2  504.70  4905.8  504.79  4926.9  507.63  4974.0  499.20  4974.6  498.70
  4979.1  499.20  4983.5  501.56  4990.7  499.60  4997.0  504.64  5004.8  503.55
  5011.8  507.46  5033.1  505.78  5040.1  508.49  5061.4  506.24  5181.6  509.56
  5195.7  506.80  5280.6  507.91  5513.9  514.88  6030.8  514.81  6632.5  520.92
#Mann=3,-1,0
  2753.8    0.05       0  4974.0    0.03       0  4979.1    0.05       0
Bank Sta=4974,4979.1
Exp/Cntr=0.3,0.1

Type RM Length L Ch R = 1,610,0,0,0
BEGIN DESCRIPTION:
Walnut Creek Trib 1 1.0
END DESCRIPTION:
XS GIS Cut Line= 4
      2671888.72      6972200.54      2671777.13      6969778.50
      2671426.40      6969411.17      2669363.94      6969076.75
#Sta/Elev= 30
  2067.5  518.79  2557.6  517.99  2577.6  516.60  2597.6  518.73  2627.6  518.94
  2677.7  515.82  2697.7  517.35  2998.0  516.26  3088.1  513.97  3108.8  516.71
  3148.2  514.73  3218.3  514.22  3668.7  514.73  4099.2  512.80  4339.5  509.43
  4526.6  509.18  4972.3  503.10  4994.0  496.45  4994.8  495.95  4999.3  496.45
  5051.1  501.97  5090.6  503.31  5243.5  502.01  5588.0  504.16  5912.2  511.39
  6915.1  513.16  6996.1  513.62  7031.6  516.42  7077.2  515.71  7089.4  513.59
#Mann=3,-1,0
  2067.5    0.05       0  4994.0    0.04       0  4999.3    0.05       0
Bank Sta=4994,4999.3
Exp/Cntr=0.3,0.1

Chan Stop Cuts=-1