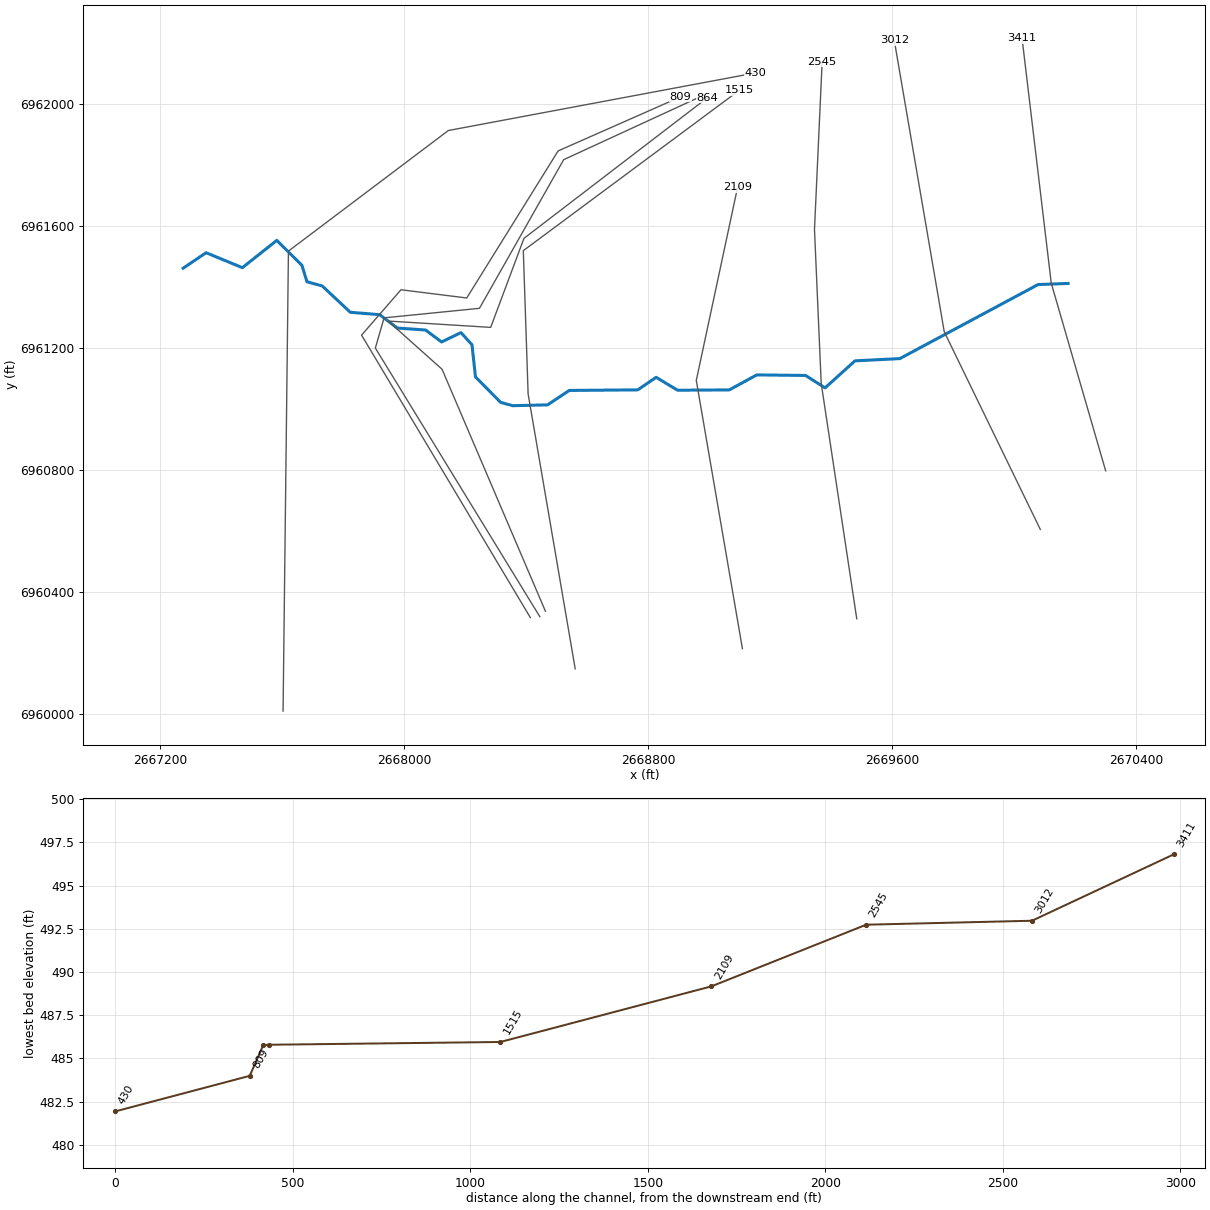
--- Walnut Creek Trib 2.prj (project) ---

Proj Title=Walnut Creek Trib 2 Base Level Engineering
Current Plan=p01
Default Exp/Contr=0.3,0.1
English Units
Geom File=g01
Flow File=f01
Plan File=p01
BEGIN DESCRIPTION:
Walnut Creek Trib 2
END DESCRIPTION:

--- Walnut Creek Trib 2.p01 (plan) ---

Plan Title=Multiple Run
Short Identifier=Multiple
Geom File=g01
Flow File=f01
Subcritical Flow
K Sum by GR= 0
Std Step Tol= 0.01
Critical Tol= 0.01
Num of Std Step Trials= 20
Max Error Tol= 0.3
Flow Tol Ratio= 0.001
Split Flow NTrial= 30
Split Flow Tol= 0.02
Split Flow Ratio= 0.02
Log Output Level= 0
Friction Slope Method= 1
Unsteady Friction Slope Method= 2
Unsteady Bridges Friction Slope Method= 1
Parabolic Critical Depth
Global Vel Dist=  1 , 1 , 1
Global Log Level= 0
CheckData=True
Encroach Param= -1, 0, 0, 0
BEGIN DESCRIPTION:
Multiple Run
END DESCRIPTION:

--- Walnut Creek Trib 2.f01 (steady flow) ---

Flow Title=Multiple
Number of Profiles=7
Profile Names=10-year,25-year,50-year,1pct_min,100-year,1pct_plu,500-year
River Rch & RM= Walnut Creek Tri,Reach-1,3411
     519     691     828     493     985    1965    1389
River Rch & RM= Walnut Creek Tri,Reach-1,2109
     565     756     909     543    1083    2160    1535
River Rch & RM= Walnut Creek Tri,Reach-1,809
     600     806     973     583    1163    2321    1662
Boundary for River Rch & Prof#=Walnut Creek Tri,Reach-1,1
Up Type=0
Dn Type=3
Dn Slope=0.005
Boundary for River Rch & Prof#=Walnut Creek Tri,Reach-1,2
Up Type=0
Dn Type=3
Dn Slope=0.005
Boundary for River Rch & Prof#=Walnut Creek Tri,Reach-1,3
Up Type=0
Dn Type=3
Dn Slope=0.005
Boundary for River Rch & Prof#=Walnut Creek Tri,Reach-1,4
Up Type=0
Dn Type=3
Dn Slope=0.005
Boundary for River Rch & Prof#=Walnut Creek Tri,Reach-1,5
Up Type=0
Dn Type=3
Dn Slope=0.005
Boundary for River Rch & Prof#=Walnut Creek Tri,Reach-1,6
Up Type=0
Dn Type=3
Dn Slope=0.005
Boundary for River Rch & Prof#=Walnut Creek Tri,Reach-1,7
Up Type=0
Dn Type=3
Dn Slope=0.005

--- Walnut Creek Trib 2.g01 (geometry) ---

Geom Title=Existing Conditions

River Reach=Walnut Creek Tri,Reach-1
Reach XY= 30
      2670176.00      6961411.00      2670077.50      6961407.37
      2669624.44      6961164.76      2669477.47      6961157.43
      2669379.41      6961068.81      2669315.57      6961109.61
      2669155.85      6961111.36      2669065.49      6961062.22
      2668895.99      6961061.18      2668826.00      6961103.44
      2668765.56      6961062.38      2668541.22      6961060.48
      2668470.06      6961013.25      2668355.83      6961010.53
      2668316.18      6961021.46      2668233.86      6961104.81
      2668222.39      6961209.97      2668186.37      6961249.92
      2668122.79      6961219.29      2668070.11      6961258.46
      2667977.60      6961264.85      2667920.02      6961308.64
      2667823.58      6961316.54      2667731.74      6961402.70
      2667681.62      6961416.62      2667665.11      6961470.46
      2667582.69      6961552.04      2667469.97      6961462.64
      2667351.06      6961511.60      2667276.00      6961461.00

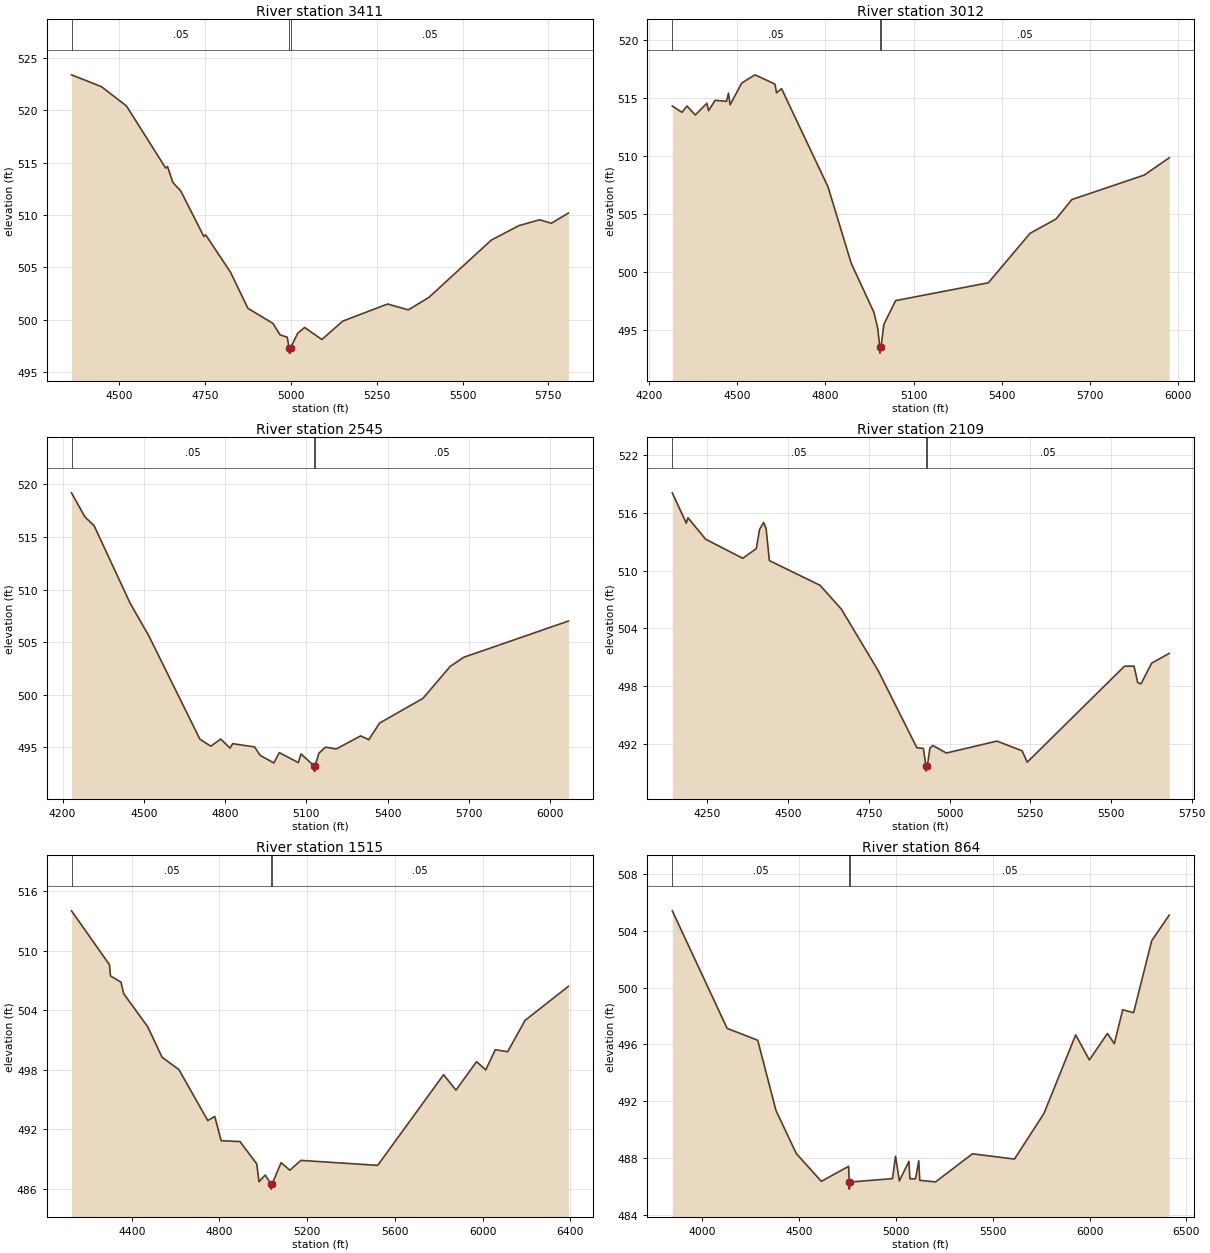
Type RM Length L Ch R = 1,3411,399,399,399
BEGIN DESCRIPTION:
Walnut Creek Trib 2 4.0
END DESCRIPTION:
XS GIS Cut Line= 3
      2670298.95      6960797.24      2670120.71      6961411.70
      2670024.99      6962214.32
#Sta/Elev= 30
  4360.2  523.38  4447.4  522.25  4520.3  520.41  4634.8  514.47  4640.0  514.63
  4655.7  513.10  4678.8  512.28  4745.9  507.95  4751.1  508.10  4823.5  504.54
  4874.3  501.09  4947.2  499.65  4968.1  498.55  4988.9  498.33  4994.5  497.31
  4994.8  496.81  4998.3  496.81  4998.5  497.31  5019.4  498.71  5039.6  499.26
  5089.9  498.11  5150.4  499.86  5281.3  501.50  5341.7  500.94  5402.1  502.14
  5583.4  507.60  5664.0  508.98  5724.4  509.54  5758.6  509.21  5808.3  510.18
#Mann=3,-1,0
  4360.2    0.05       0  4994.5    0.03       0  4998.5    0.05       0
Bank Sta=4994.5,4998.5
Exp/Cntr=0.3,0.1

Type RM Length L Ch R = 1,3012,467,467,467
BEGIN DESCRIPTION:
Walnut Creek Trib 2 3.0
END DESCRIPTION:
XS GIS Cut Line= 3
      2670084.82      6960605.13      2669770.06      6961252.57
      2669606.33      6962207.03
#Sta/Elev= 30
  4280.1  514.32  4313.1  513.78  4330.1  514.32  4358.2  513.55  4397.7  514.56
  4403.3  513.92  4425.8  514.82  4464.5  514.73  4471.0  515.44  4476.5  514.43
  4516.1  516.31  4561.2  517.02  4628.8  516.22  4634.4  515.47  4651.4  515.82
  4809.2  507.34  4888.1  500.73  4964.9  496.51  4978.3  495.10  4985.1  493.47
  4985.4  492.97  4989.1  493.47  4998.9  495.46  5039.0  497.51  5354.0  499.05
  5495.6  503.32  5583.9  504.56  5637.6  506.24  5883.9  508.36  5968.4  509.85
#Mann=3,-1,0
  4280.1    0.05       0  4985.1    0.03       0  4989.1    0.05       0
Bank Sta=4985.1,4989.1
Exp/Cntr=0.3,0.1

Type RM Length L Ch R = 1,2545,436,436,436
BEGIN DESCRIPTION:
Mapping XS fa143cd5
END DESCRIPTION:
XS GIS Cut Line= 4
      2669483.35      6960312.30      2669366.83      6961083.79
      2669344.79      6961587.64      2669369.92      6962137.39
#Sta/Elev= 30
  4233.0  519.20  4282.3  516.92  4316.7  516.06  4449.4  508.71  4518.2  505.62
  4707.0  495.78  4747.5  495.11  4783.7  495.79  4818.3  494.93  4828.4  495.35
  4909.3  495.04  4929.5  494.24  4980.1  493.52  5000.3  494.50  5070.5  493.55
  5080.5  494.38  5128.6  493.24  5128.8  492.74  5132.3  492.74  5132.6  493.24
  5146.2  494.43  5170.6  495.02  5210.6  494.85  5300.7  496.09  5330.8  495.73
  5370.7  497.31  5530.9  499.66  5631.1  502.69  5681.1  503.56  6067.9  507.01
#Mann=3,-1,0
  4233.0    0.05       0  5128.6    0.04       0  5132.6    0.05       0
Bank Sta=5128.6,5132.6
Exp/Cntr=0.3,0.1

Type RM Length L Ch R = 1,2109,594,594,594
BEGIN DESCRIPTION:
Walnut Creek Trib 2 2.0
END DESCRIPTION:
XS GIS Cut Line= 3
      2669108.62      6960214.63      2668957.46      6961093.24
      2669092.89      6961726.39
#Sta/Elev= 30
  4141.4  518.08  4184.8  514.93  4189.9  515.49  4244.8  513.26  4359.6  511.28
  4401.5  512.28  4411.7  514.28  4424.6  515.00  4432.0  514.34  4442.1  511.04
  4599.3  508.47  4665.4  505.98  4779.1  499.61  4898.9  491.60  4919.0  491.53
  4927.2  489.67  4927.4  489.17  4931.2  489.67  4939.3  491.57  4948.7  491.83
  4990.1  491.05  5146.9  492.29  5224.9  491.28  5240.7  490.10  5541.9  500.07
  5571.6  500.08  5582.8  498.37  5593.1  498.23  5626.2  500.39  5680.4  501.40
#Mann=3,-1,0
  4141.4    0.05       0  4927.2    0.04       0  4931.2    0.05       0
Bank Sta=4927.2,4931.2
Exp/Cntr=0.3,0.1

Type RM Length L Ch R = 1,1515,651,651,651
BEGIN DESCRIPTION:
Mapping XS 309b6b24
END DESCRIPTION:
XS GIS Cut Line= 4
      2668560.68      6960148.52      2668406.37      6961049.15
      2668390.62      6961518.36      2669099.15      6962044.25
#Sta/Elev= 30
  4125.4  514.04  4298.2  508.61  4303.3  507.47  4351.1  506.84  4363.3  505.68
  4472.9  502.34  4538.4  499.26  4614.9  498.02  4746.8  492.87  4778.6  493.29
  4807.7  490.84  4893.6  490.75  4970.0  488.50  4980.2  486.70  5008.6  487.37
  5035.6  486.45  5035.8  485.95  5039.6  486.45  5081.0  488.62  5121.1  487.86
  5171.1  488.85  5521.5  488.35  5821.9  497.50  5878.3  495.94  5972.2  498.82
  6013.9  497.98  6057.7  500.02  6114.0  499.82  6193.3  502.98  6391.0  506.42
#Mann=3,-1,0
  4125.4    0.05       0  5035.6    0.04       0  5039.6    0.05       0
Bank Sta=5035.6,5039.6
Exp/Cntr=0.3,0.1

Type RM Length L Ch R = 1,864,17,17,17
BEGIN DESCRIPTION:
Mapping XS b4c10be2
END DESCRIPTION:
XS GIS Cut Line= 6
      2668463.05      6960337.28      2668124.30      6961129.89
      2667947.41      6961287.84      2668283.72      6961267.04
      2668392.72      6961558.67      2668994.32      6962019.64
#Sta/Elev= 30
  3845.0  505.42  4128.2  497.13  4286.1  496.29  4380.5  491.33  4485.8  488.29
  4614.7  486.34  4755.4  487.40  4758.7  486.29  4758.9  485.79  4762.7  486.29
  4981.9  486.53  4997.8  488.11  5017.4  486.37  5066.8  487.75  5071.9  486.52
  5101.2  486.52  5117.6  487.79  5122.7  486.41  5204.2  486.30  5395.0  488.28
  5611.7  487.91  5763.8  491.12  5927.9  496.67  5998.5  494.90  6091.9  496.77
  6127.3  496.05  6170.8  498.44  6227.0  498.24  6320.4  503.31  6410.7  505.12
#Mann=3,-1,0
  3845.0    0.05       0  4758.7    0.04       0  4762.7    0.05       0
Bank Sta=4758.7,4762.7
Exp/Cntr=0.3,0.1

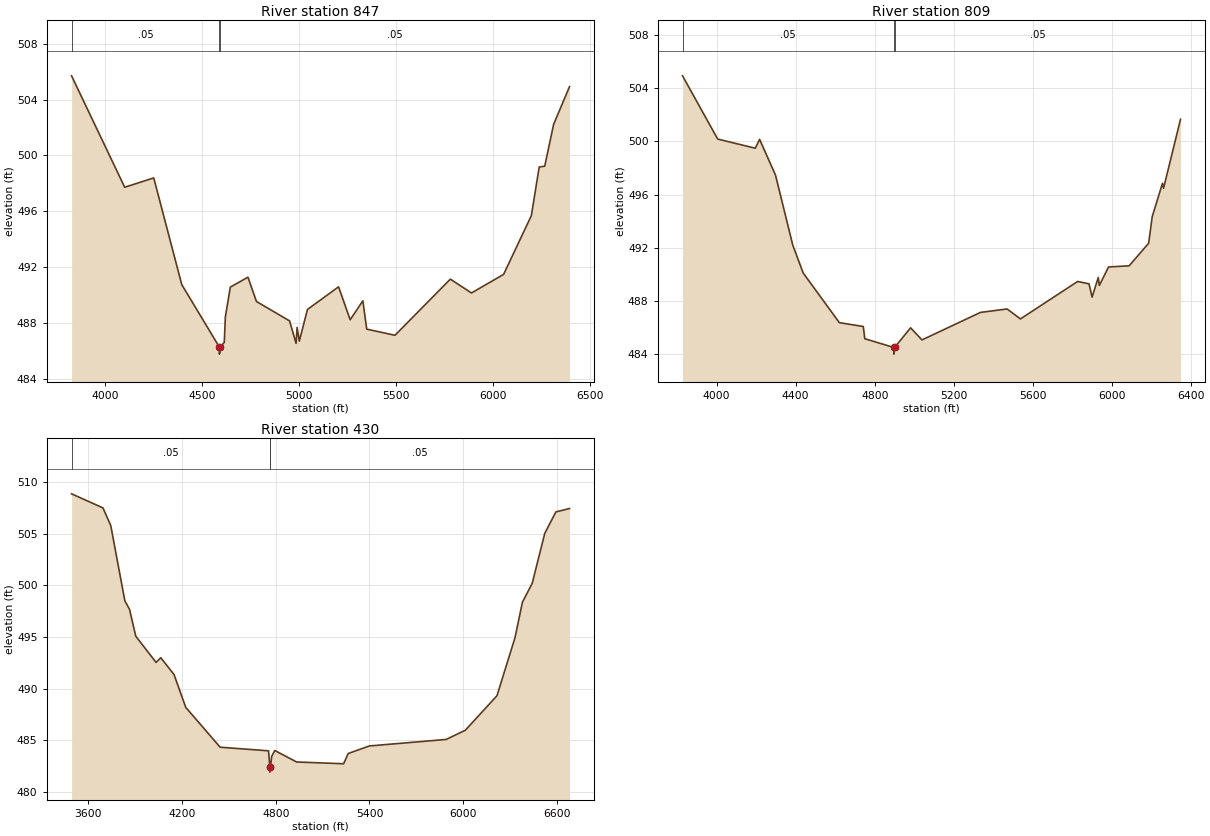
Type RM Length L Ch R = 1,847,38,38,38
BEGIN DESCRIPTION:
Mapping XS c4d58e80
END DESCRIPTION:
XS GIS Cut Line= 6
      2668444.79      6960319.12      2667905.74      6961199.30
      2667934.39      6961298.26      2668246.89      6961329.51
      2668522.93      6961816.49      2668986.43      6962030.01
#Sta/Elev= 30
  3826.9  505.70  4101.0  497.72  4250.9  498.39  4395.4  490.75  4589.6  486.27
  4589.9  485.77  4593.6  486.27  4614.8  486.61  4620.3  488.43  4646.0  490.57
  4737.0  491.28  4780.8  489.54  4951.6  488.15  4985.2  486.54  4990.4  487.68
  5001.8  486.70  5044.0  488.97  5204.5  490.59  5264.3  488.23  5329.7  489.59
  5349.8  487.56  5495.5  487.12  5781.1  491.14  5890.2  490.15  6055.9  491.48
  6199.1  495.69  6239.6  499.17  6268.0  499.23  6313.9  502.22  6396.1  504.93
#Mann=3,-1,0
  3826.9    0.05       0  4589.6    0.04       0  4593.6    0.05       0
Bank Sta=4589.6,4593.6
Exp/Cntr=0.3,0.1

Type RM Length L Ch R = 1,809,379,379,379
BEGIN DESCRIPTION:
Mapping XS 0dbb20ce
END DESCRIPTION:
XS GIS Cut Line= 6
      2668413.55      6960316.49      2667860.63      6961241.65
      2667989.75      6961390.31      2668205.22      6961363.36
      2668504.70      6961845.13      2668905.77      6962022.23
#Sta/Elev= 30
  3827.7  504.94  4005.5  500.18  4195.9  499.49  4217.5  500.16  4298.2  497.46
  4385.3  492.20  4438.0  490.10  4621.0  486.36  4742.0  486.07  4749.8  485.15
  4896.5  484.49  4896.7  483.99  4900.5  484.49  4981.4  485.97  5039.0  485.06
  5334.9  487.13  5469.8  487.39  5537.1  486.64  5826.4  489.46  5884.2  489.28
  5899.6  488.28  5930.8  489.76  5936.3  489.16  5982.9  490.55  6087.1  490.64
  6185.8  492.34  6203.6  494.33  6255.7  496.85  6261.2  496.48  6346.9  501.67
#Mann=3,-1,0
  3827.7    0.05       0  4896.5    0.04       0  4900.5    0.05       0
Bank Sta=4896.5,4900.5
Exp/Cntr=0.3,0.1

Type RM Length L Ch R = 1,430,0,0,0
BEGIN DESCRIPTION:
Walnut Creek Trib 2 1.0
END DESCRIPTION:
XS GIS Cut Line= 4
      2667603.36      6960009.95      2667620.92      6961516.95
      2668145.00      6961912.00      2669151.86      6962100.78
#Sta/Elev= 30
  3492.9  508.84  3694.0  507.48  3744.0  505.76  3834.0  498.50  3864.0  497.67
  3904.0  495.07  4034.0  492.54  4064.0  492.99  4148.8  491.37  4224.0  488.19
  4444.0  484.34  4754.0  483.99  4762.0  482.43  4762.3  481.93  4766.0  482.43
  4774.0  483.46  4794.0  484.02  4934.0  482.91  5234.5  482.74  5263.7  483.73
  5399.0  484.46  5890.7  485.09  6013.4  485.98  6216.2  489.32  6331.5  494.93
  6379.0  498.36  6441.8  500.19  6522.1  505.02  6593.3  507.09  6680.7  507.42
#Mann=3,-1,0
  3492.9    0.05       0  4762.0    0.04       0  4766.0    0.05       0
Bank Sta=4762,4766
Exp/Cntr=0.3,0.1

Chan Stop Cuts=-1