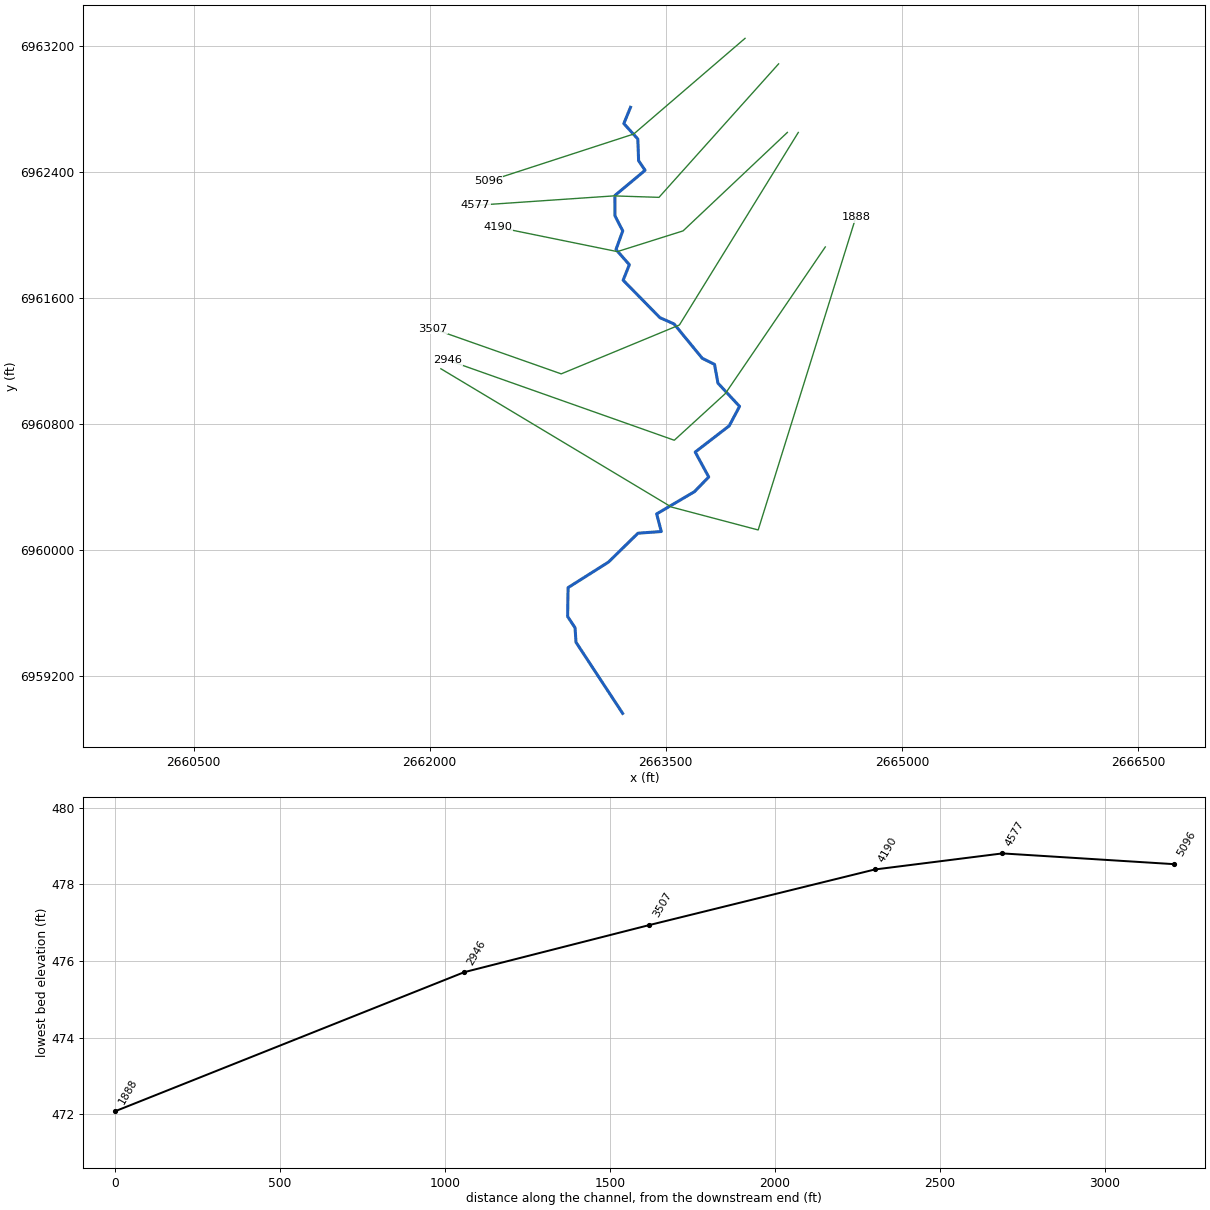
--- Walnut Creek Trib 3.prj (project) ---

Proj Title=Walnut Creek Trib 3 Base Level Engineering
Current Plan=p01
Default Exp/Contr=0.3,0.1
English Units
Geom File=g01
Flow File=f01
Plan File=p01
BEGIN DESCRIPTION:
Walnut Creek Trib 3
END DESCRIPTION:

--- Walnut Creek Trib 3.p01 (plan) ---

Plan Title=Multiple Run
Short Identifier=Multiple
Geom File=g01
Flow File=f01
Subcritical Flow
K Sum by GR= 0
Std Step Tol= 0.01
Critical Tol= 0.01
Num of Std Step Trials= 20
Max Error Tol= 0.3
Flow Tol Ratio= 0.001
Split Flow NTrial= 30
Split Flow Tol= 0.02
Split Flow Ratio= 0.02
Log Output Level= 0
Friction Slope Method= 1
Unsteady Friction Slope Method= 2
Unsteady Bridges Friction Slope Method= 1
Parabolic Critical Depth
Global Vel Dist=  1 , 1 , 1
Global Log Level= 0
CheckData=True
Encroach Param= -1, 0, 0, 0
BEGIN DESCRIPTION:
Multiple Run
END DESCRIPTION:

--- Walnut Creek Trib 3.f01 (steady flow) ---

Flow Title=Multiple
Number of Profiles=7
Profile Names=10-year,25-year,50-year,1pct_min,100-year,1pct_plu,500-year
River Rch & RM= Walnut Creek Tri,Reach-1,5096
     449     589     699     412     823    1642    1138
River Rch & RM= Walnut Creek Tri,Reach-1,3507
     690     929    1122     672    1341    2676    1915
Boundary for River Rch & Prof#=Walnut Creek Tri,Reach-1,1
Up Type=0
Dn Type=3
Dn Slope=0.005
Boundary for River Rch & Prof#=Walnut Creek Tri,Reach-1,2
Up Type=0
Dn Type=3
Dn Slope=0.005
Boundary for River Rch & Prof#=Walnut Creek Tri,Reach-1,3
Up Type=0
Dn Type=3
Dn Slope=0.005
Boundary for River Rch & Prof#=Walnut Creek Tri,Reach-1,4
Up Type=0
Dn Type=3
Dn Slope=0.005
Boundary for River Rch & Prof#=Walnut Creek Tri,Reach-1,5
Up Type=0
Dn Type=3
Dn Slope=0.005
Boundary for River Rch & Prof#=Walnut Creek Tri,Reach-1,6
Up Type=0
Dn Type=3
Dn Slope=0.005
Boundary for River Rch & Prof#=Walnut Creek Tri,Reach-1,7
Up Type=0
Dn Type=3
Dn Slope=0.005

--- Walnut Creek Trib 3.g01 (geometry) ---

Geom Title=Existing Conditions

River Reach=Walnut Creek Tri,Reach-1
Reach XY= 30
      2663276.00      6962811.00      2663233.60      6962707.62
      2663322.43      6962609.53      2663327.40      6962471.44
      2663368.69      6962410.89      2663176.97      6962250.71
      2663177.21      6962121.51      2663226.69      6962026.06
      2663183.83      6961907.58      2663268.63      6961811.09
      2663229.16      6961712.65      2663462.79      6961474.63
      2663552.82      6961434.70      2663731.65      6961216.64
      2663809.62      6961178.10      2663831.53      6961058.58
      2663968.72      6960911.09      2663903.02      6960787.49
      2663686.95      6960621.02      2663772.91      6960462.64
      2663682.07      6960369.15      2663442.15      6960228.07
      2663471.37      6960116.19      2663323.56      6960105.53
      2663135.68      6959921.78      2662879.45      6959759.75
      2662876.52      6959576.22      2662923.64      6959505.02
      2662929.83      6959412.58      2663226.00      6958961.00

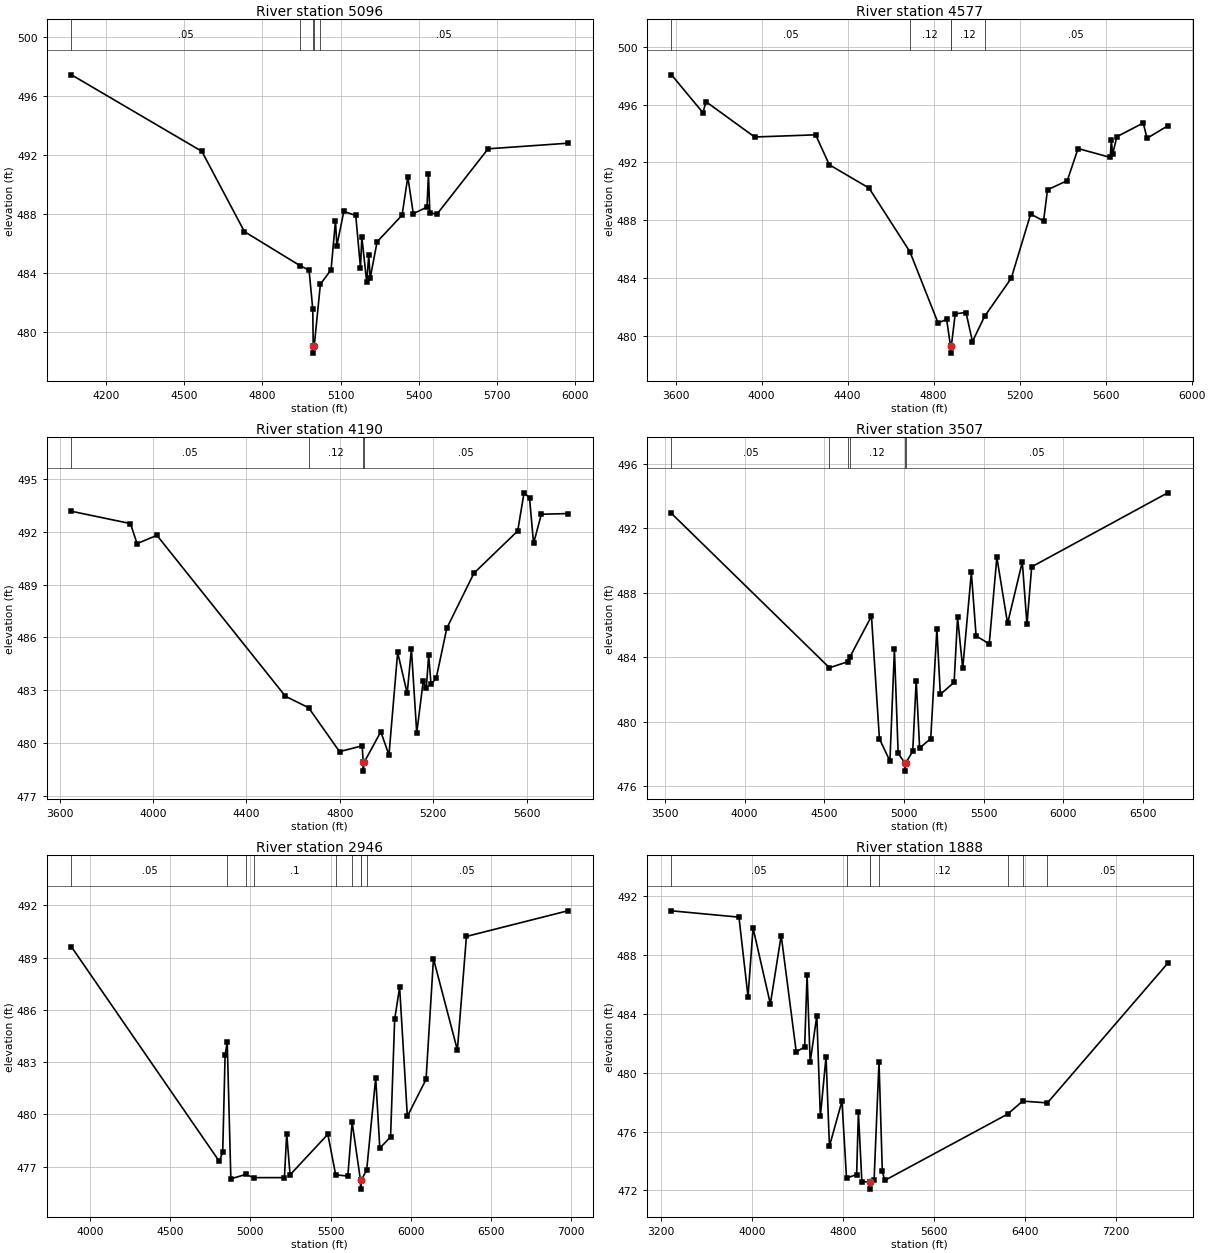
Type RM Length L Ch R = 1,5096,519,519,519
BEGIN DESCRIPTION:
Walnut Creek Trib 3 3.0
END DESCRIPTION:
XS GIS Cut Line= 3
      2664003.60      6963249.08      2663296.33      6962641.20
      2662372.62      6962340.91
#Sta/Elev= 30
  4067.4  497.45  4567.5  492.25  4731.0  486.79  4945.0  484.47  4979.0  484.17
  4993.2  481.52  4994.9  479.03  4995.2  478.53  4998.9  479.03  5022.4  483.21
  5063.4  484.20  5080.4  487.53  5085.6  485.84  5112.3  488.16  5158.1  487.89
  5176.2  484.35  5181.5  486.41  5200.1  483.36  5208.1  485.20  5213.4  483.62
  5240.1  486.10  5335.9  487.91  5357.9  490.52  5378.9  488.01  5431.5  488.46
  5437.0  490.70  5442.3  488.09  5469.0  487.96  5665.9  492.42  5971.3  492.80
#Mann=5,-1,0
  4067.4    0.05       0  4945.0    0.12       0  4994.9    0.07       0
  4998.9    0.12       0  5022.4    0.05       0
Bank Sta=4994.9,4998.9
Exp/Cntr=0.3,0.1

Type RM Length L Ch R = 1,4577,387,387,387
BEGIN DESCRIPTION:
Mapping XS 08abf209
END DESCRIPTION:
XS GIS Cut Line= 4
      2664216.74      6963086.91      2663456.85      6962238.98
      2663169.57      6962248.24      2662290.06      6962188.07
#Sta/Elev= 30
  3581.0  498.06  3727.2  495.44  3741.4  496.20  3967.9  493.76  4251.3  493.91
  4314.8  491.84  4499.5  490.23  4689.8  485.82  4820.5  480.90  4860.5  481.14
  4878.5  479.31  4878.8  478.81  4882.5  479.31  4900.5  481.53  4950.6  481.62
  4980.6  479.61  5036.9  481.35  5161.0  483.99  5251.2  488.43  5311.3  487.96
  5329.6  490.11  5421.6  490.74  5471.7  492.96  5621.4  492.35  5626.5  493.58
  5632.1  492.55  5652.1  493.78  5774.9  494.73  5792.4  493.67  5888.6  494.53
#Mann=5,-1,0
  3581.0    0.05       0  4689.8    0.12       0  4878.5    0.07       0
  4882.5    0.12       0  5036.9    0.05       0
Bank Sta=4878.5,4882.5
Exp/Cntr=0.3,0.1

Type RM Length L Ch R = 1,4190,683,683,683
BEGIN DESCRIPTION:
Walnut Creek Trib 3 2.0
END DESCRIPTION:
XS GIS Cut Line= 4
      2664272.32      6962651.33      2663609.75      6962025.84
      2663192.36      6961894.29      2662432.86      6962049.00
#Sta/Elev= 30
  3651.2  493.18  3903.6  492.48  3931.9  491.34  4016.9  491.81  4567.0  482.65
  4666.2  482.00  4798.5  479.50  4895.5  479.83  4899.8  478.89  4900.1  478.39
  4903.8  478.89  4975.2  480.63  5010.1  479.31  5047.3  485.15  5088.1  482.82
  5106.1  485.34  5129.0  480.56  5156.7  483.51  5169.8  483.10  5180.0  484.98
  5190.2  483.33  5212.3  483.68  5257.8  486.53  5373.9  489.66  5561.2  492.06
  5588.2  494.23  5611.7  493.95  5629.0  491.35  5662.3  493.01  5775.1  493.05
#Mann=4,-1,0
  3651.2    0.05       0  4666.2    0.12       0  4899.8    0.03       0
  4903.8    0.05       0
Bank Sta=4899.8,4903.8
Exp/Cntr=0.3,0.1

Type RM Length L Ch R = 1,3507,561,561,561
BEGIN DESCRIPTION:
Mapping XS e1293bd0
END DESCRIPTION:
XS GIS Cut Line= 4
      2664341.85      6962651.37      2663586.58      6961428.12
      2662835.96      6961117.67      2662020.78      6961404.84
#Sta/Elev= 30
  3541.5  492.92  4532.8  483.35  4649.5  483.73  4660.2  484.00  4796.5  486.55
  4846.5  478.94  4912.4  477.57  4940.5  484.50  4964.0  478.04  5006.8  477.44
  5007.1  476.94  5010.8  477.44  5055.5  478.17  5077.2  482.56  5098.8  478.37
  5168.5  478.96  5207.0  485.75  5228.7  481.70  5315.2  482.45  5336.9  486.48
  5369.3  483.31  5423.4  489.26  5453.1  485.33  5535.6  484.83  5583.4  490.20
  5650.7  486.10  5743.1  489.91  5772.4  486.04  5802.0  489.61  6655.7  494.20
#Mann=6,-1,0
  3541.5    0.05       0  4532.8    0.12       0  4649.5    0.05       0
  4660.2    0.12       0  5006.8    0.07       0  5010.8    0.05       0
Bank Sta=5006.8,5010.8
Exp/Cntr=0.3,0.1

Type RM Length L Ch R = 1,2946,1058,1058,1058
BEGIN DESCRIPTION:
Mapping XS c06de805
END DESCRIPTION:
XS GIS Cut Line= 4
      2664513.29      6961923.91      2663878.49      6960992.57
      2663554.15      6960696.03      2662113.11      6961205.72
#Sta/Elev= 30
  3884.2  489.62  4806.5  477.30  4827.5  477.84  4842.4  483.39  4855.7  484.17
  4878.3  476.30  4969.7  476.55  5022.3  476.37  5212.4  476.37  5226.6  478.90
  5247.6  476.53  5483.3  478.86  5532.2  476.53  5607.9  476.46  5634.7  479.55
  5687.0  476.21  5687.3  475.71  5691.0  476.21  5725.6  476.82  5781.8  482.09
  5807.4  478.06  5874.5  478.71  5900.1  485.46  5931.0  487.30  5979.2  479.89
  6095.8  482.01  6142.0  488.94  6291.2  483.70  6347.7  490.22  6979.3  491.69
#Mann=9,-1,0
  3884.2    0.05       0  4855.7     0.1       0  4969.7    0.05       0
  5022.3     0.1       0  5532.2    0.05       0  5634.7     0.1       0
  5687.0    0.03       0  5691.0     0.1       0  5725.6    0.05       0
Bank Sta=5687,5691
Exp/Cntr=0.3,0.1

Type RM Length L Ch R = 1,1888,0,0,0
BEGIN DESCRIPTION:
Walnut Creek Trib 3 1.0
END DESCRIPTION:
XS GIS Cut Line= 4
      2662071.46      6961150.10      2663535.64      6960271.80
      2664087.00      6960126.11      2664707.90      6962113.91
#Sta/Elev= 30
  3292.6  491.02  3885.3  490.59  3965.0  485.18  4009.2  489.85  4161.3  484.68
  4256.5  489.34  4388.7  481.42  4462.6  481.76  4484.0  486.67  4511.2  480.72
  4569.5  483.88  4600.6  477.03  4650.6  481.09  4680.3  475.00  4790.5  478.07
  4830.5  472.83  4919.4  473.07  4934.9  477.31  4965.4  472.58  5032.6  472.58
  5032.8  472.08  5036.6  472.58  5072.8  472.71  5115.9  480.74  5145.2  473.31
  5165.9  472.67  6247.1  477.19  6377.8  478.07  6596.1  477.95  7652.8  487.45
#Mann=8,-1,0
  3292.6    0.05       0  4830.5     0.1       0  5032.6    0.07       0
  5036.6     0.1       0  5115.9    0.12       0  6247.1    0.05       0
  6377.8    0.12       0  6596.1    0.05       0
Bank Sta=5032.6,5036.6
Exp/Cntr=0.3,0.1

Chan Stop Cuts=-1