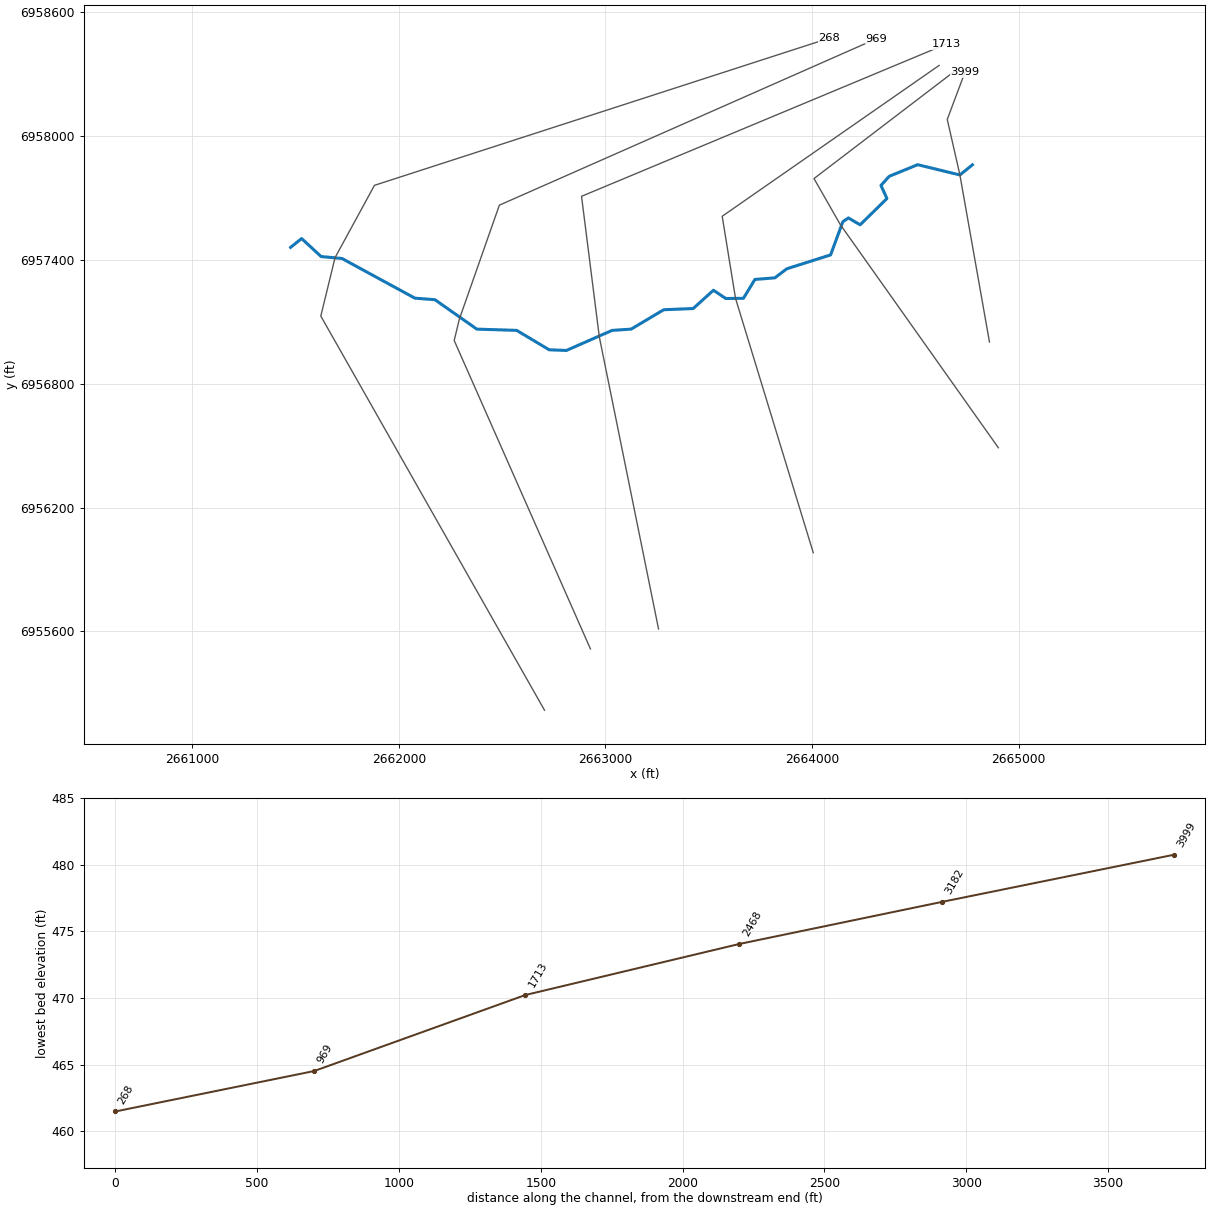
--- Walnut Creek Trib 4.prj (project) ---

Proj Title=Walnut Creek Trib 4 Base Level Engineering
Current Plan=p01
Default Exp/Contr=0.3,0.1
English Units
Geom File=g01
Flow File=f01
Plan File=p01
BEGIN DESCRIPTION:
Walnut Creek Trib 4
END DESCRIPTION:

--- Walnut Creek Trib 4.p01 (plan) ---

Plan Title=Multiple Run
Short Identifier=Multiple
Geom File=g01
Flow File=f01
Subcritical Flow
K Sum by GR= 0
Std Step Tol= 0.01
Critical Tol= 0.01
Num of Std Step Trials= 20
Max Error Tol= 0.3
Flow Tol Ratio= 0.001
Split Flow NTrial= 30
Split Flow Tol= 0.02
Split Flow Ratio= 0.02
Log Output Level= 0
Friction Slope Method= 1
Unsteady Friction Slope Method= 2
Unsteady Bridges Friction Slope Method= 1
Parabolic Critical Depth
Global Vel Dist=  1 , 1 , 1
Global Log Level= 0
CheckData=True
Encroach Param= -1, 0, 0, 0
BEGIN DESCRIPTION:
Multiple Run
END DESCRIPTION:

--- Walnut Creek Trib 4.f01 (steady flow) ---

Flow Title=Multiple
Number of Profiles=7
Profile Names=10-year,25-year,50-year,1pct_min,100-year,1pct_plu,500-year
River Rch & RM= Walnut Creek Tri,Reach-1,3999
     489     646     772     458     914    1823    1278
Boundary for River Rch & Prof#=Walnut Creek Tri,Reach-1,1
Up Type=0
Dn Type=3
Dn Slope=0.005
Boundary for River Rch & Prof#=Walnut Creek Tri,Reach-1,2
Up Type=0
Dn Type=3
Dn Slope=0.005
Boundary for River Rch & Prof#=Walnut Creek Tri,Reach-1,3
Up Type=0
Dn Type=3
Dn Slope=0.005
Boundary for River Rch & Prof#=Walnut Creek Tri,Reach-1,4
Up Type=0
Dn Type=3
Dn Slope=0.005
Boundary for River Rch & Prof#=Walnut Creek Tri,Reach-1,5
Up Type=0
Dn Type=3
Dn Slope=0.005
Boundary for River Rch & Prof#=Walnut Creek Tri,Reach-1,6
Up Type=0
Dn Type=3
Dn Slope=0.005
Boundary for River Rch & Prof#=Walnut Creek Tri,Reach-1,7
Up Type=0
Dn Type=3
Dn Slope=0.005

--- Walnut Creek Trib 4.g01 (geometry) ---

Geom Title=Existing Conditions

River Reach=Walnut Creek Tri,Reach-1
Reach XY= 30
      2664776.00      6957861.00      2664715.54      6957811.82
      2664510.94      6957861.72      2664373.16      6957805.17
      2664333.47      6957761.21      2664362.35      6957697.67
      2664232.66      6957570.31      2664175.76      6957603.54
      2664148.88      6957585.41      2664089.63      6957424.45
      2663877.60      6957357.15      2663820.02      6957313.36
      2663723.34      6957305.54      2663667.65      6957214.01
      2663581.98      6957213.33      2663522.59      6957253.19
      2663424.53      6957164.57      2663281.93      6957158.75
      2663124.42      6957064.83      2663031.97      6957058.65
      2662810.73      6956961.38      2662727.58      6956964.67
      2662570.07      6957058.76      2662377.55      6957064.75
      2662174.50      6957207.38      2662077.59      6957214.83
      2661724.41      6957407.17      2661623.57      6957416.54
      2661529.33      6957503.73      2661476.00      6957461.00

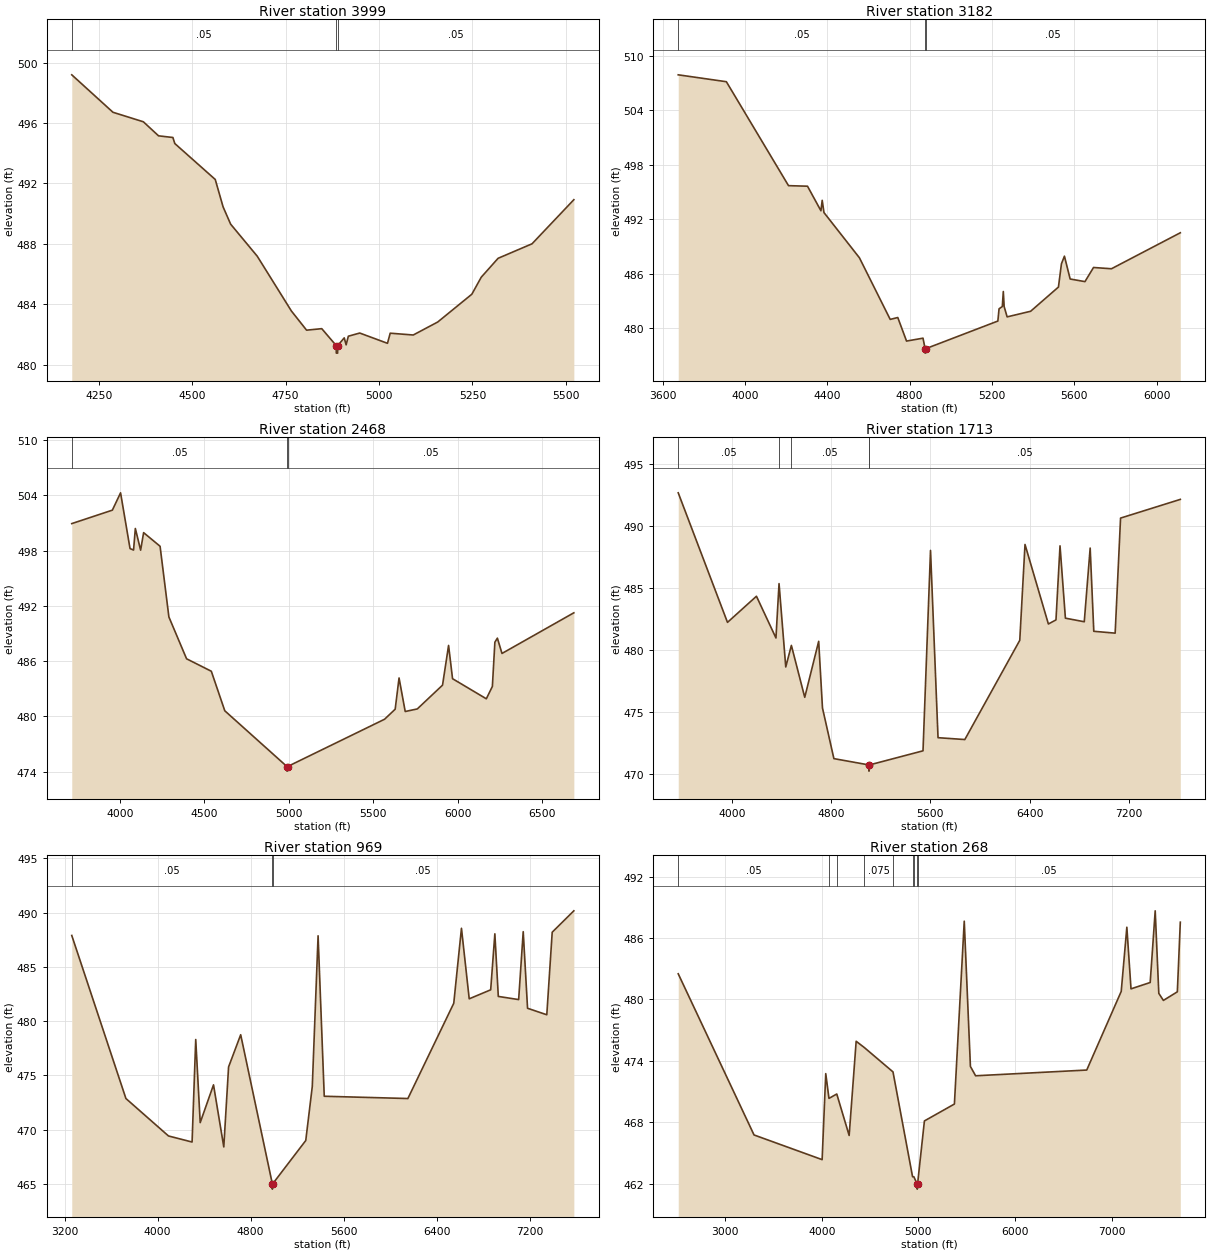
Type RM Length L Ch R = 1,3999,817,817,817
BEGIN DESCRIPTION:
Walnut Creek Trib 4 5.0
END DESCRIPTION:
XS GIS Cut Line= 4
      2664858.59      6957002.46      2664715.54      6957811.82
      2664654.33      6958081.10      2664740.33      6958310.45
#Sta/Elev= 30
  4178.1  499.19  4288.3  496.71  4369.6  496.08  4410.2  495.15  4448.6  495.04
  4453.7  494.64  4561.9  492.26  4582.8  490.45  4603.1  489.30  4674.2  487.18
  4765.6  483.55  4806.2  482.28  4846.8  482.38  4885.5  481.26  4885.7  480.76
  4889.2  480.76  4889.5  481.26  4906.9  481.77  4912.0  481.31  4917.9  481.88
  4948.4  482.09  5022.6  481.41  5029.9  482.08  5091.5  481.96  5157.0  482.82
  5248.2  484.66  5273.5  485.79  5318.5  487.04  5409.3  488.00  5521.1  490.92
#Mann=3,-1,0
  4178.1    0.05       0  4885.5    0.04       0  4889.5    0.05       0
Bank Sta=4885.5,4889.5
Exp/Cntr=0.3,0.1

Type RM Length L Ch R = 1,3182,714,714,714
BEGIN DESCRIPTION:
Walnut Creek Trib 4 4.0
END DESCRIPTION:
XS GIS Cut Line= 4
      2664901.59      6956490.06      2664136.52      6957571.49
      2664009.31      6957794.43      2664691.31      6958315.75
#Sta/Elev= 30
  3675.3  507.93  3909.2  507.17  4211.2  495.70  4303.5  495.64  4368.7  492.93
  4374.9  494.08  4383.5  492.73  4555.8  487.74  4705.4  480.94  4742.2  481.15
  4784.7  478.55  4864.7  478.87  4875.0  477.72  4875.3  477.22  4879.0  477.72
  5228.5  480.76  5234.3  482.11  5250.1  482.36  5255.0  484.02  5259.0  482.36
  5273.6  481.22  5387.8  481.84  5522.9  484.51  5537.5  487.08  5552.0  487.92
  5579.8  485.40  5651.7  485.11  5693.4  486.67  5780.5  486.53  6115.1  490.50
#Mann=3,-1,0
  3675.3    0.05       0  4875.0   0.035       0  4879.0    0.05       0
Bank Sta=4875,4879
Exp/Cntr=0.3,0.1

Type RM Length L Ch R = 1,2468,755,755,755
BEGIN DESCRIPTION:
Mapping XS 610687e9
END DESCRIPTION:
XS GIS Cut Line= 4
      2664005.73      6955981.21      2663629.47      6957213.92
      2663564.97      6957611.68      2664614.93      6958342.71
#Sta/Elev= 30
  3715.2  500.92  3955.5  502.38  4004.0  504.26  4060.0  498.21  4080.9  498.05
  4091.4  500.39  4122.7  498.04  4140.4  499.94  4237.8  498.46  4290.0  490.79
  4394.6  486.25  4541.0  484.90  4620.7  480.61  4988.5  474.56  4988.8  474.06
  4992.5  474.56  5566.3  479.69  5629.1  480.78  5652.0  484.17  5688.5  480.53
  5760.1  480.81  5909.3  483.39  5945.1  487.70  5968.6  484.09  6168.5  481.91
  6204.3  483.25  6219.1  488.05  6233.9  488.49  6261.2  486.83  6686.4  491.24
#Mann=3,-1,0
  3715.2    0.05       0  4988.5   0.035       0  4992.5    0.05       0
Bank Sta=4988.5,4992.5
Exp/Cntr=0.3,0.1

Type RM Length L Ch R = 1,1713,744,744,744
BEGIN DESCRIPTION:
Mapping XS 2e620fdb
END DESCRIPTION:
XS GIS Cut Line= 4
      2663256.79      6955612.18      2662970.12      6957027.58
      2662884.12      6957708.43      2664650.05      6958446.32
#Sta/Elev= 30
  3569.4  492.69  3966.1  482.23  4199.4  484.34  4356.6  480.97  4381.4  485.36
  4435.5  478.63  4480.8  480.37  4588.5  476.18  4700.7  480.70  4731.3  475.32
  4823.2  471.23  5105.7  470.72  5106.0  470.22  5109.7  470.72  5541.1  471.86
  5601.6  488.04  5662.1  472.92  5877.9  472.77  6320.5  480.78  6362.7  488.52
  6551.0  482.10  6612.2  482.43  6644.7  488.41  6688.1  482.57  6840.0  482.28
  6887.6  488.23  6916.8  481.51  7088.9  481.36  7132.4  490.65  7613.7  492.16
#Mann=5,-1,0
  3569.4    0.05       0  4381.4   0.075       0  4480.8    0.05       0
  5105.7    0.03       0  5109.7    0.05       0
Bank Sta=5105.7,5109.7
Exp/Cntr=0.3,0.1

Type RM Length L Ch R = 1,969,701,701,701
BEGIN DESCRIPTION:
Mapping XS 99880270
END DESCRIPTION:
XS GIS Cut Line= 5
      2662927.14      6955515.34      2662267.77      6957009.66
      2662292.86      6957113.58      2662486.36      6957665.43
      2664310.29      6958471.68
#Sta/Elev= 30
  3261.7  487.89  3727.6  472.86  4093.7  469.41  4296.7  468.85  4328.1  478.30
  4366.6  470.64  4481.1  474.12  4569.5  468.40  4610.7  475.77  4714.9  478.74
  4986.9  465.01  4987.2  464.51  4990.9  465.01  5274.7  468.99  5330.9  473.98
  5380.7  487.86  5433.7  473.07  6153.2  472.86  6547.9  481.64  6614.1  488.55
  6680.8  482.05  6865.5  482.88  6901.4  488.04  6931.1  482.27  7106.1  481.98
  7145.4  488.24  7182.6  481.18  7348.2  480.58  7394.8  488.19  7580.9  490.16
#Mann=3,-1,0
  3261.7    0.05       0  4986.9   0.035       0  4990.9    0.05       0
Bank Sta=4986.9,4990.9
Exp/Cntr=0.3,0.1

Type RM Length L Ch R = 1,268,0,0,0
BEGIN DESCRIPTION:
Walnut Creek Trib 4 1.0
END DESCRIPTION:
XS GIS Cut Line= 5
      2662704.94      6955217.97      2661622.15      6957128.08
      2661691.06      6957411.14      2661881.81      6957761.60
      2664082.76      6958474.70
#Sta/Elev= 30
  2513.0  482.50  3298.1  466.76  4003.2  464.35  4040.7  472.75  4074.0  470.33
  4154.8  470.76  4283.1  466.71  4355.7  475.91  4439.9  475.30  4737.1  472.92
  4939.8  462.68  4952.9  462.68  4987.6  461.97  4987.8  461.47  4991.6  461.97
  5062.5  468.13  5373.1  469.78  5475.0  487.64  5538.9  473.45  5592.6  472.54
  6743.6  473.10  7100.7  480.78  7158.9  487.05  7202.0  481.03  7400.7  481.65
  7452.6  488.65  7489.9  480.59  7537.3  479.90  7681.8  480.74  7712.6  487.54
#Mann=9,-1,0
  2513.0    0.05       0  4074.0   0.075       0  4154.8    0.05       0
  4439.9   0.075       0  4737.1    0.05       0  4939.8    0.12       0
  4952.9    0.05       0  4987.6   0.035       0  4991.6    0.05       0
Bank Sta=4987.6,4991.6
Exp/Cntr=0.3,0.1

Chan Stop Cuts=-1