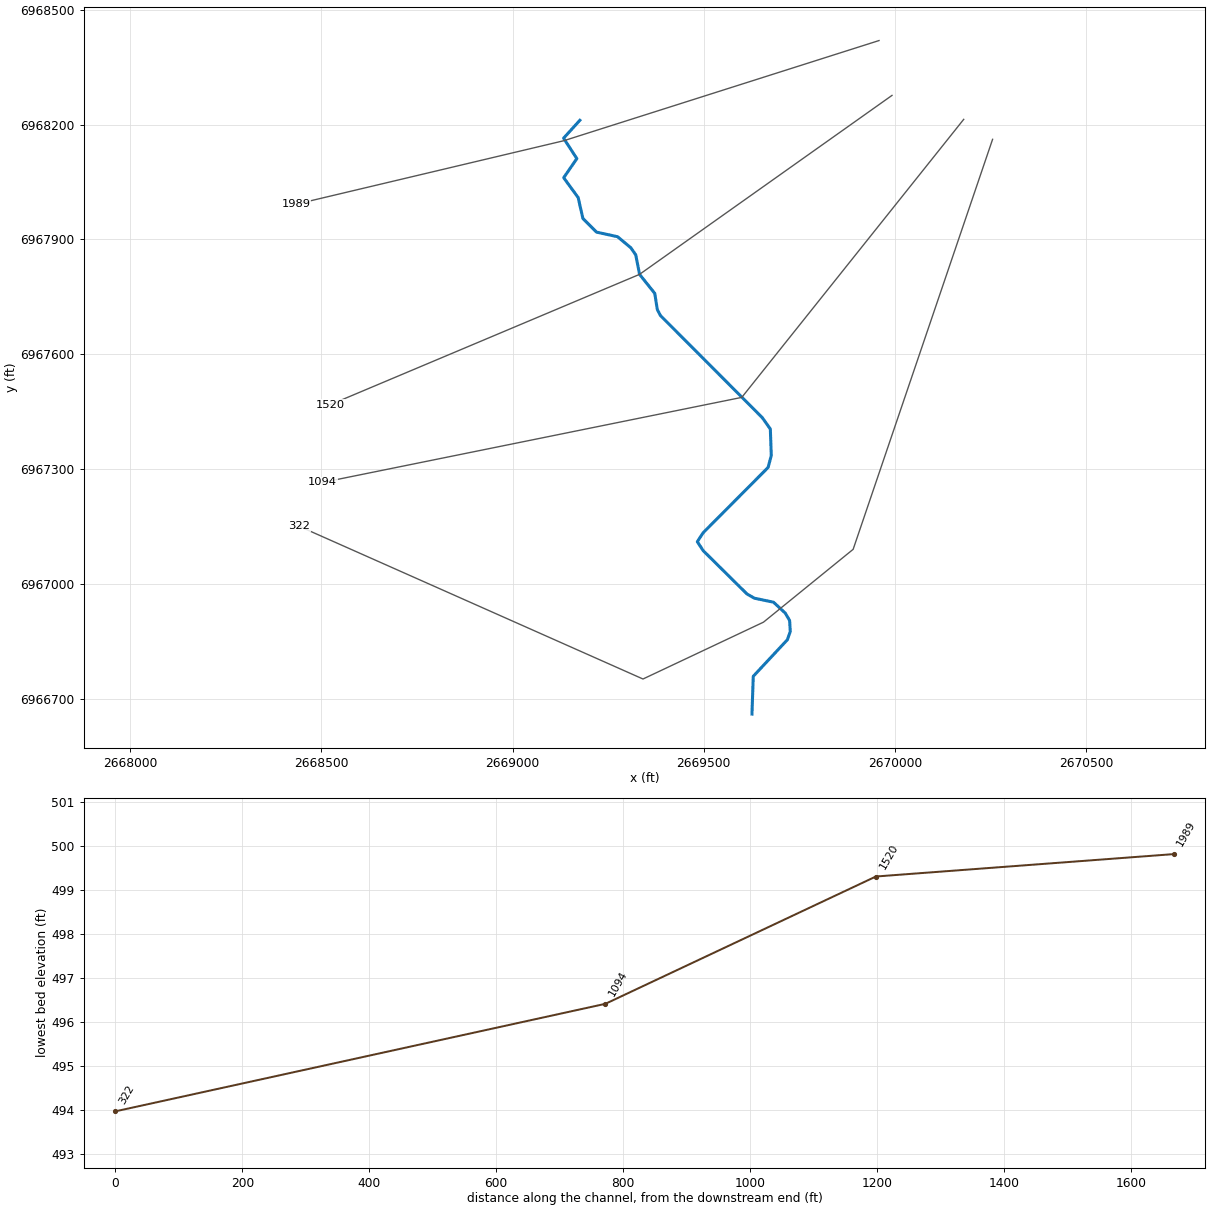
--- Walnut Creek Trib 5.prj (project) ---

Proj Title=Walnut Creek Trib 5 Base Level Engineering
Current Plan=p01
Default Exp/Contr=0.3,0.1
English Units
Geom File=g01
Flow File=f01
Plan File=p01
BEGIN DESCRIPTION:
Walnut Creek Trib 5
END DESCRIPTION:

--- Walnut Creek Trib 5.p01 (plan) ---

Plan Title=Multiple Run
Short Identifier=Multiple
Geom File=g01
Flow File=f01
Subcritical Flow
K Sum by GR= 0
Std Step Tol= 0.01
Critical Tol= 0.01
Num of Std Step Trials= 20
Max Error Tol= 0.3
Flow Tol Ratio= 0.001
Split Flow NTrial= 30
Split Flow Tol= 0.02
Split Flow Ratio= 0.02
Log Output Level= 0
Friction Slope Method= 1
Unsteady Friction Slope Method= 2
Unsteady Bridges Friction Slope Method= 1
Parabolic Critical Depth
Global Vel Dist=  1 , 1 , 1
Global Log Level= 0
CheckData=True
Encroach Param= -1, 0, 0, 0
BEGIN DESCRIPTION:
Multiple Run
END DESCRIPTION:

--- Walnut Creek Trib 5.f01 (steady flow) ---

Flow Title=Multiple
Number of Profiles=7
Profile Names=10-year,25-year,50-year,1pct_min,100-year,1pct_plu,500-year
River Rch & RM= Walnut Creek Tri,Reach-1,1989
     343     441     518     302     602    1202     814
Boundary for River Rch & Prof#=Walnut Creek Tri,Reach-1,1
Up Type=0
Dn Type=3
Dn Slope=0.005
Boundary for River Rch & Prof#=Walnut Creek Tri,Reach-1,2
Up Type=0
Dn Type=3
Dn Slope=0.005
Boundary for River Rch & Prof#=Walnut Creek Tri,Reach-1,3
Up Type=0
Dn Type=3
Dn Slope=0.005
Boundary for River Rch & Prof#=Walnut Creek Tri,Reach-1,4
Up Type=0
Dn Type=3
Dn Slope=0.005
Boundary for River Rch & Prof#=Walnut Creek Tri,Reach-1,5
Up Type=0
Dn Type=3
Dn Slope=0.005
Boundary for River Rch & Prof#=Walnut Creek Tri,Reach-1,6
Up Type=0
Dn Type=3
Dn Slope=0.005
Boundary for River Rch & Prof#=Walnut Creek Tri,Reach-1,7
Up Type=0
Dn Type=3
Dn Slope=0.005

--- Walnut Creek Trib 5.g01 (geometry) ---

Geom Title=Existing Conditions

River Reach=Walnut Creek Tri,Reach-1
Reach XY= 30
      2669176.00      6968211.00      2669133.50      6968164.33
      2669168.12      6968111.00      2669133.74      6968061.09
      2669171.55      6968009.32      2669184.00      6967954.67
      2669219.68      6967919.05      2669274.54      6967907.10
      2669309.51      6967878.05      2669322.14      6967859.58
      2669332.11      6967808.84      2669371.81      6967759.27
      2669378.50      6967717.04      2669386.76      6967701.32
      2669653.16      6967434.52      2669674.04      6967405.11
      2669676.51      6967335.96      2669668.24      6967304.83
      2669498.38      6967134.33      2669483.07      6967111.00
      2669498.38      6967087.66      2669612.80      6966974.64
      2669632.09      6966963.55      2669682.43      6966952.96
      2669713.04      6966924.56      2669724.50      6966905.13
      2669726.13      6966876.42      2669718.53      6966854.98
      2669629.40      6966759.59      2669626.00      6966661.00

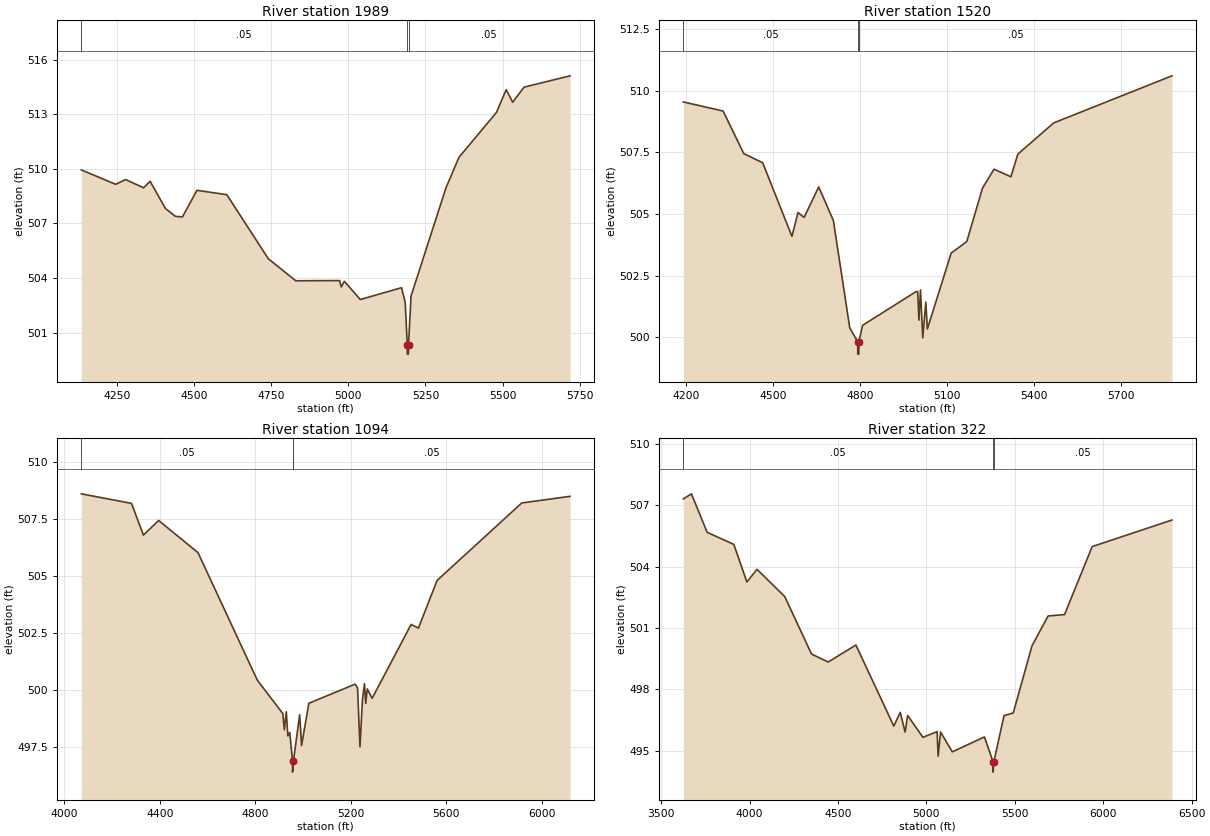
Type RM Length L Ch R = 1,1989,469,469,469
BEGIN DESCRIPTION:
Walnut Creek Trib 5 2.0
END DESCRIPTION:
XS GIS Cut Line= 3
      2669958.28      6968419.19      2669133.97      6968157.67
      2668434.81      6967992.10
#Sta/Elev= 30
  4135.2  509.94  4246.4  509.15  4278.6  509.41  4336.9  508.96  4357.9  509.32
  4407.7  507.82  4440.0  507.39  4462.8  507.36  4509.8  508.82  4606.6  508.58
  4740.9  505.06  4830.0  503.85  4972.0  503.86  4977.3  503.51  4987.4  503.82
  5039.0  502.82  5172.6  503.47  5184.4  502.67  5191.2  500.32  5191.4  499.82
  5194.9  499.82  5195.2  500.32  5203.4  503.01  5316.5  508.95  5358.6  510.63
  5480.2  513.10  5511.7  514.35  5532.7  513.66  5569.8  514.49  5718.5  515.11
#Mann=3,-1,0
  4135.2    0.05       0  5191.2    0.04       0  5195.2    0.05       0
Bank Sta=5191.2,5195.2
Exp/Cntr=0.3,0.1

Type RM Length L Ch R = 1,1520,426,426,426
BEGIN DESCRIPTION:
Walnut Creek Trib 5 3.0
END DESCRIPTION:
XS GIS Cut Line= 3
      2669992.13      6968275.97      2669332.11      6967808.84
      2668523.34      6967468.65
#Sta/Elev= 30
  4191.4  509.55  4328.7  509.18  4400.1  507.45  4465.3  507.08  4566.2  504.09
  4587.1  505.06  4608.1  504.86  4658.5  506.10  4709.0  504.74  4765.6  500.38
  4793.1  499.81  4793.4  499.31  4796.9  499.31  4797.1  499.81  4809.9  500.48
  4994.6  501.85  5000.0  501.85  5004.3  500.69  5009.7  501.92  5017.5  499.97
  5028.0  501.42  5033.4  500.33  5115.5  503.41  5169.4  503.88  5223.6  506.05
  5263.4  506.82  5321.7  506.51  5345.5  507.43  5469.6  508.70  5877.4  510.61
#Mann=3,-1,0
  4191.4    0.05       0  4793.1    0.03       0  4797.1    0.05       0
Bank Sta=4793.1,4797.1
Exp/Cntr=0.3,0.1

Type RM Length L Ch R = 1,1094,772,772,772
BEGIN DESCRIPTION:
Walnut Creek Trib 5 4.0
END DESCRIPTION:
XS GIS Cut Line= 3
      2670179.62      6968213.46      2669599.39      6967487.69
      2668503.64      6967265.76
#Sta/Elev= 30
  4070.8  508.62  4281.0  508.20  4330.6  506.81  4394.7  507.45  4559.5  506.04
  4807.7  500.45  4914.9  498.98  4921.3  498.27  4929.4  499.06  4935.8  498.00
  4943.8  498.15  4955.4  496.91  4955.6  496.41  4959.4  496.91  4985.4  498.93
  4993.4  497.58  5023.9  499.43  5217.7  500.27  5227.9  500.11  5238.1  497.52
  5248.3  499.57  5256.9  500.29  5262.0  499.42  5268.7  500.06  5289.1  499.65
  5452.4  502.89  5483.0  502.73  5561.1  504.82  5916.0  508.22  6118.0  508.51
#Mann=3,-1,0
  4070.8    0.05       0  4955.4    0.04       0  4959.4    0.05       0
Bank Sta=4955.4,4959.4
Exp/Cntr=0.3,0.1

Type RM Length L Ch R = 1,322,0,0,0
BEGIN DESCRIPTION:
Walnut Creek Trib 5 1.0
END DESCRIPTION:
XS GIS Cut Line= 5
      2670255.13      6968161.34      2669890.56      6967091.06
      2669656.18      6966900.96      2669341.08      6966752.52
      2668442.63      6967150.96
#Sta/Elev= 30
  3625.2  507.31  3671.1  507.56  3759.8  505.68  3910.8  505.09  3984.7  503.25
  4042.0  503.87  4198.8  502.54  4350.3  499.73  4444.3  499.34  4601.1  500.17
  4815.6  496.21  4851.9  496.88  4879.5  495.92  4893.9  496.73  4980.2  495.66
  5060.5  495.94  5066.3  494.74  5080.0  495.92  5146.3  494.95  5328.0  495.68
  5377.1  494.46  5377.4  493.96  5381.1  494.46  5439.0  496.72  5491.1  496.85
  5597.5  500.14  5688.2  501.59  5781.3  501.66  5937.3  504.98  6388.8  506.28
#Mann=3,-1,0
  3625.2    0.05       0  5377.1    0.03       0  5381.1    0.05       0
Bank Sta=5377.1,5381.1
Exp/Cntr=0.3,0.1

Chan Stop Cuts=-1